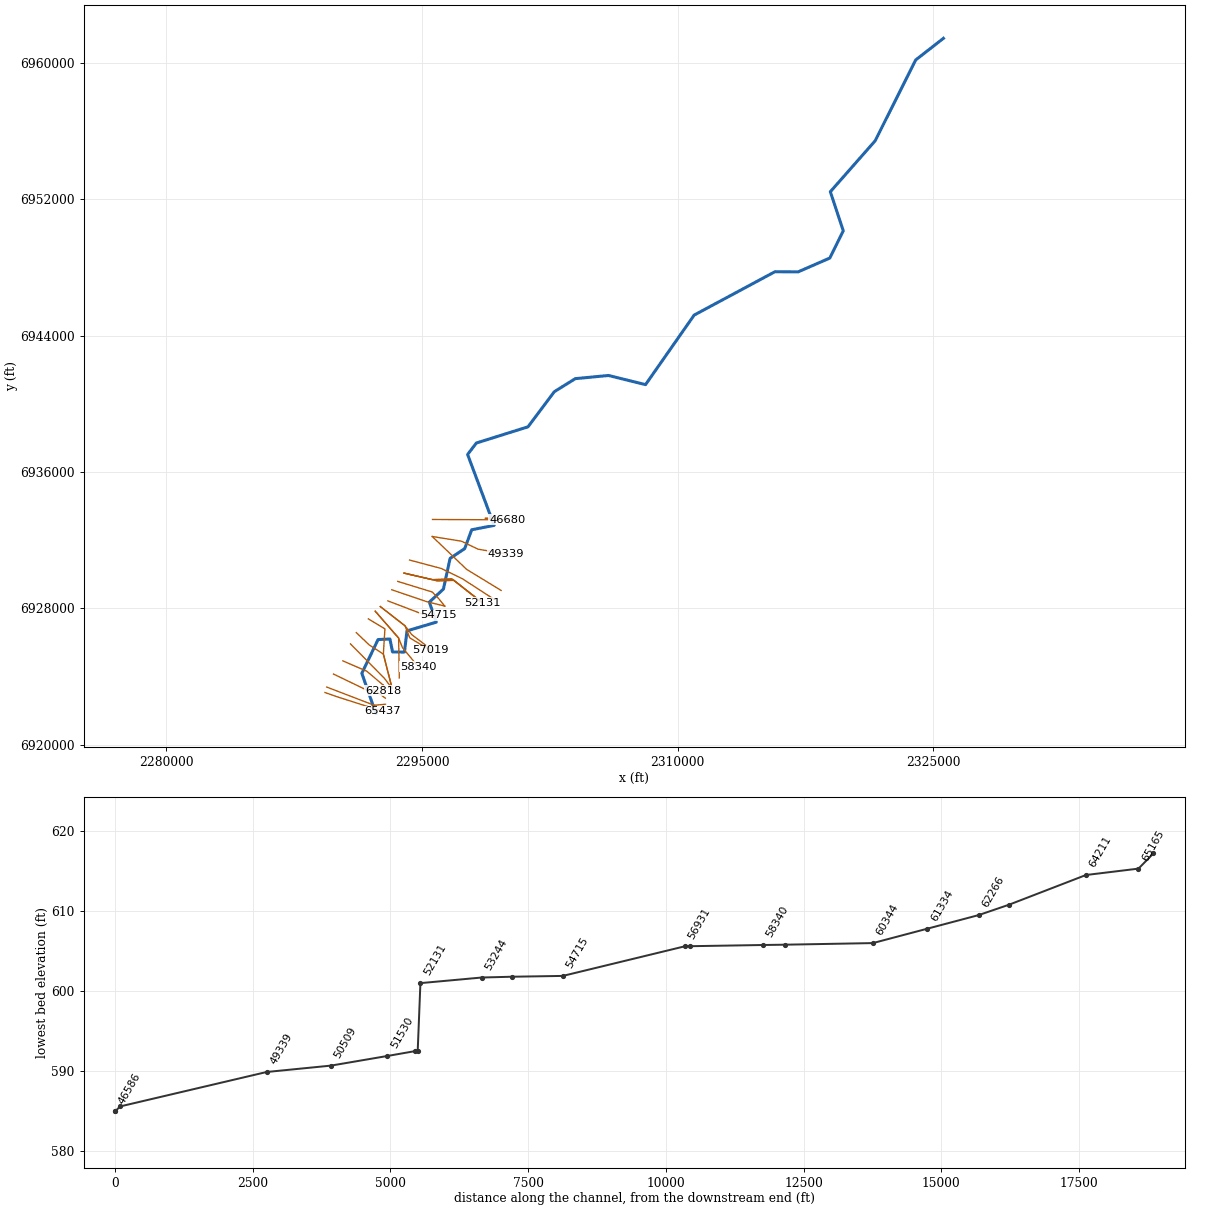
HEC-RAS study CDC_Consolidated_Model.prj: Upper Trinity CDC Consolidated Model

--- CDC_Consolidated_Model.f13 (steady flow) ---

Flow Title=CDC: 0.2% AEP, SPF [WF/EF/TRMS]
Program Version=6.10
BEGIN FILE DESCRIPTION:
CDC: 0.2% ACE (Annual Exceedance Probability) and SPF peak flows
END FILE DESCRIPTION:
Number of Profiles= 2
Profile Names=0.2% AEP,SPF
River Rch & RM=Elm Fork,ef6             ,153328
       1       1
River Rch & RM=Elm Fork,ef4             ,147489
   57000   66600
River Rch & RM=Elm Fork,ef4             ,138514
    9500   10600
River Rch & RM=Elm Fork,ef3             ,125658
   57000   66600
River Rch & RM=Elm Fork,ef3             ,118732
   57000   66600
River Rch & RM=Elm Fork,ef3             ,110572
   57000   66600
River Rch & RM=Elm Fork,ef3             ,102686
   71500   87000
River Rch & RM=Elm Fork,PGBT split west ,97178
   57900   66500
River Rch & RM=Elm Fork,PGBT split east ,98000
    8100   15500
River Rch & RM=Elm Fork,ef3 ds          ,87645
   66000   82000
River Rch & RM=Elm Fork,ef3 ds          ,83530
   66000   82500
River Rch & RM=Elm Fork,ef3 ds          ,80579
   68000   85000
River Rch & RM=Elm Fork,ef3 ds          ,72713
   68500   85500
River Rch & RM=Elm Fork,ef3 ds          ,71682
   68500   85500
River Rch & RM=Elm Fork,ef3 ds          ,69701
   68500   86000
River Rch & RM=Elm Fork,ef3 ds          ,67364
   68500   87500
River Rch & RM=Elm Fork,ef3 ds          ,60810
   68500   88500
River Rch & RM=Elm Fork,ef3 ds          ,57195
   67000   88000
River Rch & RM=Elm Fork,ef3 ds          ,53292
   68500   92000
River Rch & RM=Elm Fork L-Spill,efl             ,20757
   57000   66600
River Rch & RM=Elm Fork Split2,efs2            ,139902
       1       1
River Rch & RM=Elm Fork Split2,efs2            ,132950
   47500   56000
River Rch & RM=Main Stem,ms              ,148136
  210000  296000
River Rch & RM=Main Stem,ms              ,138046
  209000  295000
River Rch & RM=Main Stem,ms              ,91392
  209000  295000
River Rch & RM=Main Stem,ms              ,82361
  202000  284000
River Rch & RM=Main Stem,ms              ,77843
  212000  302000
River Rch & RM=Main Stem,ms              ,68027
  212000  302000
River Rch & RM=Main Stem,ms              ,51060
  211000  300000
River Rch & RM=West Fork,wf              ,206218
  123000  154000
River Rch & RM=West Fork,wf              ,184495
  142000  182000
River Rch & RM=West Fork,wf              ,162435
  138000  179000
River Rch & RM=West Fork,wf              ,140885
  180000  217000
River Rch & RM=West Fork,wf              ,133413
  176000  215000
River Rch & RM=West Fork,wf              ,123744
  179000  220000
River Rch & RM=West Fork,wf              ,116053
  178000  219000
River Rch & RM=West Fork,wf              ,96240
  175000  217000
River Rch & RM=West Fork,wf              ,70006
  173000  221000
River Rch & RM=West Fork,wf              ,53730
  174000  223000
River Rch & RM=West Fork,wf              ,46184
  172000  223000
River Rch & RM=West Fork,wf              ,41697
  168000  217000
River Rch & RM=West Fork,wf              ,37015
  108000  242000
River Rch & RM=West Fork,wf              ,18823
  168000  228000
River Rch & RM=West Fork,wf              ,11911
  170000  234000
River Rch & RM=West Fork,wf              ,8149
  169000  234000
Boundary for River Rch & Prof#=Elm Fork,ef6             , 1
Up Type= 3
Up Slope=0.001
Dn Type= 0
Boundary for River Rch & Prof#=Elm Fork,ef6             , 2
Up Type= 3
Up Slope=0.001
Dn Type= 0
Boundary for River Rch & Prof#=Elm Fork,ef4             , 1
Up Type= 0
Dn Type= 0
Boundary for River Rch & Prof#=Elm Fork,ef4             , 2
Up Type= 0
Dn Type= 0
Boundary for River Rch & Prof#=Elm Fork,ef3             , 1
Up Type= 0
Dn Type= 0
Boundary for River Rch & Prof#=Elm Fork,ef3             , 2
Up Type= 0
Dn Type= 0
Boundary for River Rch & Prof#=Elm Fork,PGBT split west , 1
Up Type= 0
Dn Type= 0
Boundary for River Rch & Prof#=Elm Fork,PGBT split west , 2
Up Type= 0
Dn Type= 0
Boundary for River Rch & Prof#=Elm Fork,PGBT split east , 1
Up Type= 0
Dn Type= 0
Boundary for River Rch & Prof#=Elm Fork,PGBT split east , 2
Up Type= 0
Dn Type= 0
Boundary for River Rch & Prof#=Elm Fork,ef3 ds          , 1
Up Type= 0
Dn Type= 0
Boundary for River Rch & Prof#=Elm Fork,ef3 ds          , 2
Up Type= 0
Dn Type= 0
Boundary for River Rch & Prof#=Elm Fork L-Spill,efl             , 1
Up Type= 3
Up Slope=0.0022
Dn Type= 0
Boundary for River Rch & Prof#=Elm Fork L-Spill,efl             , 2
Up Type= 3
Up Slope=0.0022
Dn Type= 0
Boundary for River Rch & Prof#=Elm Fork Split2,efs2            , 1
Up Type= 0
Dn Type= 0
Boundary for River Rch & Prof#=Elm Fork Split2,efs2            , 2
Up Type= 0
Dn Type= 0
Boundary for River Rch & Prof#=Main Stem,ms              , 1
Up Type= 0
Dn Type= 1
Dn Known WS=400.48
Boundary for River Rch & Prof#=Main Stem,ms              , 2
Up Type= 0
Dn Type= 1
Dn Known WS=404.02
Boundary for River Rch & Prof#=West Fork,wf              , 1
Up Type= 0
Dn Type= 0
Boundary for River Rch & Prof#=West Fork,wf              , 2
Up Type= 0
Dn Type= 0
DSS Import GetInterval= 0
DSS Import GetPeak= 0
DSS Import FillOption= 0

--- CDC_Consolidated_Model.g11 (geometry) ---

Geom Title=CDC: 50% to 0.2% AEP, SPF [WF/CF]
Program Version=6.10
BEGIN GEOM DESCRIPTION:
CDC: Geometry file for use with 50%, 20%, 10%, 4%, 2%, 1%, 0.2% AEP and SPF peak flows for the WF/CF
END GEOM DESCRIPTION:

Junct Name=wf-cf
Junct Desc=West Fork/Clear Fork confluence, 0 , 0 ,-1 ,0
Up River,Reach=Clear Fork      ,cf
Up River,Reach=West Fork       ,wf4
Dn River,Reach=West Fork       ,wf3
Junc L&A=608.8,
Junc L&A=670,

River Reach=Clear Fork      ,cf
Reach XY= 30
      2292288.59      6921831.412291466.294063426924183.98560091
      2292420.81      6926165.572293115.134634586926197.49979012
       2293269.8      6925436.762293970.410516916925430.68962115
      2294117.76       6926675.9      2295837.81      6927186.34
2295431.270763016928362.48285814 2296257.13710796929128.81411107
2296647.510189586930929.527057212297506.448960416931504.42009387
2297917.568629466932609.62635503      2299232.22      6932867.28
2297676.33418507 6937029.9338043      2298189.42      6937701.98
2301220.944649976938652.674418752302764.568217376940712.59373286
2303997.234395656941480.91846615      2305947.37      6941667.25
2308121.925069136941129.52494022      2310975.73      6945211.82
 2315719.54032636947758.310712762317079.314854566947749.76581876
2318938.651812746948560.02569258  2319730.099339  6950160.702548
  2318969.749911  6952453.650916  2321604.185503  6955447.933657
  2323980.952878  6960189.917956  2325608.947074   6961458.87796

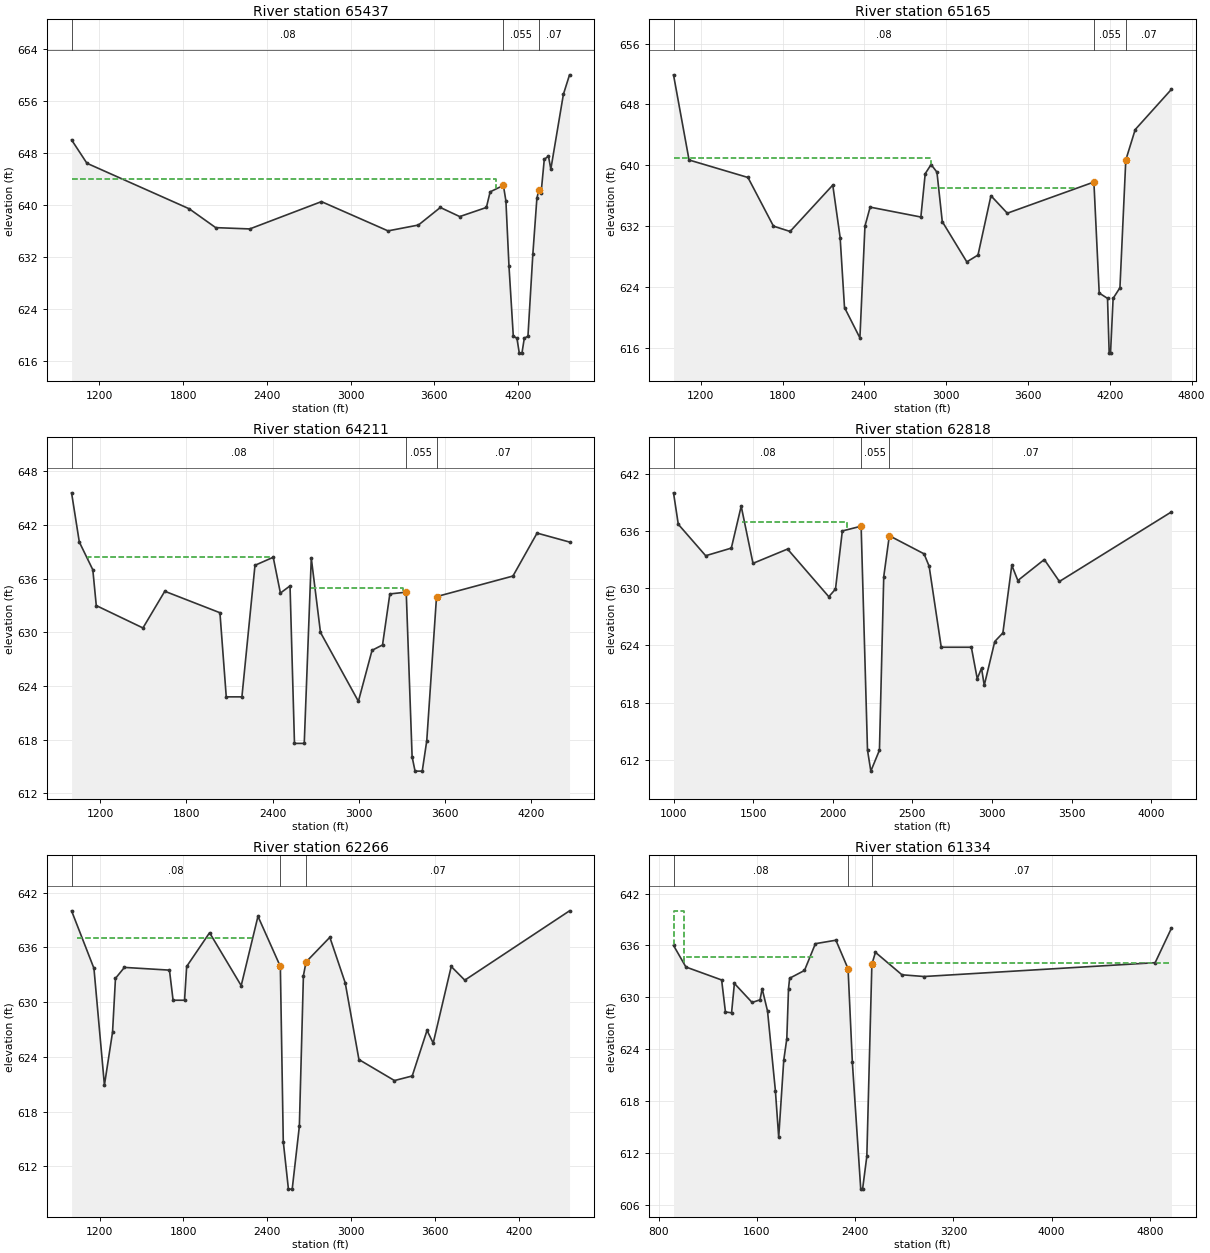
Type RM Length L Ch R = 1 ,65437   ,235.8,271.7,293.2
BEGIN DESCRIPTION:
This cross section corresponds to cross section 65616 of the non-georeferenced CDC model which was the source of this model.
Approx. 600 feet downstream from centerline of Benbrook
Dam.  Main channel within Benbrook Lake outlet works basin.  Benbrook Dam at sta 66206, river mile 12.54.
Channel data from 1975 USACE field survey.
END DESCRIPTION:
XS GIS Cut Line= 5
2289302.451151216923055.48400696   2290010.37999   6922808.27192
     2290779.761   6922562.03816   2291609.16911   6922297.63712
   2292697.71615   6921956.35204
#Sta/Elev= 30
    1000     650    1110   646.4    1843   639.4    2033   636.5    2277   636.3
    2791   640.5    3268     636    3486   636.9    3643   639.6    3782   638.2
    3973   639.6    4000     642    4095     643    4113   640.6    4135   630.6
    4166   619.8 4191.91   619.5 4208.91   617.2 4227.91   617.2 4244.91   619.5
    4271   619.8    4306   632.4    4335     641    4349   642.3    4365   641.8
    4388     647    4418   647.5    4435   645.5    4525     657    4569     660
#Mann= 3 ,0,0
    1000     .08       0    4095    .055       0    4349     .07       0
#XS Ineff= 2 , 0
            4044     644
Permanent Ineff=
       F       F
Bank Sta=4095,4349
XS Rating Curve= 0 ,0
Exp/Cntr=0.3,0.1

Type RM Length L Ch R = 1 ,65165   ,924.3,954.4,967.5
BEGIN DESCRIPTION:
This cross section corresponds to cross section 65344 of the non-georeferenced CDC model which was the source of this model.
Main channel is Benbrook Lake outlet works discharge
channel.  Old Clear Fork channel in LOB.  Pecan Valley Golf Course in LOB and ROB.
Channel data from 1975 USACE field survey.
END DESCRIPTION:
XS GIS Cut Line= 3
   2289405.28901   6923376.84001   2292198.44615   6922304.71912
   2292855.65612    6922369.6209
#Sta/Elev= 30
    1000   651.9    1114   640.7    1546   638.4    1733     632    1855   631.3
    2168   637.4    2222   630.5    2254   621.3    2367   617.3    2404     632
    2442   634.5    2814   633.2    2846   638.9    2889   640.1    2932   639.1
    2971   632.6    3151   627.3    3233   628.2    3328     636    3448   633.7
    4083   637.8    4122   623.2    4183   622.5    4195   615.3    4205   615.3
    4224   622.5    4274   623.9    4317   640.7    4386   644.7    4652     650
#Mann= 3 ,0,0
    1000     .08       0    4083    .055       0    4317     .07       0
#XS Ineff= 2 ,-1
    1000    2889     641    2889    3939     637
Permanent Ineff=
       F       F
Bank Sta=4083,4317
XS Rating Curve= 0 ,0
Exp/Cntr=0.3,0.1

Type RM Length L Ch R = 1 ,64211   ,1413.5,1392.8,1331.7
BEGIN DESCRIPTION:
This cross section corresponds to cross section 64380 of the non-georeferenced CDC model which was the source of this model.
Main channel is Benbrook Lake outlet works discharge
channel.  Old Clear Fork channel in LOB.  Pecan Valley Golf Course in LOB and ROB.
Channel data from 1975 USACE field survey.
END DESCRIPTION:
XS GIS Cut Line= 4
   2289805.88893   6924138.74006   2291888.51206   6923134.21812
   2292151.08995   6923248.88784   2292843.05903   6922725.25897
#Sta/Elev= 30
    1000   645.6    1054   640.1    1148     637    1172     633    1497   630.5
    1649   634.6    2033   632.2    2077   622.8    2186   622.8    2277   637.5
    2404   638.4    2454   634.4    2521   635.2    2552   617.6    2620   617.6
    2669   638.3    2733     630    2997   622.3    3092     628    3165   628.6
    3216   634.3    3330   634.5    3371   616.1  3391.5   614.5  3441.5   614.5
    3473   617.9    3541     634    4073   636.3    4241   641.1    4467   640.1
#Mann= 3 ,0,0
    1000     .08       0    3330    .055       0    3541     .07       0
#XS Ineff= 3 ,-1
  1112.4 2379.84  638.44 2405.08    2670   636.2    2670  3304.3     635
Permanent Ineff=
       F       F       F
Bank Sta=3330,3541
XS Rating Curve= 0 ,0
Exp/Cntr=0.3,0.1

Type RM Length L Ch R = 1 ,62818   ,564.3,551.8,538.6
BEGIN DESCRIPTION:
This cross section corresponds to cross section 62953 of the non-georeferenced CDC model which was the source of this model.
Approx. 300 feet downstream of Clear Fork/old Clear Fork
confluence.  Pecan Valley Golf Course in LOB and ROB.
Channel data from 1975 USACE field survey.
END DESCRIPTION:
XS GIS Cut Line= 5
   2290353.38291   6924913.24311   2291747.77809   6924311.60815
    2292745.2131   6923474.95399      2292737.38     6923479.203
     2292708.734     6923173.213
#Sta/Elev= 30
    1000     640    1030   636.7    1202   633.4    1363   634.2    1425   638.6
    1499   632.6    1716   634.1    1975   629.1    2017   629.9    2060     636
    2178   636.5    2218     613    2239   610.8    2293     613    2320   631.2
    2355   635.5    2573   633.6    2605   632.3    2681   623.8    2870   623.8
    2907   620.5    2934   621.6    2951   619.8    3017   624.4    3068   625.3
    3124   632.4    3162   630.8    3328     633    3423   630.7  4126.6     638
#Mann= 3 ,0,0
    1000     .08       0    2178    .055       0    2355     .07       0
#XS Ineff= 3 ,-1
 1013.29    1428     638    1428  2089.7 636.911    2431    4500  634.23
Permanent Ineff=
       F       F       F
Bank Sta=2178,2355
XS Rating Curve= 0 ,0
Exp/Cntr=0.3,0.1

Type RM Length L Ch R = 1 ,62266   ,911.3,932.5,937.1
BEGIN DESCRIPTION:
This cross section corresponds to cross section 62405 of the non-georeferenced CDC model which was the source of this model.
Benbrook Lake spillway channel in LOB, Pecan Valley
Golf Course in LOB and ROB.
Channel data from 1975 USACE field survey.
END DESCRIPTION:
XS GIS Cut Line= 3
   2290801.86397   6925909.86907   2292800.27992   6923879.75895
     2293230.432     6923313.582
#Sta/Elev= 30
    1000     640    1160   633.7    1235   620.9    1293   626.7    1314   632.6
    1378   633.8    1700   633.5    1726   630.2    1808   630.2    1823   633.9
    1987   637.6    2213   631.8    2333   639.4    2493   633.9    2514   614.7
 2550.81   609.5 2577.81   609.5    2629   616.4    2658   632.9    2677   634.4
    2847   637.1    2957   632.1    3055   623.7    3309   621.4    3436   621.9
    3542   626.9    3586   625.5    3715   633.9    3812   632.4    4561     640
#Mann= 3 ,0,0
    1000     .08       0    2493    .055       0    2677     .07       0
#XS Ineff= 2 ,-1
 1036.54 2292.36     637    2847    4500   634.1
Permanent Ineff=
       F       F
Bank Sta=2493,2677
XS Rating Curve= 0 ,0
Exp/Cntr=0.3,0.1

Type RM Length L Ch R = 1 ,61334   ,1037.3,989.6,927.1
BEGIN DESCRIPTION:
This cross section corresponds to cross section 61472 of the non-georeferenced CDC model which was the source of this model.
Approx. 650 feet upstream of Clear Fork/Benbrook Lake
spillway channel confluence.  Benbrook Lake spillway channel in LOB.  Pecan Valley Golf Course in LOB and ROB.
Channel data from 1975 USACE field survey.
END DESCRIPTION:
XS GIS Cut Line= 5
 2291138.8580606 6926573.7674949   2291196.79297   6926518.59915
   2291893.24794   6925855.40198   2292731.49659   6925311.56547
     2293229.455     6923357.887
#Sta/Elev= 30
     920     636    1021   633.5    1312     632    1343   628.3    1393   628.2
    1416   631.6    1560   629.4    1625   629.7    1642     631    1686   628.4
    1750   619.2    1777   613.8    1818   622.7    1843   625.2    1857     631
    1866   632.2    1987   633.1    2076   636.2    2243   636.6    2342   633.3
    2377   622.5 2445.35   607.8 2460.35   607.8    2495   611.6    2536   633.8
    2565   635.2    2781   632.6    2961   632.4    4844     634    4977     638
#Mann= 3 ,0,0
     920     .08       0    2342    .055       0    2536     .07       0
#XS Ineff= 3 ,-1
     920 1004.43     640 1004.43    2076   634.6    2667    4977     634
Permanent Ineff=
       F       F       F
Bank Sta=2342,2536
XS Rating Curve= 0 ,0
Exp/Cntr=0.3,0.1

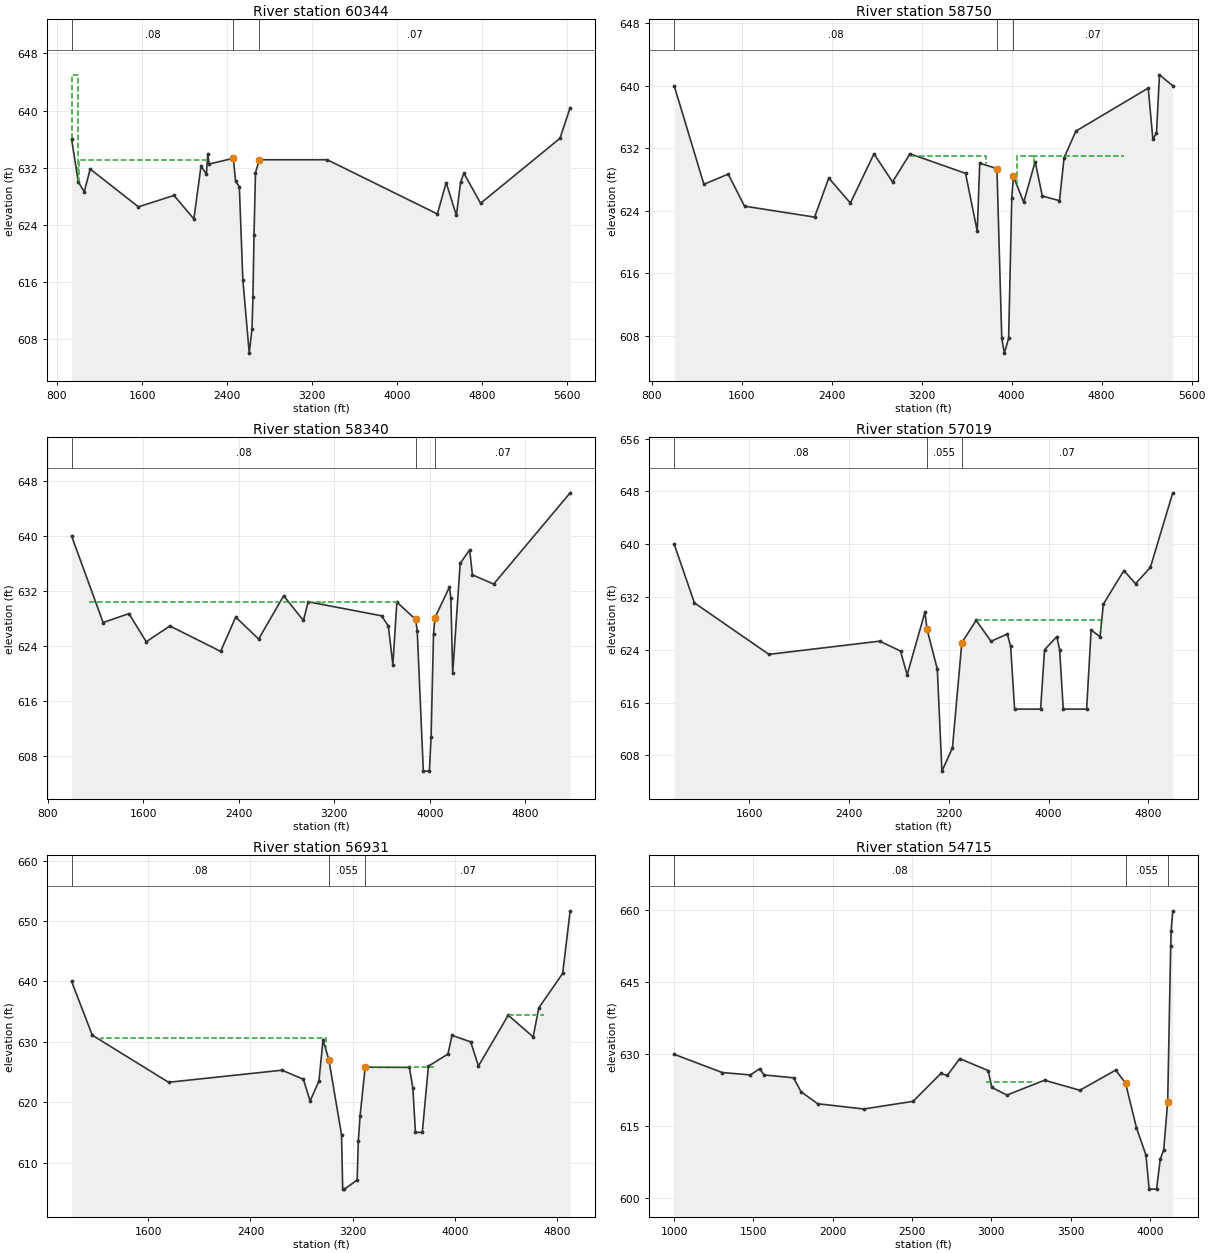
Type RM Length L Ch R = 1 ,60344   ,1524.5,1593.5,1566.2
BEGIN DESCRIPTION:
This cross section corresponds to cross section 60451 of the non-georeferenced CDC model which was the source of this model.
Approx. 400 feet downstream of Clear Fork/Benbrook Lake spillway channel confluence.
Channel data from 1975 USACE field survey.
END DESCRIPTION:
XS GIS Cut Line= 5
 2291850.84332586927377.71680122   2291904.80796   6927345.20806
   2292821.71098   6926792.85811   2292731.61306   6925311.49001
   2293246.02903    6923300.9189
#Sta/Elev= 30
     937     636    1000     630    1056   628.6    1112   631.8    1566   626.5
    1901   628.1    2088   624.8    2155   632.2    2206   631.1    2219   633.9
    2232   632.5    2459   633.3    2481   630.1    2516   629.3    2549   616.3
 2609.17     606    2635   609.4    2644   613.9    2654   622.5    2668   631.3
    2705   633.1    3343   633.1    4380   625.5    4463   629.9    4559   625.3
    4599     630    4630   631.2    4787     627    5534   636.1    5630   640.4
#Mann= 3 ,0,0
     937     .08       0    2459    .055       0    2705     .07       0
#XS Ineff= 3 ,-1
     937    1000     645 1005.54 2218.16  633.02    2877    5247   632.5
Permanent Ineff=
       F       F       F
Bank Sta=2459,2705
XS Rating Curve= 0 ,0
Exp/Cntr=0.3,0.1

Type RM Length L Ch R = 1 ,58750   ,380,410,430
BEGIN DESCRIPTION:
This cross section corresponds to cross section 58850 of the non-georeferenced CDC model which was the source of this model.
Channel data from 1975 USACE field survey.
END DESCRIPTION:
XS GIS Cut Line= 3
   2292254.84499   6927827.90985   2293628.29008   6926249.91694
   2293665.95995   6923910.19098
#Sta/Elev= 30
    1000     640    1264   627.4    1480   628.7    1625   624.6    2248   623.2
    2374   628.2    2566     625    2776   631.3    2941   627.7    3096   631.3
    3590   628.8    3694   621.4    3716   630.1    3869   629.4    3912   607.7
 3935.14   605.8    3973   607.7    4001   625.7    4016   628.4    4107   625.1
    4209   630.3    4272   625.9    4425   625.3    4466   630.8    4571   634.2
    5214   639.7    5255   633.2    5287   633.9    5314   641.4    5432     640
#Mann= 3 ,0,0
    1000     .08       0    3869    .055       0    4016     .07       0
#XS Ineff= 4 ,-1
  1149.5  3104.1  630.99  3104.1 3768.55  630.99  4045.4    4199  630.99
    4199    5000  630.99
Permanent Ineff=
       F       F       F       F
Bank Sta=3869,4016
XS Rating Curve= 0 ,0
Exp/Cntr=0.3,0.1

Type RM Length L Ch R = 1 ,58340   ,1300,1321,1285
BEGIN DESCRIPTION:
Added cross-section.
CDC FW05224-1   Mira Vista Country Club Golf Course Improvements.
Located in ROB.
END DESCRIPTION:
XS GIS Cut Line= 4
   2292254.84499   6927827.90985   2293628.29008   6926249.91694
  2293854.241632 6925685.9482923 2294773.4569704 6924577.6434337
#Sta/Elev= 30
    1000     640    1264   627.4    1480   628.7    1625   624.6    1823   626.9
    2248   623.2    2374   628.2    2566     625    2776   631.3    2941   627.7
 2981.44  630.42 3595.95  628.38  3652.5  626.88 3690.42  621.23 3723.74  630.37
 3881.52  627.85 3894.31  626.18 3945.46  605.76 3996.05  605.76 4010.33  610.69
 4030.71   625.7  4042.3  628.08 4164.12  632.58 4175.93  630.93 4191.38     620
 4253.88     636 4333.41     638  4356.3  634.35 4534.36     633 5174.97  646.29
#Mann= 3 ,0,0
    1000     .08       0 3881.52    .055       0  4042.3     .07       0
#XS Ineff= 3 ,-1
  1149.5  3104.1  630.39  3104.1  3728.7  630.39 4150.14 4234.85  630.39
Permanent Ineff=
       F       F       F
Bank Sta=3881.52,4042.3
XS Rating Curve= 0 ,0
Exp/Cntr=0.3,0.1

Type RM Length L Ch R = 1 ,57019   ,76,88,107
BEGIN DESCRIPTION:
Added cross-section.
CDC FW05224-1   Mira Vista Country Club Golf Course Improvements.
Located in ROB.
END DESCRIPTION:
XS GIS Cut Line= 4
   2292550.51402    6928102.5179   2294005.40415   6926968.38795
 2294276.8991896 6926266.4022394 2295474.8597463 6925544.6947723
#Sta/Elev= 30
    1000     640    1162   631.1    1759   623.3    2647   625.3    2814   623.8
    2867   620.2 3010.07  629.71 3026.11  627.14 3109.01  621.04 3145.72  605.61
 3230.15  609.11 3305.14  625.06  3420.1  628.45 3539.71  625.28 3669.66  626.38
 3696.52   624.5 3728.38  615.01 3936.78     615  3968.3     624 4066.39  625.98
 4089.16  624.03  4118.3  615.01 4305.48     615 4341.67  626.99 4413.22  625.97
 4439.73  630.91 4604.34     636 4697.36     634  4816.4  636.47 4995.93  647.77
#Mann= 3 ,0,0
    1000     .08       0 3026.11    .055       0 3305.14     .07       0
#XS Ineff= 2 ,-1
 1243.63 3010.07  629.69  3420.1    4419  628.45
Permanent Ineff=
       F       F
Bank Sta=3026.11,3305.14
XS Rating Curve= 0 ,0
Exp/Cntr=0.3,0.1

Type RM Length L Ch R = 1 ,56931   ,2045.2,2216.4,2234.5
BEGIN DESCRIPTION:
This cross section corresponds to cross section 57021 of the non-georeferenced CDC model which was the source of this model.
USGS gaging station 08047000 - Benbrook Gage - located
on left bank.  Gage datum elev. 604.22 MSL.
Channel data from 1975 USACE field survey.
CDC FW05224-1   Mira Vista Country Club Golf Course Improvements.
Located in ROB.
END DESCRIPTION:
XS GIS Cut Line= 4
   2292550.51402    6928102.5179   2294005.40415   6926968.38795
   2294400.56511   6926451.90112   2295520.89095   6925600.00092
#Sta/Elev= 30
    1000     640    1162   631.1    1759   623.3    2647   625.3    2814   623.8
    2867   620.2    2936   623.5    2968   630.3    3014     627    3113   614.6
    3122   605.7    3135   605.6    3235   607.1    3244   613.5    3258   617.7
    3298   625.8 3644.15 625.759 3671.35 622.313 3691.46     615  3745.1     615
 3792.84 625.969 3945.46  627.97 3978.21  631.06 4123.83     630 4184.56     626
 4417.82  634.41 4612.77  630.82 4657.11  635.63 4843.74  641.33 4902.46   651.7
#Mann= 3 ,0,0
    1000     .08       0    3014    .055       0    3298     .07       0
#XS Ineff= 3 ,-1
    1230    2991   630.6  3297.9    3840   625.8  4424.1    4700  634.43
Permanent Ineff=
       F       F       F
Bank Sta=3014,3298
XS Rating Curve= 0 ,0
Exp/Cntr=0.3,0.1

Type RM Length L Ch R = 1 ,54715   ,920.5,913.8,857.5
BEGIN DESCRIPTION:
This cross section corresponds to cross section 54806 of the non-georeferenced CDC model which was the source of this model.
Channel data from 1975 USACE field survey.
END DESCRIPTION:
XS GIS Cut Line= 3
   2292993.46195   6928436.13009   2295483.60001   6927485.79013
   2295952.42716   6927587.07601
#Sta/Elev= 30
    1000     630    1303   626.2    1481   625.7    1539     627    1567   625.7
    1753   625.1    1800   622.2    1905   619.7    2195   618.6    2507   620.2
    2682     626    2723   625.6    2801   629.1    2981   626.6    3003   623.1
    3099   621.5    3336   624.6    3559   622.5    3785   626.7    3847     624
    3916   614.7    3976     609  3995.9   601.9  4042.9   601.9    4066   608.1
    4088   610.1    4113   620.1    4132   652.6    4135   655.8    4145   659.9
#Mann= 3 ,0,0
    1000     .08       0    3847    .055       0    4113     .07       0
#XS Ineff= 3 ,-1
 1093.02 2802.33  627.56 2965.12 3255.81  624.21    4113    4145   620.1
Permanent Ineff=
       F       F       F
Bank Sta=3847,4113
XS Rating Curve= 0 ,0
Exp/Cntr=0.3,0.1

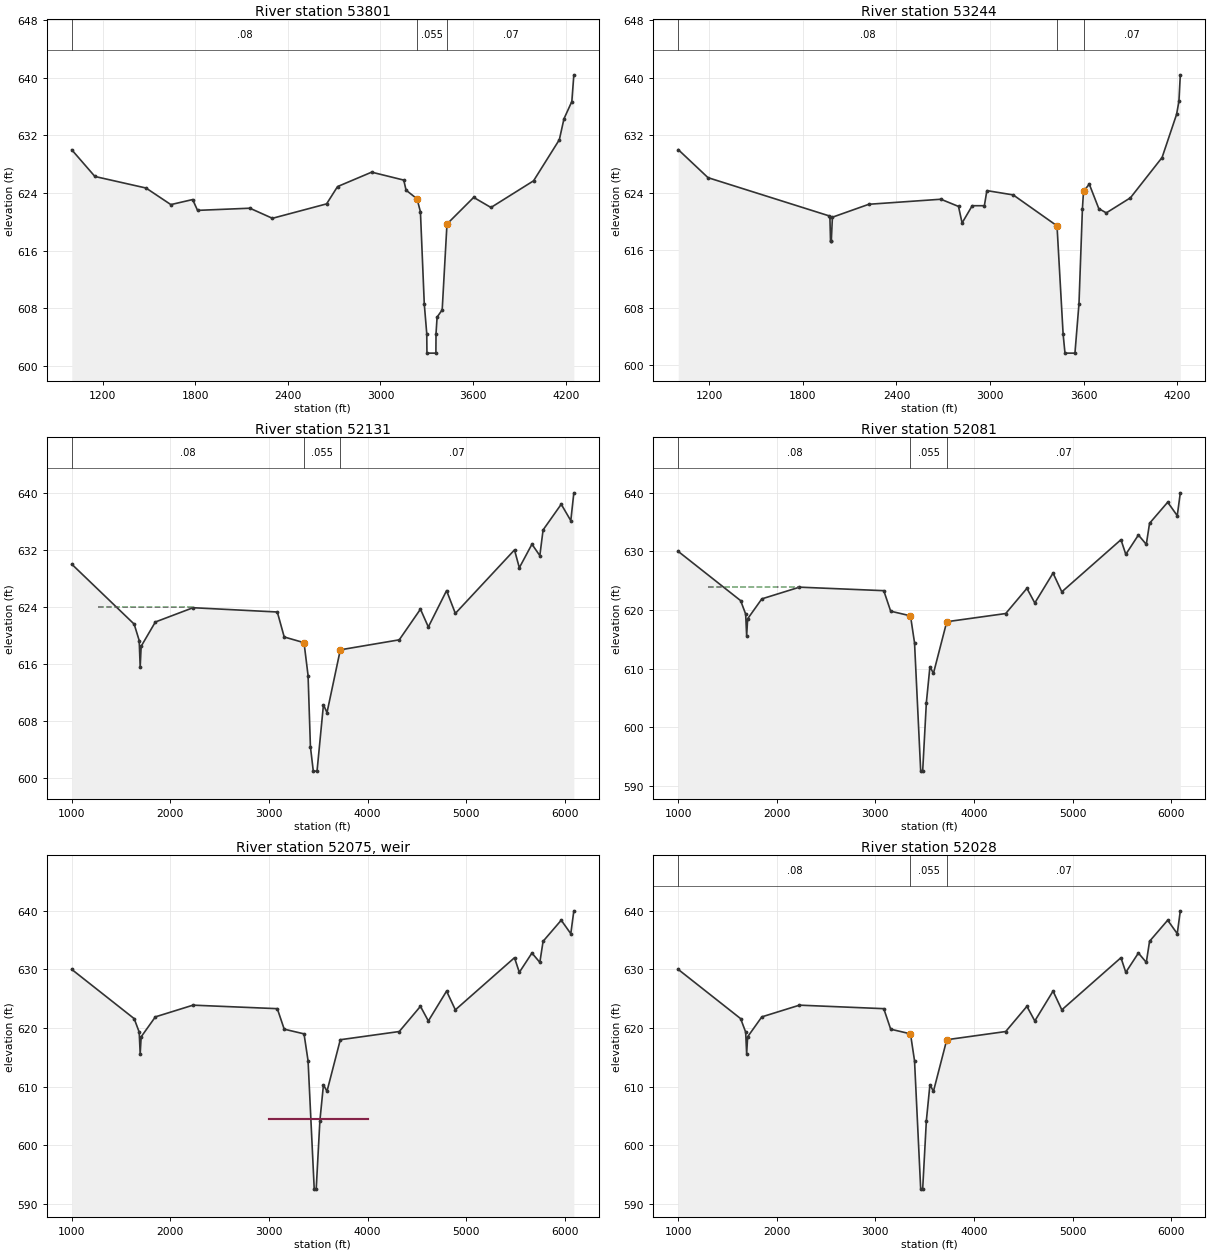
Type RM Length L Ch R = 1 ,53801   ,573.4,557.2,519.3
BEGIN DESCRIPTION:
This cross section corresponds to cross section 53901 of the non-georeferenced CDC model which was the source of this model.
Channel data from 1975 USACE field survey.
END DESCRIPTION:
XS GIS Cut Line= 3
   2293225.28596   6929086.76691   2295284.68112   6928387.10099
   2296332.22004   6928130.91909
#Sta/Elev= 30
    1000     630    1150   626.3    1481   624.7    1642   622.4    1783   623.1
    1815   621.6    2154   621.9    2300   620.5    2651   622.5    2722   624.9
    2943   626.9    3151   625.8    3166   624.4    3237   623.2    3259   621.4
    3284   608.6    3300   604.5 3301.22   601.8 3359.22   601.8    3360   604.5
    3367   606.8    3400   607.8    3431   619.7    3604   623.4    3716     622
    3992   625.7    4159   631.4    4189   634.3    4240   636.7    4253   640.4
#Mann= 3 ,0,0
    1000     .08       0    3237    .055       0    3431     .07       0
#XS Ineff= 1 ,-1
 1135.66 2934.11  626.63
Permanent Ineff=
       F
Bank Sta=3237,3431
XS Rating Curve= 0 ,0
Exp/Cntr=0.3,0.1

Type RM Length L Ch R = 1 ,53244   ,1025.6,1113.6,1150.9
BEGIN DESCRIPTION:
This cross section corresponds to cross section 53352 of the non-georeferenced CDC model which was the source of this model.
Channel data from 1975 USACE field survey.
END DESCRIPTION:
XS GIS Cut Line= 4
   2293577.18191   6929578.50805   2295600.82714   6928956.42597
     2295998.348   6928545.33591   2296332.11374   6928131.05098
#Sta/Elev= 30
    1000     630    1191   626.1    1966   620.8    1973   620.6    1977   617.3
    1982   617.3    1989   620.6    2223   622.4    2685   623.1    2798   622.1
    2821   619.8    2886   622.2    2964   622.2    2980   624.3    3149   623.7
    3430   619.4    3469   604.4 3481.07   601.7 3545.07   601.7    3571   608.6
    3593   621.8    3600   624.2    3637   625.2    3698   621.8    3746   621.2
    3901   623.3    4104   628.9    4197   634.9    4212   636.7    4221   640.4
#Mann= 3 ,0,0
    1000     .08       0    3430    .055       0    3600     .07       0
#XS Ineff= 2 ,-1
 1406.98 2988.37  624.17 3620.16 3953.49621.5899
Permanent Ineff=
       F       F
Bank Sta=3430,3600
XS Rating Curve= 0 ,0
Exp/Cntr=0.3,0.1

Type RM Length L Ch R = 1 ,52131   ,48.9,49.2,50.1
BEGIN DESCRIPTION:
This cross section corresponds to cross section 52242 of the non-georeferenced CDC model which was the source of this model.
50 feet upstream of Rawls Dam.
Channel data from 1975 USACE field survey.
END DESCRIPTION:
XS GIS Cut Line= 5
      2293950.84      6930062.52      2295780.52      6929641.18
     2295873.856     6929597.844      2296865.83      6929641.16
    2298532.2459    6928332.6397
#Sta/Elev= 30
    1000     630    1633   621.6    1684   619.3    1694   615.6    1704   618.5
    1848   621.9    2230   623.9    3085   623.3    3155   619.8    3356     619
    3397   614.4    3421   604.4    3450     601    3488     601    3553   610.3
    3589   609.2    3724     618    4322   619.4    4537   623.7    4617   621.2
    4802   626.3    4891   623.1    5491     632    5540   629.5    5668   632.8
    5748   631.2    5781   634.8    5965   638.4    6062   636.1    6093     640
#Mann= 3 ,0,0
    1000     .08       0    3356    .055       0    3724     .07       0
#XS Ineff= 1 ,-1
 1265.78 2215.95 623.967
Permanent Ineff=
       F
Bank Sta=3356,3724
XS Rating Curve= 0 ,0
Exp/Cntr=0.3,0.1

Type RM Length L Ch R = 1 ,52081   ,50.6,53.6,51.5
BEGIN DESCRIPTION:
This cross section corresponds to cross section 52192 of the non-georeferenced CDC model which was the source of this model.
One-foot upstream of Rawls Dam.
Channel data from 1975 USACE field survey.
END DESCRIPTION:
XS GIS Cut Line= 4
     2293951.113     6930064.424      2295780.54     6929641.247
    2296805.5596    6929688.6595     2298532.276     6928332.653
#Sta/Elev= 30
    1000     630    1633   621.6    1684   619.3    1694   615.6    1704   618.5
    1848   621.9    2230   623.9    3085   623.3    3155   619.8    3356     619
    3397   614.4  3459.5   592.5  3479.5   592.5    3517   604.2    3553   610.3
    3589   609.2    3724     618    4322   619.4    4537   623.7    4617   621.2
    4802   626.3    4891   623.1    5491     632    5540   629.5    5668   632.8
    5748   631.2    5781   634.8    5965   638.4    6062   636.1    6093     640
#Mann= 3 ,0,0
    1000     .08       0    3356    .055       0    3724     .07       0
#XS Ineff= 1 ,-1
 1305.65 2222.59  623.95
Permanent Ineff=
       F
Bank Sta=3356,3724
XS Rating Curve= 0 ,0
Exp/Cntr=0.3,0.1

Type RM Length L Ch R = 5 ,52075   ,,,
BEGIN DESCRIPTION:
Rawls Dam
crest elevation 604.4
END DESCRIPTION:
Node Name=Rawls Dam
IW Pilot Flow=0
#Inline Weir SE= 2
    3000   604.4    4000   604.4
IW Dist,WD,Coef,Skew,MaxSub,Min_El,Is_Ogee,SpillHt,DesHd
3.5,5,3,0,0.95,, 0 ,,,0,0,
Inline Weir Flap Gates= 0
IW Outlet Rating Curve= 0 ,False,,

Type RM Length L Ch R = 1 ,52028   ,531.4,497.5,452.8
BEGIN DESCRIPTION:
This cross section corresponds to cross section 52140 of the non-georeferenced CDC model which was the source of this model.
52 feet downstream of Rawls Dam.
Channel data from 1975 USACE field survey.
END DESCRIPTION:
XS GIS Cut Line= 5
    2293951.1174    6930064.4332    2295602.0909    6929682.6609
     2296744.081     6929736.733    2296805.5702    6929688.6655
      2298533.18      6928333.95
#Sta/Elev= 30
    1000     630    1633   621.6    1684   619.3    1694   615.6    1704   618.5
    1848   621.9    2230   623.9    3085   623.3    3155   619.8    3356     619
    3397   614.4  3459.5   592.5  3479.5   592.5    3517   604.2    3553   610.3
    3589   609.2    3724     618    4322   619.4    4537   623.7    4617   621.2
    4802   626.3    4891   623.1    5491     632    5540   629.5    5668   632.8
    5748   631.2    5781   634.8    5965   638.4    6062   636.1    6093     640
#Mann= 3 ,0,0
    1000     .08       0    3356    .055       0    3724     .07       0
#XS Ineff= 1 ,-1
 1332.23 2229.24  623.69
Permanent Ineff=
       F
Bank Sta=3356,3724
XS Rating Curve= 0 ,0
Exp/Cntr=0.3,0.1

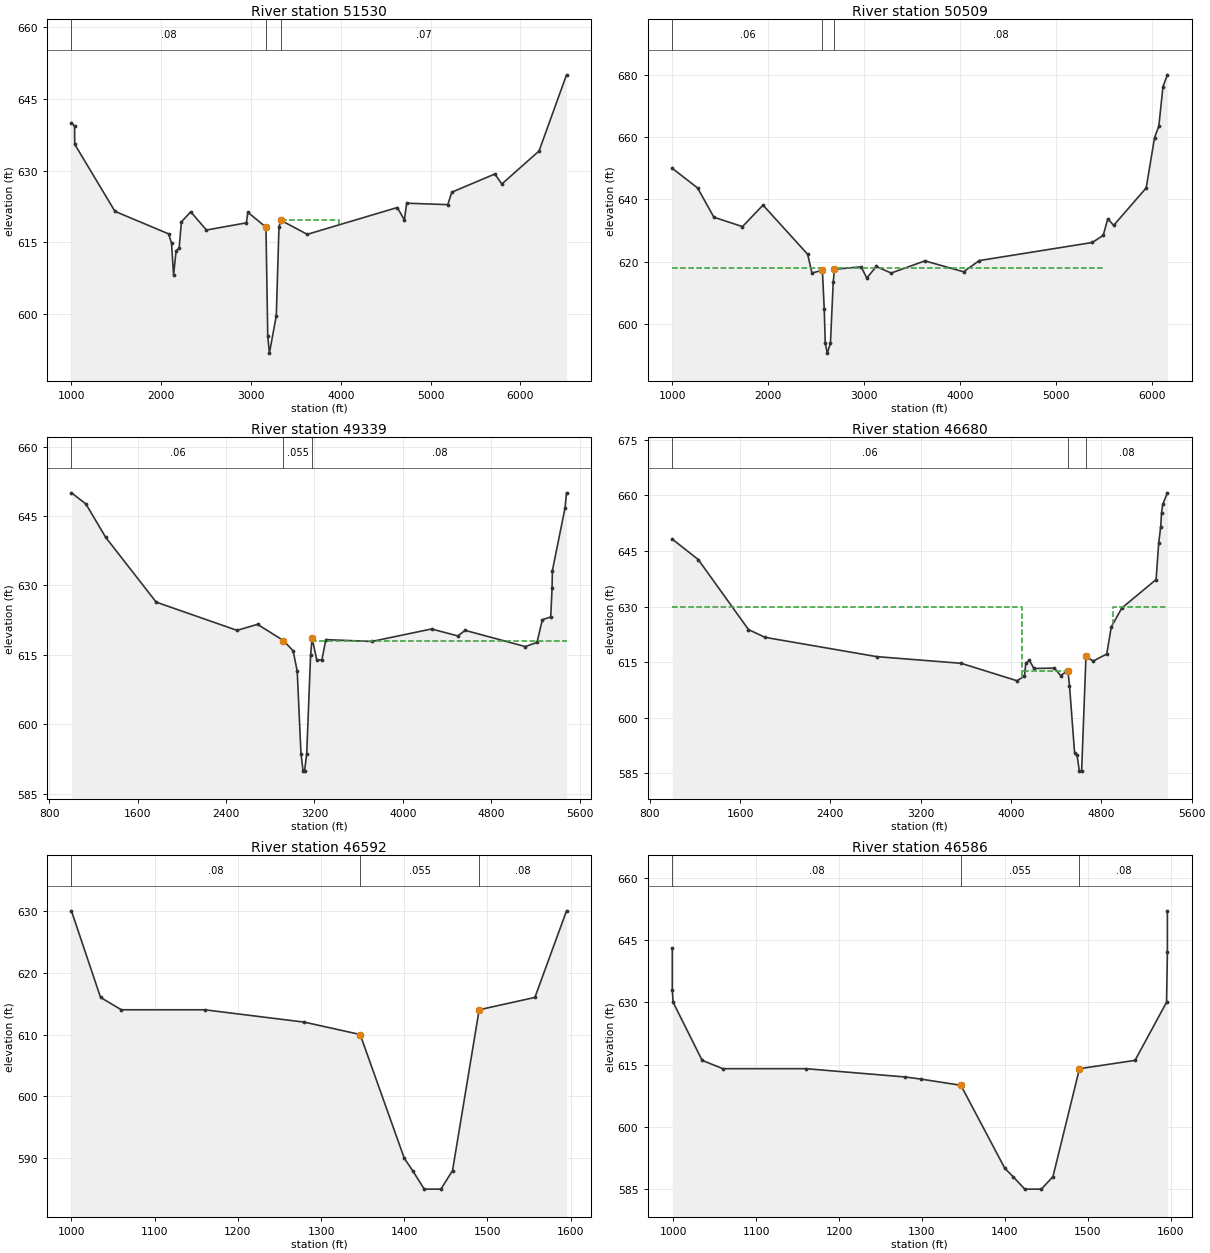
Type RM Length L Ch R = 1 ,51530   ,1007.7,1021.2,967.2
BEGIN DESCRIPTION:
This cross section corresponds to cross section 51599 of the non-georeferenced CDC model which was the source of this model.
Channel data from 1975 USACE field survey.
END DESCRIPTION:
XS GIS Cut Line= 4
   2294267.97515    6930833.8169   2296137.94188   6930334.70799
   2297376.60509   6929730.37291   2299223.99706   6928532.58495
#Sta/Elev= 30
    1000     640    1035   639.3    1037   635.5    1485   621.5    2082   616.8
    2115   614.9    2138   608.2    2166   613.3    2200   613.8    2225   619.3
    2329   621.4    2504   617.6    2949   619.1    2965   621.3    3167   618.2
    3187   595.4 3205.33   591.9    3282   599.7    3312   618.3    3336   619.6
    3627   616.7    4630   622.3    4709   619.7    4734   623.2    5192   622.9
    5237   625.5    5717   629.3    5794   627.2    6209   634.1    6515     650
#Mann= 3 ,0,0
    1000     .08       0    3167    .055       0    3336     .07       0
#XS Ineff= 2 ,-1
 1471.76 2973.42     621  3358.8 3983.39  619.65
Permanent Ineff=
       F       F
Bank Sta=3167,3336
XS Rating Curve= 0 ,0
Exp/Cntr=0.3,0.1

Type RM Length L Ch R = 1 ,50509   ,1130.5,1170,1180.6
BEGIN DESCRIPTION:
This cross section corresponds to cross section 50598 of the non-georeferenced CDC model which was the source of this model.
Channel data from 1975 USACE field survey.
END DESCRIPTION:
XS GIS Cut Line= 3
   2295599.88587   6932214.68192   2297620.19909   6930283.47909
   2299641.16585   6929050.26502
#Sta/Elev= 30
    1000     650    1264   643.7    1434   634.3    1732   631.3    1946   638.2
    2412   622.4    2456   616.4    2565   617.3    2584     605    2595   593.9
 2616.04   590.7    2649   593.9    2678   613.5    2691   617.6    2969   618.4
    3028   614.8    3127   618.5    3282   616.4    3634   620.3    4037   616.8
    4201   620.4    5379   626.2    5493   628.5    5541   633.8    5602   631.7
    5941   643.7    6028   659.8    6073   663.6    6116   676.2    6162     680
#Mann= 3 ,0,0
    1000     .06       0    2565    .055       0    2691     .08       0
#XS Ineff= 3 ,-1
    1000    2565     618    2691    2733     618    2733    5500     618
Permanent Ineff=
       F       F       F
Bank Sta=2565,2691
XS Rating Curve= 0 ,0
Exp/Cntr=0.3,0.1

Type RM Length L Ch R = 1 ,49339   ,2264.6,2659.3,2611.9
BEGIN DESCRIPTION:
This cross section corresponds to cross section 49420 of the non-georeferenced CDC model which was the source of this model.
Channel data from 1975 USACE field survey.
END DESCRIPTION:
XS GIS Cut Line= 4
   2295600.04958   6932214.65567   2297310.18986   6931940.04893
   2298288.57013   6931471.27789     2299929.828   6931190.55404
#Sta/Elev= 30
    1000     650    1131   647.6    1310   640.4    1767   626.4    2499   620.3
    2685   621.6    2919   618.1    3007   615.9    3044   611.5    3078   593.7
  3097.3   589.9  3110.3   589.9    3130   593.7    3165   614.9    3179   618.6
    3221   613.9    3267   613.9    3303   618.3    3719   617.9    4260   620.6
    4498   619.1    4564   620.3    5109   616.8    5215   617.7    5263   622.6
    5339   623.2    5351   629.4    5354   633.2    5469   646.8    5482     650
#Mann= 3 ,0,0
    1000     .06       0    2919    .055       0    3179     .08       0
#XS Ineff= 2 , 0
                            3188             618
Permanent Ineff=
       F       F
Bank Sta=2919,3179
XS Rating Curve= 0 ,0
Exp/Cntr=0.3,0.1

Type RM Length L Ch R = 1 ,46680   ,81.1,88.1,88
BEGIN DESCRIPTION:
This cross section corresponds to cross section 46736 of the non-georeferenced CDC model which was the source of this model.
Cross-section modified by USACE February 2007 - blocked obstruction in LOB changed to ineffective flow.
Effective flow limit set at sta 4100 in LOB, at sta 4900 in ROB.
126 feet upstream of I.H. 20.
Channel data from 1975 USACE field survey.
END DESCRIPTION:
XS GIS Cut Line= 2
   2295615.17291   6933214.44107    2300000.0001   6933192.25214
#Sta/Elev= 30
    1000   648.2    1230   642.7    1675   623.8    1822   621.7    2810   616.5
    3558   614.7    4052     610    4119   611.2    4131   614.7    4163   615.5
    4203   613.3    4384   613.4    4440   611.4    4504   612.7    4518   608.7
    4563   590.6    4585   589.9 4605.39   585.6 4625.39   585.6    4664   616.6
    4727   615.3    4848   617.2    4888   624.5    4981   629.6    5285   637.3
    5308   647.1    5326   651.6    5333   655.2    5344   657.6    5385   660.7
#Mann= 3 ,0,0
    1000     .06       0    4504    .055       0    4664     .08       0
#XS Ineff= 4 ,-1
    1000    4100     630    4100    4504   612.7    4664    4900   616.6
    4900    5385     630
Permanent Ineff=
       F       F       F       F
Bank Sta=4504,4664
XS Rating Curve= 0 ,0
Exp/Cntr=0.3,0.1

Type RM Length L Ch R = 1 ,46592   ,6,6,6
BEGIN DESCRIPTION:
This cross section corresponds to cross section 46611 of the non-georeferenced CDC model which was the source of this model.
Upstream of I.H. 20.
Channel data from 1975 USACE field survey.
END DESCRIPTION:
XS GIS Cut Line= 2
      2298724.45      6933276.342299319.445994796933274.15684196
#Sta/Elev= 14
    1000     630    1035     616    1060     614    1160     614    1280     612
    1347     610    1400     590    1410     588 1424.03     585 1444.03     585
    1458     588    1490     614    1557     616    1595     630
#Mann= 3 ,0,0
    1000     .08       0    1347    .055       0    1490     .08       0
Bank Sta=1347,1490
XS Rating Curve= 0 ,0
Exp/Cntr=0.5,0.3

Type RM Length L Ch R = 1 ,46586   ,93,127,101
XS GIS Cut Line= 2
      2298724.63      6933280.48 2299321.6254746 6933278.1555035
#Sta/Elev= 19
     999     643     999     633    1000     630    1035     616    1060     614
    1160     614    1280     612  1298.5   611.5    1347     610    1400     590
    1410     588    1424     585    1444     585    1458     588    1490     614
    1557     616    1595     630    1596     642    1596     652
#Mann= 3 ,0,0
     999     .08       0    1347    .055       0    1490     .08       0
Bank Sta=1347,1490
XS Rating Curve= 0 ,0
Exp/Cntr=0.5,0.3