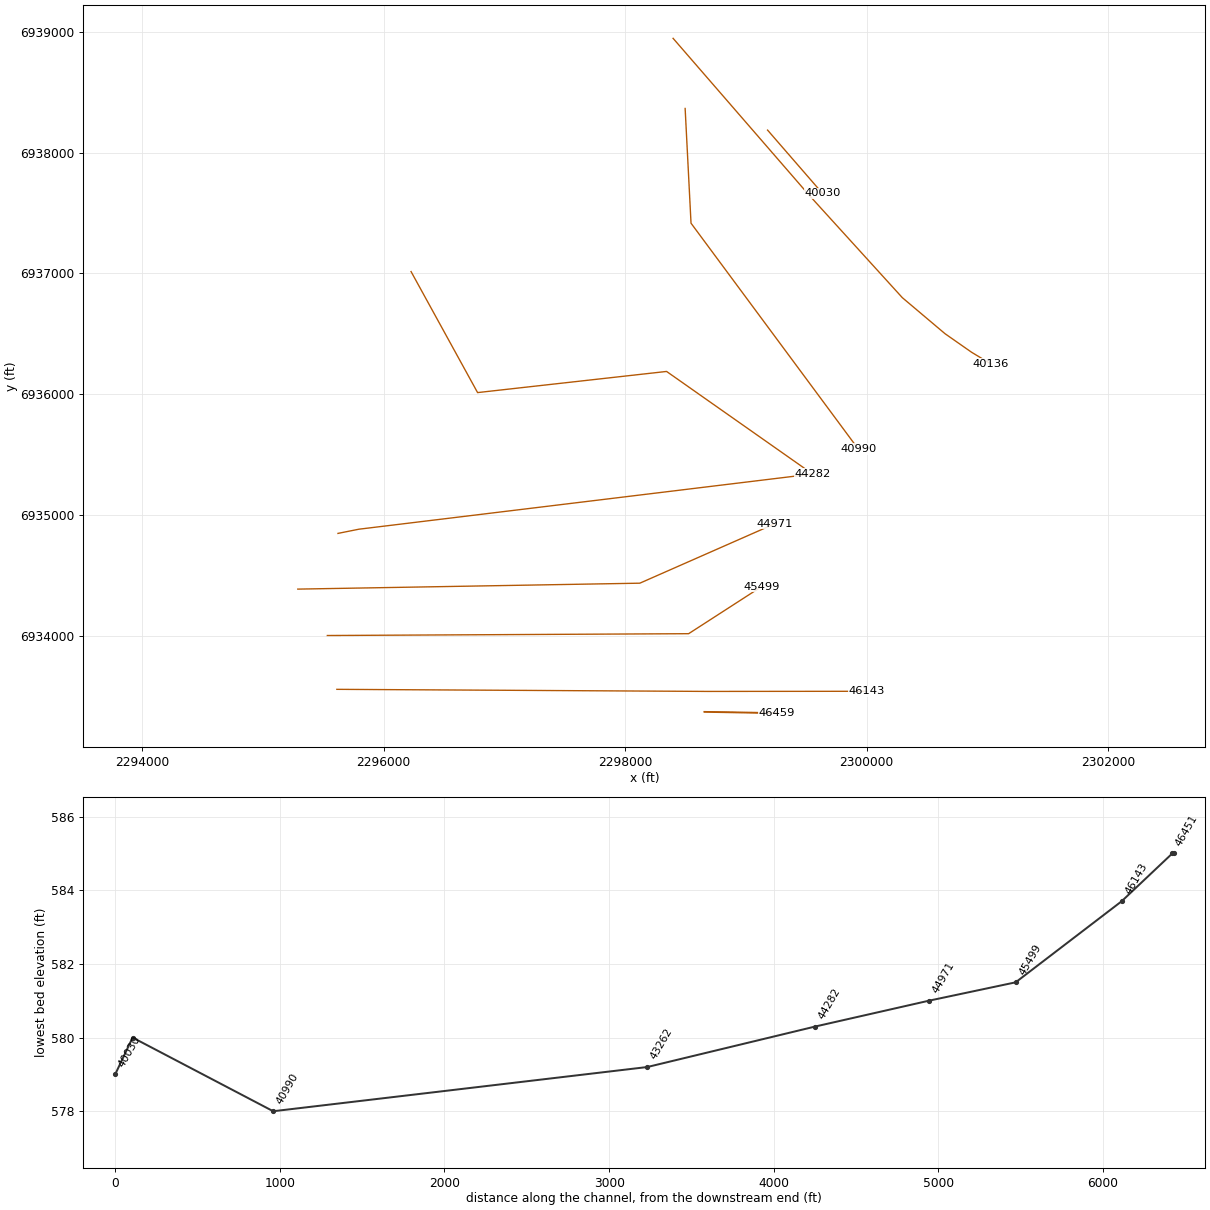
HEC-RAS study CDC_Consolidated_Model.prj: Upper Trinity CDC Consolidated Model

--- CDC_Consolidated_Model.g11 (geometry) --- (continued)

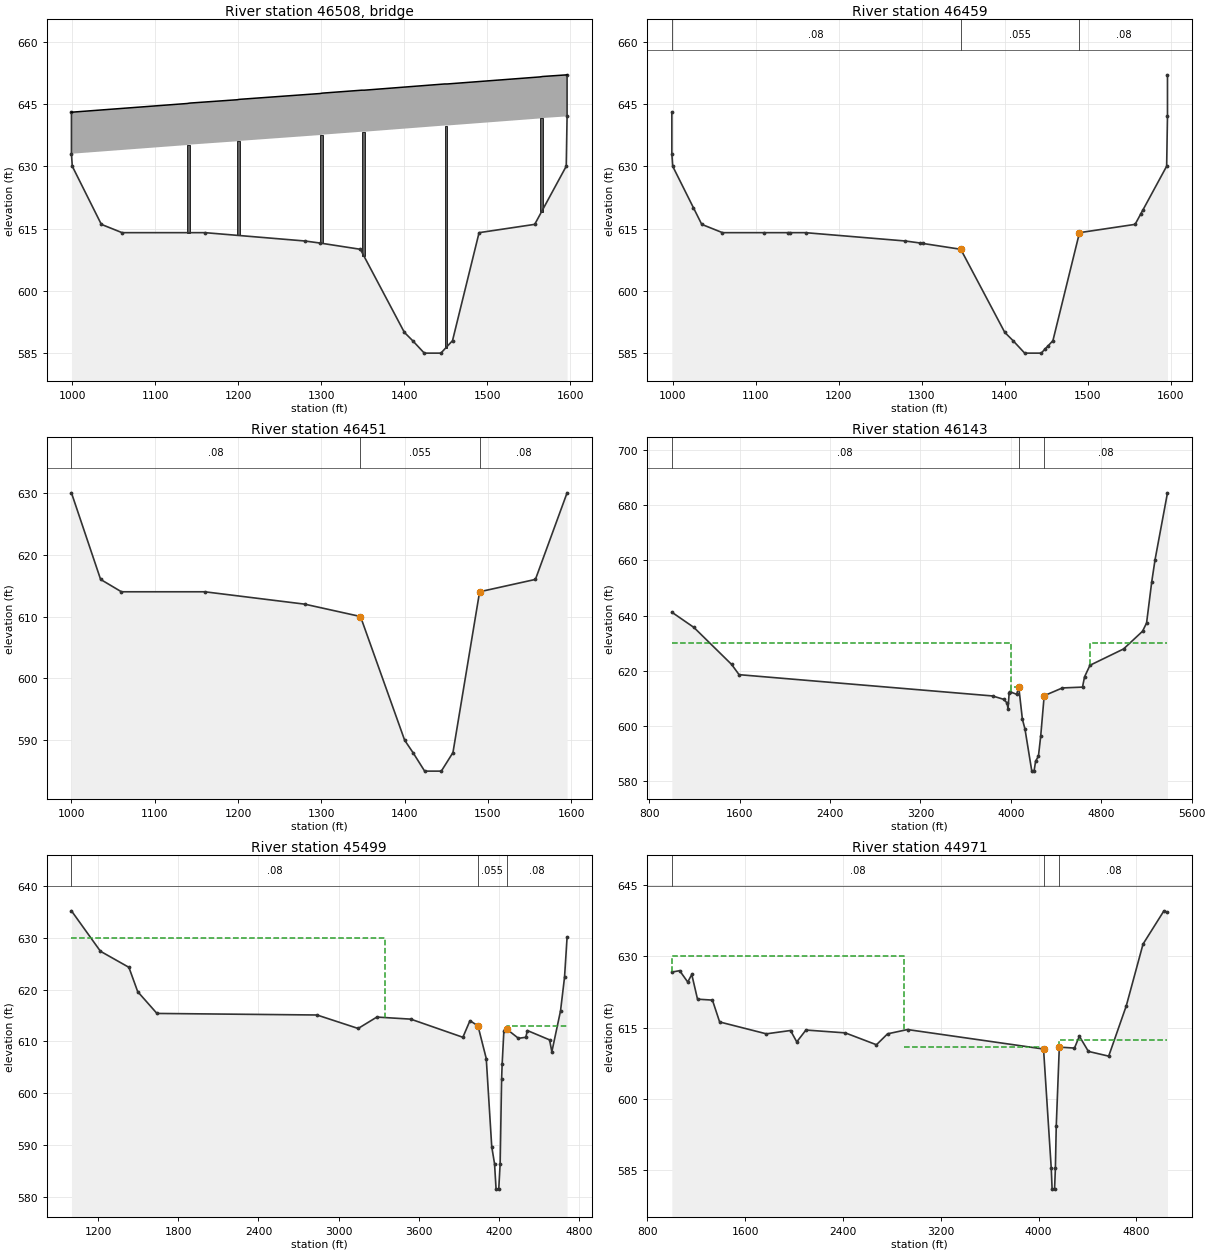
Type RM Length L Ch R = 3 ,46508   ,,,
BEGIN DESCRIPTION:
IH 20
Double bridge - one composite bridge represented.
Bridge data from bridge plans.
Channel data from 1975 USACE field survey.
END DESCRIPTION:
Node Name=IH 20
Bridge Culvert--1,0,-1,-1, 0
Deck Dist Width WeirC Skew NumUp NumDn MinLoCord MaxHiCord MaxSubmerge Is_Ogee
19,100,2.6,0, 14, 10, , , 0.95, 0, 0,0,,
     999  1138.5  1141.5  1198.5  1201.5  1298.5  1301.5  1348.5  1351.5  1448.5
  1451.5  1563.5  1566.5    1596
     643   645.1   645.2     646   646.1   647.5   647.6   648.3   648.3   649.8
   649.8   651.5   651.6     652
     633   635.1   635.2     636   636.1   637.5   637.6   638.3   638.3   639.8
   639.8   641.5   641.6     642
     999  1138.5  1141.5  1298.5  1301.5  1448.5  1451.5  1563.5  1566.5    1596
     643   645.1   645.2   647.5   647.6   649.8   649.8   651.5   651.6     652
     633   635.1   635.2   637.5   637.6   639.8   639.8   641.5   641.6     642
Pier Skew, UpSta & Num, DnSta & Num=  ,1140, 2 ,1140, 2 , 0 , 0 , 0 ,,
       3       3
     580     640
       3       3
     580     640
Pier Skew, UpSta & Num, DnSta & Num=  ,1200, 2 ,1200, 2 , 0 , 0 , 0 ,,
       3       3
     580     640
       3       3
     580     640
Pier Skew, UpSta & Num, DnSta & Num=  ,1300, 2 ,1300, 2 , 0 , 0 , 0 ,,
       3       3
     580     640
       3       3
     580     640
Pier Skew, UpSta & Num, DnSta & Num=  ,1351, 2 ,1351, 2 , 0 , 0 , 0 ,,
       3       3
     580     642
       3       3
     580     642
Pier Skew, UpSta & Num, DnSta & Num=  ,1450, 2 ,1450, 2 , 0 , 0 , 0 ,,
       3       3
     580     642
       3       3
     580     642
Pier Skew, UpSta & Num, DnSta & Num=  ,1565, 2 ,1565, 2 , 0 , 0 , 0 ,,
       3       3
     580     642
       3       3
     580     642
BR Coef=-1 , 0 , 0 ,1.05, 0 ,,,0.8,-1,0.5,1,
WSPro=,,,, 1 ,,,, 0 ,,,, 0 ,,,,-1 ,-1 ,-1 , 0 , 0 , 0 , 0 , 0
BC Design=,, 0 ,, 0 ,,,,,,
BC HTab HWMax=652
BC Use User HTab Curves=0
BC User HTab FreeFlow(D)= 0

Type RM Length L Ch R = 1 ,46459   ,8,8,8
XS GIS Cut Line= 3
      2298655.66      6933368.69      2298729.42      6933367.14
 2299252.5618915  6933357.886991
#Sta/Elev= 28
     999     643     999     633    1000     630    1025     620    1035     616
    1060     614    1110     614  1138.5     614  1141.5     614    1160     614
    1280     612  1298.5   611.5  1301.5   611.4    1347     610    1400     590
    1410     588    1424     585    1444     585  1448.5     586  1451.5   586.6
    1458     588    1490     614    1557     616  1563.5   618.4  1566.5   619.5
    1595     630    1596     642    1596     652
#Mann= 3 ,0,0
     999     .08       0    1347    .055       0    1490     .08       0
Bank Sta=1347,1490
XS Rating Curve= 0 ,0
Exp/Cntr=0.5,0.3

Type RM Length L Ch R = 1 ,46451   ,202,308,233
BEGIN DESCRIPTION:
This cross section corresponds to cross section 46489 of the non-georeferenced CDC model which was the source of this model.
Downstream of I.H. 20.
Channel data from 1975 USACE field survey.
END DESCRIPTION:
XS GIS Cut Line= 3
      2298655.03      6933372.26      2298827.09      6933370.08
 2299249.9404161 6933362.0745018
#Sta/Elev= 14
    1000     630    1035     616    1060     614    1160     614    1280     612
    1347     610    1400     590    1410     588 1424.03     585 1444.03     585
    1458     588    1490     614    1557     616    1595     630
#Mann= 3 ,0,0
    1000     .08       0    1347    .055       0    1490     .08       0
Bank Sta=1347,1490
XS Rating Curve= 0 ,0
Exp/Cntr=0.3,0.1

Type RM Length L Ch R = 1 ,46143   ,553.9,643.6,682.3
BEGIN DESCRIPTION:
This cross section corresponds to cross section 46175 of the non-georeferenced CDC model which was the source of this model.
Cross-section modified by USACE February 2007 - blocked obstruction in LOB and ROB changed to ineffective flow.
Effective flow limit set at sta 4000 in LOB, at sta 4700 in ROB.
315 feet downstream of I.H. 20.
Channel data from 1975 USACE field survey.
END DESCRIPTION:
XS GIS Cut Line= 3
   2295613.70901   6933556.90594   2298682.34099   6933539.63694
    2300000.0001   6933540.79803
#Sta/Elev= 30
    1000   641.2    1195   635.7    1529   622.3    1595   618.6    3838   610.9
    3935   609.7    3966   608.4    3975   606.3    3985     612    3988   612.5
    4051   611.5    4070   614.1    4102   602.5    4125   598.9 4185.33   583.7
 4205.33   583.7    4219   587.3    4244   589.1    4264   596.3    4295     611
    4456   613.8    4634   614.1    4652   617.8    4700     622    4997   627.9
    5165   634.3    5201   637.3    5247   652.3    5276   660.2    5386   684.4
#Mann= 3 ,0,0
    1000     .08       0    4070    .055       0    4295     .08       0
#XS Ineff= 3 ,-1
    1000    4000     630    4000    4070   614.1    4700    5386     630
Permanent Ineff=
       F       F       F
Bank Sta=4070,4295
XS Rating Curve= 0 ,0
Exp/Cntr=0.3,0.1

Type RM Length L Ch R = 1 ,45499   ,523.4,528,501.9
BEGIN DESCRIPTION:
This cross section corresponds to cross section 45544 of the non-georeferenced CDC model which was the source of this model.
Cross-section modified by USACE February 2007 - blocked obstruction in LOB changed to ineffective flow.
Effective flow limit set at sta 3350 in LOB.
Channel data from 1975 USACE field survey.
END DESCRIPTION:
XS GIS Cut Line= 3
   2295534.77904   6934002.51003   2298525.87707   6934017.55101
   2299129.91096   6934407.41014
#Sta/Elev= 30
    1000   635.2    1217   627.4    1430   624.3    1496   619.6    1640   615.4
    2838   615.1    3146   612.5    3286   614.7    3540   614.3    3930   610.8
    3983     614    4043     613    4105   606.7    4146   589.7    4167   586.4
  4178.5   581.5  4198.5   581.5    4209   586.4    4220   602.8    4224   605.6
    4237   612.1    4257   612.4    4346   610.6    4401   610.8    4413   612.1
    4579   610.3    4596     608    4661   615.9    4691   622.4    4710   630.1
#Mann= 3 ,0,0
    1000     .08       0    4043    .055       0    4257     .08       0
#XS Ineff= 3 ,-1
    1000    3350     630    3350    4043     613    4257    4710     613
Permanent Ineff=
       F       F       F
Bank Sta=4043,4257
XS Rating Curve= 0 ,0
Exp/Cntr=0.3,0.1

Type RM Length L Ch R = 1 ,44971   ,720.1,689.2,594.1
BEGIN DESCRIPTION:
This cross section corresponds to cross section 45015 of the non-georeferenced CDC model which was the source of this model.
Cross-section modified by USACE February 2007 - blocked obstruction in LOB changed to ineffective flow.
Effective flow limit set at sta 2900 in LOB.
Channel data from 1975 USACE field survey.
END DESCRIPTION:
XS GIS Cut Line= 3
   2295290.26116   6934386.60605    2298121.8221   6934435.63187
   2299240.73193   6934928.33692
#Sta/Elev= 30
    1000   626.7    1064     627    1130   624.6    1163   626.2    1210     621
    1332   620.8    1391   616.2    1773   613.7    1971   614.4    2022     612
    2097   614.5    2419   613.9    2674   611.4    2765   613.7    2928   614.6
    4041   610.5    4104   585.4 4111.11     581 4131.11     581    4138   585.4
    4145   594.3    4170   610.9    4294   610.7    4334   613.2    4408     610
    4574     609    4718   619.6    4855   632.6    5026   639.6    5055   639.3
#Mann= 3 ,0,0
    1000     .08       0    4041    .055       0    4170     .08       0
#XS Ineff= 3 ,-1
    1000    2900     630    2900    4041     611    4170    5055   612.5
Permanent Ineff=
       F       F       F
Bank Sta=4041,4170
XS Rating Curve= 0 ,0
Exp/Cntr=0.3,0.1

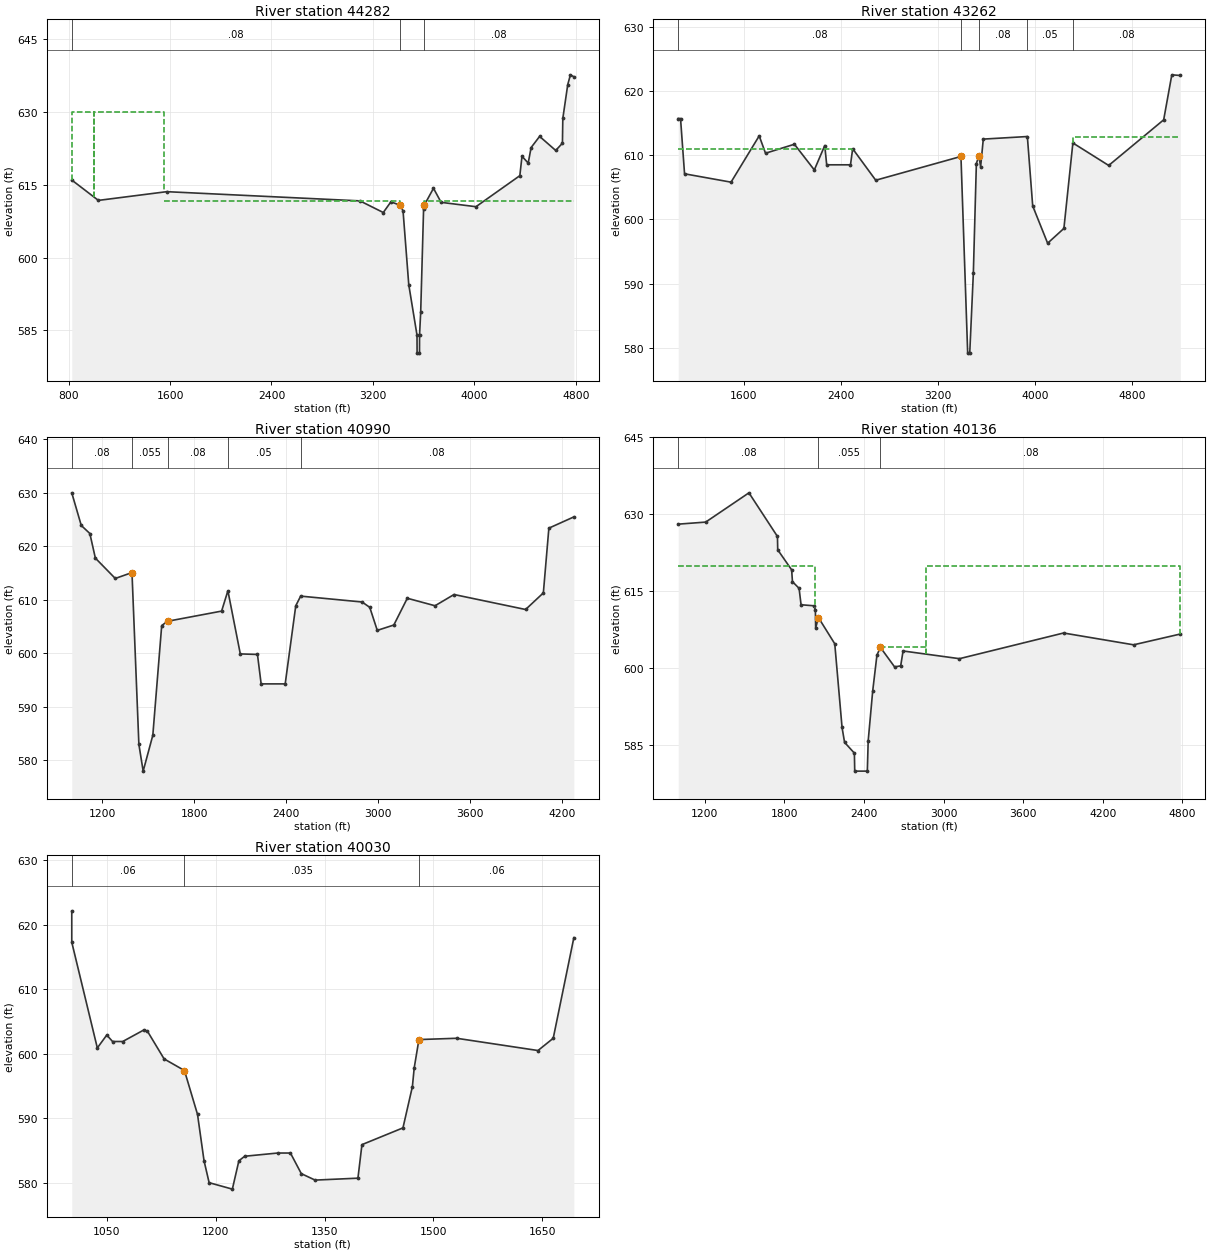
Type RM Length L Ch R = 1 ,44282   ,999,1020.3,1016.7
BEGIN DESCRIPTION:
This cross section corresponds to cross section 44342 of the non-georeferenced CDC model which was the source of this model.
Cross-section modified by USACE February 2007 - blocked obstruction in LOB changed to ineffective flow.
Effective flow limit set at sta 1550 in LOB.
Channel data from 1975 USACE field survey.
END DESCRIPTION:
XS GIS Cut Line= 3
     2295622.839     6934847.758     2295795.582      6934882.48
   2299551.85238   6935339.42632
#Sta/Elev= 30
     825     616    1035   611.8    1574   613.6    3098   611.7    3282   609.3
    3342   611.5    3416   610.8    3438   609.6    3483   594.4    3548     584
 3548.62   580.3 3567.62   580.3    3568     584    3577   588.7    3600   610.1
    3605   610.8    3678   614.3    3738   611.4    4013   610.5    4359   616.9
    4376   620.9    4425   619.5    4448   622.7    4515     625    4642   622.1
    4695   623.6    4698   628.7    4737   635.7    4758   637.7    4785   637.3
#Mann= 3 ,0,0
     825     .08       0    3416    .055       0    3605     .08       0
#XS Ineff= 4 ,-1
     825    1000     630    1000    1550     630    1550    3416   611.7
    3605    4785   611.7
Permanent Ineff=
       F       F       F       F
Bank Sta=3416,3605
XS Rating Curve= 0 ,0
Exp/Cntr=0.3,0.1

Type RM Length L Ch R = 1 ,43262   ,2300.5,2271.6,2041.6
BEGIN DESCRIPTION:
This cross section corresponds to cross section 43324 of the non-georeferenced CDC model which was the source of this model.
Cross-section modified by USACE February 2007 - n value established for swale in ROB.
Channel data from 1975 USACE field survey.
END DESCRIPTION:
XS GIS Cut Line= 4
2296227.922348656937015.32448816   2296778.68994   6936013.50995
   2298343.33904   6936188.58014 2299503.9428611 6935373.2690315
#Sta/Elev= 30
    1062   615.7    1081   615.7    1114   607.1    1497   605.8    1729     613
    1781   610.3    2019   611.7    2183   607.7    2269   611.5    2285   608.5
    2481   608.5    2499     611    2689   606.1    3391   609.8 3446.38   579.2
 3463.38   579.2    3493   591.6    3518   608.7    3539   609.9    3553   608.2
    3575   612.5    3938   612.9    3982   602.1    4105   596.3    4239   598.6
    4313   611.9    4608   608.4    5061   615.5    5128   622.5    5198   622.4
#Mann= 5 ,-1,0
    1062     .08       0    3391    .055       0    3539     .08       0
    3938     .05       0    4313     .08       0
#XS Ineff= 3 ,-1
    1062    2495     611    2495    3391   609.8    4313    5198   612.9
Permanent Ineff=
       F       F       F
Bank Sta=3391,3539
XS Rating Curve= 0 ,0
Exp/Cntr=0.3,0.1

Type RM Length L Ch R = 1 ,40990   ,754.9,853.9,867.7
BEGIN DESCRIPTION:
This cross section corresponds to cross section 41045 of the non-georeferenced CDC model which was the source of this model.
Cross-section modified by USACE February 2007.
Approx. 500 feet downstream of left bank of Mary's Creek. Channel data from 1975 USACE field survey.
END DESCRIPTION:
XS GIS Cut Line= 3
   2298496.96997   6938365.66108   2298545.68707   6937415.72991
     2299929.661   6935546.92492
#Sta/Elev= 30
    1000     630    1062   623.9    1118   622.4    1154   617.8    1284     614
    1393   615.1    1438     583    1466     578    1529   584.7    1587   605.2
    1625     606    1978   607.9    2019   611.7    2100   599.9    2212   599.8
    2236   594.3    2393   594.3    2462   608.9    2494   610.7    2895   609.6
    2945   608.6    2994   604.3    3102   605.3    3190   610.3    3371   608.9
    3495     611    3962   608.2    4078   611.3    4114   623.4    4277   625.5
#Mann= 5 ,-1,0
    1000     .08       0    1393    .055       0    1625     .08       0
    2019     .05       0    2494     .08       0
#XS Ineff= 2 , 0
            1393   615.1    1625           597.5
Permanent Ineff=
       F       F
Bank Sta=1393,1625
XS Rating Curve= 0 ,0
Exp/Cntr=0.3,0.1

Type RM Length L Ch R = 1 ,40136   ,96.2,105.9,100.1
BEGIN DESCRIPTION:
This cross section corresponds to cross section 40178 of the non-georeferenced CDC model which was the source of this model.
Cross-section modified by USACE February 2007. Effective flow set at sta 2030 in LOB, at sta 2870 in ROB.
END DESCRIPTION:
XS GIS Cut Line= 6
      2298397.21   6938946.20093   2299518.00992   6937653.98206
   2300294.94997   6936799.31513   2300648.71993   6936500.80195
   2300867.35795   6936348.04504   2301029.37403   6936250.21912
#Sta/Elev= 30
    1000   628.1    1207   628.5    1533   634.2    1748   625.7    1750   623.1
    1855   619.2    1861   616.9    1911   615.6    1926   612.4    2024   612.2
    2034   611.4    2036   607.9    2057   609.9    2180   604.8    2235   588.5
    2254   585.6    2328   583.5  2330.5     580  2425.5     580    2432   585.9
    2466   595.6    2498   602.6    2524   604.1    2631   600.3    2677   600.5
    2695   603.4    3120   601.9    3905   606.9    4433   604.6    4785   606.7
#Mann= 3 ,0,0
    1000     .08       0    2057    .055       0    2524     .08       0
#XS Ineff= 4 ,-1
    1000    2030     620    2030    2057   609.9    2524    2870   604.1
    2870    4785     620
Permanent Ineff=
       F       F       F       F
Bank Sta=2057,2524
XS Rating Curve= 0 ,0
Exp/Cntr=0.5,0.3

Type RM Length L Ch R = 1 ,40030   ,97.1,100.7,102.9
BEGIN DESCRIPTION:
This cross section corresponds to cross section 40064 of the non-georeferenced CDC model which was the source of this model.
Duplication of previous bridge cross-section without bridge piers.
One-foot upstream of S.H. 183 - Southwest Boulevard.
END DESCRIPTION:
XS GIS Cut Line= 2
     2299179.361     6938186.4732299632.674345646937664.15353711
#Sta/Elev= 30
  1001.8  622.17  1001.8   617.3    1037   600.9    1050   602.9    1058   601.9
    1072   601.9 1101.25   603.7    1106   603.5    1129   599.2    1157   597.4
    1175   590.6    1184   583.4    1191     580    1223     579    1232   583.4
    1240   584.1  1285.5   584.6    1303   584.6    1318   581.4    1337   580.4
    1396   580.7  1401.5   585.9    1458   588.5    1471   594.9  1473.5   597.8
    1480   602.2    1532   602.4    1644   600.5    1665   602.4  1693.4     618
#Mann= 3 ,0,0
  1001.8     .06       0    1157    .035       0    1480     .06       0
Bank Sta=1157,1480
XS Rating Curve= 0 ,0
Exp/Cntr=0.5,0.3