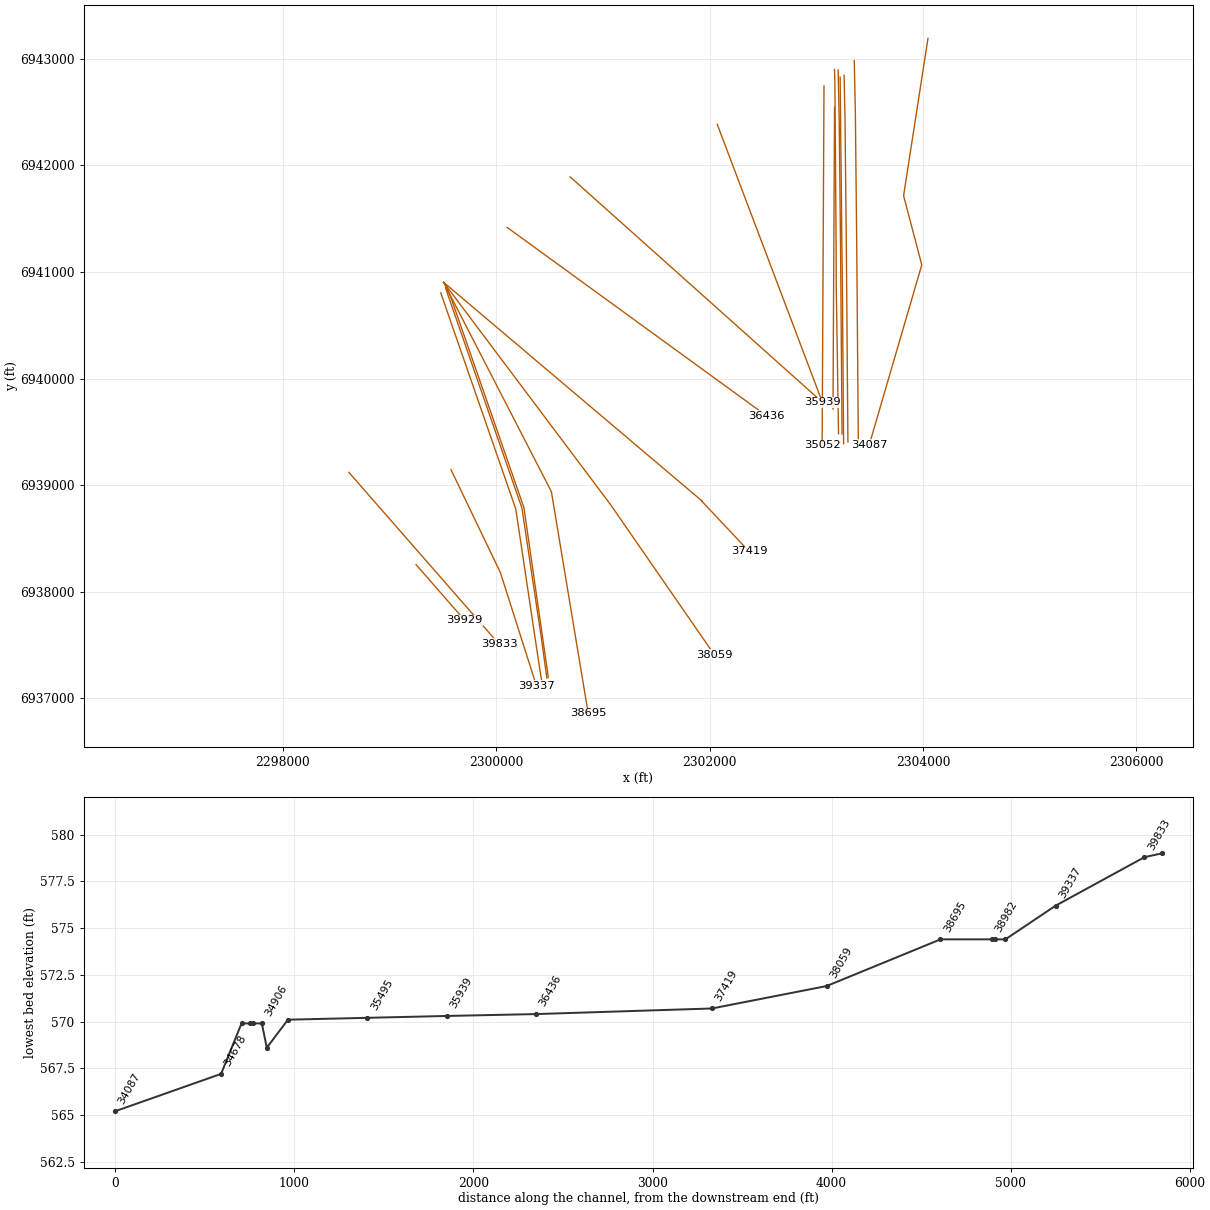
HEC-RAS study CDC_Consolidated_Model.prj: Upper Trinity CDC Consolidated Model

--- CDC_Consolidated_Model.g11 (geometry) --- (continued)

Type RM Length L Ch R = 3 ,39980   ,,,
BEGIN DESCRIPTION:
SH 183/Southwest Boulevard
Bridge data from 1975 survey.  Minimum low chord elev. 614.77.  Bridge width 85 feet.
Channel data from 1975 USACE field survey.
END DESCRIPTION:
Node Name=SH 183
Bridge Culvert--1,0,-1,-1, 0
Deck Dist Width WeirC Skew NumUp NumDn MinLoCord MaxHiCord MaxSubmerge Is_Ogee
7.5,85,2.6,0, 22, 22, , , 0.95, 0, 0,0,,
  1001.8 1098.75 1101.25    1106    1161  1163.5    1205    1223  1225.5  1285.5
    1288 1346.75 1349.25    1399  1401.5    1471  1473.5    1594  1596.5    1644
  1646.5  1693.4
  622.17   621.7  621.68  621.66  621.37  621.35  621.14  621.05  621.04  620.77
  620.76  620.48  620.46  620.22  620.21  619.83  619.82   619.2  619.19  618.62
  618.59     618
  618.37  617.96  617.95  617.93  617.64  617.63  617.42  617.33  617.31     617
  616.99  616.69  616.68  616.42  616.41  616.05  616.04  615.42   615.4  614.81
  614.77  614.35
  1001.8 1098.75 1101.25    1106    1161  1163.5    1205    1223  1225.5  1285.5
    1288 1346.75 1349.25    1399  1401.5    1471  1473.5    1594  1596.5    1644
  1646.5  1693.4
  622.17   621.7  621.68  621.66  621.37  621.35  621.14  621.05  621.04  620.77
  620.76  620.48  620.46  620.22  620.21  619.83  619.82   619.2  619.19  618.62
  618.59     618
  618.37  617.96  617.95  617.93  617.64  617.63  617.42  617.33  617.31     617
  616.99  616.69  616.68  616.42  616.41  616.05  616.04  615.42   615.4  614.81
  614.77  614.35
Pier Skew, UpSta & Num, DnSta & Num=  ,1100, 2 ,1100, 2 , 0 , 0 , 0 ,,
     2.5     2.5
     600     620
     2.5     2.5
     600     620
Pier Skew, UpSta & Num, DnSta & Num=  ,1162.25, 2 ,1162.25, 2 , 0 , 0 , 0 ,,
     2.5     2.5
     570     620
     2.5     2.5
     570     620
Pier Skew, UpSta & Num, DnSta & Num=  ,1224.25, 2 ,1224.25, 2 , 0 , 0 , 0 ,,
     2.5     2.5
     570     620
     2.5     2.5
     570     620
Pier Skew, UpSta & Num, DnSta & Num=  ,1286.75, 2 ,1286.75, 2 , 0 , 0 , 0 ,,
     2.5     2.5
     570     620
     2.5     2.5
     570     620
Pier Skew, UpSta & Num, DnSta & Num=  ,1348, 2 ,1348, 2 , 0 , 0 , 0 ,,
     2.5     2.5
     570     620
     2.5     2.5
     570     620
Pier Skew, UpSta & Num, DnSta & Num=  ,1400.25, 2 ,1400.25, 2 , 0 , 0 , 0 ,,
     2.5     2.5
     570     619
     2.5     2.5
     570     619
Pier Skew, UpSta & Num, DnSta & Num=  ,1472.25, 2 ,1472.25, 2 , 0 , 0 , 0 ,,
     2.5     2.5
     570     619
     2.5     2.5
     570     619
Pier Skew, UpSta & Num, DnSta & Num=  ,1645.25, 2 ,1645.25, 2 , 0 , 0 , 0 ,,
     2.5     2.5
     570     618
     2.5     2.5
     570     618
BR Coef=-1 , 0 , 0 ,1.05, 0 ,,,0.8,-1,0.5,1,
WSPro=,,,, 1 ,,,, 0 ,,,, 0 ,,,,-1 ,-1 ,-1 , 0 , 0 , 0 , 0 , 0
BC Design=,, 0 ,, 0 ,,,,,,
BC HTab HWMax=622.17
BC Use User HTab Curves=0
BC User HTab FreeFlow(D)= 0

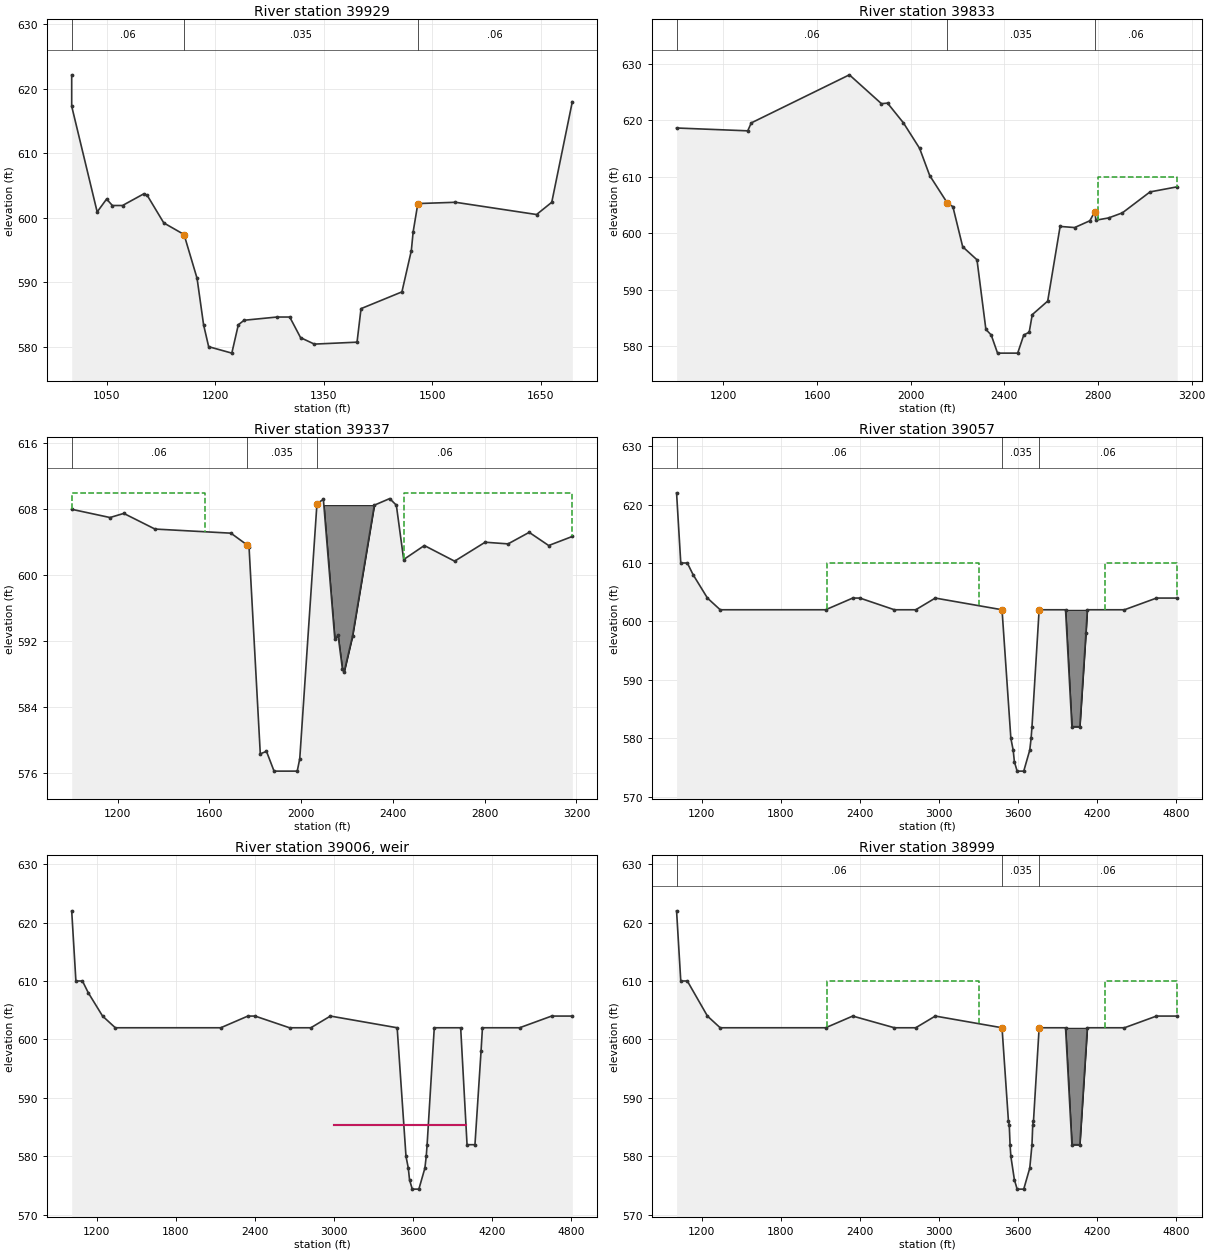
Type RM Length L Ch R = 1 ,39929   ,95.9,96.3,99.7
BEGIN DESCRIPTION:
This cross section corresponds to cross section 39977 of the non-georeferenced CDC model which was the source of this model.
Duplication of following bridge cross-section without bridge piers.
Upstream end of Fort Worth Floodway.
Channel data from 1975 USACE field survey.
END DESCRIPTION:
XS GIS Cut Line= 2
2299248.380017766938253.76990765 2299703.3820877 6937732.9208633
#Sta/Elev= 30
  1001.8  622.17  1001.8   617.3    1037   600.9    1050   602.9    1058   601.9
    1072   601.9 1101.25   603.7    1106   603.5    1129   599.2    1157   597.4
    1175   590.6    1184   583.4    1191     580    1223     579    1232   583.4
    1240   584.1  1285.5   584.6    1303   584.6    1318   581.4    1337   580.4
    1396   580.7  1401.5   585.9    1458   588.5    1471   594.9  1473.5   597.8
    1480   602.2    1532   602.4    1644   600.5    1665   602.4  1693.4     618
#Mann= 3 ,0,0
  1001.8     .06       0    1157    .035       0    1480     .06       0
Bank Sta=1157,1480
XS Rating Curve= 0 ,0
Exp/Cntr=0.5,0.3

Type RM Length L Ch R = 1 ,39833   ,538.1,496.5,474.4
BEGIN DESCRIPTION:
This cross section corresponds to cross section 39879 of the non-georeferenced CDC model which was the source of this model.
Cross-section modified by USACE February 2007.  Effective  in LOB set at sta 2050, in ROB set at sta 2800.
99 feet downstream of S.H. 183 - Southwest Boulevard.
Channel data from 1975 USACE field survey.
END DESCRIPTION:
XS GIS Cut Line= 5
   2298618.45398   6939119.50899   2298788.15213   6938925.26889
   2299301.79513   6938337.33601   2299792.84107    6937775.2269
 2300025.2667818 6937509.5644535
#Sta/Elev= 30
    1000   618.6    1304   618.1    1319   619.5    1738     628    1875   622.9
    1901     623    1969   619.5    2038     615    2081   610.2    2157   605.3
    2180   604.7    2222   597.6    2283   595.3    2321     583 2343.81     582
 2370.81   578.8 2456.81   578.8 2482.81     582    2506   582.5    2519   585.6
    2585     588    2638   601.2    2700     601    2765   602.2    2786   603.8
    2791   602.3    2845   602.7    2904   603.6    3022   607.3    3138   608.2
#Mann= 3 ,0,0
    1000     .06       0    2157    .035       0    2786     .06       0
#XS Ineff= 4 ,-1
    1000    2050     610    2050    2157   605.3    2786    2800   603.8
    2800    3138     610
Permanent Ineff=
       F       F       F       F
Bank Sta=2157,2786
XS Rating Curve= 0 ,0
Exp/Cntr=0.3,0.1

Type RM Length L Ch R = 1 ,39337   ,320,280,247
BEGIN DESCRIPTION:
This cross section corresponds to cross section 39380 of the non-georeferenced CDC model which was the source of this model.
Cross-section modified by USACE February 2007.  Effective  in LOB set at sta 1580, in ROB set at sta 2450.  Old river channel in ROB.  Channel data from 1975 USACE field survey.
Note:  Channel dam indicated on 1991 topography has been removed by the TRWD after construction of the new downstream channel dam and during the completion of the original CDC Model.
END DESCRIPTION:
XS GIS Cut Line= 3
   2299575.70305   6939144.79109   2300039.24313   6938178.48396
    2300375.7546   6937120.47394
#Sta/Elev= 30
    1000     608    1167     607    1227   607.5    1363   605.6    1694   605.1
    1763   603.7    1773   603.4    1822   578.3    1849   578.6    1882   576.2
    1983   576.2    1994   577.7    2069   608.7    2097   609.2    2147   592.2
    2161   592.7    2180   588.6    2187   588.2    2224   592.6    2319   608.5
    2386   609.3    2415   608.5    2447   601.9    2537   603.6    2669   601.7
    2802     604    2902   603.8    2994   605.2    3079   603.6    3182   604.7
#Mann= 3 ,0,0
    1000     .06       0    1763    .035       0    2069     .06       0
#XS Ineff= 2 , 0
            1580     610    2450             610
Permanent Ineff=
       F       F
#Block Obstruct= 1 ,-1
    2097    2319   608.5
Bank Sta=1763,2069
XS Rating Curve= 0 ,0
Exp/Cntr=0.3,0.1

Type RM Length L Ch R = 1 ,39057   ,58,58,58
XS GIS Cut Line= 4
  2299479.566364 6940803.2307766 2300183.0383354 6938775.8264183
      2300405.25      6937290.92       2300429.4     6937142.698
#Sta/Elev= 30
  1009.4     622  1041.3     610    1091     610  1134.8     608  1243.6     604
  1340.3     602  2140.2     602  2345.8     604  2400.2     604  2661.8     602
  2823.7     602  2971.9     604  3478.3     602  3545.3     580  3562.8     578
  3572.1     576    3593   574.4    3643   574.4  3688.7     578  3698.8     580
  3705.5     582  3759.8     602  3960.1     602  4008.4     582  4068.4     582
  4114.7     598  4125.3     602    4407     602    4650     604    4807     604
#Mann= 3 ,0,0
  1009.4     .06       0  3478.3    .035       0  3759.8     .06       0
#XS Ineff= 5 ,-1
  1009.4    2150     602    2150    3300     610    3300  3478.3     602
  3759.8    4260     602    4260    4807     610
Permanent Ineff=
       F       F       F       F       F
#Block Obstruct= 1 ,-1
 3960.12  4125.3     602
Bank Sta=3478.3,3759.8
XS Rating Curve= 0 ,0
Exp/Cntr=0.3,0.1

Type RM Length L Ch R = 5 ,39006   ,,,
BEGIN DESCRIPTION:
Cityview Dam
Data from plans.  Crest elevation 585.4, width 12 feet.
END DESCRIPTION:
Node Name=Cityview Dam
IW Pilot Flow=0
#Inline Weir SE= 2
    3000   585.4    4000   585.4
IW Dist,WD,Coef,Skew,MaxSub,Min_El,Is_Ogee,SpillHt,DesHd
33,12,3,0,0.95,, 0 ,,,2,2,
Inline Weir Flap Gates= 0
IW Outlet Rating Curve= 0 ,False,,

Type RM Length L Ch R = 1 ,38999   ,17.7,16.8,16.3
BEGIN DESCRIPTION:
This cross section corresponds to cross section 39055 of the non-georeferenced CDC model which was the source of this model.
One-foot downstream of Cityview Dam.
Cross-section modified by USACE February 2007.
Ineffective flow in LOB due to group of structures, effective flow in ROB set at sta 4260.
Old river channel in ROB.
Channel data from 1975 USACE field survey.
END DESCRIPTION:
XS GIS Cut Line= 4
2299524.272482346940850.03415726   2300240.39496   6938786.17107
   2300421.66396   6937574.60689      2300474.54      6937190.25
#Sta/Elev= 30
  1009.4     622  1041.3     610    1091     610  1243.6     604  1340.3     602
  2140.2     602  2345.8     604  2661.8     602  2823.7     602  2971.9     604
  3478.3     602    3527     586  3533.1   585.4  3539.2     582  3545.3     580
  3572.1     576    3593   574.4    3643   574.4  3688.7     578  3705.5     582
  3711.2   585.4  3716.8     586  3759.8     602  3960.1     602  4008.4     582
  4068.4     582  4125.3     602    4407     602    4650     604    4807     604
#Mann= 3 ,0,0
  1009.4     .06       0  3478.3    .035       0  3759.8     .06       0
#XS Ineff= 5 ,-1
  1009.4    2150     602    2150    3300     610    3300  3478.3     602
  3759.8    4260     602    4260    4807     610
Permanent Ineff=
       F       F       F       F       F
#Block Obstruct= 1 ,-1
 3960.12  4125.3     602
Bank Sta=3478.3,3759.8
XS Rating Curve= 0 ,0
Exp/Cntr=0.3,0.1

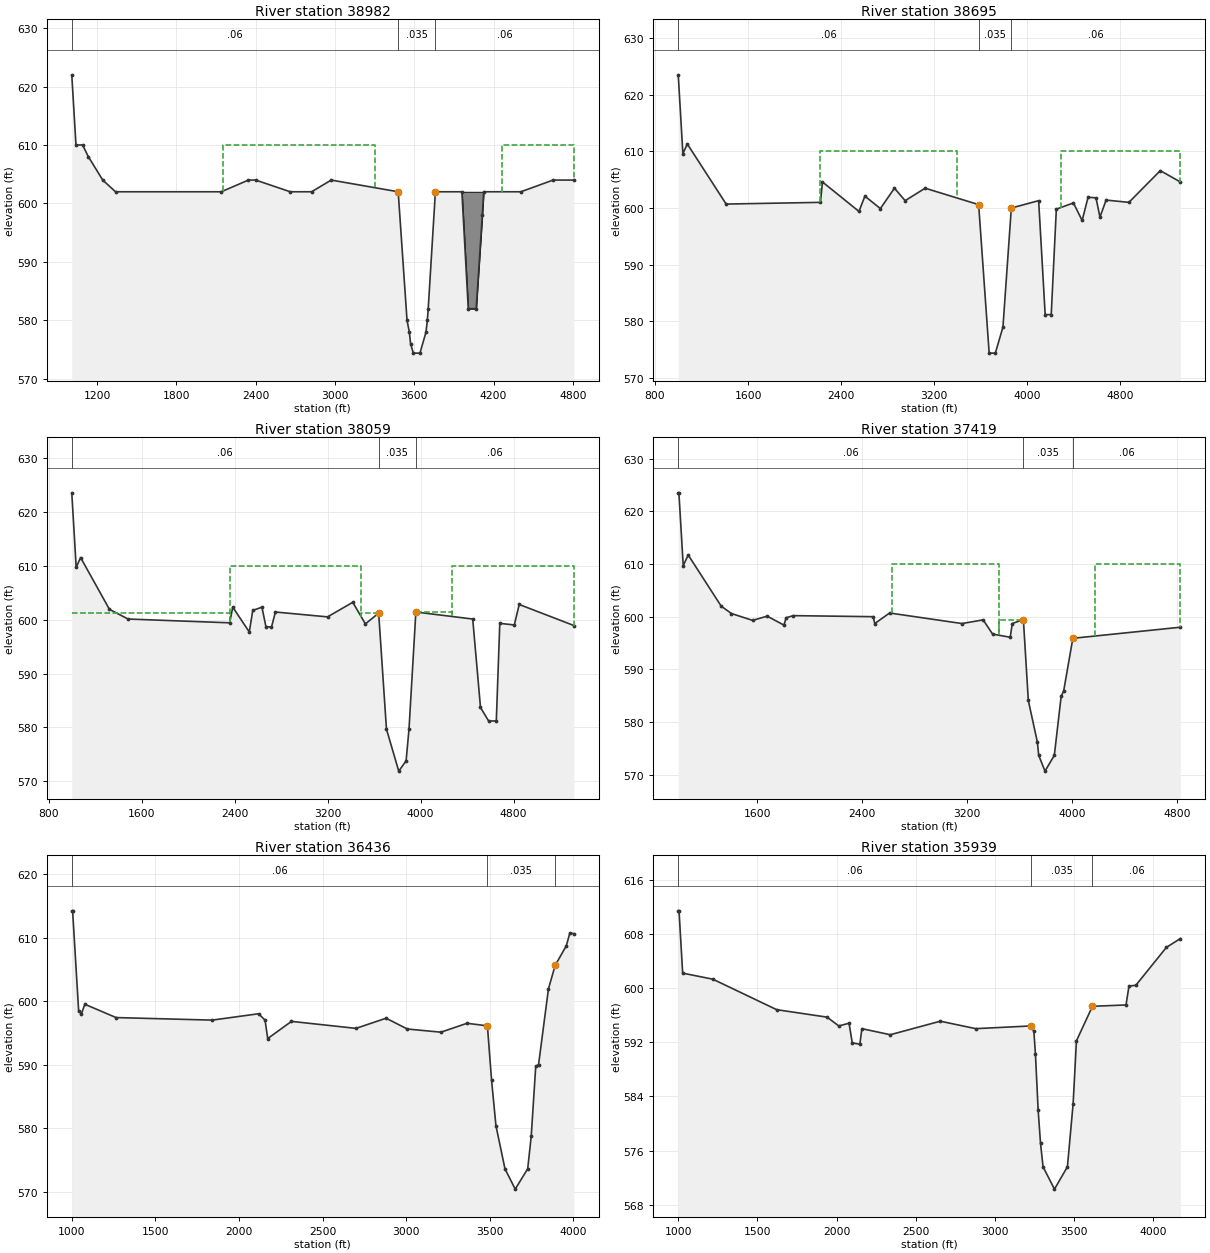
Type RM Length L Ch R = 1 ,38982   ,285.9,287.5,291
BEGIN DESCRIPTION:
This cross section corresponds to cross section 39023 of the non-georeferenced CDC model which was the source of this model.
Cross-section modified by USACE February 2007.
39 feet downstream of Cityview Dam.  Ineffective flow in LOB due to group of structures, effective flow in ROB set at sta 4260.
Old river channel in ROB.
Channel data from 1975 USACE field survey.
END DESCRIPTION:
XS GIS Cut Line= 4
2299530.905865176940852.77955862      2299570.13      6940774.24
 2300259.3457513 6938788.5749798      2300487.99      6937196.98
#Sta/Elev= 30
  1009.4     622  1041.3     610    1091     610  1134.8     608  1243.6     604
  1340.3     602  2140.2     602  2345.8     604  2400.2     604  2661.8     602
  2823.7     602  2971.9     604  3478.3     602  3545.3     580  3562.8     578
  3572.1     576    3593   574.4    3643   574.4  3688.7     578  3698.8     580
  3705.5     582  3759.8     602  3960.1     602  4008.4     582  4068.4     582
  4114.7     598  4125.3     602    4407     602    4650     604    4807     604
#Mann= 3 ,0,0
  1009.4     .06       0  3478.3    .035       0  3759.8     .06       0
#XS Ineff= 5 ,-1
  1009.4    2150     602    2150    3300     610    3300  3478.3     602
  3759.8    4260     602    4260    4807     610
Permanent Ineff=
       F       F       F       F       F
#Block Obstruct= 1 ,-1
 3960.12  4125.3     602
Bank Sta=3478.3,3759.8
XS Rating Curve= 0 ,0
Exp/Cntr=0.3,0.1

Type RM Length L Ch R = 1 ,38695   ,574.5,636,683.1
BEGIN DESCRIPTION:
This cross section corresponds to cross section 38738 of the non-georeferenced CDC model which was the source of this model.
Cross-section modified by USACE February 2007.
Ineffective flow in LOB due to group of structures, effective flow in ROB set at sta 4290.
Old river channel in ROB.
Channel data from 1975 USACE field survey.
END DESCRIPTION:
XS GIS Cut Line= 3
   2299505.98206   6940902.74689   2300516.75005   6938938.63894
   2300862.11911   6936859.02007
#Sta/Elev= 30
    1000   623.5    1040   609.6    1078   611.3    1412   600.7    2223     601
    2240   604.6    2554   599.4    2605   602.1    2738   599.9    2859   603.5
    2951   601.3    3123   603.5    3583   600.6 3673.51   574.4 3726.51   574.4
    3792     579    3864     600    4099   601.3    4155   581.2    4207   581.2
    4251   599.8    4398   600.9    4473   597.8    4524   601.9    4592   601.8
    4626   598.4    4679   601.4    4875     601    5145   606.6    5317   604.6
#Mann= 3 ,0,0
    1000     .06       0    3583    .035       0    3864     .06       0
#XS Ineff= 5 ,-1
    1000    2220   600.6    2220    3400     610    3400    3583   600.6
    3864    4290     600    4290    5317     610
Permanent Ineff=
       F       F       F       F       F
#Block Obstruct= 2 , 0
                            4099           601.3
Bank Sta=3583,3864
XS Rating Curve= 0 ,0
Exp/Cntr=0.3,0.1

Type RM Length L Ch R = 1 ,38059   ,596.7,640.2,667.6
BEGIN DESCRIPTION:
This cross section corresponds to cross section 38091 of the non-georeferenced CDC model which was the source of this model.
Cross-section modified by USACE February 2007.
Ineffective flow in LOB due to group of structures, effective flow in ROB set at sta 4270.
Old river channel in ROB.
Channel data from 1975 USACE field survey.
END DESCRIPTION:
XS GIS Cut Line= 3
    2299506.1169    6940902.5671   2301072.22401   6938816.13295
   2302044.02292   6937409.74206
#Sta/Elev= 30
    1000   623.5    1038   609.7    1076   611.5    1324   601.9    1484   600.1
    2358   599.4    2385   602.3    2527   597.7    2557   601.7    2636   602.3
    2670   598.7    2718   598.6    2752   601.4    3200   600.5    3417   603.2
    3526   599.2    3640   601.2    3707   579.7 3812.69   571.9    3876   573.8
    3901   579.7    3960   601.4    4449   600.1    4516   583.7    4586   581.2
    4652   581.2    4682   599.3    4807     599    4849   602.8    5319   598.9
#Mann= 3 ,0,0
    1000     .06       0    3640    .035       0    3960     .06       0
#XS Ineff= 5 ,-1
    1000    2360   601.2    2360    3490     610    3490    3640   601.2
    3960    4270   601.4    4270    5319     610
Permanent Ineff=
       F       F       F       F       F
#Block Obstruct= 2 , 0
                            4449           600.1
Bank Sta=3640,3960
XS Rating Curve= 0 ,0
Exp/Cntr=0.3,0.1

Type RM Length L Ch R = 1 ,37419   ,973,982.3,986.1
BEGIN DESCRIPTION:
This cross section corresponds to cross section 37449 of the non-georeferenced CDC model which was the source of this model.
Cross-section modified by USACE February 2007.
Ineffective flow in LOB due to group of structures.
Lockheed Recreation Area in ROB.
Channel data from 1975 USACE field survey.
END DESCRIPTION:
XS GIS Cut Line= 4
   2299506.17596   6940902.58285   2301929.37091   6938851.04594
     2301925.292     6938850.987     2302370.605     6938378.331
#Sta/Elev= 30
    1000   623.5    1005   623.5    1038   609.7    1076   611.7    1327     602
    1405   600.6    1566   599.3    1677   600.1    1805   598.4    1821   599.8
    1876   600.2    2484     600    2496   598.7    2609   600.7    3160   598.7
    3321   599.4    3393   596.7    3527   596.1    3543   598.7    3621   599.4
    3628   599.2    3665   584.1    3734   576.2    3744   573.7 3792.04   570.7
    3863   573.7    3915   584.9    3934   585.9    4004   595.9    4822     598
#Mann= 3 ,0,0
    1000     .06       0    3621    .035       0    4004     .06       0
#XS Ineff= 5 ,-1
    1000    2630   599.4    2630    3440     610    3440    3621   599.4
    4004    4175   595.9    4175    4822     610
Permanent Ineff=
       F       F       F       F       F
Bank Sta=3621,4004
XS Rating Curve= 0 ,0
Exp/Cntr=0.3,0.1

Type RM Length L Ch R = 1 ,36436   ,510,497.7,480
BEGIN DESCRIPTION:
This cross section corresponds to cross section 36466 of the non-georeferenced CDC model which was the source of this model.
Channel data from 1975 USACE field survey.
END DESCRIPTION:
XS GIS Cut Line= 2
   2300102.25187   6941417.19993   2302531.11905   6939651.87898
#Sta/Elev= 30
    1000   614.2    1005   614.2    1041   598.5    1058     598    1078   599.5
    1265   597.4    1840     597    2117     598    2156     597    2172   594.1
    2314   596.8    2700   595.7    2880   597.3    3007   595.6    3208   595.1
    3364   596.5    3486   596.1    3511   587.5    3537   580.4    3591   573.6
 3652.28   570.4    3727   573.6    3748   578.7    3775   589.7    3792     590
    3851   601.9    3891   605.6    3958   608.7    3979   610.7    4003   610.6
#Mann= 3 ,0,0
    1000     .06       0    3486    .035       0    3891     .06       0
Bank Sta=3486,3891
XS Rating Curve= 0 ,0
Exp/Cntr=0.3,0.1

Type RM Length L Ch R = 1 ,35939   ,521,444,385.3
BEGIN DESCRIPTION:
This cross section corresponds to cross section 35969 of the non-georeferenced CDC model which was the source of this model.
Channel data from 1975 USACE field survey.
END DESCRIPTION:
XS GIS Cut Line= 2
    2300693.3081   6941891.10515    2303057.2768   6939777.65334
#Sta/Elev= 30
    1000   611.4    1005   611.4    1028   602.2    1219   601.3    1622   596.8
    1940   595.7    2014   594.4    2079   594.8    2099   591.9    2147   591.7
    2160     594    2339   593.1    2655   595.1    2879     594    3227   594.4
    3246   593.6    3256   590.3    3273     582    3288   577.1    3304   573.6
 3376.18   570.3    3458   573.6    3494   582.9    3515   592.2    3616   597.3
    3828   597.5    3847   600.3    3890   600.4    4083     606    4171   607.3
#Mann= 3 ,0,0
    1000     .06       0    3227    .035       0    3616     .06       0
Bank Sta=3227,3616
XS Rating Curve= 0 ,0
Exp/Cntr=0.3,0.1

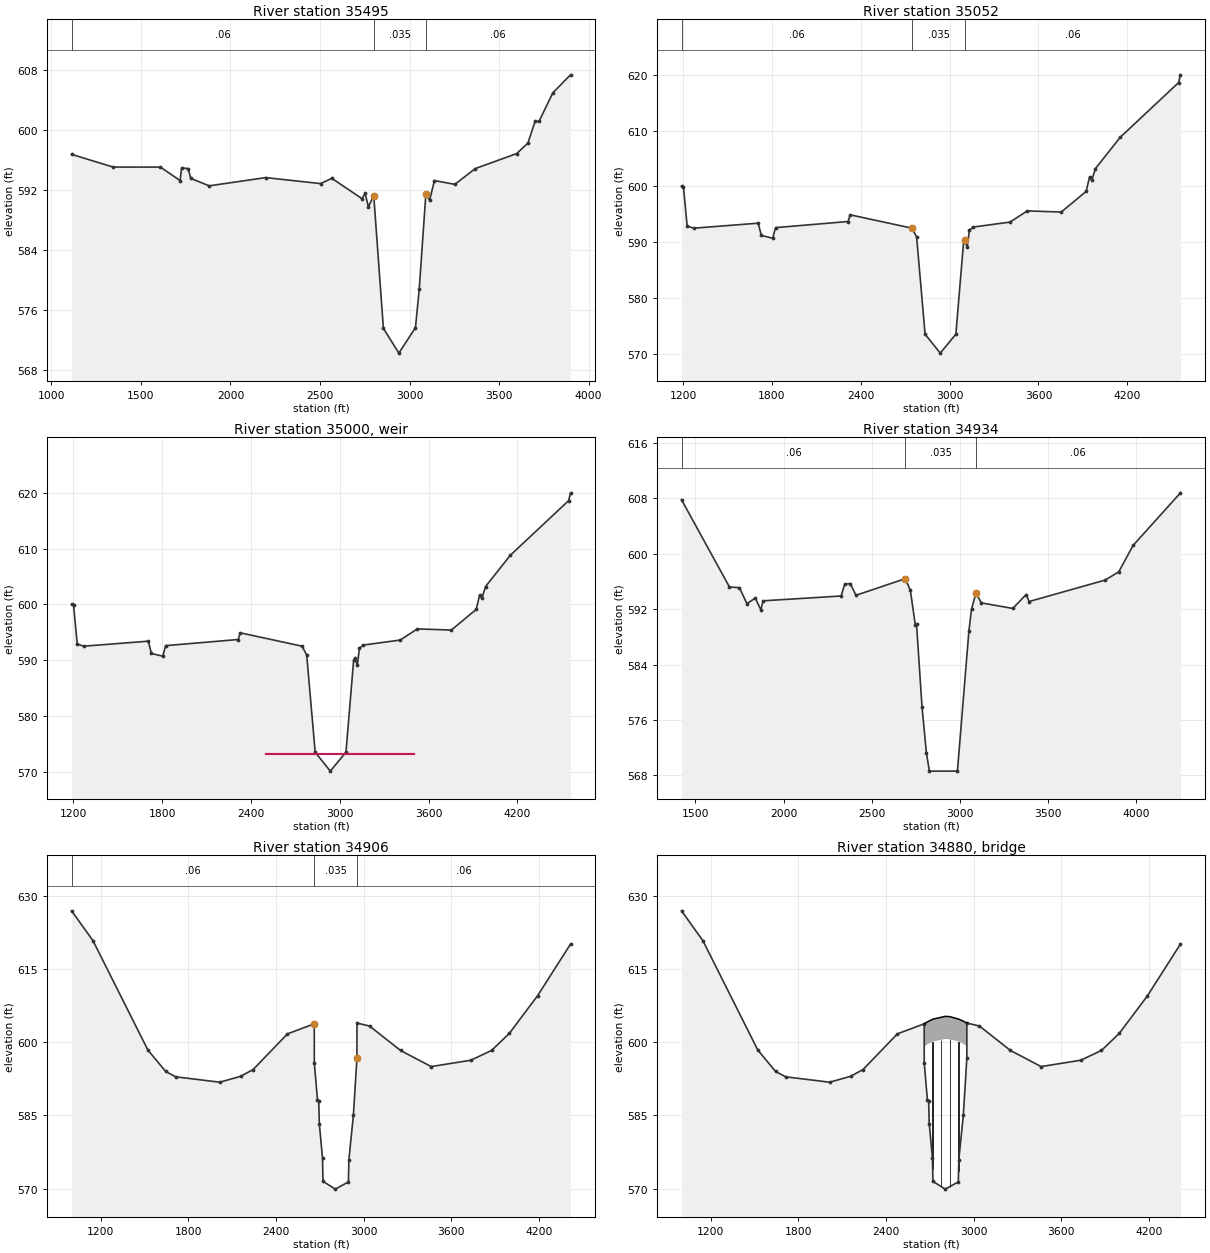
Type RM Length L Ch R = 1 ,35495   ,508.6,443,395.8
BEGIN DESCRIPTION:
This cross section corresponds to cross section 35519 of the non-georeferenced CDC model which was the source of this model.
Channel data from 1975 USACE field survey.
END DESCRIPTION:
XS GIS Cut Line= 2
2302071.995496046942383.72166837   2303057.27811   6939777.76423
#Sta/Elev= 30
    1113   596.7    1345     595    1609     595    1719   593.2    1727   594.9
    1764   594.8    1778   593.5    1881   592.5    2197   593.6    2503   592.8
    2566   593.5    2734   590.8    2752   591.5    2770   589.7    2800   591.2
    2854   573.5  2940.3   570.2    3033   573.6    3054   578.7    3091   591.4
    3112   590.6    3139   593.2    3253   592.7    3367   594.8    3598   596.8
    3661   598.2    3701   601.1    3723   601.1    3800   604.9    3899   607.3
#Mann= 3 ,0,0
    1113     .06       0    2800    .035       0    3091     .06       0
Bank Sta=2800,3091
XS Rating Curve= 0 ,0
Exp/Cntr=0.3,0.1

Type RM Length L Ch R = 1 ,35052   ,109.3,118.2,122.7
BEGIN DESCRIPTION:
This cross section corresponds to cross section 35076 of the non-georeferenced CDC model which was the source of this model.
50 feet upstream of channel dam.
Channel data from 1975 USACE field survey.
END DESCRIPTION:
XS GIS Cut Line= 4
2303072.729449086942743.06528603   2303057.34208   6939777.59494
 2303055.4949284 6939421.6380934      2303055.49      6939373.11
#Sta/Elev= 30
    1189     600    1202   599.9    1227   592.9    1270   592.5    1707   593.4
    1728   591.2    1805   590.7    1824   592.6    2314   593.7    2328   594.9
    2746   592.5    2777   590.9    2834   573.5 2936.39   570.1    3042   573.5
    3094     590    3103   590.3    3119   589.1    3133   592.1    3158   592.7
    3408   593.6    3524   595.6    3754   595.4    3922   599.1    3945   601.7
    3960   601.1    3985   603.2    4152   608.8    4546   618.6    4559     620
#Mann= 3 ,0,0
    1189     .06       0    2746    .035       0    3103     .06       0
Bank Sta=2746,3103
XS Rating Curve= 0 ,0
Exp/Cntr=0.3,0.1

Type RM Length L Ch R = 5 ,35000   ,,,
BEGIN DESCRIPTION:
channel dam
crest elevation 573.2
END DESCRIPTION:
Node Name=channel dam
IW Pilot Flow=0
#Inline Weir SE= 2
    2500   573.2    3500   573.2
IW Dist,WD,Coef,Skew,MaxSub,Min_El,Is_Ogee,SpillHt,DesHd
49.5,5,3,0,0.95,, 0 ,,,2,2,
Inline Weir Flap Gates= 0
IW Outlet Rating Curve= 0 ,False,,

Type RM Length L Ch R = 1 ,34934   ,23.9,27.6,29.6
BEGIN DESCRIPTION:
This cross section corresponds to cross section 34957 of the non-georeferenced CDC model which was the source of this model.
43 feet upstream of Bryant-Irvin Road, 55.5 feet downstream of channel dam.
Channel data from 1975 USACE field survey.
END DESCRIPTION:
XS GIS Cut Line= 3
  2303171.707448 6942545.9068369 2303157.7506186  6939856.216303
2303157.012371286939713.94496309
#Sta/Elev= 30
    1421   607.8    1693   595.2    1750   595.1    1792   592.8    1840   593.6
    1871   591.9    1884   593.2    2327   593.9    2347   595.6    2379   595.7
    2411     594    2691   596.4    2720   594.7    2748   589.7    2755   589.8
    2786   577.9    2811   571.2    2828   568.6    2987   568.6    3052   588.8
    3067     592    3092   594.3    3123   592.9    3301   592.1    3377   594.1
    3394   593.1    3826   596.2    3903   597.4    3984   601.2    4253   608.8
#Mann= 3 ,0,0
    1421     .06       0    2691    .035       0    3092     .06       0
#XS Ineff= 2 , 0
            2691   596.4    3092           594.3
Permanent Ineff=
       F       F
Bank Sta=2691,3092
XS Rating Curve= 0 ,0
Exp/Cntr=0.5,0.3

Type RM Length L Ch R = 1 ,34906   ,46.2,49.7,51.9
BEGIN DESCRIPTION:
This cross section corresponds to cross section 34915 of the non-georeferenced CDC model which was the source of this model.
Duplication of previous bridge cross-section without bridge piers.
One-foot upstream of Bryant-Irvin Road.
Bank stations changed by USACE February 2007.
END DESCRIPTION:
XS GIS Cut Line= 5
      2303171.28      6942898.55  2303174.718485 6942779.8316517
     2303186.522     6941229.008     2303187.607     6940864.424
2303208.961237226939482.81133342
#Sta/Elev= 30
    1000   626.9    1146   620.8    1522   598.4    1644     594    1713   592.9
    2014   591.8    2157     593    2243   594.4    2478   601.7 2661.58  603.76
 2661.58   595.8 2683.39   588.2 2691.78     588 2695.97   583.3 2717.95  576.21
 2721.13   571.5    2805   569.9 2895.23  571.38 2898.23  575.89 2929.12     585
 2953.44   596.7 2953.44  603.92    3040   603.3    3252   598.3    3462     595
    3733   596.3    3875   598.3    3997   601.8    4190   609.5    4416   620.1
#Mann= 3 ,0,0
    1000     .06       0 2661.58    .035       0 2953.44     .06       0
Bank Sta=2661.58,2953.44
XS Rating Curve= 0 ,0
Exp/Cntr=0.5,0.3

Type RM Length L Ch R = 3 ,34880   ,,,
BEGIN DESCRIPTION:
Bryant-Irvin Road - south bound
END DESCRIPTION:
Node Name=Bryant-Irvin Roa
Bridge Culvert--1,0,-1,-1, 0
Deck Dist Width WeirC Skew NumUp NumDn MinLoCord MaxHiCord MaxSubmerge Is_Ogee
8.5,35,2.6,0, 14, 14, , , 0.95, 0, 0,0,,
 2661.58 2683.39 2717.95 2720.95 2721.13 2776.66 2779.66    2805 2835.37 2838.37
 2895.23 2898.23 2929.12    2954
  603.76  604.15  604.66  604.71  604.71  605.09  605.11  605.29  605.23  605.22
  604.74  604.71  604.29  603.92
  599.08  599.57  600.08  600.12  600.12  600.47  600.49  600.65   600.6  600.59
  600.13   600.1  599.67  599.18
 2661.58 2683.39 2717.95 2720.95 2721.13 2776.66 2779.66    2805 2835.37 2838.37
 2895.23 2898.23 2929.12    2954
  603.76  604.15  604.66  604.71  604.71  605.09  605.11  605.29  605.23  605.22
  604.74  604.71  604.29  603.92
  599.08  599.57  600.08  600.12  600.12  600.47  600.49  600.65   600.6  600.59
  600.13   600.1  599.67  599.18
Pier Skew, UpSta & Num, DnSta & Num=  ,2719.45, 2 ,2719.45, 2 , 0 , 0 , 0 ,,
       3       3
     560     602
       3       3
     560     602
Pier Skew, UpSta & Num, DnSta & Num=  ,2778.16, 2 ,2778.16, 2 , 0 , 0 , 0 ,,
       3       3
     560     602
       3       3
     560     602
Pier Skew, UpSta & Num, DnSta & Num=  ,2836.87, 2 ,2836.87, 2 , 0 , 0 , 0 ,,
       3       3
     560     602
       3       3
     560     602
Pier Skew, UpSta & Num, DnSta & Num=  ,2896.73, 2 ,2896.73, 2 , 0 , 0 , 0 ,,
       3       3
     560     602
       3       3
     560     602
BR Coef=-1 , 0 , 0 ,1.05, 0 ,,,0.8,-1,0.5,1,
WSPro=,,,, 1 ,,,, 0 ,,,, 0 ,,,,-1 ,-1 ,-1 , 0 , 0 , 0 , 0 , 0
BC Design=,, 0 ,, 0 ,,,,,,
BC HTab HWMax=626.9
BC Use User HTab Curves=0
BC User HTab FreeFlow(D)= 0

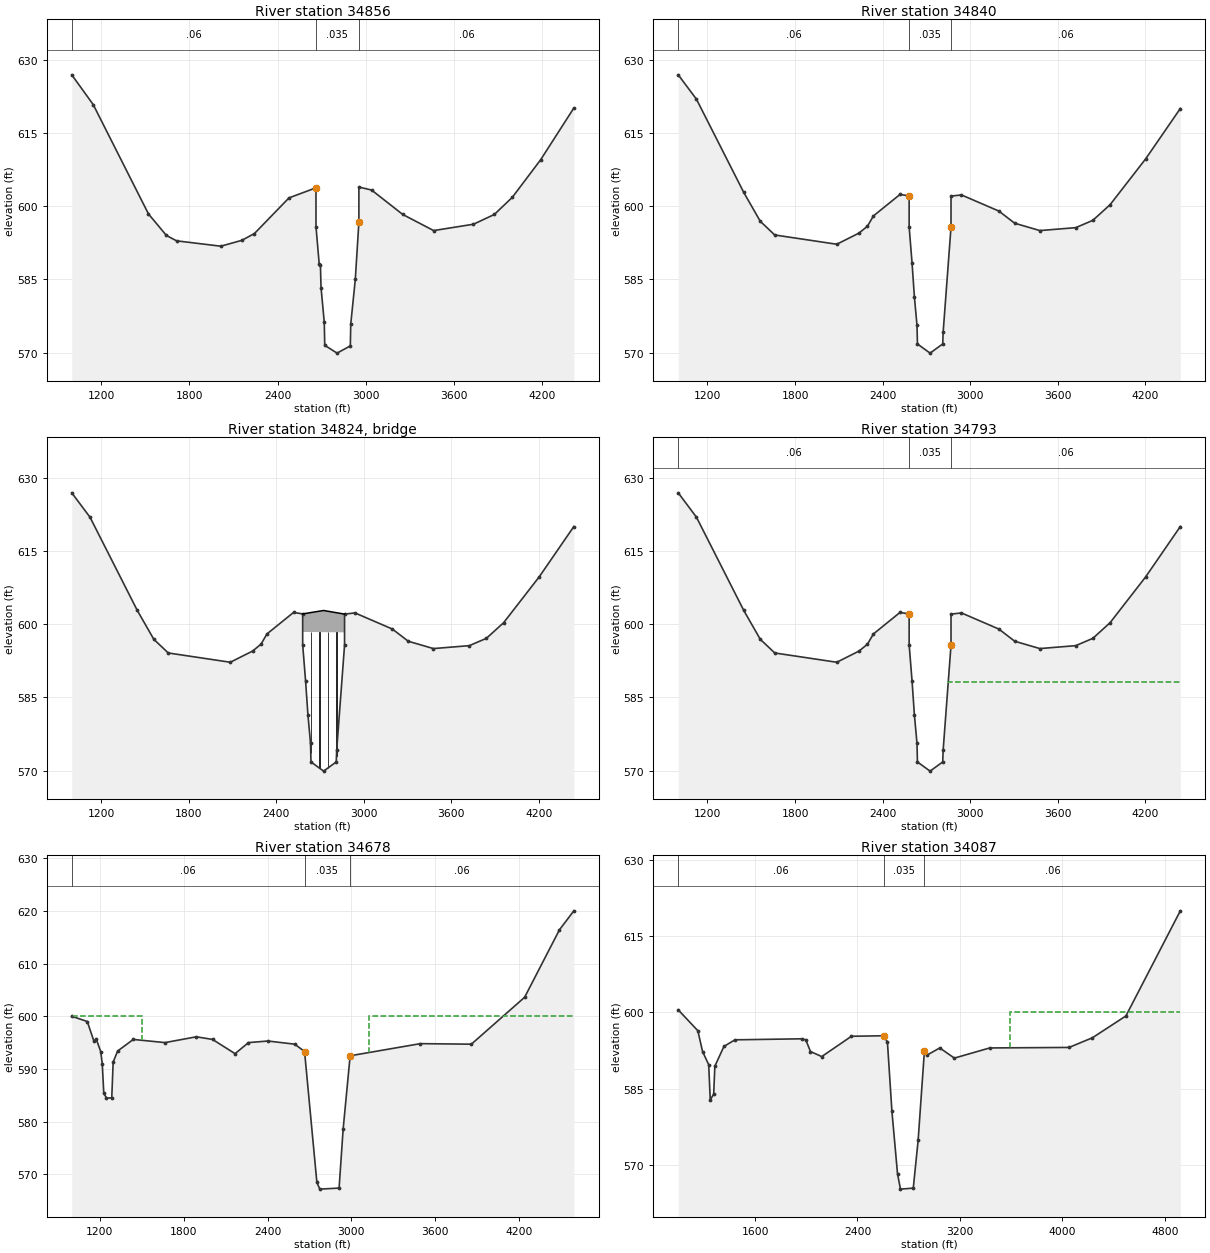
Type RM Length L Ch R = 1 ,34856   ,14.3,15.8,17
BEGIN DESCRIPTION:
This cross section corresponds to cross section 34878 of the non-georeferenced CDC model which was the source of this model.
Channel data from 1975 USACE field survey.  Duplication of following bridge cross-section without bridge piers.
Bank stations changed by USACE February 2007.
END DESCRIPTION:
XS GIS Cut Line= 5
      2303204.96      6942894.34  2303207.195843 6942799.2908942
 2303215.5347035 6942403.6342418 2303228.2174235 6941187.5024818
2303241.978059426939478.57568988
#Sta/Elev= 30
    1000   626.9    1146   620.8    1522   598.4    1644     594    1713   592.9
    2014   591.8    2157     593    2243   594.4    2478   601.7 2661.58  603.76
 2661.58   595.8 2683.39   588.2 2691.78     588 2695.97   583.3 2717.95  576.21
 2721.13   571.5    2805   569.9 2895.23  571.38 2898.23  575.89 2929.12     585
 2953.44   596.7 2953.44  603.92    3040   603.3    3252   598.3    3462     595
    3733   596.3    3875   598.3    3997   601.8    4190   609.5    4416   620.1
#Mann= 3 ,0,0
    1000     .06       0 2661.58    .035       0 2953.44     .06       0
#XS Ineff= 2 , 0
         2691.78     588 2929.12             585
Permanent Ineff=
       F       F
Bank Sta=2661.58,2953.44
XS Rating Curve= 0 ,0
Exp/Cntr=0.5,0.3

Type RM Length L Ch R = 1 ,34840   ,46.2,47.9,48.5
BEGIN DESCRIPTION:
This cross section corresponds to cross section 34846 of the non-georeferenced CDC model which was the source of this model.
Duplication of previous bridge cross-section without bridge piers.
One-foot upstream of Bryant-Irvin Road.
Bank stations changed by USACE February 2007.
END DESCRIPTION:
XS GIS Cut Line= 4
2303223.945786546942827.34139884     2303240.198     6941261.185
     2303244.842      6940894.282303256.640458846939388.50133359
#Sta/Elev= 30
    1000   626.9    1125   621.9    1449   602.8    1562   596.9    1661   594.1
    2086   592.2    2239   594.5    2296   595.9    2337     598    2519   602.4
 2581.58   602.1 2581.58   595.8 2601.71   588.3 2617.65   581.4 2635.44  575.58
 2638.44  571.78    2725   569.9 2811.56  571.78 2814.56   574.2 2868.41   595.7
 2868.41  602.06    2940   602.3    3196     599    3305   596.5    3477     595
    3723   595.6    3840   597.1    3958   600.3    4202   609.7    4439     620
#Mann= 3 ,0,0
    1000     .06       0 2581.58    .035       0 2868.41     .06       0
Bank Sta=2581.58,2868.41
XS Rating Curve= 0 ,0
Exp/Cntr=0.5,0.3

Type RM Length L Ch R = 3 ,34824   ,,,
BEGIN DESCRIPTION:
Bryant-Irvin Road - north bound
Downstream bridge: bridge data from 1975 survey.  Minimum low chord elev. 598.3.  Bridge width 30 feet.
Channel data from 1975 USACE field survey.
END DESCRIPTION:
Node Name=Bryant-Irvin Roa
Bridge Culvert--1,0,-1,-1, 0
Deck Dist Width WeirC Skew NumUp NumDn MinLoCord MaxHiCord MaxSubmerge Is_Ogee
3.5,25,2.6,0, 11, 11, , , 0.95, 0, 0,0,,
 2581.58 2635.44 2638.44 2694.14 2697.14    2725 2752.85 2755.85 2811.56 2814.56
    2869
   602.1 602.363 602.378 602.649 602.664   602.8 602.656 602.641 602.353 602.338
  602.06
  598.41 598.391  598.39 598.371  598.37  598.36 598.352 598.351 598.336 598.335
  598.32
 2581.58 2635.44 2638.44 2694.14 2697.14    2725 2752.85 2755.85 2811.56 2814.56
    2869
   602.1 602.363 602.378 602.649 602.664   602.8 602.656 602.641 602.353 602.338
  602.06
  598.41 598.391  598.39 598.371  598.37  598.36 598.352 598.351 598.336 598.335
  598.32
Pier Skew, UpSta & Num, DnSta & Num=  ,2636.94, 2 ,2636.94, 2 , 0 , 0 , 0 ,,
       3       3
     560     600
       3       3
     560     600
Pier Skew, UpSta & Num, DnSta & Num=  ,2695.64, 2 ,2695.64, 2 , 0 , 0 , 0 ,,
       3       3
     560     600
       3       3
     560     600
Pier Skew, UpSta & Num, DnSta & Num=  ,2754.35, 2 ,2754.35, 2 , 0 , 0 , 0 ,,
       3       3
     560     600
       3       3
     560     600
Pier Skew, UpSta & Num, DnSta & Num=  ,2813.06, 2 ,2813.06, 2 , 0 , 0 , 0 ,,
       3       3
     560     600
       3       3
     560     600
BR Coef=-1 , 0 , 0 ,1.05, 0 ,,,0.8,-1,0.5,1,
WSPro=,,,, 1 ,,,, 0 ,,,, 0 ,,,,-1 ,-1 ,-1 , 0 , 0 , 0 , 0 , 0
BC Design=,, 0 ,, 0 ,,,,,,
BC HTab HWMax=626.9
BC Use User HTab Curves=0
BC User HTab FreeFlow(D)= 0

Type RM Length L Ch R = 1 ,34793   ,118.3,114.1,117.2
BEGIN DESCRIPTION:
This cross section corresponds to cross section 34814 of the non-georeferenced CDC model which was the source of this model.
Bridge skewed 33 degrees - bridge area is duplication of
following bridge cross-section without bridge piers.
Channel data from 1975 USACE field survey.
Bank stations changed by USACE February 2007.
END DESCRIPTION:
XS GIS Cut Line= 4
 2303261.09176746942844.41489762 2303269.6729479 6942437.2607985
 2303282.3556679 6941221.12903852303296.974443446939405.63030242
#Sta/Elev= 30
    1000   626.9    1125   621.9    1449   602.8    1562   596.9    1661   594.1
    2086   592.2    2239   594.5    2296   595.9    2337     598    2519   602.4
 2581.58   602.1 2581.58   595.8 2601.71   588.3 2617.65   581.4 2635.44  575.58
 2638.44  571.78    2725   569.9 2811.56  571.78 2814.56   574.2 2868.41   595.7
 2868.41  602.06    2940   602.3    3196     599    3305   596.5    3477     595
    3723   595.6    3840   597.1    3958   600.3    4202   609.7    4439     620
#Mann= 3 ,0,0
    1000     .06       0 2581.58    .035       0 2868.41     .06       0
#XS Ineff= 2 , 0
         2601.71   588.3 2849.12           588.1
Permanent Ineff=
       F       F
Bank Sta=2581.58,2868.41
XS Rating Curve= 0 ,0
Exp/Cntr=0.5,0.3

Type RM Length L Ch R = 1 ,34678   ,547.9,591.3,625.1
BEGIN DESCRIPTION:
This cross section corresponds to cross section 34699 of the non-georeferenced CDC model which was the source of this model.
116 feet downstream of Bryant-Irvin Road.
Effective flow limit in ROB established by USACE October 2006.
Channel data from 1975 USACE field survey.
END DESCRIPTION:
XS GIS Cut Line= 4
   2303356.44713   6942980.68893   2303366.63116   6942497.48386
   2303379.31388    6941281.3521   2303394.54515   6939389.78797
#Sta/Elev= 30
    1000     600    1111     599    1158   595.3    1176   595.6    1207   593.3
    1218     591    1229   585.4    1248   584.5    1286   584.5    1296   591.3
    1328   593.4    1440   595.6    1667     595    1891   596.1    2007   595.6
    2168   592.9    2264     595    2403   595.3    2595   594.7    2665   593.3
    2753   568.5    2774   567.2    2912   567.4    2941   578.6    2991   592.5
    3493   594.8    3858   594.7    4239   603.6    4488   616.4    4591     620
#Mann= 3 ,0,0
    1000     .06       0    2665    .035       0    2991     .06       0
#XS Ineff= 4 ,-1
    1000    1500     600    1500    2665   593.3    2991    3125   592.5
    3125    4591     600
Permanent Ineff=
       F       F       F       F
Bank Sta=2665,2991
XS Rating Curve= 0 ,0
Exp/Cntr=0.3,0.1

Type RM Length L Ch R = 1 ,34087   ,569,535.8,504.8
BEGIN DESCRIPTION:
This cross section corresponds to cross section 34116 of the non-georeferenced CDC model which was the source of this model.
Effective flow limit in ROB established by USACE October 2006.
Drainage channel in LOB removed from conveyance.
Channel data from 1975 USACE field survey.
END DESCRIPTION:
XS GIS Cut Line= 4
   2304047.70198   6943190.78004   2303819.00493   6941714.72295
   2303989.44914   6941065.44013   2303497.05511    6939378.6561
#Sta/Elev= 30
    1000   600.5    1153   596.4    1190   592.3    1238   589.7    1250   582.8
    1277   583.9    1286   589.4    1357   593.3    1443   594.6    1966   594.8
    1996   594.6    2033   592.3    2121   591.3    2353   595.3    2604   595.4
    2634   594.2    2669   580.6    2713   568.2    2736   565.2    2836   565.4
    2874   574.8    2923   592.4    2944   591.6    3043     593    3157     591
    3433     593    4053   593.1    4235     595    4497   599.3    4922     620
#Mann= 3 ,0,0
    1000     .06       0    2604    .035       0    2923     .06       0
#XS Ineff= 3 ,-1
    1000    2604   595.4    2923    3590   592.4    3590    4922     600
Permanent Ineff=
       F       F       F
#Block Obstruct= 2 , 0
            1357   593.3
Bank Sta=2604,2923
XS Rating Curve= 0 ,0
Exp/Cntr=0.3,0.1