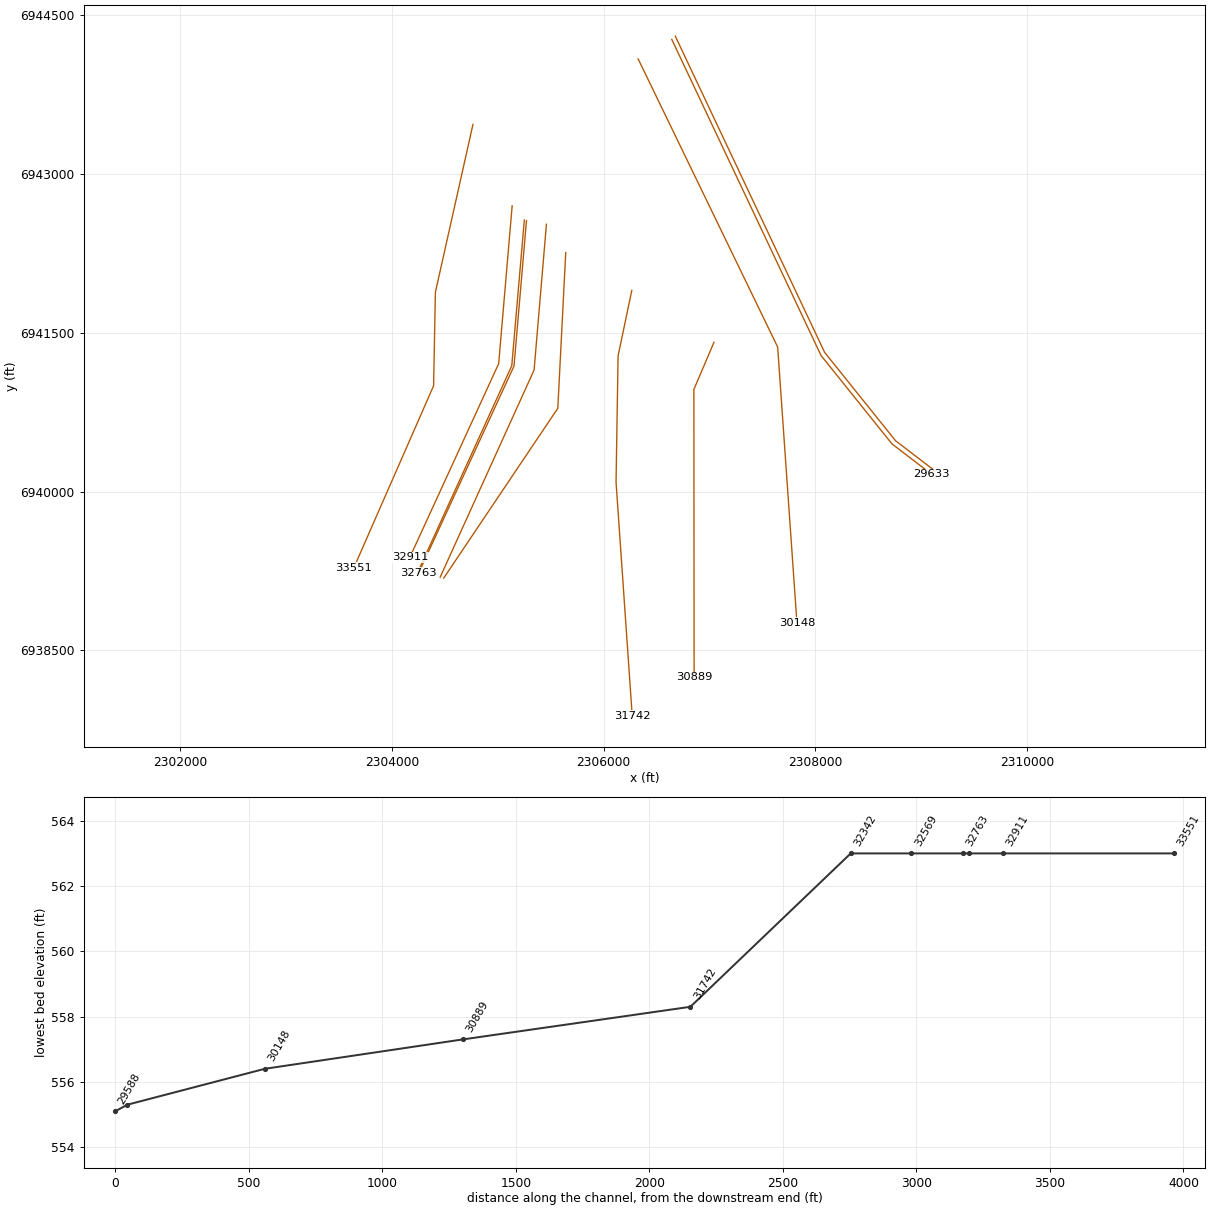
HEC-RAS study CDC_Consolidated_Model.prj: Upper Trinity CDC Consolidated Model

--- CDC_Consolidated_Model.g11 (geometry) --- (continued)

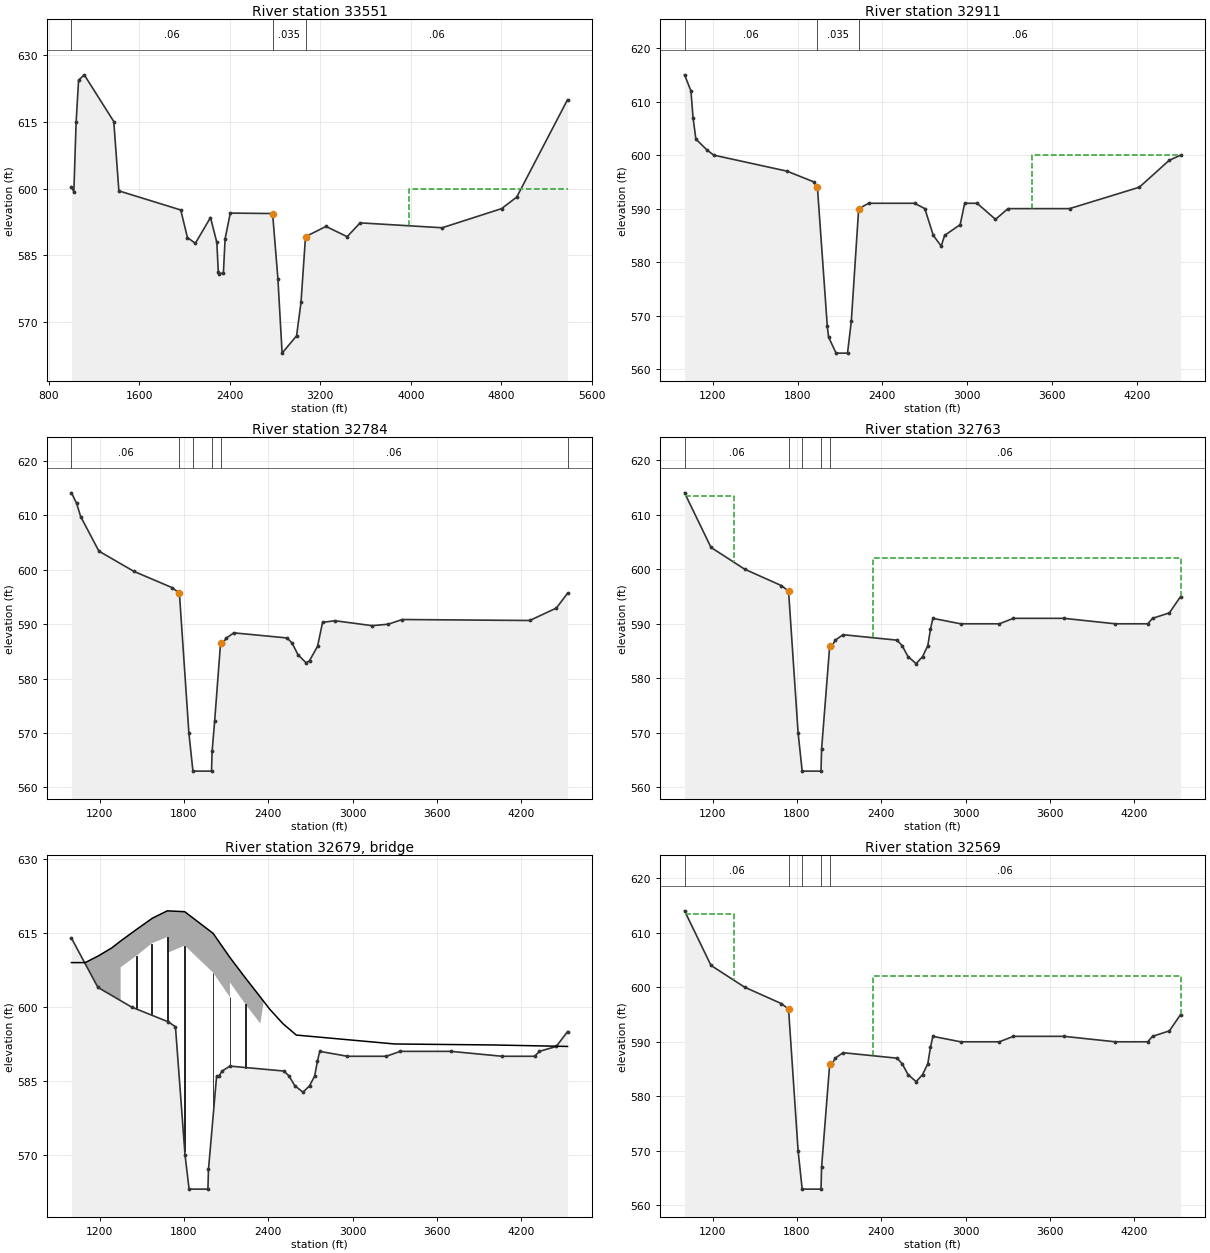
Type RM Length L Ch R = 1 ,33551   ,649.6,640.4,635
BEGIN DESCRIPTION:
This cross section corresponds to cross section 33577 of the non-georeferenced CDC model which was the source of this model.
Effective flow limit in ROB established by USACE October 2006.
Drainage channel in LOB removed from conveyance.
Channel data from 1975 USACE field survey.
END DESCRIPTION:
XS GIS Cut Line= 4
    2304766.1779   6943468.66597   2304411.44896   6941883.67997
   2304394.57005   6941000.22012   2303641.18015   6939280.79114
#Sta/Elev= 30
    1000   600.4    1021   599.3    1041   614.9    1063   624.4    1113   625.6
    1374   615.1    1419   599.5    1966   595.2    2025     589    2095   587.7
    2229   593.5    2285   587.9    2298   581.2    2308   580.9    2343     581
    2358   588.7    2404   594.5    2778   594.4    2825   579.7    2862     563
    2990   566.9    3029   574.4    3069   589.2    3250   591.5    3437   589.2
    3552   592.3    4277   591.2    4802   595.5    4936   598.1    5385     620
#Mann= 3 ,0,0
    1000     .06       0    2778    .035       0    3069     .06       0
#XS Ineff= 3 ,-1
    1000    2778   594.4    3069    3980   589.2    3980    5385     600
Permanent Ineff=
       F       F       F
#Block Obstruct= 2 , 0
            2404   594.5
Bank Sta=2778,3069
XS Rating Curve= 0 ,0
Exp/Cntr=0.3,0.1

Type RM Length L Ch R = 1 ,32911   ,127.5,126.4,126.7
BEGIN DESCRIPTION:
This cross section corresponds to cross section 32940 of the non-georeferenced CDC model which was the source of this model.
Cross-section generated from SH 121 Southwest Tollway project study using new topo.  Replaces original cross-section.Effective flow limit in ROB established by USACE October 2006.
---------------------------------------------------------------------
CDC FW111809-01 SH121/SOUTHWEST PARKWAY
CROSS-SECTION 32602 - 32940
UPSTREAM END.
----------------------------------------------
END DESCRIPTION:
XS GIS Cut Line= 3
   2305136.54888   6942700.42111   2305009.22991    6941209.1531
 2304169.8036398 6939379.1891681
#Sta/Elev= 30
    1000     615    1045     612    1060     607    1080     603    1157     601
    1206     600    1725     597    1914     595    1940     594    2010     568
    2019     566    2072     563    2153     563    2180     569    2232     590
    2303     591    2628     591    2700     590    2760     585    2816     583
    2840     585    2950     587    2982     591    3070     591    3200     588
    3289     590    3724     590    4218     594    4428     599    4510     600
#Mann= 3 ,0,0
    1000     .06       0    1940    .035       0    2232     .06       0
#XS Ineff= 3 ,-1
    1000    1940     594    2232    3460     590    3460    4510     600
Permanent Ineff=
       F       F       F
Bank Sta=1940,2232
XS Rating Curve= 0 ,0
Exp/Cntr=0.3,0.1

Type RM Length L Ch R = 1 ,32784   ,21.2,21.4,21.4
BEGIN DESCRIPTION:
This cross section corresponds to cross section 32814 of the non-georeferenced CDC model which was the source of this model.
Interpolated cross-section by USACE 12/1/07.
Paved side slopes of concrete block, natural bottom.
END DESCRIPTION:
XS GIS Cut Line= 3
2305251.616347856942566.71575549       2305132.9      6941189.36
      2304244.23      6939237.33
#Sta/Elev= 30
    1000  614.14 1036.74   612.2 1065.31  609.78 1194.96  603.43 1443.85  599.71
 1714.51  596.73  1767.4  595.73 1834.92  570.01 1863.71     563 1995.93     563
 2000.08  566.62 2017.92  572.13 2060.26  586.55 2078.04  586.55 2098.79  587.41
 2154.12  588.41 2533.51  587.47 2569.07  586.53 2610.57   584.4 2667.87  582.91
 2692.71   583.3 2749.87  585.94 2785.44  590.33 2872.49  590.64 3137.81  589.73
 3252.76     590 3351.56  590.86 4258.68  590.68 4448.22  592.97 4527.26  595.68
#Mann= 6 ,-1,0
    1000     .06       0  1767.4    .018       0 1863.71    .035       0
 1995.93    .018       0 2060.26     .06       0 4527.26     .06       0
Bank Sta=1767.4,2060.26
XS Rating Curve= 0 ,0
Exp/Cntr=0.5,0.3

Type RM Length L Ch R = 1 ,32763   ,192.7,194,193.8
BEGIN DESCRIPTION:
This cross section corresponds to cross section 32794 of the non-georeferenced CDC model which was the source of this model.
Upstream bounding bridge cross-section.
Copy of cross-section 32602 by USACE 12/1/07.  Paved side slopes of concrete block - no change of cross-section template.
Revised Existing Cross Section 32602
USACE relocated 32611 here Dec2006.
END DESCRIPTION:
XS GIS Cut Line= 3
2305271.851324616942559.61834532      2305154.01      6941186.11
      2304253.61      6939232.14
#Sta/Elev= 30
    1000     614    1188     604    1428     600    1689     597    1740     596
    1808     570    1837     563    1971     563    1975     567    2033     586
    2051     586    2072     587    2128     588    2512     587    2548     586
    2590     584    2648   582.7    2694     584    2731     586    2750     589
    2767     591    2964     590    3240     590    3340     591    3700     591
    4065     590    4296     590    4330     591    4450     592    4530     595
#Mann= 5 ,-1,0
    1000     .06       0    1740    .018       0    1837    .035       0
    1971    .018       0    2033     .06       0
#XS Ineff= 2 , 0
            1350  613.43    2344          602.04
Permanent Ineff=
       F       F
Bank Sta=1740,2033
XS Rating Curve= 0 ,0
Exp/Cntr=0.5,0.3

Type RM Length L Ch R = 3 ,32679   ,,,
BEGIN DESCRIPTION:
SH 121/Southwest Parkway
Data from bridge plans.  Concrete block on river side slopes.
END DESCRIPTION:
Node Name=SH 121/SW Parkwa
Bridge Culvert--1,0,-1,-1, 0
Deck Dist Width WeirC Skew NumUp NumDn MinLoCord MaxHiCord MaxSubmerge Is_Ogee
1.5,165,2.6,0, 21, 21, , , 0.95, 0, 0,0,,
    1000    1098    1192    1287    1350    1462    1575    1682 1682.01    1806
    2008    2128 2128.01    2236    2344    2410    2505    2600    3300    4000
    4530
  609.04  609.04  610.41  612.03  613.43  615.76  618.05  619.56  619.56  619.38
  614.98  610.06  610.06  605.99  602.04  599.59  596.62  594.31   592.5   592.3
     592
                                   608.1  610.43     613  614.23     611   612.5
     607     602     605  600.66  596.67
    1000    1098    1192    1287    1350    1462    1575    1682 1682.01    1806
    2008    2128 2128.01    2236    2344    2410    2505    2600    3300    4000
    4530
  609.04  609.04  610.41  612.03  613.43  615.76  618.05  619.56  619.56  619.38
  614.98  610.06  610.06  605.99  602.04  599.59  596.62  594.31   592.5   592.3
     592
                                   608.1  610.43     613  614.23     611   612.5
     607     602     605  600.66  596.67
Pier Skew, UpSta & Num, DnSta & Num=  ,1462, 2 ,1462, 2 , 0 , 0 , 0 ,,
       5       5
     580     620
       5       5
     580     620
Pier Skew, UpSta & Num, DnSta & Num=  ,1570, 2 ,1570, 2 , 0 , 0 , 0 ,,
       5       5
     580     620
      15      15
     580     620
Pier Skew, UpSta & Num, DnSta & Num=  ,1682, 2 ,1682, 2 , 0 , 0 , 0 ,,
       5       5
     580     620
       5       5
     580     620
Pier Skew, UpSta & Num, DnSta & Num=  ,1806, 2 ,1806, 2 , 0 , 0 , 0 ,,
       5       5
     580     620
       5       5
     580     620
Pier Skew, UpSta & Num, DnSta & Num=  ,2008, 2 ,2008, 2 , 0 , 0 , 0 ,,
       5       5
     580     620
       5       5
     580     620
Pier Skew, UpSta & Num, DnSta & Num=  ,2128, 2 ,2128, 2 , 0 , 0 , 0 ,,
       5       5
     580     620
       5       5
     580     620
Pier Skew, UpSta & Num, DnSta & Num=  ,2236, 2 ,2236, 2 , 0 , 0 , 0 ,,
       5       5
     580     620
       5       5
     580     620
BR Coef=-1 , 0 , 0 ,, 0 ,,,0.8,-1,,0,
WSPro=,,,, 1 ,,,, 0 ,,,, 0 ,,,,-1 ,-1 ,-1 , 0 , 0 , 0 , 0 , 0
BC Design=,, 0 ,, 0 ,,,,,,
BC Use User HTab Curves=0
BC User HTab FreeFlow(D)= 0

Type RM Length L Ch R = 1 ,32569   ,223.8,227.1,230.3
BEGIN DESCRIPTION:
This cross section corresponds to cross section 32602 of the non-georeferenced CDC model which was the source of this model.
Downstream bridge bounding cross-section.  Paved side slopes of concrete block - no change of cross-section template. Revised Existing Cross Section 32602.  USACE relocated 32611 here Dec2006.
------------------------------------------------------
CDC FW111809-01 SH121/SOUTHWEST PARKWAY
CROSS-SECTION 32602 - 32940
DOWNSTREAM END.
----------------------------------------------
END DESCRIPTION:
XS GIS Cut Line= 3
2305460.240985066942525.59415373       2305343.7      6941149.03
      2304456.55      6939192.23
#Sta/Elev= 30
    1000     614    1188     604    1428     600    1689     597    1740     596
    1808     570    1837     563    1971     563    1975     567    2033     586
    2051     586    2072     587    2128     588    2512     587    2548     586
    2590     584    2648   582.7    2694     584    2731     586    2750     589
    2767     591    2964     590    3240     590    3340     591    3700     591
    4065     590    4296     590    4330     591    4450     592    4530     595
#Mann= 5 ,-1,0
    1000     .06       0    1740    .018       0    1837    .035       0
    1971    .018       0    2033     .06       0
#XS Ineff= 2 , 0
            1350  613.43    2344          602.04
Permanent Ineff=
       F       F
Bank Sta=1740,2033
XS Rating Curve= 0 ,0
Exp/Cntr=0.5,0.3

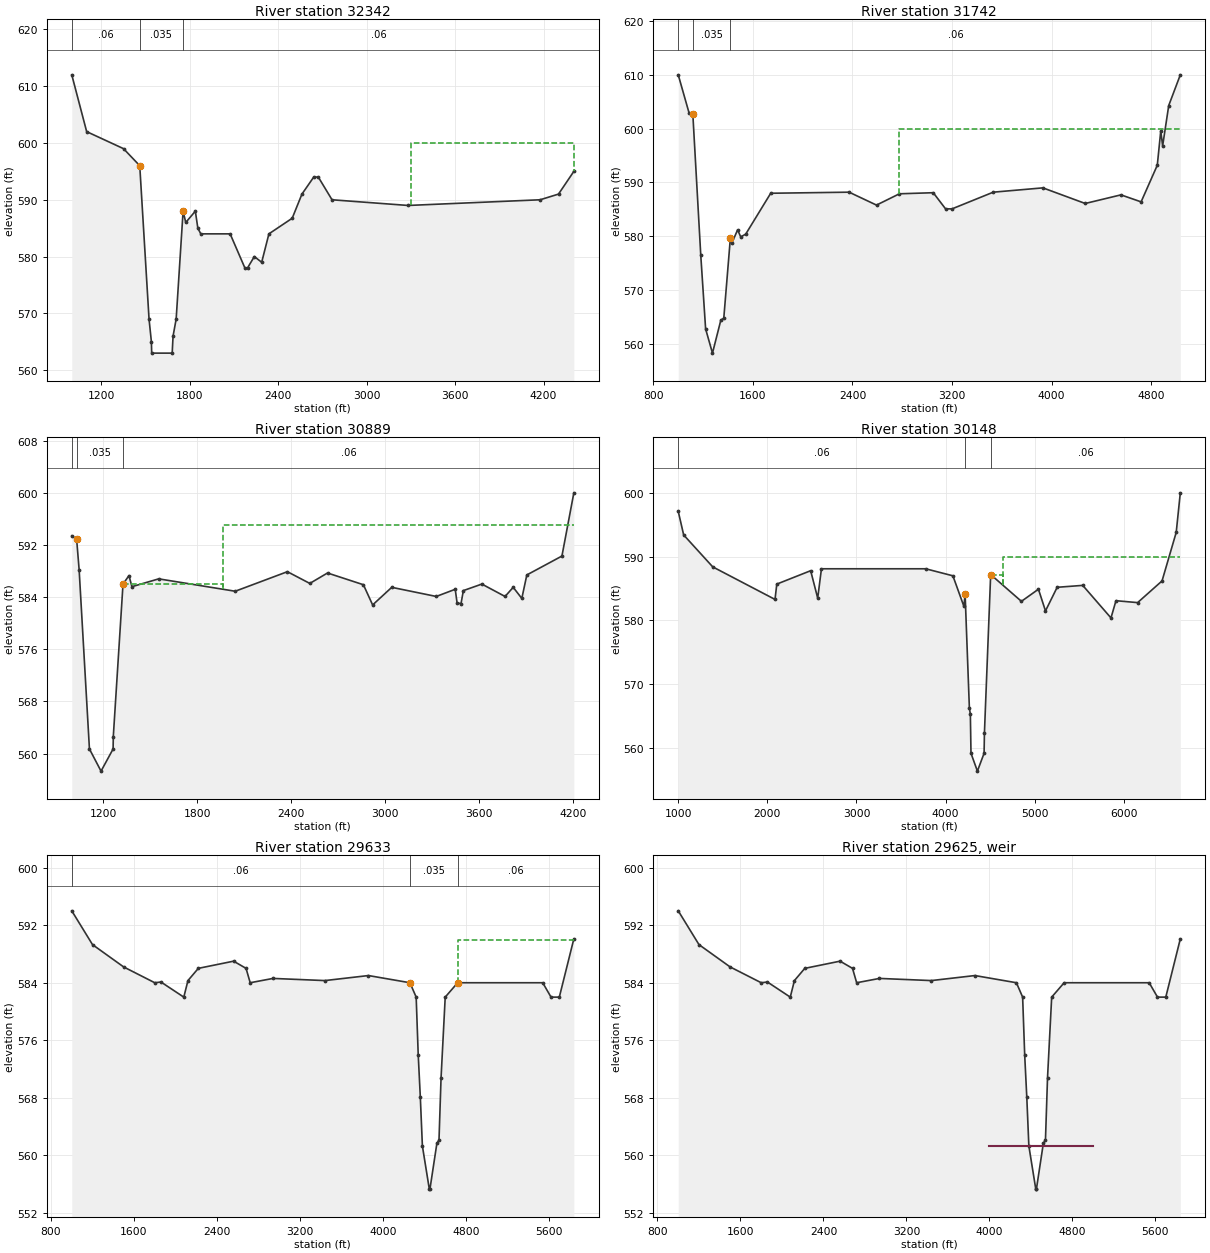
Type RM Length L Ch R = 1 ,32342   ,620.9,600.4,585
BEGIN DESCRIPTION:
This cross section corresponds to cross section 32371 of the non-georeferenced CDC model which was the source of this model.
Cross-section generated from SH 121 Southwest Tollway project study using newly topo.  Replaces original cross-section.
Effective flow limit in ROB established by USACE October 2006.
END DESCRIPTION:
XS GIS Cut Line= 3
2305642.604083846942258.56714084   2305567.67204    6940787.4689
      2304490.23      6939183.81
#Sta/Elev= 30
    1000     612    1101     602    1351     599    1461     596    1524     569
    1540     565    1542     563    1681     563    1687     566    1708     569
    1755     588    1773     586    1838     588    1855     585    1875     584
    2074     584    2174     578    2192     578    2238     580    2288     579
    2337     584    2495  586.75    2561     591    2641     594    2672     594
    2765     590    3281     589    4176     590    4301     591    4405     595
#Mann= 3 ,0,0
    1000     .06       0    1461    .035       0    1755     .06       0
#XS Ineff= 3 ,-1
    1000    1461     596    1755    3298     588    3298    4405     600
Permanent Ineff=
       F       F       F
Bank Sta=1461,1755
XS Rating Curve= 0 ,0
Exp/Cntr=0.3,0.1

Type RM Length L Ch R = 1 ,31742   ,877.5,852.6,833.3
BEGIN DESCRIPTION:
This cross section corresponds to cross section 31770 of the non-georeferenced CDC model which was the source of this model.
Effective flow limit in ROB established by USACE October 2006.
Channel data from 1975 USACE field survey.
END DESCRIPTION:
XS GIS Cut Line= 4
   2306266.49216   6941900.40795   2306137.03212   6941282.05092
   2306117.89895   6940089.65009   2306270.41505   6937885.00916
#Sta/Elev= 30
    1000     610    1086     603    1117   602.8    1181   576.5    1220   562.8
 1275.08   558.3    1342   564.4    1366   564.8    1419   579.7    1430   578.7
    1477   581.2    1502   579.9    1542   580.4    1743     588    2373   588.2
    2593   585.8    2777   587.9    3049   588.1    3148   585.1    3200   585.1
    3531   588.2    3930     589    4270   586.1    4557   587.7    4719   586.4
    4849   593.2    4877   599.6    4892   596.8    4941   604.3    5034     610
#Mann= 3 ,0,0
    1000     .06       0    1117    .035       0    1419     .06       0
#XS Ineff= 3 ,-1
    1000    1117   602.8    1419    2775   579.7    2775    5034     600
Permanent Ineff=
       F       F       F
Bank Sta=1117,1419
XS Rating Curve= 0 ,0
Exp/Cntr=0.3,0.1

Type RM Length L Ch R = 1 ,30889   ,680.3,741.2,790.5
BEGIN DESCRIPTION:
This cross section corresponds to cross section 30913 of the non-georeferenced CDC model which was the source of this model.
Effective flow limit in ROB established by USACE October 2006.
Channel data from 1975 USACE field survey.
END DESCRIPTION:
XS GIS Cut Line= 3
   2307042.71207     6941410.571   2306852.94899   6940965.73889
   2306855.10713   6938245.54912
#Sta/Elev= 30
    1000   593.4    1031   592.9    1047   588.2 1112.75   560.7 1186.75   557.3
 1263.75   560.7    1265   562.6    1327     586    1365   587.3    1384   585.6
    1555   586.8    2043   584.9    2376   587.9    2519   586.1    2632   587.7
    2861   585.9    2920   582.8    3042   585.5    3326   584.1    3447   585.2
    3459   583.1    3484     583    3499     585    3617     586    3765   584.1
    3817   585.5    3872   583.8    3904   587.4    4128   590.3    4204     600
#Mann= 3 ,0,0
    1000     .06       0    1031    .035       0    1327     .06       0
#XS Ineff= 3 ,-1
    1000    1031   592.9    1327    1965     586    1965    4204     595
Permanent Ineff=
       F       F       F
Bank Sta=1031,1327
XS Rating Curve= 0 ,0
Exp/Cntr=0.3,0.1

Type RM Length L Ch R = 1 ,30148   ,429.8,514.6,577.8
BEGIN DESCRIPTION:
This cross section corresponds to cross section 30174 of the non-georeferenced CDC model which was the source of this model.
Effective flow limit in ROB established by USACE October 2006.
Channel data from 1975 USACE field survey.
END DESCRIPTION:
XS GIS Cut Line= 3
   2306326.32997   6944087.84911   2307644.36014   6941365.81913
    2307826.3601   6938762.19802
#Sta/Elev= 30
    1000   597.1    1061   593.4    1387   588.4    2086   583.3    2106   585.7
    2486   587.8    2565   583.5    2607   588.1    3777   588.1    4082     587
    4206   582.2    4219   584.2    4267   566.3    4278   565.3 4285.11   559.2
 4357.11   556.4 4432.11   559.2    4436   562.4    4506   587.2    4851     583
    5042   584.9    5121   581.5    5252   585.2    5539   585.5    5856   580.4
    5912   583.1    6155   582.8    6429   586.2    6588   593.8    6634     600
#Mann= 3 ,0,0
    1000     .06       0    4219    .035       0    4506     .06       0
#XS Ineff= 3 ,-1
    1000    4219   584.2    4506    4645   587.2    4645    6634     590
Permanent Ineff=
       F       F       F
Bank Sta=4219,4506
XS Rating Curve= 0 ,0
Exp/Cntr=0.3,0.1

Type RM Length L Ch R = 1 ,29633   ,46.1,45.1,46.1
BEGIN DESCRIPTION:
This cross section corresponds to cross section 29663 of the non-georeferenced CDC model which was the source of this model.
Effective flow limit in ROB established by USACE October 2006.
25 feet upstream of channel dam.
Channel data from 1975 USACE field survey.
END DESCRIPTION:
XS GIS Cut Line= 4
  2306643.936829 6944272.3195512 2308054.4169494 6941285.6073512
 2308724.6117994 6940450.5906412 2309098.2170294 6940164.7906912
#Sta/Elev= 30
    1000     594    1200   589.3    1500   586.2    1800     584    1860   584.1
    2080     582    2120   584.3    2220     586    2560     587    2680     586
    2720     584    2940   584.6    3440   584.3    3860     585    4260     584
    4320     582    4340   573.9    4360   568.1    4380   561.3 4446.79   555.3
 4452.79   555.3    4520   561.7    4540   562.1    4560   570.8    4600     582
    4720     584    5540     584    5620     582    5700     582    5840   590.1
#Mann= 3 ,0,0
    1000     .06       0    4260    .035       0    4720     .06       0
#XS Ineff= 3 ,-1
    1000    4260     584    4720    4725     584    4725    5840     590
Permanent Ineff=
       F       F       F
Bank Sta=4260,4720
XS Rating Curve= 0 ,0
Exp/Cntr=0.3,0.1

Type RM Length L Ch R = 5 ,29625   ,,,
BEGIN DESCRIPTION:
channel dam
crest elevation 561.3
END DESCRIPTION:
Node Name=channel dam
IW Pilot Flow=0
#Inline Weir SE= 2
    4000   561.3    5000   561.3
IW Dist,WD,Coef,Skew,MaxSub,Min_El,Is_Ogee,SpillHt,DesHd
5.5,5,3,0,0.95,, 0 ,,,2,2,
Inline Weir Flap Gates= 0
IW Outlet Rating Curve= 0 ,False,,

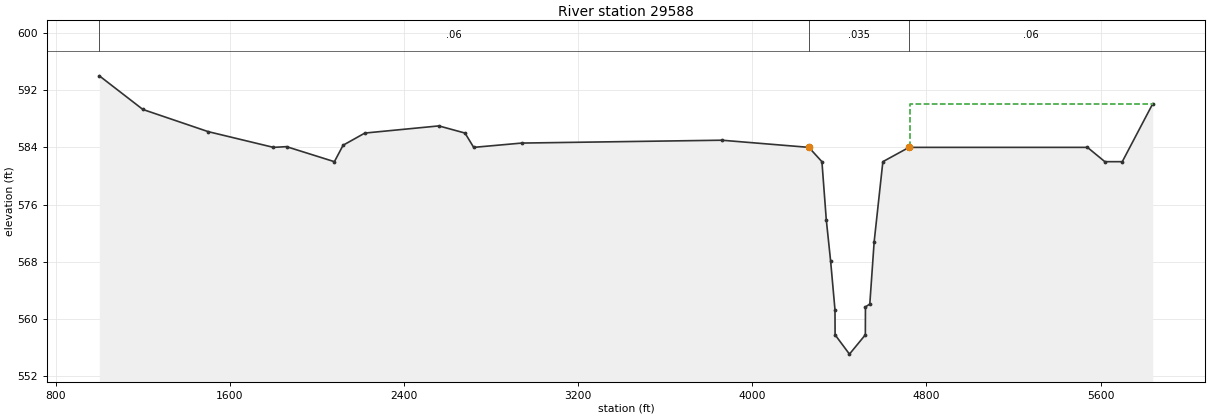
Type RM Length L Ch R = 1 ,29588   ,75.5,76.6,79.4
BEGIN DESCRIPTION:
This cross section corresponds to cross section 29613 of the non-georeferenced CDC model which was the source of this model.
Effective flow limit in ROB established by USACE October 2006.
21.5 feet downstream of channel dam.
Channel data from 1975 USACE field survey.
END DESCRIPTION:
XS GIS Cut Line= 4
  2306677.273096 6944302.6838326 2308087.7532162 6941315.9716326
 2308757.9480662 6940480.9549226 2309131.5532962 6940195.1549726
#Sta/Elev= 30
    1000     594    1200   589.3    1500   586.2    1800     584    1860   584.1
    2080     582    2120   584.3    2220     586    2560     587    2680     586
    2720     584    2940   584.6    3860     585    4260     584    4320     582
    4340   573.9    4360   568.1    4380   561.3 4380.51   557.8 4446.51   555.1
 4519.51   557.8    4520   561.7    4540   562.1    4560   570.8    4600     582
    4720     584    5540     584    5620     582    5700     582    5840   590.1
#Mann= 3 ,0,0
    1000     .06       0    4260    .035       0    4720     .06       0
#XS Ineff= 3 ,-1
    1000    4260     584    4720    4725     584    4725    5840     590
Permanent Ineff=
       F       F       F
Bank Sta=4260,4720
XS Rating Curve= 0 ,0
Exp/Cntr=0.3,0.1