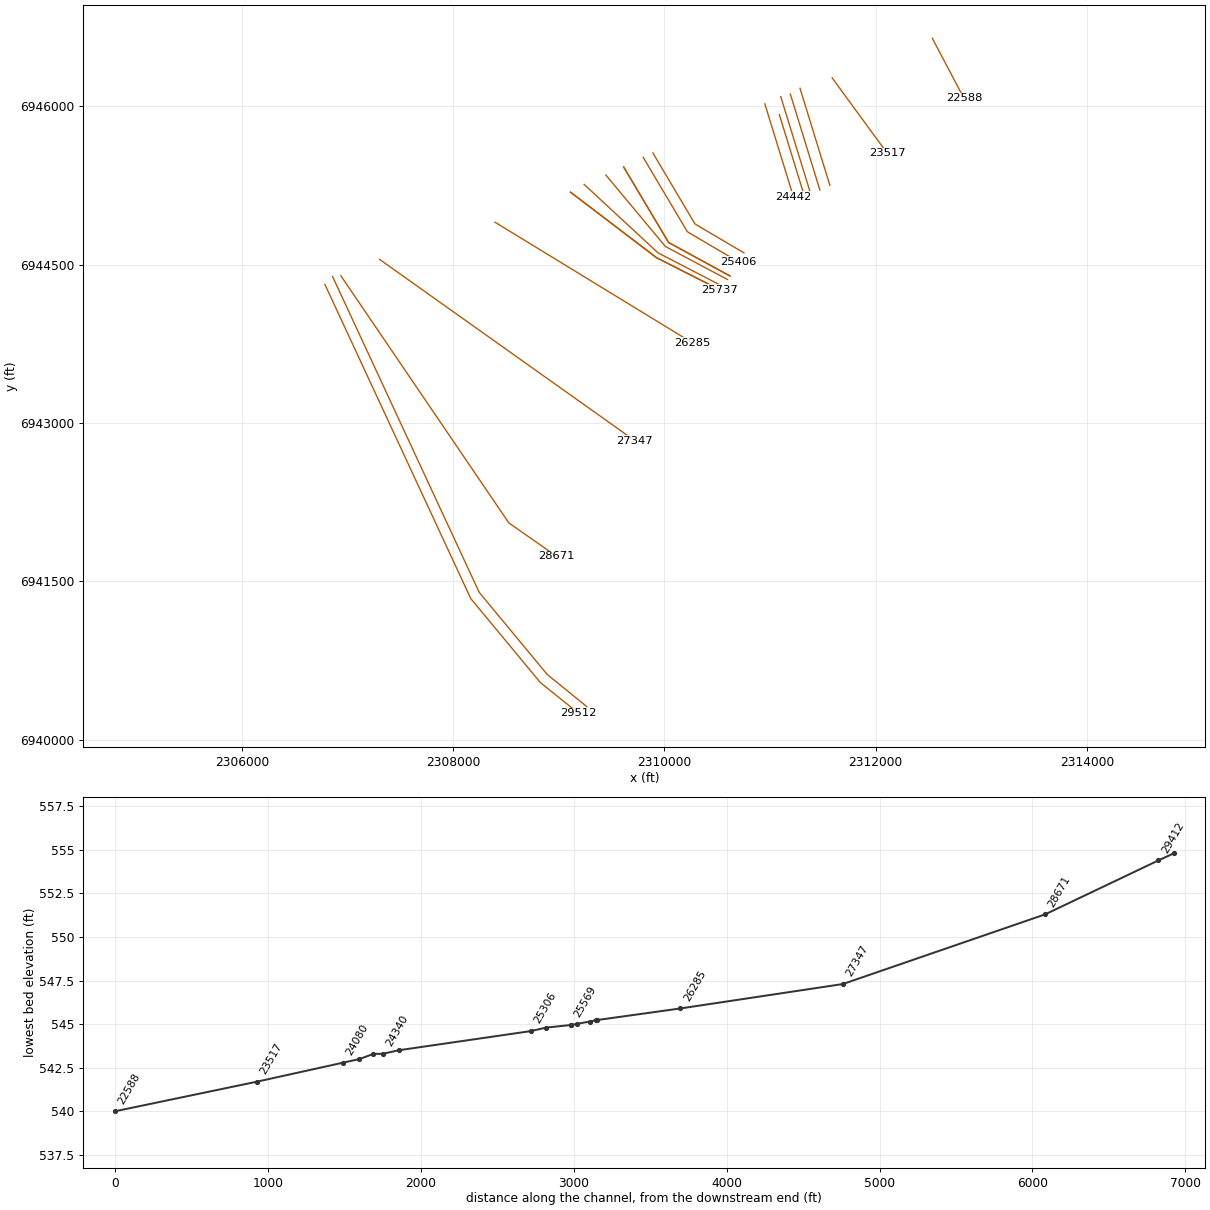
HEC-RAS study CDC_Consolidated_Model.prj: Upper Trinity CDC Consolidated Model

--- CDC_Consolidated_Model.g11 (geometry) --- (continued)

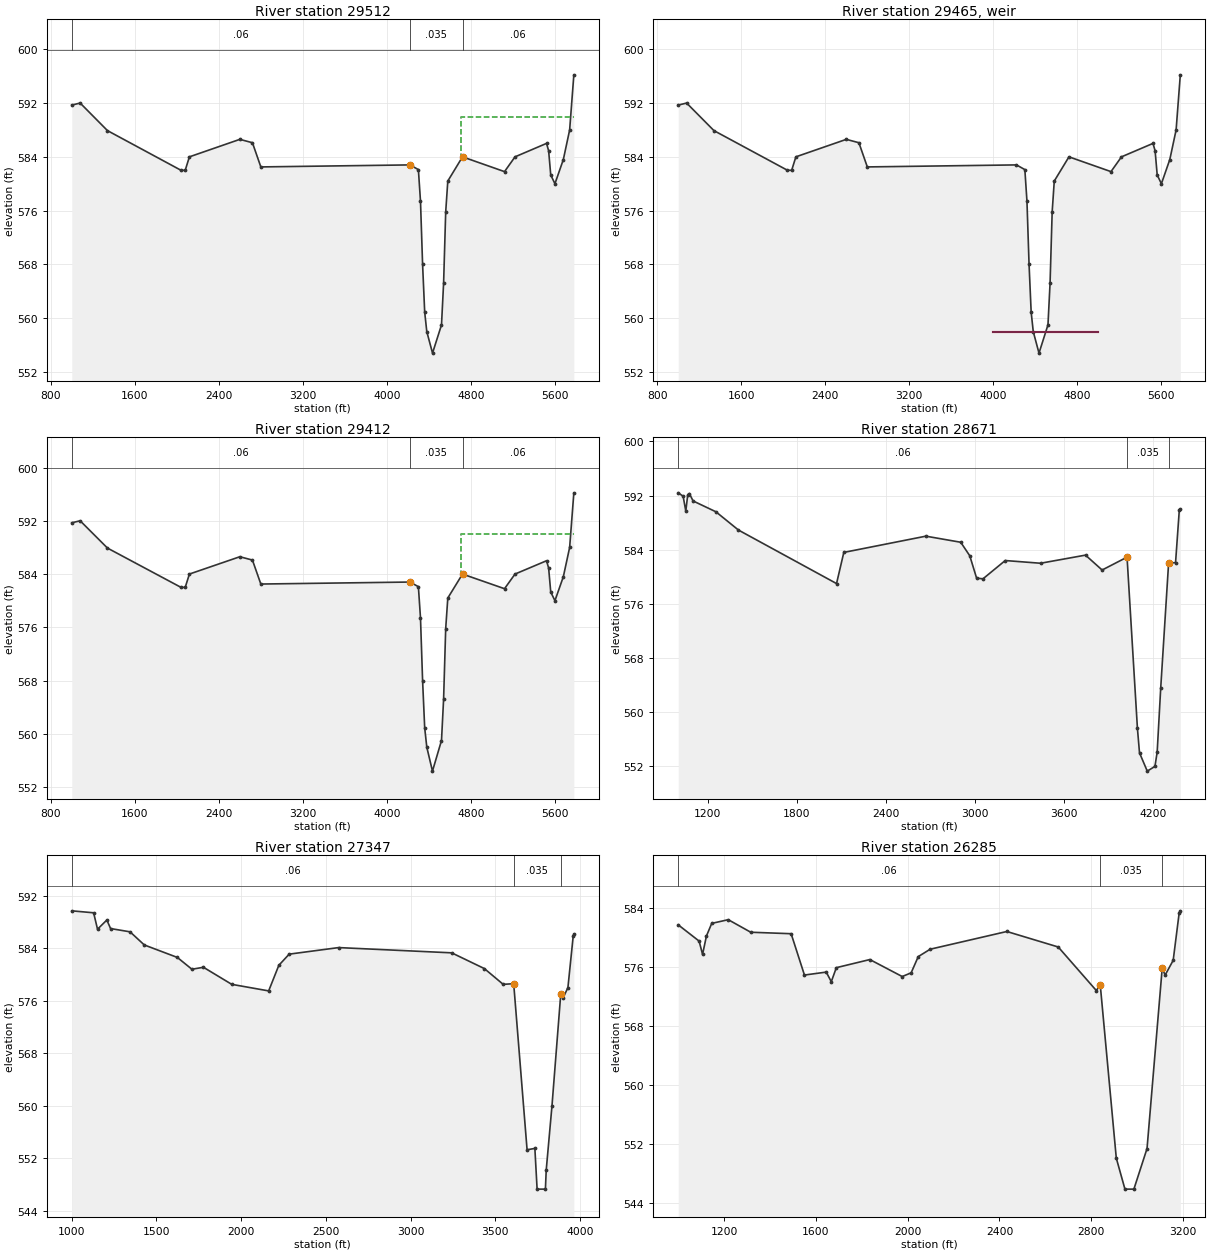
Type RM Length L Ch R = 1 ,29512   ,99.7,99.2,99.5
BEGIN DESCRIPTION:
This cross section corresponds to cross section 29535 of the non-georeferenced CDC model which was the source of this model.
Effective flow limit in ROB established by USACE October 2006.
Cross-section generated from topographic file.  50 feet upstream of channel dam.
Channel data from 1975 USACE field survey.
END DESCRIPTION:
XS GIS Cut Line= 4
2306784.007642616944313.01996774      2308165.41       6941337.6
      2308825.17       6940541.52309188.082737116940249.83446717
#Sta/Elev= 30
    1000   591.7    1080     592    1340   587.9    2040     582    2080     582
    2120     584    2600   586.6    2720   586.1    2800   582.5    4220   582.8
    4300   582.1    4320   577.4    4340     568    4360   560.9    4380     558
 4434.58   554.8    4520     559    4540   565.2    4560   575.8    4580   580.4
    4720     584    5120   581.8    5220     584    5520     586    5540   584.9
    5560   581.3    5600     580    5680   583.6    5740     588    5780   596.2
#Mann= 3 ,0,0
    1000     .06       0    4220    .035       0    4720     .06       0
#XS Ineff= 2 , 0
            4220   582.8    4710             590
Permanent Ineff=
       F       F
Bank Sta=4220,4720
XS Rating Curve= 0 ,0
Exp/Cntr=0.3,0.1

Type RM Length L Ch R = 5 ,29465   ,,,
BEGIN DESCRIPTION:
channel dam
crest elevation 558.0
END DESCRIPTION:
Node Name=channel dam
IW Pilot Flow=0
#Inline Weir SE= 2
    4000     558    5000     558
IW Dist,WD,Coef,Skew,MaxSub,Min_El,Is_Ogee,SpillHt,DesHd
42,10,3,0,0.95,, 0 ,,,2,2,
Inline Weir Flap Gates= 0
IW Outlet Rating Curve= 0 ,False,,

Type RM Length L Ch R = 1 ,29412   ,712.4,741.7,778.6
BEGIN DESCRIPTION:
This cross section corresponds to cross section 29435 of the non-georeferenced CDC model which was the source of this model.
Effective flow limit in ROB established by USACE October 2006.
Approx. 250 feet upstream of left bank of Overton Woods diversion channel, 46.5 feet downstream of channel
dam.
Channel data from 1975 USACE field survey.
END DESCRIPTION:
XS GIS Cut Line= 4
  2306857.262319 6944386.2579837 2308245.5984494 6941396.3381037
 2308889.8934194 6940618.2271337 2309265.0724594 6940313.3812837
#Sta/Elev= 30
    1000   591.7    1080     592    1340   587.9    2040     582    2080     582
    2120     584    2600   586.6    2720   586.1    2800   582.5    4220   582.8
    4300   582.1    4320   577.4    4340     568    4360   560.9    4380     558
 4434.01   554.4    4520     559    4540   565.2    4560   575.8    4580   580.4
    4720     584    5120   581.8    5220     584    5520     586    5540   584.9
    5560   581.3    5600     580    5680   583.6    5740     588    5780   596.2
#Mann= 3 ,0,0
    1000     .06       0    4220    .035       0    4720     .06       0
#XS Ineff= 2 , 0
            4220   582.8    4710             590
Permanent Ineff=
       F       F
Bank Sta=4220,4720
XS Rating Curve= 0 ,0
Exp/Cntr=0.3,0.1

Type RM Length L Ch R = 1 ,28671   ,1325,1323.7,1323
BEGIN DESCRIPTION:
This cross section corresponds to cross section 28689 of the non-georeferenced CDC model which was the source of this model.
Approx. 450 feet downstream of right bank of Overton
Woods diversion channel.  Effective flow limit set at Overton Levee in ROB.
Channel data from 1975 USACE field survey.
END DESCRIPTION:
XS GIS Cut Line= 3
   2306935.33006   6944394.67494   2308526.63003   6942053.40994
   2308979.91784   6941736.65795
#Sta/Elev= 30
    1000   592.4    1033   591.9    1051   589.7    1064   592.1    1075   592.3
    1100   591.2    1254   589.6    1406   586.9    2067     579    2116   583.6
    2669     586    2904   585.1    2965   583.1    3011   579.8    3054   579.7
    3204   582.4    3442     582    3745   583.2    3857     581    4025   582.9
    4095   557.6    4109     554 4161.26   551.3    4213     552    4228   554.1
    4252   563.6    4305     582    4352   582.1    4377   589.8    4384     590
#Mann= 3 ,0,0
    1000     .06       0    4025    .035       0    4305     .06       0
#XS Ineff= 2 , 0
            4025   582.9    4305             582
Permanent Ineff=
       F       F
Bank Sta=4025,4305
XS Rating Curve= 0 ,0
Exp/Cntr=0.3,0.1

Type RM Length L Ch R = 1 ,27347   ,1053,1062,1068.8
BEGIN DESCRIPTION:
This cross section corresponds to cross section 27364 of the non-georeferenced CDC model which was the source of this model.
Effective flow limit set at Overton Levee in ROB.
Channel data from 1975 USACE field survey.
END DESCRIPTION:
XS GIS Cut Line= 2
   2307302.02093   6944549.78585   2309717.94687   6942833.62885
#Sta/Elev= 30
    1000   589.7    1129   589.4    1152   586.9    1207   588.3    1229     587
    1344   586.5    1428   584.5    1623   582.6    1709   580.8    1777   581.1
    1944   578.5    2162   577.5    2222   581.4    2283   583.1    2575   584.1
    3242   583.3    3435   580.9    3546   578.5    3608   578.6    3687   553.3
    3733   553.5 3746.19   547.3 3795.19   547.3    3800   550.2    3834     560
    3886   577.1    3899   576.4    3928     578    3959   585.8    3963   586.1
#Mann= 3 ,0,0
    1000     .06       0    3608    .035       0    3886     .06       0
#XS Ineff= 2 , 0
            3608   578.6    3886           577.1
Permanent Ineff=
       F       F
Bank Sta=3608,3886
XS Rating Curve= 0 ,0
Exp/Cntr=0.3,0.1

Type RM Length L Ch R = 1 ,26285   ,540.1,548.4,559.4
BEGIN DESCRIPTION:
This cross section corresponds to cross section 26300 of the non-georeferenced CDC model which was the source of this model.
Effective flow limit set at Overton Levee in ROB.
Channel data from 1975 USACE field survey.
END DESCRIPTION:
XS GIS Cut Line= 2
   2308395.51809   6944901.52596   2310262.30799   6943760.74314
#Sta/Elev= 30
    1000   581.7    1091   579.5    1106   577.7    1123   580.2    1146   581.9
    1218   582.4    1316   580.7    1492   580.5    1550   574.9    1645   575.3
    1667     574    1689   575.9    1835     577    1976   574.7    2015   575.2
    2046   577.4    2098   578.4    2432   580.8    2656   578.7    2822   572.8
    2839   573.6    2909   550.1 2946.71   545.9 2985.71   545.9    3043   551.4
    3109   575.8    3122   574.9    3157   576.9    3183   583.3    3188   583.6
#Mann= 3 ,0,0
    1000     .06       0    2839    .035       0    3109     .06       0
#XS Ineff= 2 , 0
            2839   573.6    3109           575.8
Permanent Ineff=
       F       F
Bank Sta=2839,3109
XS Rating Curve= 0 ,0
Exp/Cntr=0.3,0.1

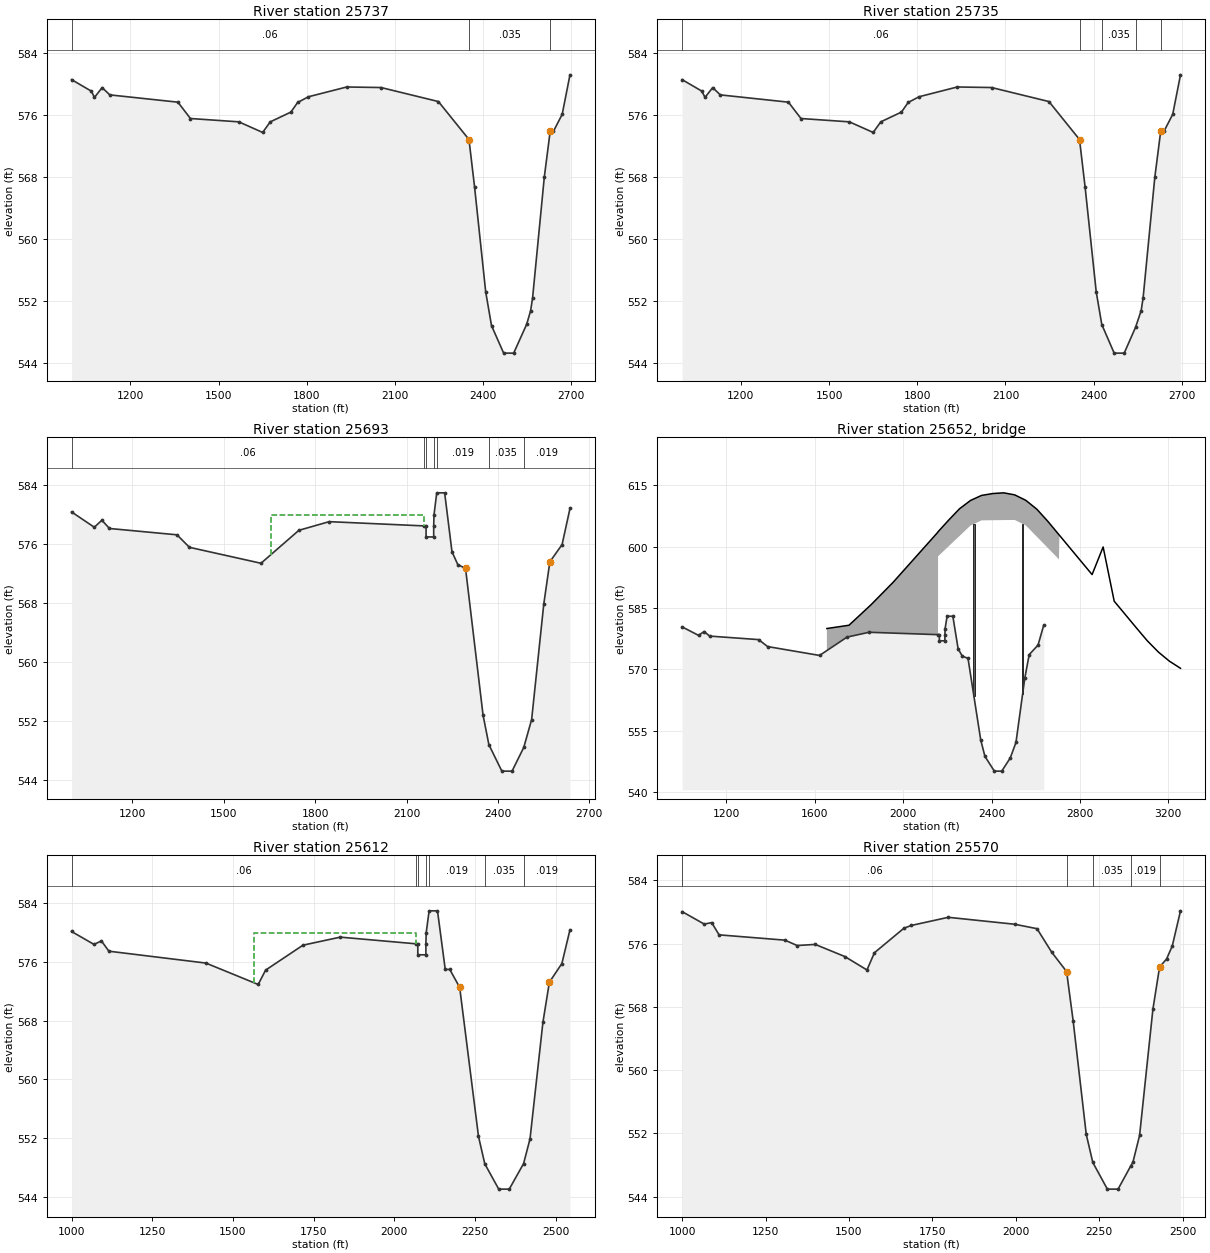
Type RM Length L Ch R = 1 ,25737   ,1.7,1.5,1.2
BEGIN DESCRIPTION:
This cross section corresponds to cross section 25739 of the non-georeferenced CDC model which was the source of this model.
Copy of cross-section 25738.
Interpolated cross-section.
Effective flow limit set at Overton Levee in ROB.
---------------------------------------------------------------------
CDC FW110209-01 STONEGATE/CLEAR FORK MAIN STREET BRIDGE
CROSS-SECTION 25577 - 25739
UPSTREAM END.
---------------------------------------------------------------------
END DESCRIPTION:
XS GIS Cut Line= 3
2309110.272845756945185.53241212      2309923.17      6944565.19
2310523.454409876944261.50273915
#Sta/Elev= 30
    1000  580.54 1066.89  579.06 1077.92  578.25 1103.98  579.51 1129.98  578.57
 1361.65  577.63 1404.29  575.52 1568.94  575.09  1649.9  573.72 1675.89  575.09
 1746.09  576.35 1768.88  577.59 1805.87  578.33 1935.85  579.59 2052.61  579.52
  2247.8  577.71 2351.78  572.81 2370.73   566.7 2408.63  553.14 2428.42  548.78
 2469.71  545.23 2503.83  545.23 2548.19  548.97 2561.48  550.71 2568.11  552.35
 2607.96  567.94 2627.88  573.85 2638.97  573.86 2668.84  576.06 2695.29  581.16
#Mann= 3 ,-1,0
    1000     .06       0 2351.78    .035       0 2627.88     .06       0
#XS Ineff= 2 , 0
         2351.78  572.81 2627.88          573.85
Permanent Ineff=
       F       F
Bank Sta=2351.78,2627.88
XS Rating Curve= 0 ,0
Exp/Cntr=0.3,0.1

Type RM Length L Ch R = 1 ,25735   ,43.2,42.4,41.4
BEGIN DESCRIPTION:
This cross section corresponds to cross section 25738 of the non-georeferenced CDC model which was the source of this model.
Upstream end of paved side slopes of concrete block.
Interpolated cross-section.
Effective flow limit set at Overton Levee in ROB.
END DESCRIPTION:
XS GIS Cut Line= 3
2309110.891708116945186.57215516     2309925.819     6944566.601
2310524.262564366944262.35663211
#Sta/Elev= 30
    1000  580.54 1066.89  579.06 1077.92  578.25 1103.98  579.51 1129.98  578.57
 1361.65  577.63 1404.29  575.52 1568.94  575.09  1649.9  573.72 1675.89  575.09
 1746.09  576.35 1768.88  577.59 1805.87  578.33 1935.85  579.59 2052.61  579.52
  2247.8  577.71 2351.78  572.81 2370.73   566.7 2408.63  553.14 2427.58  548.92
 2469.71  545.23 2503.83  545.23 2542.36  548.56 2561.48  550.71 2568.11  552.35
 2607.96  567.94 2627.88  573.85 2638.97  573.86 2668.84  576.06 2695.29  581.16
#Mann= 5 ,-1,0
    1000     .06       0 2351.78    .019       0 2427.58    .035       0
 2542.36    .019       0 2627.88     .06       0
#XS Ineff= 2 , 0
         2351.78  572.81 2627.88          573.85
Permanent Ineff=
       F       F
Bank Sta=2351.78,2627.88
XS Rating Curve= 0 ,0
Exp/Cntr=0.5,0.3

Type RM Length L Ch R = 1 ,25693   ,81.8,80.6,79.2
BEGIN DESCRIPTION:
This cross section corresponds to cross section 25699 of the non-georeferenced CDC model which was the source of this model.
Upstream bounding cross-section of Stonegate.
Interpolated cross-section.
Paved side slopes of concrete block.
Effective flow limit set at Overton Levee in ROB.
END DESCRIPTION:
XS GIS Cut Line= 3
2309239.666768716945259.45987825     2309939.245     6944611.454
2310545.627939216944297.41560301
#Sta/Elev= 30
    1000   580.4 1074.57  578.32 1099.51  579.27 1124.39  578.15 1346.09  577.29
 1386.89  575.59 1621.93  573.42 1746.31   577.9 1845.82  579.08    2158   578.5
    2164   578.5    2164     577    2189     577    2189   578.5    2190     580
    2199     583    2225     583    2249     575    2268  573.25 2293.61  572.71
 2351.04  552.78 2370.19  548.75 2412.76  545.15 2446.29  545.15 2484.85  548.38
 2510.62  552.17  2550.5  567.88 2570.43  573.62 2610.55  575.96 2636.46  580.87
#Mann= 7 ,-1,0
    1000     .06       0    2158    .035       0    2164    .025       0
    2189    .035       0    2199    .019       0 2370.19    .035       0
 2484.85    .019       0
#XS Ineff= 1 ,-1
    1655    2158     580
Permanent Ineff=
       F
Bank Sta=2293.61,2570.43
XS Rating Curve= 0 ,0
Exp/Cntr=0.5,0.3

Type RM Length L Ch R = 3 ,25652   ,,,
BEGIN DESCRIPTION:
Stonegate/Clear Fork Main Street
Data from bridge plans.  Concrete block on river side slopes.
END DESCRIPTION:
Node Name=Stonegate/Clear
Bridge Culvert--1,0,-1,-1, 0
Deck Dist Width WeirC Skew NumUp NumDn MinLoCord MaxHiCord MaxSubmerge Is_Ogee
0.5,80,2.6,0, 25, 25, , , 0.98, 0, 0,0,,
    1655    1755    1855    1955    2155    2158    2205    2255    2305    2355
    2405    2455    2505    2555    2605    2655    2705    2855    2905    2955
    3055    3105    3155    3205    3255
     580   580.8  585.82  591.31  603.41  603.64  606.43  609.26   611.3  612.53
  612.98  613.16  612.66  611.33  609.16  606.18  602.93  593.18  599.93  586.68
  580.18  576.99  574.25  572.01  570.28
                                          597.64  600.05  602.61  605.17  606.43
  606.46   606.5  606.53   605.2  602.44  599.68  596.91
    1564    1664    1764    1864    2064    2067    2114    2164    2214    2264
    2314    2364    2414    2464    2514    2564    2614    2764    2814    2864
    2964    3014    3064    3114    3164
     580   580.8  585.82  591.31  603.41  603.64  606.43  609.26   611.3  612.53
  612.98  613.16  612.66  611.33  609.16  606.18  602.93  593.18  599.93  586.68
  580.18  576.99  574.25  572.01  570.28
                                          597.64  600.05  602.61  605.17  606.43
  606.46   606.5  606.53   605.2  602.44  599.68  596.91
Pier Skew, UpSta & Num, DnSta & Num=  ,2320.35, 2 ,2229.35, 2 , 0 , 0 , 0 ,,
     5.5     5.5
  545.11  606.54
     5.5     5.5
  545.11  606.54
Pier Skew, UpSta & Num, DnSta & Num=  ,2540.35, 2 ,2449.35, 2 , 0 , 0 , 0 ,,
     5.5     5.5
  545.11  606.54
     5.5     5.5
  545.11  606.54
BR Coef=-1 , 0 , 0 ,, 0 ,,,0.8,-1,,0,
WSPro=,,,, 1 ,,,, 0 ,,,, 0 ,,,,-1 ,-1 ,-1 , 0 , 0 , 0 , 0 , 0
BC Design=,, 0 ,, 0 ,,,,,,
BC Use User HTab Curves=0
BC User HTab FreeFlow(D)= 0

Type RM Length L Ch R = 1 ,25612   ,43.4,42.3,40.9
BEGIN DESCRIPTION:
This cross section corresponds to cross section 25618 of the non-georeferenced CDC model which was the source of this model.
Downstream bounding cross-section of Stonegate.
Interpolated cross-section.
Paved side slopes of concrete block.
Effective flow limit set at Overton Levee in ROB.
END DESCRIPTION:
XS GIS Cut Line= 3
2309445.706353996945347.86257521     2310009.001     6944671.909
2310595.700238596944359.59845725
#Sta/Elev= 30
    1000  580.18 1069.33  578.42 1092.52  578.89 1115.65  577.49 1416.32  575.87
 1578.23  572.95 1601.35  574.91    1717  578.31 1832.64  579.41    2067   578.5
    2073   578.5    2073     577    2098     577    2098   578.5    2099     580
    2108     583    2134     583    2158     575    2172     575 2202.71  572.56
 2261.06  552.21 2280.52  548.48 2323.77  545.02 2356.39  545.02 2400.83  548.51
 2420.79  551.89 2460.71  567.78 2480.67  573.25 2519.48  575.81 2544.54  580.41
#Mann= 7 ,-1,0
    1000     .06       0    2067    .035       0    2073    .025       0
    2098    .035       0    2108    .019       0 2280.52    .035       0
 2400.83    .019       0
#XS Ineff= 1 ,-1
    1564    2067     580
Permanent Ineff=
       F
Bank Sta=2202.71,2480.67
XS Rating Curve= 0 ,0
Exp/Cntr=0.5,0.3

Type RM Length L Ch R = 1 ,25570   ,0.9,1,1
BEGIN DESCRIPTION:
This cross section corresponds to cross section 25578 of the non-georeferenced CDC model which was the source of this model.
Downstream end paved side slopes of concrete block.
Interpolated cross-section.
Effective flow limit set at Overton Levee in ROB.
END DESCRIPTION:
XS GIS Cut Line= 3
2309613.89585912  6945423.224461     2310039.229     6944709.113
 2310620.20372676944392.01525908
#Sta/Elev= 30
    1000  580.06  1066.4  578.48  1088.6  578.67 1110.75  577.12 1308.15  576.45
 1344.48  575.77  1398.7  575.91 1487.29  574.38 1553.75  572.68 1576.22  574.86
  1664.5  577.96 1686.65  578.31  1797.4  579.34 1996.76  578.46  2063.2   577.9
  2107.5  574.91 2151.81  572.48 2171.43  566.25 2210.67  551.89  2230.3  548.33
 2273.93  544.95 2306.05  544.95 2344.67  547.93 2350.51  548.35 2370.49  551.74
 2410.43  567.72  2430.4  573.05 2451.29  574.06 2468.48  575.72 2493.06  580.16
#Mann= 5 ,-1,0
    1000     .06       0 2151.81    .019       0  2230.3    .035       0
 2344.67    .019       0  2430.4     .06       0
#XS Ineff= 2 , 0
         2151.81  572.48  2430.4          573.05
Permanent Ineff=
       F       F
Bank Sta=2151.81,2430.4
XS Rating Curve= 0 ,0
Exp/Cntr=0.3,0.1

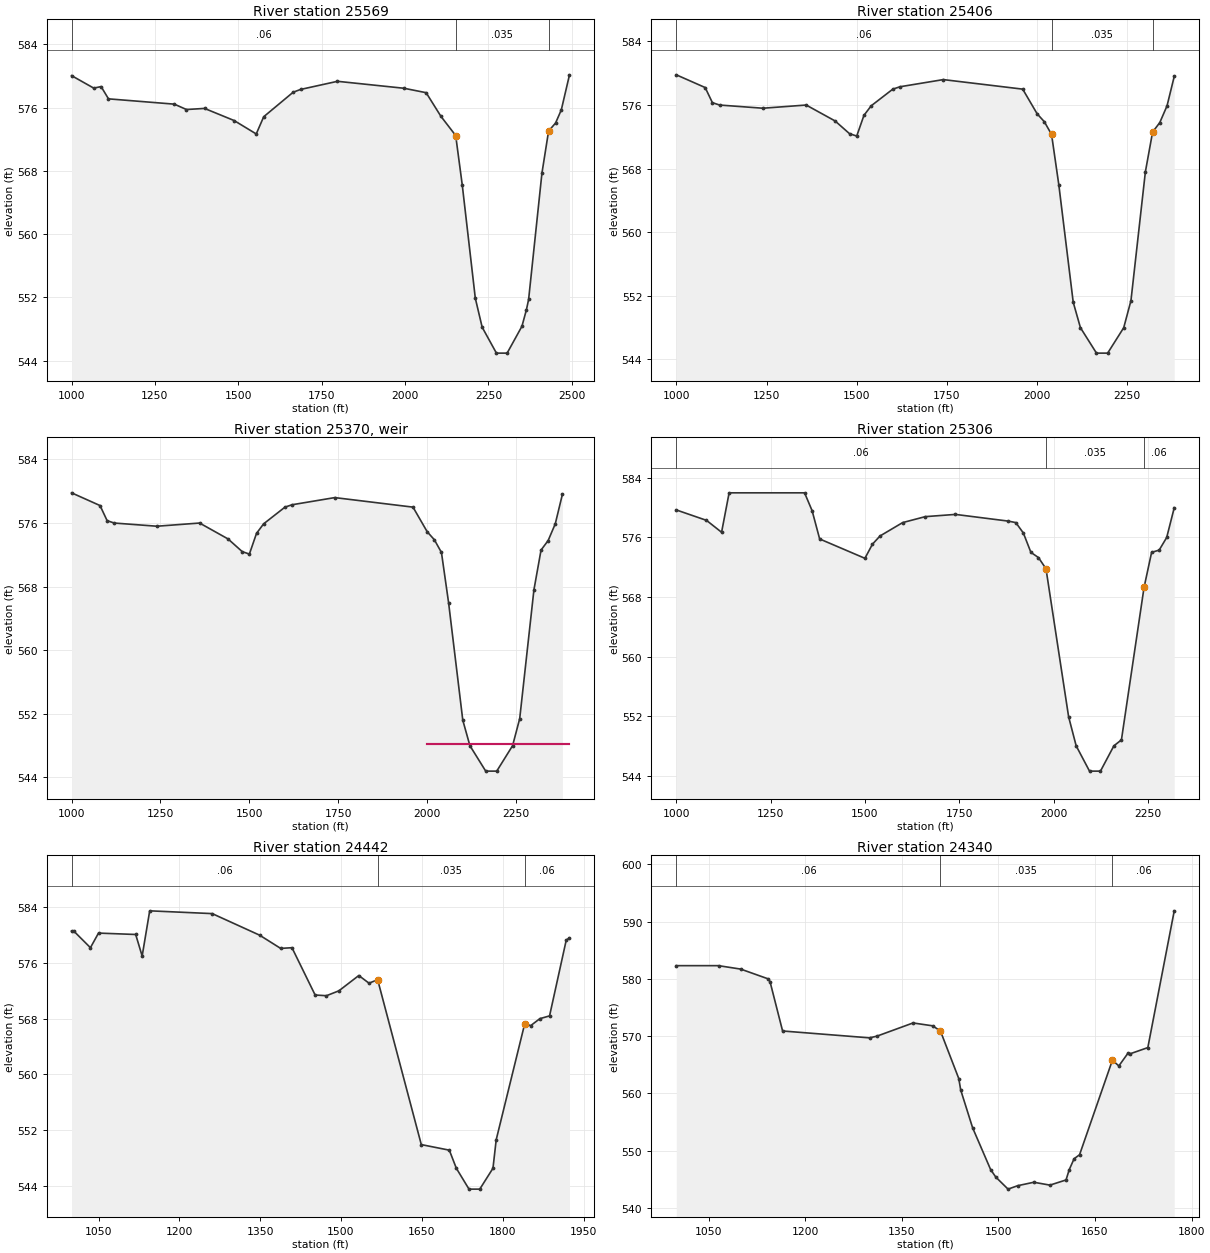
Type RM Length L Ch R = 1 ,25569   ,166,162.4,157.9
BEGIN DESCRIPTION:
This cross section corresponds to cross section 25577 of the non-georeferenced CDC model which was the source of this model.
Copy of cross-section 25578.
Interpolated cross-section.
Effective flow limit set at Overton Levee in ROB.
---------------------------------------------------------------------
CDC FW110209-01 STONEGATE/CLEAR FORK MAIN STREET BRIDGE
CROSS-SECTION 25577 - 25739
DOWNSTREAM END.
---------------------------------------------------------------------
END DESCRIPTION:
XS GIS Cut Line= 3
2309614.717974336945423.78682027      2310039.99      6944709.45
2310621.025756466944392.80325632
#Sta/Elev= 30
    1000  580.06  1066.4  578.48  1088.6  578.67 1110.75  577.12 1308.15  576.45
 1344.48  575.77  1398.7  575.91 1487.29  574.38 1553.75  572.68 1576.22  574.86
  1664.5  577.96 1686.65  578.31  1797.4  579.34 1996.76  578.46  2063.2   577.9
  2107.5  574.91 2151.81  572.48 2171.43  566.25 2210.67  551.89 2231.17  548.23
 2273.93  544.95 2306.05  544.95 2350.51  548.35 2363.85  550.43 2370.49  551.74
 2410.43  567.72  2430.4  573.05 2451.29  574.06 2468.48  575.72 2493.06  580.16
#Mann= 3 ,-1,0
    1000     .06       0 2151.81    .035       0  2430.4     .06       0
#XS Ineff= 2 , 0
         2151.81  572.48  2430.4          573.05
Permanent Ineff=
       F       F
Bank Sta=2151.81,2430.4
XS Rating Curve= 0 ,0
Exp/Cntr=0.3,0.1

Type RM Length L Ch R = 1 ,25406   ,100,100,100.1
BEGIN DESCRIPTION:
This cross section corresponds to cross section 25421 of the non-georeferenced CDC model which was the source of this model.
50 feet upstream of channel dam.  Effective flow limit set at Overton Levee in ROB.
Channel data from 1975 USACE field survey.
END DESCRIPTION:
XS GIS Cut Line= 3
2309799.271659526945515.25360241   2310217.03807   6944811.30305
 2310700.73612846944526.29905733
#Sta/Elev= 30
    1000   579.8    1080   578.2    1100   576.3    1120     576    1240   575.6
    1360     576    1440     574    1480   572.4    1500   572.1    1520   574.7
    1540   575.9    1600     578    1620   578.3    1740   579.2    1960     578
    2000   574.9    2020   573.9    2040   572.3    2060     566    2100   551.2
    2120     548 2164.47   544.8 2195.47   544.8    2240     548    2260   551.4
    2300   567.6    2320   572.6    2340   573.8    2360   575.9    2380   579.6
#Mann= 3 ,0,0
    1000     .06       0    2040    .035       0    2320     .06       0
#XS Ineff= 2 , 0
            2040   572.3    2320           572.6
Permanent Ineff=
       F       F
Bank Sta=2040,2320
XS Rating Curve= 0 ,0
Exp/Cntr=0.3,0.1

Type RM Length L Ch R = 5 ,25370   ,,,
BEGIN DESCRIPTION:
channel dam
crest elevation 548.2
END DESCRIPTION:
Node Name=channel dam
IW Pilot Flow=0
#Inline Weir SE= 2
    2000   548.2    2400   548.2
IW Dist,WD,Coef,Skew,MaxSub,Min_El,Is_Ogee,SpillHt,DesHd
33.5,5,3,0,0.95,, 0 ,,,2,2,
Inline Weir Flap Gates= 0
IW Outlet Rating Curve= 0 ,False,,

Type RM Length L Ch R = 1 ,25306   ,962.6,864.1,769.9
BEGIN DESCRIPTION:
This cross section corresponds to cross section 25321 of the non-georeferenced CDC model which was the source of this model.
50 feet downstream of channel dam.  Effective flow limit set at Overton Levee in ROB.
Channel data from 1975 USACE field survey.
END DESCRIPTION:
XS GIS Cut Line= 3
2309890.661496436945557.19963767   2310289.92703   6944884.42298
2310753.163240266944611.47529393
#Sta/Elev= 30
    1000   579.7    1080   578.3    1120   576.7    1140     582    1340     582
    1360   579.6    1380   575.8    1500   573.2    1520   575.1    1540   576.2
    1600     578    1660   578.8    1740   579.1    1880   578.2    1900     578
    1920   576.6    1940     574    1960   573.3    1980   571.8    2040   551.9
    2060     548  2095.4   544.6  2124.4   544.6    2160     548    2180   548.8
    2240   569.3    2260     574    2280   574.3    2300     576    2320     580
#Mann= 3 ,0,0
    1000     .06       0    1980    .035       0    2240     .06       0
#XS Ineff= 2 , 0
            1980   571.8    2240           569.3
Permanent Ineff=
       F       F
Bank Sta=1980,2240
XS Rating Curve= 0 ,0
Exp/Cntr=0.3,0.1

Type RM Length L Ch R = 1 ,24442   ,101.4,101.8,101.3
BEGIN DESCRIPTION:
This cross section corresponds to cross section 24456 of the non-georeferenced CDC model which was the source of this model.
102 feet upstream of Hulen Street.  Effective flow limit
set at Overton Levee in ROB.
Channel data from 1975 USACE field survey.
END DESCRIPTION:
XS GIS Cut Line= 2
   2310950.99788   6946022.53685   2311222.49012   6945139.79616
#Sta/Elev= 30
    1000   580.6    1004   580.6    1035   578.2    1050   580.3    1119   580.1
    1131     577    1145   583.5    1261   583.1    1349     580    1388   578.1
    1409   578.2    1452   571.4    1473   571.3    1496     572    1533   574.2
    1552   573.1    1568   573.6    1649   549.9    1701   549.1    1714   546.5
 1737.51   543.5 1757.51   543.5    1782   546.5    1788   550.6    1841   567.3
    1852     567    1869     568    1887   568.4    1918   579.3    1924   579.6
#Mann= 3 ,0,0
    1000     .06       0    1568    .035       0    1841     .06       0
#XS Ineff= 2 , 0
            1568   573.6    1841           567.3
Permanent Ineff=
       F       F
Bank Sta=1568,1841
XS Rating Curve= 0 ,0
Exp/Cntr=0.3,0.1

Type RM Length L Ch R = 1 ,24340   ,63.2,63.3,63.3
BEGIN DESCRIPTION:
This cross section corresponds to cross section 24355 of the non-georeferenced CDC model which was the source of this model.
Duplication of previous bridge cross-section without bridge piers.
One-foot upstream of Hulen Street.
Effective flow limit set at Overton Levee in ROB.
Channel data from 1975 USACE field survey.
END DESCRIPTION:
XS GIS Cut Line= 2
2311088.536827946945919.82977455  2311315.773221 6945180.9843092
#Sta/Elev= 30
    1000   582.3  1065.5   582.3    1100   581.7  1142.5     580  1145.5   579.5
    1165   570.9    1300   569.7  1311.5     570  1367.5   572.3    1398   571.8
    1410   570.9  1438.5   562.6  1441.5   560.6    1460     554    1488   546.7
    1496   545.4    1515   543.3    1530   543.9    1555   544.5    1580     544
    1605   544.9    1610   546.7  1617.5   548.6    1626   549.3    1677   565.8
    1687   564.8    1701     567    1704   566.9    1732     568    1773  591.87
#Mann= 3 ,0,0
    1000     .06       0    1410    .035       0    1677     .06       0
#XS Ineff= 2 , 0
            1410   570.9    1677           565.8
Permanent Ineff=
       F       F
Bank Sta=1410,1677
XS Rating Curve= 0 ,0
Exp/Cntr=0.5,0.3

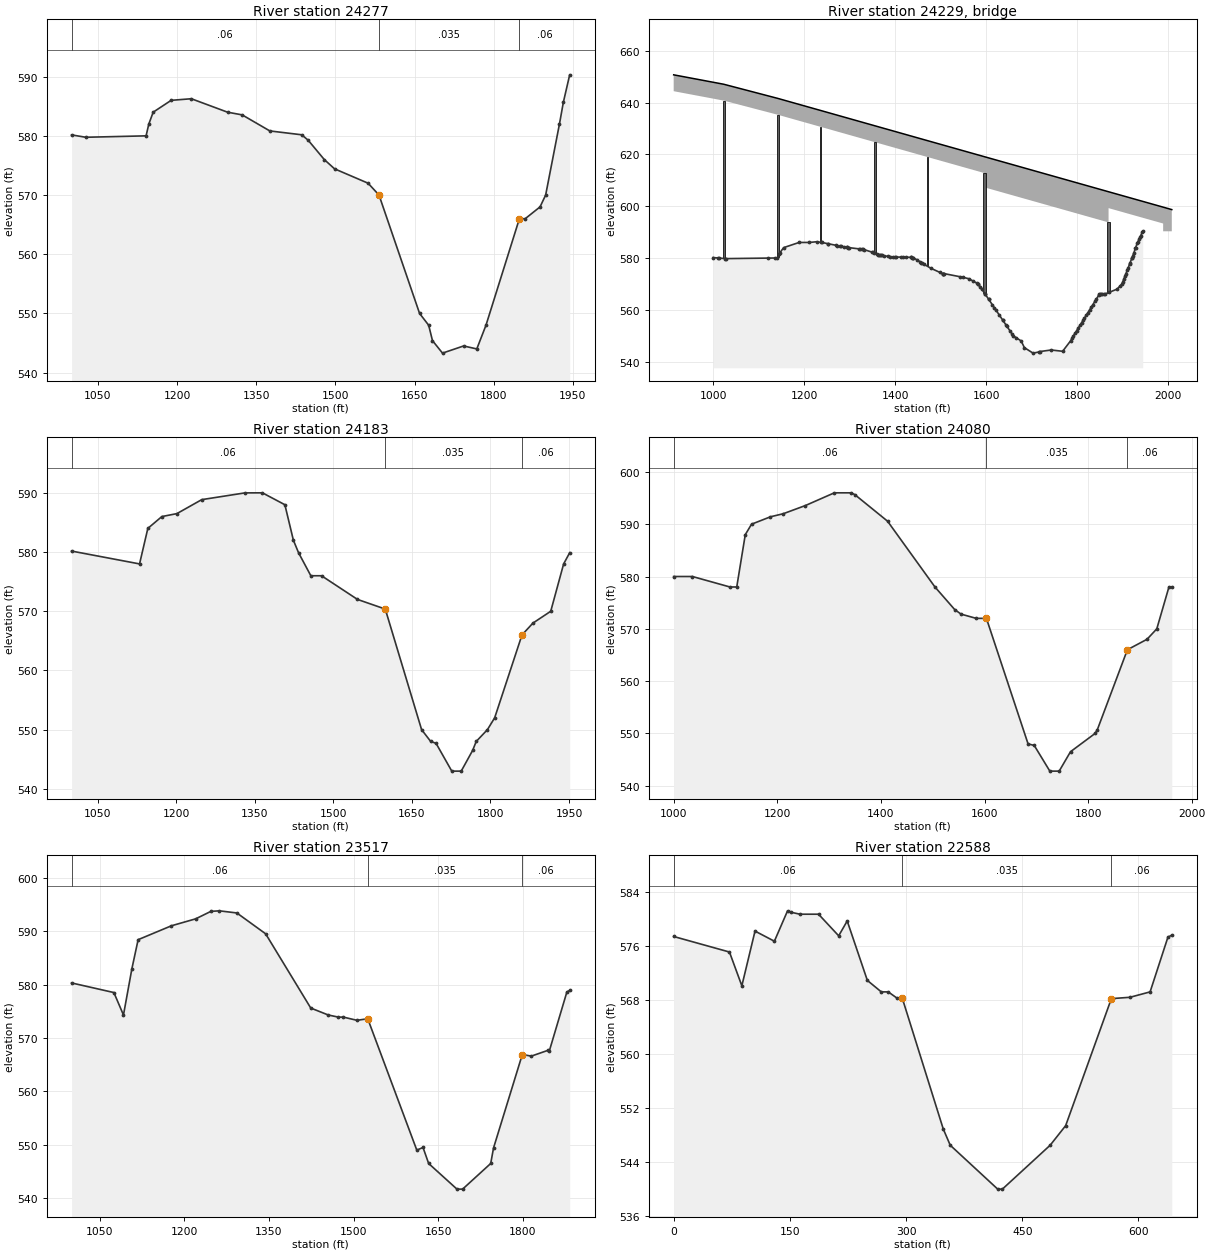
Type RM Length L Ch R = 1 ,24277   ,93.8,93.9,93.8
BEGIN DESCRIPTION:
This cross section corresponds to cross section 24293 of the non-georeferenced CDC model which was the source of this model.
Upstream Hulen Street.
---------------------------------------------------------------------
CDC FW111809-01 SH121/SOUTHWEST PARKWAY
CROSS-SECTION 24191 - 24293
UPSTREAM END.
---------------------------------------------------------------------
END DESCRIPTION:
XS GIS Cut Line= 4
2311101.615438446946091.33791827      2311104.95      6946080.51
      2311376.13      6945199.942311379.464561566945189.11208173
#Sta/Elev= 30
    1000  580.16 1026.99  579.76  1141.2     580 1146.41     582 1154.68     584
 1188.71     586 1226.98  586.27 1295.54     584 1323.39  583.54 1375.78  580.83
 1436.16  580.18 1448.53  579.25  1478.9     576 1498.37  574.43 1561.93     572
 1582.65     570 1659.54     550  1676.8     548    1684   545.4    1703  543.29
    1743   544.5    1768     544 1785.39     548 1848.73     566 1859.72     566
  1887.9     568  1898.5     570 1924.66     582 1932.01  585.66 1944.04  590.31
#Mann= 3 ,0,0
    1000     .06       0 1582.65    .035       0 1848.73     .06       0
Bank Sta=1582.65,1848.73
XS Rating Curve= 0 ,0
Exp/Cntr=0.5,0.3

Type RM Length L Ch R = 3 ,24229   ,,,
BEGIN DESCRIPTION:
Hulen Street
Data from bridge plans.  Old Hulen Street bridge removed.  Part of SH 121/Southwest Parkway project.
Paved side slopes of concrete block under bridge.
END DESCRIPTION:
Node Name=Hulen Street
Bridge Culvert--1,0,-1,-1, 0
Deck Dist Width WeirC Skew NumUp NumDn MinLoCord MaxHiCord MaxSubmerge Is_Ogee
0.5,93,2.6,0, 13, 13, , , 0.95, 0, 0,0,,
     913    1023    1142    1236    1356    1471    1596    1596    1869    1869
    1989    1989    2008
  650.69  647.06  641.59  636.94  630.99  625.29   619.1   619.1  605.57  605.57
  599.63  599.63  598.68
  644.37  640.74  635.27  630.62  624.67  618.97  612.78  607.27  593.74  599.25
  593.31     520     520
     913    1023    1142    1236    1356    1471    1596    1596    1869    1869
    1989    1989    2008
  650.69  647.06  641.59  636.94  630.99  625.29   619.1   619.1  605.57  605.57
  599.63  599.63  598.68
  644.37 639.326  635.27  630.62  624.67  618.97  612.78  607.27  593.74  599.25
  593.31     520     520
Pier Skew, UpSta & Num, DnSta & Num=  ,1023, 2 ,1023, 2 , 0 , 0 , 0 ,,
       4       4
     520  640.74
       4       4
     520  640.74
Pier Skew, UpSta & Num, DnSta & Num=  ,1142, 2 ,1142, 2 , 0 , 0 , 0 ,,
       4       4
     520  635.27
       4       4
     520  635.27
Pier Skew, UpSta & Num, DnSta & Num=  ,1236, 2 ,1236, 2 , 0 , 0 , 0 ,,
     3.5     3.5
     520  630.62
     3.5     3.5
     520  630.62
Pier Skew, UpSta & Num, DnSta & Num=  ,1356, 2 ,1356, 2 , 0 , 0 , 0 ,,
     3.5     3.5
     520  624.67
     3.5     3.5
     520  624.67
Pier Skew, UpSta & Num, DnSta & Num=  ,1471, 2 ,1471, 2 , 0 , 0 , 0 ,,
     3.5     3.5
     520  618.97
     3.5     3.5
     520  618.97
Pier Skew, UpSta & Num, DnSta & Num=  ,1596, 2 ,1596, 2 , 0 , 0 , 0 ,,
       5       5
     520  612.78
       5       5
     520  612.78
Pier Skew, UpSta & Num, DnSta & Num=  ,1869, 2 ,1869, 2 , 0 , 0 , 0 ,,
       5       5
     520  607.27
       5       5
     520  607.27
BR Coef=-1 , 0 , 0 ,, 0 ,,,0.8,-1,,0,
WSPro=,,,, 1 ,,,, 0 ,,,, 0 ,,,,-1 ,-1 ,-1 , 0 , 0 , 0 , 0 , 0
BR U #Sta/Elev= 147
    1000  580.16 1011.18  580.01 1012.21     580 1025.37  579.78 1026.99  579.76
 1120.43     580 1134.63     580  1141.2     580  1145.4  581.63 1146.41     582
 1154.68     584 1188.71     586 1211.32     586 1226.98  586.27 1236.93  586.04
 1238.51     586 1251.75  585.52 1253.25  585.46 1268.91  584.93 1272.75   584.8
 1279.22   584.6 1281.81  584.52 1287.04  584.34 1293.14   584.1 1293.84  584.08
 1295.54     584 1298.18     584 1321.32  583.51 1323.39  583.54 1326.38  583.38
 1328.19  583.34 1332.32   583.2 1348.06  582.31 1350.52   582.2 1353.62     582
 1360.61  581.42 1362.84  581.29 1364.68  581.18 1366.32  581.11 1369.03  581.07
  1370.9  580.98 1375.78  580.83 1384.09  580.63  1387.6  580.54  1394.8  580.43
 1399.81   580.4 1402.39  580.34 1412.87  580.36 1416.13   580.3 1423.64  580.33
 1433.62  580.25 1434.54  580.24 1436.16  580.18 1438.27     580 1439.63     580
 1448.53  579.25 1453.96  578.62 1457.14  578.25 1459.31     578  1463.6  577.53
  1478.9     576 1498.37  574.43 1504.82     574 1505.34     574 1505.84     574
 1506.91     574  1542.4  572.76  1549.2  572.54 1561.93     572 1571.91  571.02
 1579.21  570.31 1581.09  570.14 1582.65     570 1587.27  568.79 1590.36     568
 1597.11  566.24 1598.06     566 1605.15  564.15 1605.74     564 1613.42     562
 1617.98  560.81 1621.11     560  1628.8     558  1636.5     556 1636.83  555.91
 1644.17     554 1644.82  553.83  1651.9     552 1656.61  550.76 1659.54     550
 1665.81  549.24  1676.8     548    1684   545.4    1703  543.29    1715   543.7
    1718   543.9    1743   544.5    1768     544 1785.39     548 1788.98  549.15
 1791.85     550 1795.38     551 1798.92     552  1802.7  553.06 1806.03     554
 1809.78  555.05 1813.19     556 1815.85  556.75  1820.3     558 1822.87  558.73
  1827.4     560  1830.8  560.96 1834.51     562 1839.93  563.52 1841.62     564
 1847.49  565.65 1848.73     566 1849.29     566 1853.18     566 1854.34     566
 1859.72     566 1861.84  566.15 1869.51   566.7  1887.9     568  1895.1  569.32
  1898.5     570 1900.08  570.71 1902.91     572 1904.94  572.93 1907.26     574
 1910.34   575.4 1911.66     576 1915.29  577.67 1916.02     578 1919.97  579.81
 1920.38     580 1922.12  580.82 1924.66     582 1927.76  583.67 1928.45     584
 1932.01  585.66 1932.79     586 1936.47  587.43 1937.86     588 1939.46  588.63
 1942.91     590 1944.04  590.31
BR U #Mann= 4
    1000     .06 1582.65    .018    1703    .035    1768    .018
BR D #Sta/Elev= 149
    1000  580.17 1005.35   580.1 1012.41  580.01 1013.09     580 1086.62  578.65
 1121.16  578.02 1122.46     578 1129.82     578 1134.29  579.76 1134.91     580
 1135.68   580.3 1138.47  581.34 1140.18     582 1144.44  583.57 1145.65     584
 1154.93  584.82 1160.84  585.25 1165.66  585.45 1168.38  585.63 1172.43     586
  1180.1     586 1184.34     586 1188.51  586.16 1189.58   586.2 1190.41  586.24
  1201.2   586.5 1207.98  586.88 1211.68  587.02 1220.54  587.54  1227.8  587.94
 1228.16  587.96 1229.04     588 1229.98     588    1231     588 1231.58     588
 1248.61  588.86 1267.01  589.15 1289.11  589.53 1290.21  589.53  1291.3  589.52
 1292.81   589.5    1296  589.44 1307.31   589.7 1307.84  589.69 1310.13  589.64
 1314.73  589.76 1315.34  589.75    1318  589.74 1318.36  589.73  1326.9  589.75
 1331.15     590 1332.44     590 1338.34     590  1362.6     590 1364.47  590.01
 1364.86     590 1385.99  589.15 1406.66     588 1407.36     588 1409.63  587.16
 1412.76     586 1413.12  585.87 1418.12     584 1420.26  583.24 1423.62     582
 1432.58  580.11 1432.93     580 1433.47  579.89 1436.56  579.35 1443.58   578.1
 1444.12     578  1450.4  576.98 1452.55  576.61 1454.17  576.37 1456.94     576
 1458.24     576 1459.22     576 1459.82     576 1472.82     576 1475.16     576
 1477.37     576 1509.98  574.13 1512.87     574 1531.76  572.86 1546.03     572
 1555.87  571.64 1597.74   570.4 1598.09   570.4 1598.89  570.41 1600.36     570
 1606.14  568.29 1607.13     568 1613.12  566.23 1613.91     566 1620.14  564.16
 1620.69     564 1627.46     562 1631.54   560.8 1634.26     560 1640.14  558.28
 1641.12     558 1641.76  557.81 1647.98     556 1649.25  555.62 1654.78     554
 1656.44  553.52 1661.62     552 1663.55  551.43 1668.46     550 1685.88     548
    1696   547.7    1704   546.5 1726.13  542.99 1744.13  542.99    1766   546.5
 1772.76     548 1777.07   548.4  1794.2     550 1802.86  551.22 1808.03     552
 1812.12  553.08 1815.59     554 1816.64  554.28 1823.12     556 1825.14  556.53
 1830.56     558 1831.73  558.32 1837.97     560 1842.92  561.33 1845.43     562
 1847.17  562.48 1852.83     564 1854.92  564.57  1860.2     566 1879.55  567.84
 1881.09     568 1891.89  568.63  1915.1     570 1918.54  571.12 1921.32     572
 1926.68  573.76 1927.42     574 1932.66  575.69  1933.6     576 1939.19  577.82
 1939.74     578 1950.49  579.99 1950.99  579.97 1951.29  579.89
BR D #Mann= 4
    1000     .06 1598.09    .018 1668.46    .035  1794.2    .018
BC Design=,, 0 ,, 0 ,,,,,,
BC Use User HTab Curves=0
BC User HTab FreeFlow(D)= 0

Type RM Length L Ch R = 1 ,24183   ,103.5,103.6,103.6
BEGIN DESCRIPTION:
This cross section corresponds to cross section 24191 of the non-georeferenced CDC model which was the source of this model.
Downstream Hulen Street.
---------------------------------------------------------------------
CDC FW111809-01 SH121/SOUTHWEST PARKWAY
CROSS-SECTION 24191 - 32940
DOWNSTREAM END.
---------------------------------------------------------------------
END DESCRIPTION:
XS GIS Cut Line= 2
     2311192.585   6946114.91789    2311472.1179   6945206.72188
#Sta/Elev= 30
    1000  580.17 1129.82     578 1145.65     584 1172.43     586  1201.2   586.5
 1248.61  588.86 1331.15     590 1364.47  590.01 1407.36     588 1423.62     582
 1433.47  579.89 1456.94     576 1477.37     576 1546.03     572 1598.09   570.4
 1600.36     570 1668.46     550 1685.88     548    1696   547.7 1726.13  542.99
 1744.13  542.99    1766   546.5 1772.76     548  1794.2     550 1808.03     552
  1860.2     566 1881.09     568  1915.1     570 1939.74     578 1951.29  579.89
#Mann= 3 ,0,0
    1000     .06       0 1598.09    .035       0  1860.2     .06       0
Bank Sta=1598.09,1860.2
XS Rating Curve= 0 ,0
Exp/Cntr=0.5,0.3

Type RM Length L Ch R = 1 ,24080   ,519.8,562.4,609.1
BEGIN DESCRIPTION:
This cross section corresponds to cross section 24091 of the non-georeferenced CDC model which was the source of this model.
Effective flow limit set at Overton Levee in ROB.
END DESCRIPTION:
XS GIS Cut Line= 4
2311283.936842156946169.78526674  2311285.597239 6946164.3906753
 2311565.1301398 6945256.19466532311566.790536656945250.80007386
#Sta/Elev= 30
    1000     580 1036.21     580  1108.5     578 1121.74     578 1138.21     588
  1150.3     590 1186.87  591.42 1211.38     592  1254.3  593.57  1310.1     596
    1343     596 1349.86  595.64 1412.83  590.58 1504.33     578 1542.36  573.69
 1554.68  572.81 1583.92     572 1603.69     572 1684.09     548    1696   547.7
 1726.13  542.79 1744.13  542.79    1766   546.5 1813.53     550  1817.8  550.71
 1875.82     566 1913.77     568  1932.6     570 1956.03     578 1961.53     578
#Mann= 3 ,0,0
    1000     .06       0 1603.69    .035       0 1875.82     .06       0
Bank Sta=1603.69,1875.82
XS Rating Curve= 0 ,0
Exp/Cntr=0.3,0.1

Type RM Length L Ch R = 1 ,23517   ,944.7,929.2,900.9
BEGIN DESCRIPTION:
This cross section corresponds to cross section 23535 of the non-georeferenced CDC model which was the source of this model.
Effective flow limit set at Overton Levee in ROB.
Channel data from 1975 USACE field survey.
END DESCRIPTION:
XS GIS Cut Line= 2
   2311588.30107   6946268.75715   2312108.92011   6945555.84815
#Sta/Elev= 30
    1000   580.3    1075   578.5    1092   574.3    1107     583    1118   588.4
    1177     591    1220   592.3    1247   593.7    1262   593.8    1293   593.4
    1344   589.5    1424   575.6    1455   574.3    1473   573.9    1482   573.9
    1506   573.3    1525   573.6    1612     549    1623   549.5    1633   546.5
 1683.19   541.7 1693.19   541.7    1743   546.5    1748   549.4    1799   566.9
    1815   566.6    1845   567.7    1847   567.6    1878   578.6    1883   578.9
#Mann= 3 ,0,0
    1000     .06       0    1525    .035       0    1799     .06       0
#XS Ineff= 2 , 0
            1525   573.6    1799           566.9
Permanent Ineff=
       F       F
Bank Sta=1525,1799
XS Rating Curve= 0 ,0
Exp/Cntr=0.3,0.1

Type RM Length L Ch R = 1 ,22588   ,762.4,756.1,747.6
BEGIN DESCRIPTION:
22604
Effective flow limit set at Overton Levee in ROB.
Channel data from 1975 USACE field survey.
END DESCRIPTION:
XS GIS Cut Line= 2
2312537.415971646946642.987046092312836.861895056946074.46587342
#Sta/Elev= 27
       0   577.4      72   575.1      88   570.1     105   578.2     130   576.7
     147   581.2     151     581     163   580.7     187   580.7     213   577.5
     224   579.7     250   570.9     268   569.2     277   569.2     288   568.3
     295   568.3     348   548.9     357   546.5   418.3     540   424.3     540
     486   546.5     506   549.4     565   568.2     589   568.4     615   569.2
     638   577.3     643   577.6
#Mann= 3 ,0,0
       0     .06       0     295    .035       0     565     .06       0
#XS Ineff= 2 , 0
             295   568.3     565           568.2
Permanent Ineff=
       F       F
Bank Sta=295,565
XS Rating Curve= 0 ,0
Exp/Cntr=0.3,0.1