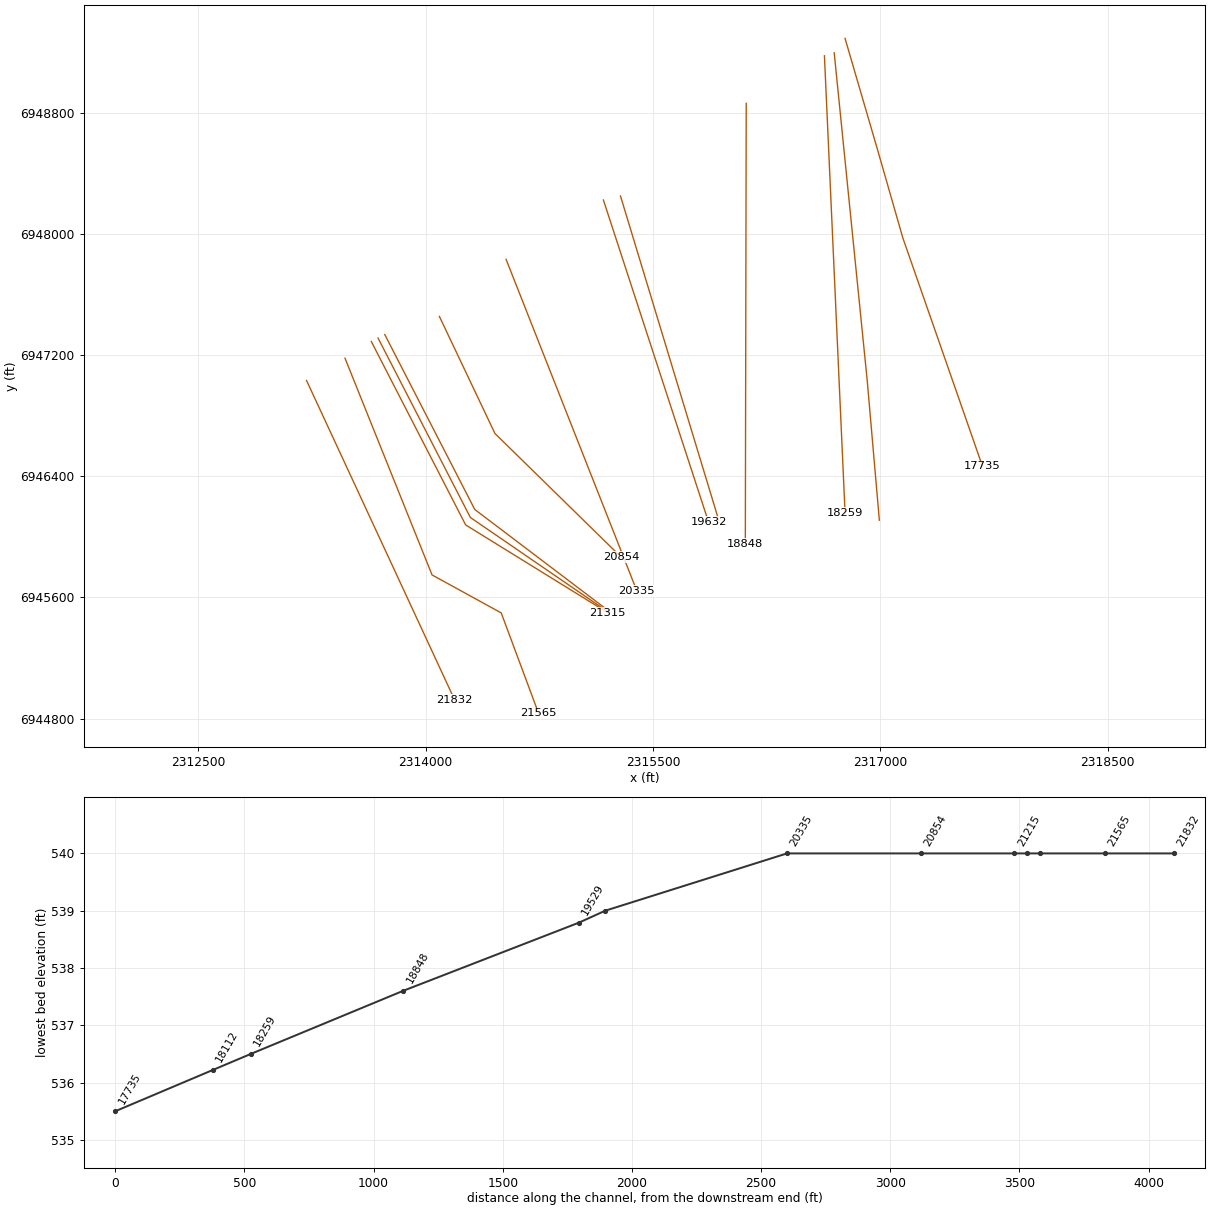
HEC-RAS study CDC_Consolidated_Model.prj: Upper Trinity CDC Consolidated Model

--- CDC_Consolidated_Model.g11 (geometry) --- (continued)

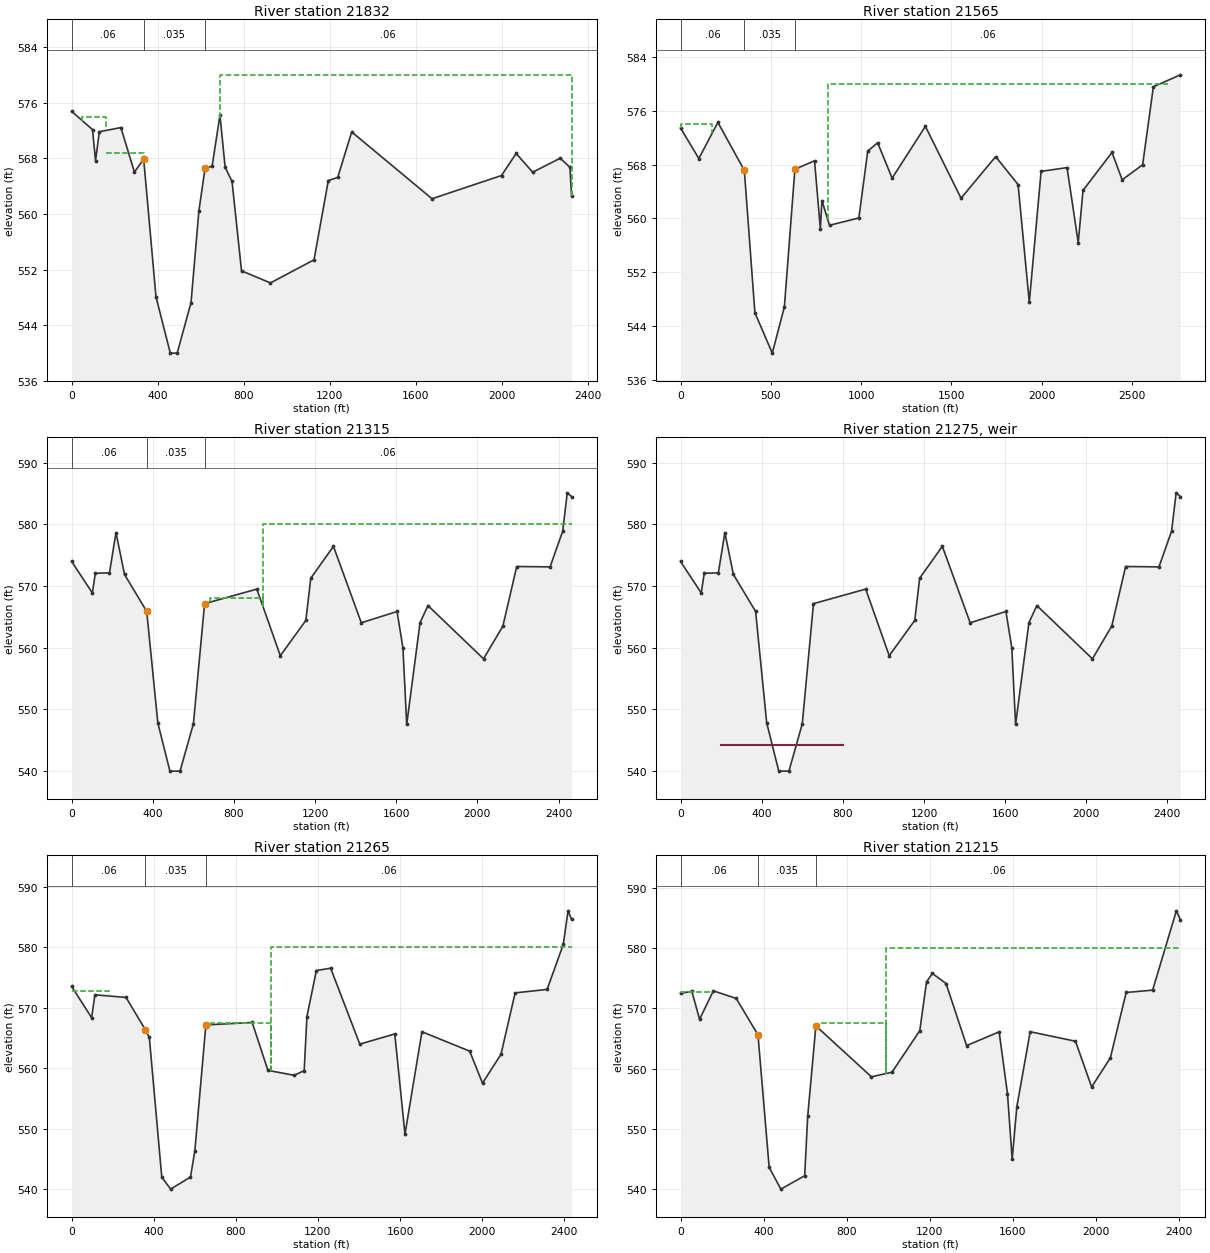
Type RM Length L Ch R = 1 ,21832   ,273.5,266.7,258.3
BEGIN DESCRIPTION:
21844
Effective flow limit set at Overton Levee in ROB.
Ground points added in ROB to account for storage within Colonial Golf Course - September 2007.
Channel data from 1975 USACE field survey.
END DESCRIPTION:
XS GIS Cut Line= 3
2313213.688897286947032.530886432313502.857938386946408.53311867
2314191.258792556944923.03280884
#Sta/Elev= 30
       0  574.75   96.93  572.13  111.09  567.67  128.73  571.82  229.02  572.42
  291.84  566.02     335  567.89  392.14  548.11  458.79     540  490.79     540
  555.26  547.27  591.63  560.41  620.29  566.54  653.35  566.88  689.72  574.21
  713.97   566.7  745.93  564.68  790.02  551.83  924.48  550.09 1127.28  553.41
 1193.71   564.8  1237.5  565.26 1302.52  571.79 1676.16  562.19 1999.37  565.53
 2067.42   568.7 2144.35     566 2272.42  568.02 2317.61   566.7    2325  562.61
#Mann= 3 ,0,0
       0     .06       0     335    .035       0  620.29     .06       0
#XS Ineff= 3 ,-1
      50   161.5     574   161.5     335   568.7     688    2325     580
Permanent Ineff=
       F       F       F
Bank Sta=335,620.29
XS Rating Curve= 0 ,0
Exp/Cntr=0.3,0.1

Type RM Length L Ch R = 1 ,21565   ,238.7,250.2,265.5
BEGIN DESCRIPTION:
Aug 2022 IFA 725    FEB 2023 IFA 815
END DESCRIPTION:
XS GIS Cut Line= 4
2313467.617851386947179.165107592314041.744327786945748.69880842
2314498.06493747 6945498.07365352314744.724549116944834.80824776
#Sta/Elev= 30
       0  573.44  101.23  568.91  206.82  574.27  353.37  567.15     412     546
  508.27     540  575.34  546.86  633.53  567.31  742.36  568.57  774.69  558.46
  783.31  562.67  825.33  558.99  988.04  560.08 1037.32  570.02 1092.15  571.25
  1172.3  565.99 1356.56  573.69 1554.16  563.01 1745.87  569.19 1870.19  565.04
 1932.34  547.55 1997.76     567 2141.55  567.56 2203.44  556.41 2230.11  564.18
 2390.45  569.81 2446.99  565.75 2560.29  567.98 2619.83  579.57 2769.64  581.34
#Mann= 3 ,-1,0
       0     .06       0  353.37    .035       0  633.53     .06       0
#XS Ineff= 2 ,-1
       0     175     574     815    2700     580
Permanent Ineff=
       F       F
Bank Sta=353.37,633.53
XS Rating Curve= 0 ,0
Exp/Cntr=0.3,0.1

Type RM Length L Ch R = 1 ,21315   ,50,50,50
BEGIN DESCRIPTION:
21329 channel from 2018 model.
50 feet upstream of channel dam.  Effective flow limits set at sta 1800 in ROB.
Ground points added in ROB to account for storage within Colonial Golf Course - September 2007.
Channel data from 1975 USACE field survey.
END DESCRIPTION:
XS GIS Cut Line= 3
2313641.088961126947289.489033922314263.720917976946078.55215134
2315201.560577726945498.82004309
#Sta/Elev= 30
       0  573.98  102.05  568.87  116.66  572.06  186.38  572.13  218.52  578.65
  260.59  571.87  370.01  565.88  424.76  547.82  484.25     540  534.25     540
  600.17  547.68  655.27  567.14  912.86   569.5 1028.59  558.71 1154.53  564.42
 1178.72  571.26 1290.58  576.43 1427.84  564.04 1604.07  565.87 1633.05  559.97
 1651.65  547.56  1717.4  564.06  1756.5  566.83 2030.42   558.2 2125.82  563.51
 2194.01  573.16 2358.42   573.1 2420.68  578.88 2443.07   585.1 2464.22   584.5
#Mann= 3 ,-1,0
       0     .06       0  370.01    .035       0  655.27     .06       0
#XS Ineff= 3 ,-1
       0     230     573     683     944     568     944    2800     580
Permanent Ineff=
       F       F       F
Bank Sta=370.01,655.27
XS Rating Curve= 0 ,0
Exp/Cntr=0.3,0.1

Type RM Length L Ch R = 5 ,21275   ,,,
BEGIN DESCRIPTION:
channel dam
crest elevation 544.3
END DESCRIPTION:
Node Name=channel dam
IW Pilot Flow=0
#Inline Weir SE= 2
     200   544.3     800   544.3
IW Dist,WD,Coef,Skew,MaxSub,Min_El,Is_Ogee,SpillHt,DesHd
35,10,3,0,0.95,, 0 ,,,2,2,
Inline Weir Flap Gates= 0
IW Outlet Rating Curve= 0 ,False,,

Type RM Length L Ch R = 1 ,21265   ,50,50,50
BEGIN DESCRIPTION:
21279 channel from 2018 model.
Upstream of channel dam.
Effective flow limit set at sta 1820 in ROB.
Ground points added in ROB to account for storage within Colonial Golf Course - September 2007.
END DESCRIPTION:
XS GIS Cut Line= 3
2313685.555079556947312.351849092314294.459045476946128.11307584
2315204.59895745 6945503.1602575
#Sta/Elev= 30
       0  573.53   97.39  568.34  113.14  572.14  264.86  571.71  359.39  566.35
  378.42   565.1     439     542  482.07     540     579     542  600.02  546.28
  653.99  567.16  879.74  567.56  956.23  559.64 1084.66  558.83 1132.97   559.6
 1146.34  568.55 1192.38  576.16 1261.93  576.54  1403.9  563.98 1574.39  565.67
 1624.12  549.08 1706.68  566.03 1939.51  562.82 2001.82  557.53 2091.92   562.3
 2160.81  572.46 2316.77  573.03 2395.68   580.5 2418.67  586.03 2435.66  584.63
#Mann= 3 ,-1,0
       0     .06       0  359.39    .035       0  653.99     .06       0
#XS Ineff= 3 ,-1
       0     180   572.7     680     969   567.5     969    2760     580
Permanent Ineff=
       F       F       F
Bank Sta=359.39,653.99
XS Rating Curve= 0 ,0
Exp/Cntr=0.3,0.1

Type RM Length L Ch R = 1 ,21215   ,364.8,360.7,355.8
BEGIN DESCRIPTION:
RECUT ROB FROM STA_____  TO END 21239
36.5 feet downstream of channel dam.  Effective flow limit set at sta 1850 in ROB.
Ground points added in ROB to account for storage within Colonial Golf Course - September 2007.
Channel data from 1975 USACE field survey.
END DESCRIPTION:
XS GIS Cut Line= 3
2313730.020869886947335.214992342314323.591861226946180.79702559
2315207.202954896945510.97290592
#Sta/Elev= 30
       0  572.52   54.51  572.85   91.62  568.21  157.96  572.93  268.16  571.67
  372.83  565.63   426.7  543.61  483.07     540  597.62  542.22  612.23  552.07
  651.59  567.11  919.21  558.65 1018.16  559.42 1151.97  566.33 1184.58  574.44
  1212.8  575.82  1278.4  574.15 1377.35  563.84 1533.99  566.12 1574.15  555.87
 1596.74  544.97 1619.32   553.7 1683.56  566.14 1901.66  564.56 1979.46  556.96
 2069.57  561.81 2145.72  572.66  2273.1  573.05 2387.29  586.22  2406.9  584.74
#Mann= 3 ,-1,0
       0     .06       0  372.83    .035       0  651.59     .06       0
#XS Ineff= 3 ,-1
       0     155   572.7     667     989  567.53     989    2740     580
Permanent Ineff=
       F       F       F
Bank Sta=372.83,651.59
XS Rating Curve= 0 ,0
Exp/Cntr=0.3,0.1

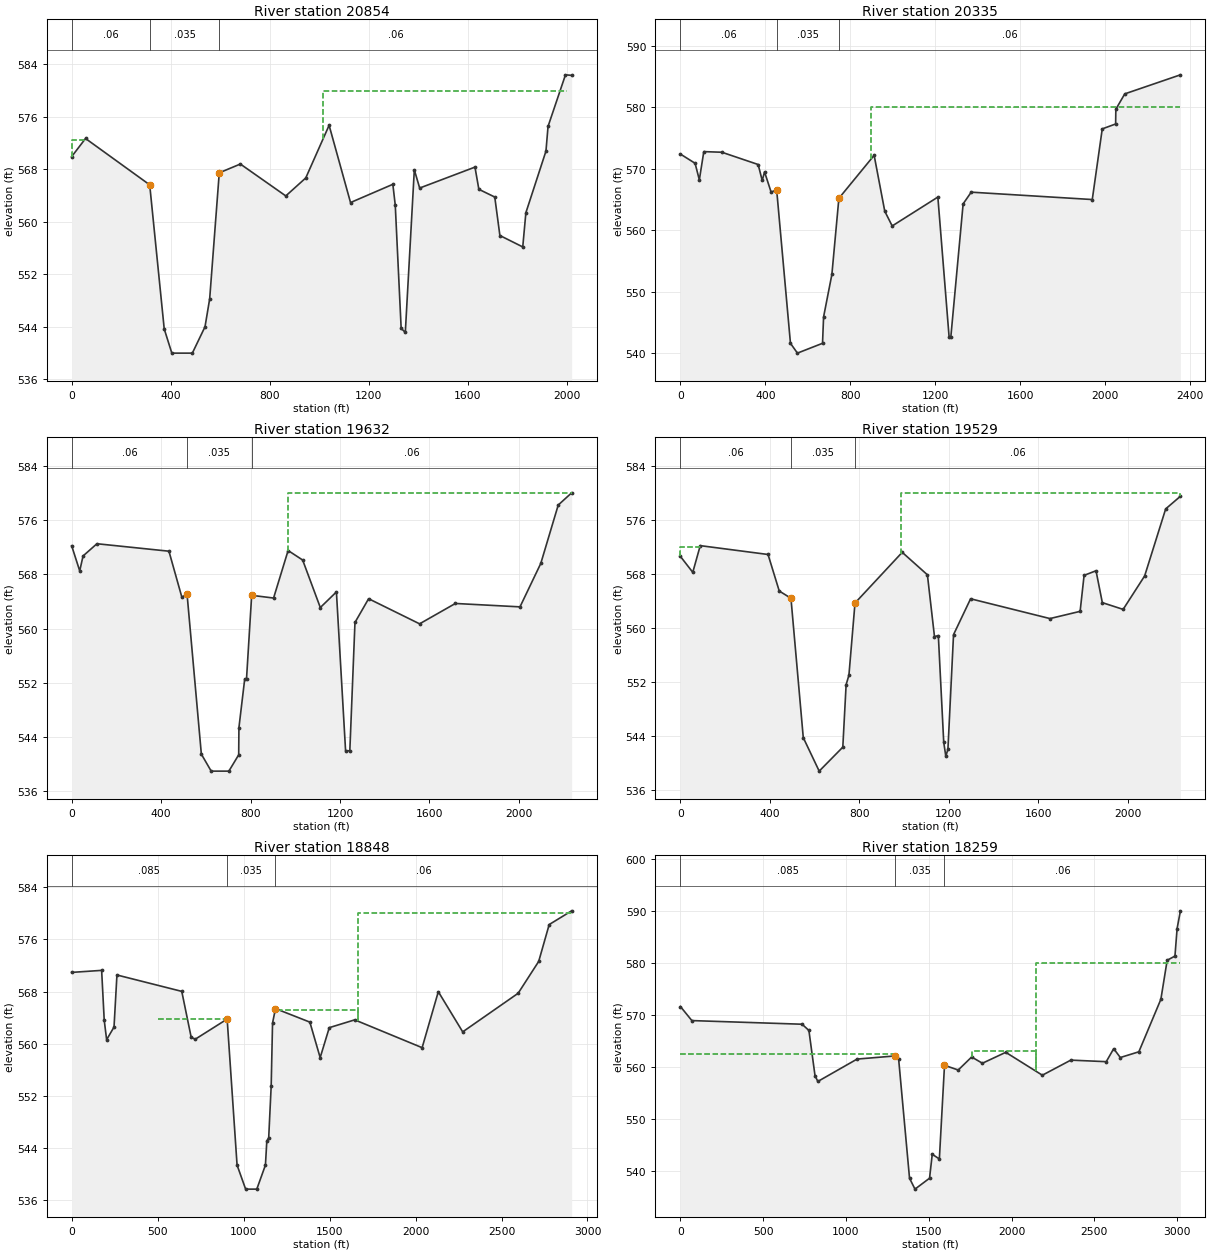
Type RM Length L Ch R = 1 ,20854   ,528.1,519.2,509.2
BEGIN DESCRIPTION:
NEW XS - NO GRADE CHANGE
END DESCRIPTION:
XS GIS Cut Line= 3
 2314090.23406026947455.200972842314456.730046396946682.38034001
2315289.057449976945866.79076384
#Sta/Elev= 30
       0  569.94   56.07   572.7   315.4  565.64  374.06  543.69  404.82     540
  487.75     540  538.96  544.02  557.78  548.27  596.51  567.47  681.73  568.81
  865.43  563.95   946.1  566.69 1040.43  574.71 1127.02  562.94 1298.05  565.72
 1307.85  562.53 1331.65  543.77 1348.45  543.16 1384.85  567.93 1406.45  565.15
 1629.95  568.34 1645.67  564.96 1709.97  563.78 1730.67  557.92 1823.07  556.18
 1835.69  561.39 1916.88  570.78 1925.28  574.54 1995.73   582.4 2020.68  582.32
#Mann= 3 ,-1,0
       0     .06       0   315.4    .035       0  596.51     .06       0
#XS Ineff= 2 ,-1
       0      55   572.5    1015    2000     580
Permanent Ineff=
       F       F
Bank Sta=315.4,596.51
XS Rating Curve= 0 ,0
Exp/Cntr=0.3,0.1

Type RM Length L Ch R = 1 ,20335   ,713.2,703.6,695
BEGIN DESCRIPTION:
20351
Effective flow limit set at sta 1000 in LOB at railroad track, at sta 1899 in ROB at levee.  Colonial Golf Course in ROB.
Channel data from 1975 USACE field survey.
END DESCRIPTION:
XS GIS Cut Line= 2
2314530.138036046947832.221872342315393.242937126945642.46804975
#Sta/Elev= 30
       0   572.4      69   570.9      89   568.2     110   572.8     195   572.7
     366   570.7     385   568.1     396   569.5     427   566.2     453   566.6
     518   541.6  550.81     540     669   541.6     674   545.9     713   552.8
     746   565.2     912   572.2     962   563.1     997   560.7    1212   565.4
    1265   542.6    1273   542.6    1331   564.3    1369   566.2    1939     565
    1986   576.5    2049   577.3    2050   579.7    2092   582.2    2354   585.3
#Mann= 3 ,0,0
       0     .06       0     453    .035       0     746     .06       0
#XS Ineff= 3 ,-1
       0     200     572     746     899   565.2     899    2354     580
Permanent Ineff=
       F       F       F
Bank Sta=453,746
XS Rating Curve= 0 ,0
Exp/Cntr=0.3,0.1

Type RM Length L Ch R = 1 ,19632   ,105.7,102.8,99.5
BEGIN DESCRIPTION:
19645
Effective flow limit set at sta 1000 in LOB.  Colonial
Golf Course in ROB.  Effective flow limit set at sta 1968 at levee at Colonial Golf Course.
Channel data from 1975 USACE field survey.
END DESCRIPTION:
XS GIS Cut Line= 2
2315172.249940786948223.676141922315865.725916066946097.94384484
#Sta/Elev= 30
       0   572.2      36   568.5      51   570.7     113   572.5     435   571.4
     493   564.6     516   565.1     580   541.5  624.02     539  703.02     539
     747   541.4     748   545.4     774   552.6     782   552.6     805   564.9
     903   564.5     968   571.5    1033   570.1    1112   563.1    1184   565.4
    1225     542    1244     542    1267   560.9    1328   564.4    1556   560.7
    1716   563.7    2005   563.2    2098   569.6    2176   578.2    2236     580
#Mann= 3 ,0,0
       0     .06       0     516    .035       0     805     .06       0
#XS Ineff= 3 ,-1
       0     140     572     805     968   564.9     968    2236     580
Permanent Ineff=
       F       F       F
Bank Sta=516,805
XS Rating Curve= 0 ,0
Exp/Cntr=0.3,0.1

Type RM Length L Ch R = 1 ,19529   ,718.4,680.5,635.4
BEGIN DESCRIPTION:
NEW XS. channel is 2015
END DESCRIPTION:
XS GIS Cut Line= 2
2315284.987904286948249.984816342315932.803537796946111.16822784
#Sta/Elev= 30
       0  570.58   55.13  568.23   88.56  572.18  391.57  570.87  441.66  565.46
  493.97  564.39  549.06  543.75  620.23  538.79  725.77  542.34  740.56  551.59
   753.1     553  780.26  563.68  991.33  571.19 1103.89  567.86 1135.52  558.71
 1152.74  558.86 1176.78  543.09 1186.18  540.98 1195.61  542.04 1220.66     559
 1296.93  564.31 1651.68  561.38 1786.47  562.45 1804.23  567.78 1857.52  568.46
 1885.73  563.74 1978.72  562.74 2074.85  567.69 2168.89  577.62 2234.77  579.49
#Mann= 3 ,0,0
       0     .06       0  493.97    .035       0  780.26     .06       0
#XS Ineff= 2 , 0
             100     572     986             580
Permanent Ineff=
       F       F
Bank Sta=493.97,780.26
XS Rating Curve= 0 ,0
Exp/Cntr=0.3,0.1

Type RM Length L Ch R = 1 ,18848   ,585.9,589,613.1
BEGIN DESCRIPTION:
18867
Effective flow limit set at sta 1000 in LOB at railroad
track.  Colonial Golf Course in ROB.  Effective flow limit set at sta 2500 in ROB due to upstream levee at Colonial Golf Course.
Channel data from 1975 USACE field survey.
END DESCRIPTION:
XS GIS Cut Line= 2
2316114.415051226948861.573160082316108.485929226945953.61408101
#Sta/Elev= 30
       0  570.94  174.35  571.25  189.35  563.59  203.35  560.59  246.35  562.53
  263.35  570.54  640.35  568.02  695.35  560.93  719.35  560.67  904.35  563.76
     962   541.3 1011.82   537.6 1076.82   537.6    1127   541.3    1135     545
    1146   545.5 1160.45  553.48 1168.35  563.14 1185.35  565.37 1385.35  563.29
 1445.35  557.83 1498.35  562.44 1646.35  563.64 2038.35  559.36 2132.47  567.97
 2274.35  561.79 2596.84  567.73 2716.36  572.63 2777.36   578.3 2907.97  580.41
#Mann= 3 ,0,0
       0    .085       0  904.35    .035       0 1185.35     .06       0
#XS Ineff= 4 ,-1
       0     270     570     500     905   563.7    1197    1667   565.1
    1667    2908     580
Permanent Ineff=
       F       F       F       F
Bank Sta=904.35,1185.35
XS Rating Curve= 0 ,0
Exp/Cntr=0.3,0.1

Type RM Length L Ch R = 1 ,18259   ,141.6,147,159
BEGIN DESCRIPTION:
18275
Colonial Golf Course in ROB.  Ineffective flow limit set
at sta 3150 in ROB due to upstream levee at Colonial Golf Course.
Channel data from 1975 USACE field survey.
END DESCRIPTION:
XS GIS Cut Line= 2
2316630.346105966949175.749040922316766.428839066946158.98014009
#Sta/Elev= 30
       0   571.6      69   568.9     735   568.2     776     567     813   558.3
     830   557.2    1067   561.5    1294   562.1    1318   561.5 1383.76   538.6
 1416.76   536.5 1504.76   538.6    1521   543.2    1564   542.3    1595   560.3
    1678   559.4    1759   561.9    1824   560.7    1965   562.8    2186   558.4
    2358   561.3    2572     561    2617   563.5    2657   561.8    2769   562.9
    2902     573    2940   580.5    2987   581.3    3000   586.6    3020     590
#Mann= 3 ,0,0
       0    .085       0    1294    .035       0    1595     .06       0
#XS Ineff= 4 ,-1
       0    1294   562.4    1595    1759   560.3    1759    2150     563
    2150    3020     580
Permanent Ineff=
       F       F       F       F
Bank Sta=1294,1595
XS Rating Curve= 0 ,0
Exp/Cntr=0.3,0.1

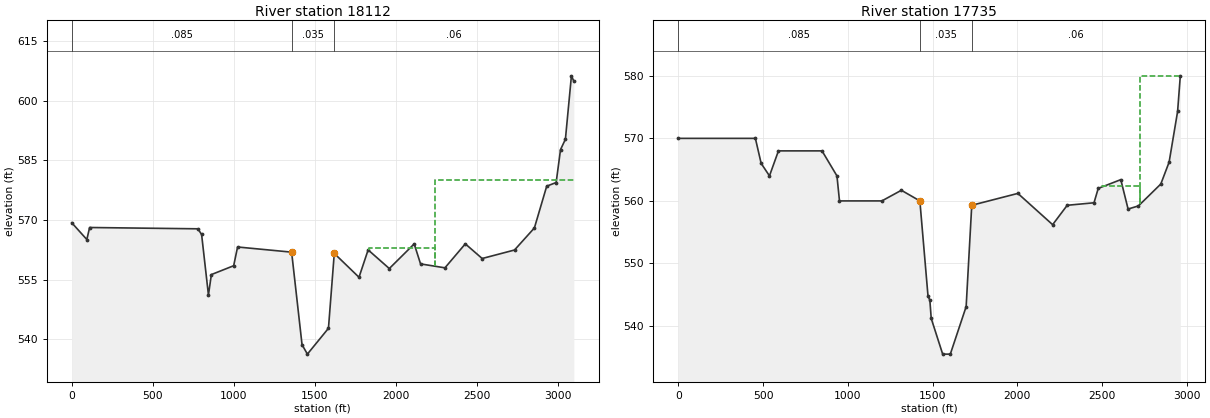
Type RM Length L Ch R = 1 ,18112   ,346.9,377.5,426.8
BEGIN DESCRIPTION:
CDC FW092622-1 Colonial Golf Course
Cross-sections 18112- 21832
END DESCRIPTION:
XS GIS Cut Line= 3
     2316694.753     6949195.346      2316911.94     6947039.269
     2316992.713     6946109.842
#Sta/Elev= 30
       0  569.31   93.08  565.09  110.16  568.12  778.53  567.79  801.65  566.36
  843.86  551.13  861.95  556.26  999.64  558.49 1023.76  563.21 1357.44  561.91
 1421.76   538.6 1454.76  536.22 1584.83  542.73 1620.77  561.59 1773.44  555.58
 1829.82  562.48 1960.48  557.78 2114.25  563.99 2153.45  558.95 2304.03  557.96
 2429.75     564  2533.9  560.31 2733.65  562.45 2856.36  568.01 2932.39  578.53
 2990.61  579.45 3017.71  587.75 3047.83  590.35 3084.97  606.33 3099.92  604.98
#Mann= 3 ,0,0
       0    .085       0 1357.44    .035       0 1620.77     .06       0
#XS Ineff= 4 ,-1
       0    1025     563    1620    1833   560.3    1833    2240     563
    2240 3099.92     580
Permanent Ineff=
       F       F       F       F
Bank Sta=1357.44,1620.77
XS Rating Curve= 0 ,0
Exp/Cntr=0.3,0.1

Type RM Length L Ch R = 1 ,17735   ,47.7,48.3,49.3
BEGIN DESCRIPTION:
17746 c/f added
Colonial Golf Course in ROB.  Ineffective flow limit
set at sta 3700 in ROB due to upstream levee at Colonial Golf Course.
Channel data from 1975 USACE field survey.
Upstream limit of Rogers Road trailhead project.
END DESCRIPTION:
XS GIS Cut Line= 5
2316766.197868386949290.864952422316794.95502871   6949192.33595
2316979.320145556948560.491085082317147.530110966947973.56607784
2317672.725910966946466.81088926
#Sta/Elev= 30
       0     570     455     570     489     566     538     564     591     568
     848     568     936     564     951     560    1201     560    1316   561.7
    1425     560    1473   544.8    1484   544.1    1492   541.2 1559.57   535.5
 1604.57   535.5    1698   543.1    1731   559.3    2003   561.2    2208   556.2
    2294   559.3    2452   559.7 2476.95     562    2610   563.4    2653   558.7
    2714   559.2    2846   562.7    2895   566.2    2945   574.3    2961     580
#Mann= 3 ,0,0
       0    .085       0    1425    .035       0    1731     .06       0
#XS Ineff= 4 ,-1
       0    1425     560    1731    2500   559.3    2500    2724   562.4
    2724    2961     580
Permanent Ineff=
       F       F       F       F
Bank Sta=1425,1731
XS Rating Curve= 0 ,0
Exp/Cntr=0.3,0.1