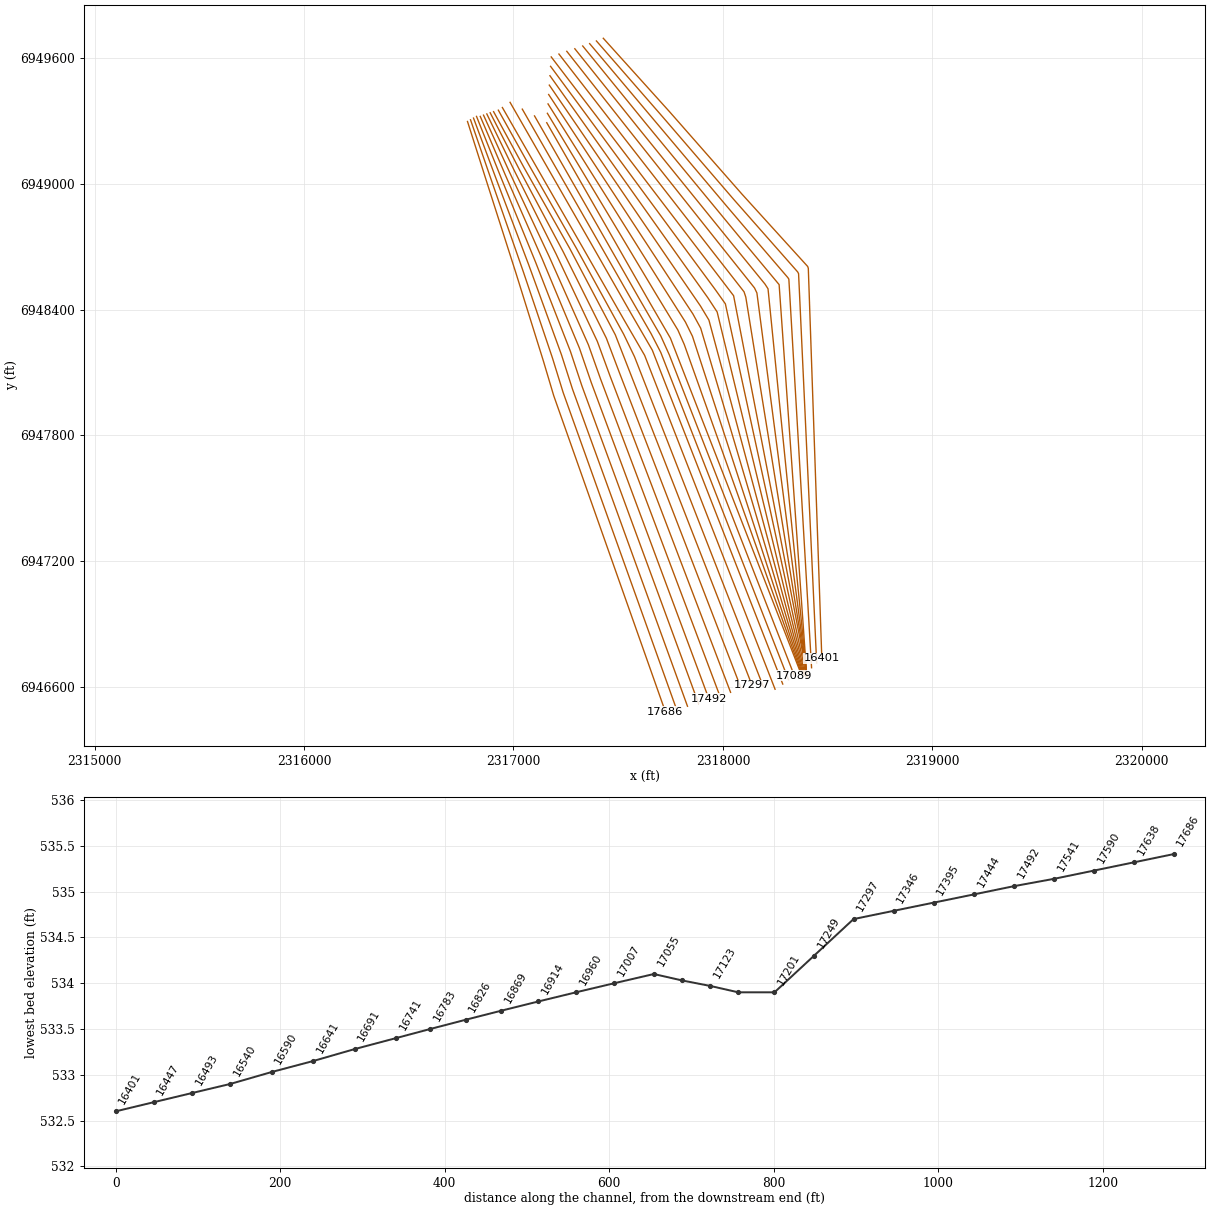
HEC-RAS study CDC_Consolidated_Model.prj: Upper Trinity CDC Consolidated Model

--- CDC_Consolidated_Model.g11 (geometry) --- (continued)

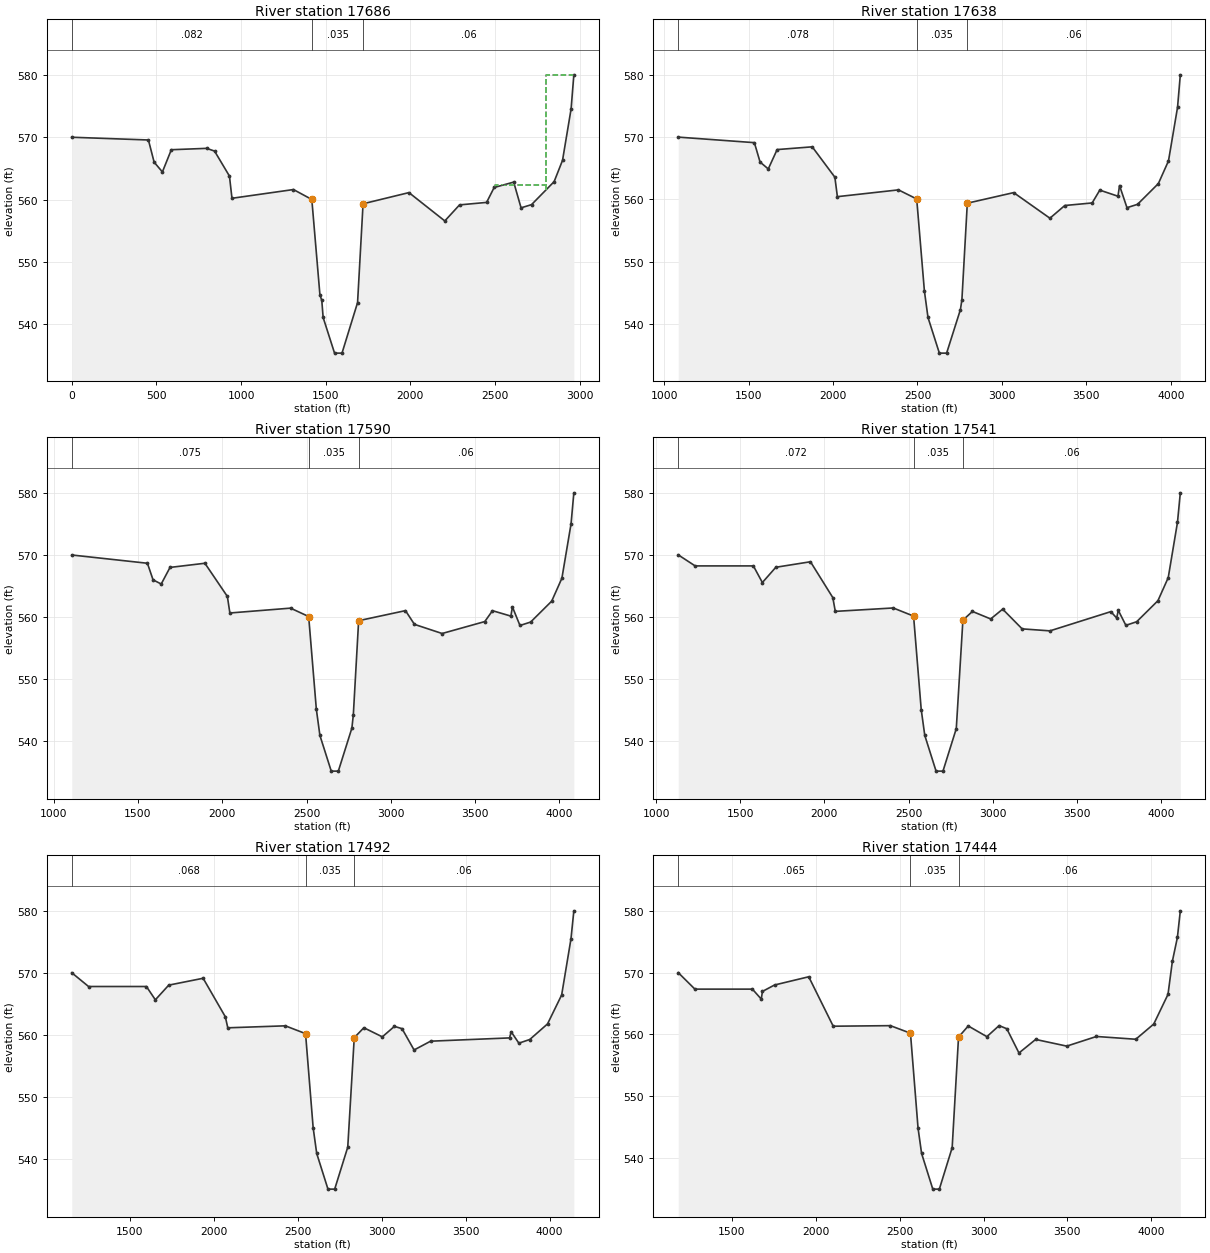
Type RM Length L Ch R = 1 ,17686   ,47.9,48.3,49.3
BEGIN DESCRIPTION:
17696.6 c/f added.
END DESCRIPTION:
XS GIS Cut Line= 6
2316780.541343636949298.991576582316875.796402456948999.75661075
2317012.218373726948573.758118932317143.173164316948154.15003425
2317192.278381056947989.401348012317725.397393556946480.15338226
#Sta/Elev= 30
       0     570  452.87  569.56  486.71     566  535.48  564.44  588.23     568
  796.97  568.22  843.73  567.78  931.62  563.78  946.55  560.22 1309.84  561.62
 1418.33  560.03 1466.25  544.75 1477.23  543.85 1485.22  541.12 1552.68  535.41
 1596.68  535.41 1688.63   543.5 1721.11  559.34 1992.21  561.13  2204.1  556.59
 2291.18  559.16 2451.16  559.56 2495.72  561.95 2611.15  562.81 2654.69  558.69
 2716.45   559.2 2850.11  562.89 2899.73   566.3 2950.35  574.54 2966.55     580
#Mann= 3 ,0,0
       0    .082       0 1418.33    .035       0 1721.11     .06       0
#XS Ineff= 2 ,-1
    2500    2800   562.4    2800    3000     580
Permanent Ineff=
       F       F
Bank Sta=1418.33,1721.11
XS Rating Curve= 0 ,0
Exp/Cntr=0.3,0.1

Type RM Length L Ch R = 1 ,17638   ,47.9,48.5,49.7
BEGIN DESCRIPTION:
This cross section corresponds to cross section 17647.3 of the non-georeferenced CDC model which was the source of this model.
END DESCRIPTION:
XS GIS Cut Line= 6
  2316794.885039 6949307.1182728 2316897.5026205 6949009.8428132
 2317045.1163826 6948587.0254391 2317186.0485118 6948169.9289979
 2317237.0267726 6948005.2367069  2317778.068807 6946493.4958043
#Sta/Elev= 30
 1083.78     570 1534.52  569.11  1568.2     566 1616.74  564.89 1669.25     568
    1877  568.44 2011.02  563.56 2025.88  560.44 2387.46  561.53 2495.44  560.07
 2540.98   545.3 2562.22  541.05 2629.56  535.32 2672.56  535.32 2754.36  542.32
 2763.04  543.91    2795  559.39 3069.47  561.09 3283.98  556.98 3372.14  559.02
 3534.11  559.43 3579.21  561.49 3686.85  560.51 3696.07  562.23 3740.15  558.67
 3802.69  559.21 3926.02  562.54 3985.89  566.18 4039.49  574.78 4055.89     580
#Mann= 3 ,0,0
 1083.78    .078       0 2495.44    .035       0    2795     .06       0
Bank Sta=2495.44,2795
XS Rating Curve= 0 ,0
Exp/Cntr=0.3,0.1

Type RM Length L Ch R = 1 ,17590   ,47.9,48.5,49.6
BEGIN DESCRIPTION:
This cross section corresponds to cross section 17598 of the non-georeferenced CDC model which was the source of this model.
END DESCRIPTION:
XS GIS Cut Line= 6
  2316809.228624 6949315.2449342 2316919.2086756 6949019.9289947
 2317072.8458059 6948614.3533444  2317228.923882 6948185.7079617
 2317281.7751039 6948021.0720204 2317830.7402554 6946506.8382614
#Sta/Elev= 30
 1107.67     570 1556.28  568.67  1589.8     566 1638.12  565.33 1690.37     568
 1897.14  568.67 2030.53  563.33 2045.32  560.67  2405.2  561.45 2512.67   560.1
 2558.13  545.19 2579.33  540.97 2646.56  535.23 2688.56  535.23 2769.03  542.16
 2777.56  544.31    2809  559.43 3086.83  561.05 3139.97  558.84 3303.97  557.37
 3557.16  559.29 3602.82  561.04 3711.77  560.17 3721.11  561.64 3765.73  558.66
 3829.03  559.21 3953.88  562.57 4014.48  566.26 4068.73  575.01 4085.33     580
#Mann= 3 ,0,0
 1107.67    .075       0 2512.67    .035       0    2809     .06       0
Bank Sta=2512.67,2809
XS Rating Curve= 0 ,0
Exp/Cntr=0.3,0.1

Type RM Length L Ch R = 1 ,17541   ,48.2,48.7,49.5
BEGIN DESCRIPTION:
This cross section corresponds to cross section 17458.6 of the non-georeferenced CDC model which was the source of this model.
END DESCRIPTION:
XS GIS Cut Line= 6
  2316823.572209 6949323.3715956 2316940.9147308 6949030.0151761
 2317105.4128483  6948627.537456 2317271.7992522 6948201.4869256
 2317326.5234352 6948036.9073338 2317883.4117039 6946520.1807185
#Sta/Elev= 30
 1131.56     570 1231.95  568.22 1578.04  568.22 1631.47  565.54  1711.5     568
 1917.29  568.89 2050.04  563.11 2064.76  560.89 2409.01  561.44 2529.89  560.13
 2575.27  545.07 2596.44   540.9 2663.55  535.14 2704.55  535.14 2783.69     542
    2823  559.48 2879.62  560.88 2988.13  559.67  3059.3  561.25 3174.96  558.07
 3340.09  557.75 3702.04  560.85  3736.7  559.82 3746.15  561.06 3791.31  558.64
 3855.37  559.22 3981.73  562.61 4043.06  566.33 4097.97  575.25 4114.78     580
#Mann= 3 ,0,0
 1131.56    .072       0 2529.89    .035       0    2823     .06       0
Bank Sta=2529.89,2823
XS Rating Curve= 0 ,0
Exp/Cntr=0.3,0.1

Type RM Length L Ch R = 1 ,17492   ,48.4,48.6,49.5
BEGIN DESCRIPTION:
This cross section corresponds to cross section 17499.3 of the non-georeferenced CDC model which was the source of this model.
END DESCRIPTION:
XS GIS Cut Line= 6
2316841.457746796949323.22228473  2316962.620786 6949040.1013575
 2317137.9798906 6948640.7215676 2317314.6746224 6948217.2658894
 2317371.2717665 6948052.74264732317932.946169186946541.96097644
#Sta/Elev= 30
 1155.44     570 1255.36  567.78  1599.8  567.78 1652.98  565.63 1732.62     568
 1937.43  569.11 2069.55  562.89  2084.2  561.11 2426.81  561.43 2547.11  560.17
 2592.42  544.96 2613.55  540.82 2680.55  535.06 2720.55  535.06 2798.35  541.84
    2837  559.52 2894.29  561.12  3004.1  559.65 3076.13  561.34 3121.55  560.97
 3193.17  557.53 3291.52  558.95 3761.62  559.48 3771.19  560.47 3816.89  558.63
 3881.71  559.22 3987.62  561.74 4071.65  566.41 4127.22  575.49 4144.22     580
#Mann= 3 ,0,0
 1155.44    .068       0 2547.11    .035       0    2837     .06       0
Bank Sta=2547.11,2837
XS Rating Curve= 0 ,0
Exp/Cntr=0.3,0.1

Type RM Length L Ch R = 1 ,17444   ,47.8,49,49.7
BEGIN DESCRIPTION:
This cross section corresponds to cross section 17450 of the non-georeferenced CDC model which was the source of this model.
END DESCRIPTION:
XS GIS Cut Line= 6
2316856.965503676949329.31145568 2316984.3268412 6949050.1875389
  2317170.546933 6948653.9056792 2317357.5499927 6948233.0448533
 2317416.0200978 6948068.5779607   2317984.761326946557.47547862
#Sta/Elev= 30
 1179.33     570 1278.77  567.33 1621.56  567.33 1674.48  565.72 1681.59  566.96
 1753.74     568 1957.57  569.33 2103.64  561.33  2444.6  561.42 2564.33   560.2
 2609.56  544.84 2630.66  540.75 2697.54  534.97 2736.54  534.97 2813.01  541.68
    2851  559.57 2908.97  561.37 3020.08  559.64 3092.95  561.43 3138.91  560.92
 3211.38     557 3310.89  559.19 3496.39  558.11 3673.63  559.67 3908.06  559.22
 4015.22  561.68 4100.24  566.48 4126.33  571.84 4156.28  575.69 4173.67     580
#Mann= 3 ,0,0
 1179.33    .065       0 2564.33    .035       0    2851     .06       0
Bank Sta=2564.33,2851
XS Rating Curve= 0 ,0
Exp/Cntr=0.3,0.1

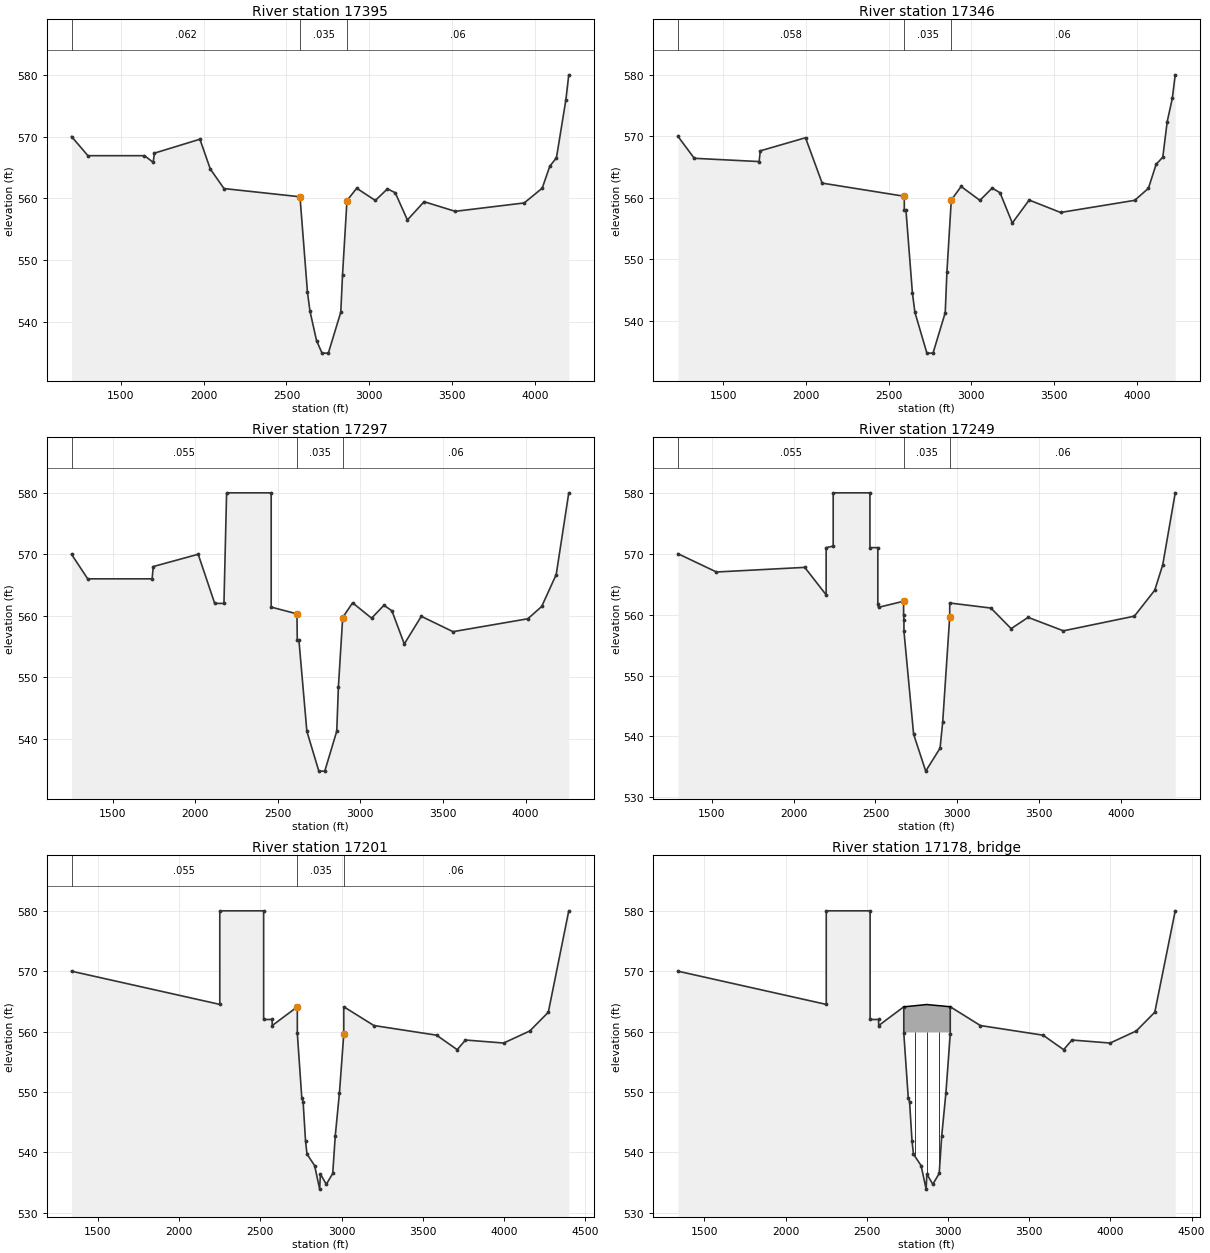
Type RM Length L Ch R = 1 ,17395   ,47.6,48.9,50.2
BEGIN DESCRIPTION:
This cross section corresponds to cross section 17400.6 of the non-georeferenced CDC model which was the source of this model.
END DESCRIPTION:
XS GIS Cut Line= 6
 2316872.73329866949335.11231885 2317006.0328896 6949060.2737172
 2317203.1139653 6948667.0897868 2317400.4253496 6948248.8238123
 2317460.7684152 6948084.41326932318036.425132866946573.33526751
#Sta/Elev= 30
 1203.22     570 1302.18  566.89 1643.32  566.89 1695.99  565.81 1703.06   567.3
 1977.71  569.56 2040.32  564.74 2123.08  561.56 2581.56  560.23 2626.71  544.73
 2641.76  541.69 2681.43  536.91 2714.54  534.88 2752.54  534.88 2827.68  541.52
 2838.04  547.52    2865  559.61 2923.65  561.61 3036.05  559.63 3109.36  561.52
 3156.28  560.88 3229.58  556.47 3330.26  559.43 3517.93  557.87  3934.4  559.23
 4042.81  561.62 4088.75  565.19 4128.83  566.55  4185.7  575.96 4203.11     580
#Mann= 3 ,0,0
 1203.22    .062       0 2581.56    .035       0    2865     .06       0
Bank Sta=2581.56,2865
XS Rating Curve= 0 ,0
Exp/Cntr=0.3,0.1

Type RM Length L Ch R = 1 ,17346   ,47.6,48.7,50.1
BEGIN DESCRIPTION:
This cross section corresponds to cross section 17351.3 of the non-georeferenced CDC model which was the source of this model.
END DESCRIPTION:
XS GIS Cut Line= 6
2316888.77476467 6949340.6521712 2317027.7389515 6949070.3599017
 2317235.6810177 6948680.2739025 2317443.3007331  6948264.602781
 2317505.5167604 6948100.24858772318087.938908166946589.52508734
#Sta/Elev= 30
 1227.11     570 1325.59  566.44 1717.49  565.91 1724.53  567.65 1997.86  569.78
 2098.35  562.41    2595  560.27    2595     558    2605     558 2643.85  544.61
 2658.88  541.44 2731.53  534.79 2768.53  534.79 2842.34  541.36 2852.52  547.96
    2879  559.66 2938.32  561.86 3052.03  559.61 3126.18  561.61 3173.64  560.84
 3247.79  555.93 3349.63  559.66 3539.46  557.64 3987.35  559.61 4070.41  561.56
 4116.88  565.45 4157.41  566.63 4184.11  572.41 4214.76  576.16 4232.56     580
#Mann= 3 ,0,0
 1227.11    .058       0    2595    .035       0    2879     .06       0
Bank Sta=2595,2879
XS Rating Curve= 0 ,0
Exp/Cntr=0.3,0.1

Type RM Length L Ch R = 1 ,17297   ,47.6,48,49
BEGIN DESCRIPTION:
This cross section corresponds to cross section 17302 of the non-georeferenced CDC model which was the source of this model.
97 feet upstream of Rogers Road.
Ineffective flow areas defined in LOB due to structures.
Channel data from 1975 USACE field survey.
END DESCRIPTION:
XS GIS Cut Line= 5
2316905.110522556949345.94086529     2317049.445   6949080.44608
   2317268.24805   6948693.45801   2317486.17609   6948280.38174
2318139.296936066946606.04812376
#Sta/Elev= 30
    1251     570    1349     566    1739     566    1746     568    2018     570
    2118     562    2174     562    2190     580    2460     580    2460   561.4
    2616   560.3    2618     556    2628     556    2676   541.2 2748.53   534.7
 2784.53   534.7    2857   541.2    2867   548.4    2893   559.7    2953   562.1
    3068   559.6    3143   561.7    3191   560.8    3266   555.4    3369   559.9
    3561   557.4    4014   559.5    4098   561.5    4186   566.7    4262     580
#Mann= 3 ,0,0
    1251    .055       0    2616    .035       0    2893     .06       0
#XS Ineff= 2 , 0
            2616   560.3    2893           557.3
Permanent Ineff=
       F       F
Bank Sta=2616,2893
XS Rating Curve= 0 ,0
Exp/Cntr=0.3,0.1

Type RM Length L Ch R = 1 ,17249   ,47.7,48.1,49.4
BEGIN DESCRIPTION:
This cross section corresponds to cross section 17254 of the non-georeferenced CDC model which was the source of this model.
END DESCRIPTION:
XS GIS Cut Line= 6
2316927.781553096949353.013804682317079.190851536949081.97179018
2317300.057483176948694.169287722317525.958752476948283.40561425
2317577.724377816948176.042345562318192.899689416946600.08203993
#Sta/Elev= 30
    1294     570 1528.83     567 2068.16  567.76 2198.63  563.25 2198.63     571
 2241.77  571.25 2241.77     580 2466.15     580 2466.15     571 2514.29     571
 2514.29   561.7 2518.67   561.2 2671.75   562.2 2671.75     560 2673.79   559.1
 2673.79   557.3 2732.88  540.36 2806.77   534.3 2894.42  538.07 2910.61   542.4
 2953.25  559.65 2953.25  561.91 3204.76  561.08  3328.5   557.7 3432.12  559.55
 3647.59  557.34 4081.01  559.75 4205.25     564 4254.04  568.16  4330.5     580
#Mann= 3 ,0,0
    1294    .055       0 2671.75    .035       0 2953.25     .06       0
#XS Ineff= 2 , 0
          2672.2  559.65  2952.9          558.15
Permanent Ineff=
       F       F
Bank Sta=2671.75,2953.25
XS Rating Curve= 0 ,0
Exp/Cntr=0.3,0.1

Type RM Length L Ch R = 1 ,17201   ,43.6,43.9,44.9
BEGIN DESCRIPTION:
This cross section corresponds to cross section 17206 of the non-georeferenced CDC model which was the source of this model.
Upstream of Rogers Road.
END DESCRIPTION:
XS GIS Cut Line= 5
  2316947.084302 6949365.6321234 2317330.1232427 6948697.9339834
 2317527.5762527 6948352.1659734 2317625.9969927 6948182.6440034
 2318248.8641827 6946588.0789534
#Sta/Elev= 30
    1337     570    2250   564.5    2250     580    2520     580    2520     562
    2572     562    2573     561  2727.5   564.1  2727.5   559.7    2755     549
    2763   548.4    2778   541.9    2787   539.7    2834   537.8    2865   533.9
  2869.5   536.4    2906   534.7  2945.5   536.5    2961   542.7    2987   549.9
  3013.5   559.6  3013.5  564.11    3199     561    3585   559.4    3712     557
    3763   558.6    3998   558.1    4159   560.1    4273   563.2    4399     580
#Mann= 3 ,0,0
    1337    .055       0  2727.5    .035       0  3013.5     .06       0
#XS Ineff= 2 , 0
          2728.4     559  3012.8           558.8
Permanent Ineff=
       F       F
Bank Sta=2727.5,3013.5
XS Rating Curve= 0 ,0
Exp/Cntr=0.5,0.3

Type RM Length L Ch R = 3 ,17178   ,,,
BEGIN DESCRIPTION:
Rogers Road
Downstream face of bridge.  Bridge data from July 1975 survey.  Minimum low chord elev. 559.87.  Bridge width 43 feet. Ineffective flow areas defined in LOB due to structures.
Channel data from 1975 USACE field survey.
END DESCRIPTION:
Node Name=Rogers Road
Bridge Culvert--1,0,-1,-1, 0
Deck Dist Width WeirC Skew NumUp NumDn MinLoCord MaxHiCord MaxSubmerge Is_Ogee
2.5,41,2.6,0, 8, 8, , , 0.95, 0, 0,0,,
  2727.5  2796.5  2799.5  2869.5  2872.5  2942.5  2945.5  3013.5
   564.1  564.28  564.29  564.48  564.47  564.29  564.29  564.11
  559.87  559.87  559.87  559.87  559.87  559.87  559.87  559.87
  2727.5  2796.5  2799.5  2869.5  2872.5  2942.5  2945.5  3013.5
   564.1  564.28  564.29  564.48  564.47  564.29  564.29  564.11
  559.87  559.87  559.87  559.87  559.87  559.87  559.87  559.87
Pier Skew, UpSta & Num, DnSta & Num=  ,2798, 2 ,2798, 2 , 0 , 0 , 0 ,,
       3       3
     535     562
       3       3
     535     562
Pier Skew, UpSta & Num, DnSta & Num=  ,2871, 2 ,2871, 2 , 0 , 0 , 0 ,,
       3       3
     535     562
       3       3
     535     562
Pier Skew, UpSta & Num, DnSta & Num=  ,2944, 2 ,2944, 2 , 0 , 0 , 0 ,,
       3       3
     535     562
       3       3
     535     562
BR Coef=-1 , 0 , 0 ,1.05, 0 ,,,0.8,-1,0.5,1,
WSPro=,,,, 1 ,,,, 0 ,,,, 0 ,,,,-1 ,-1 ,-1 , 0 , 0 , 0 , 0 , 0
BC Design=,, 0 ,, 0 ,,,,,,
BC HTab HWMax=580
BC Use User HTab Curves=0
BC User HTab FreeFlow(D)= 0

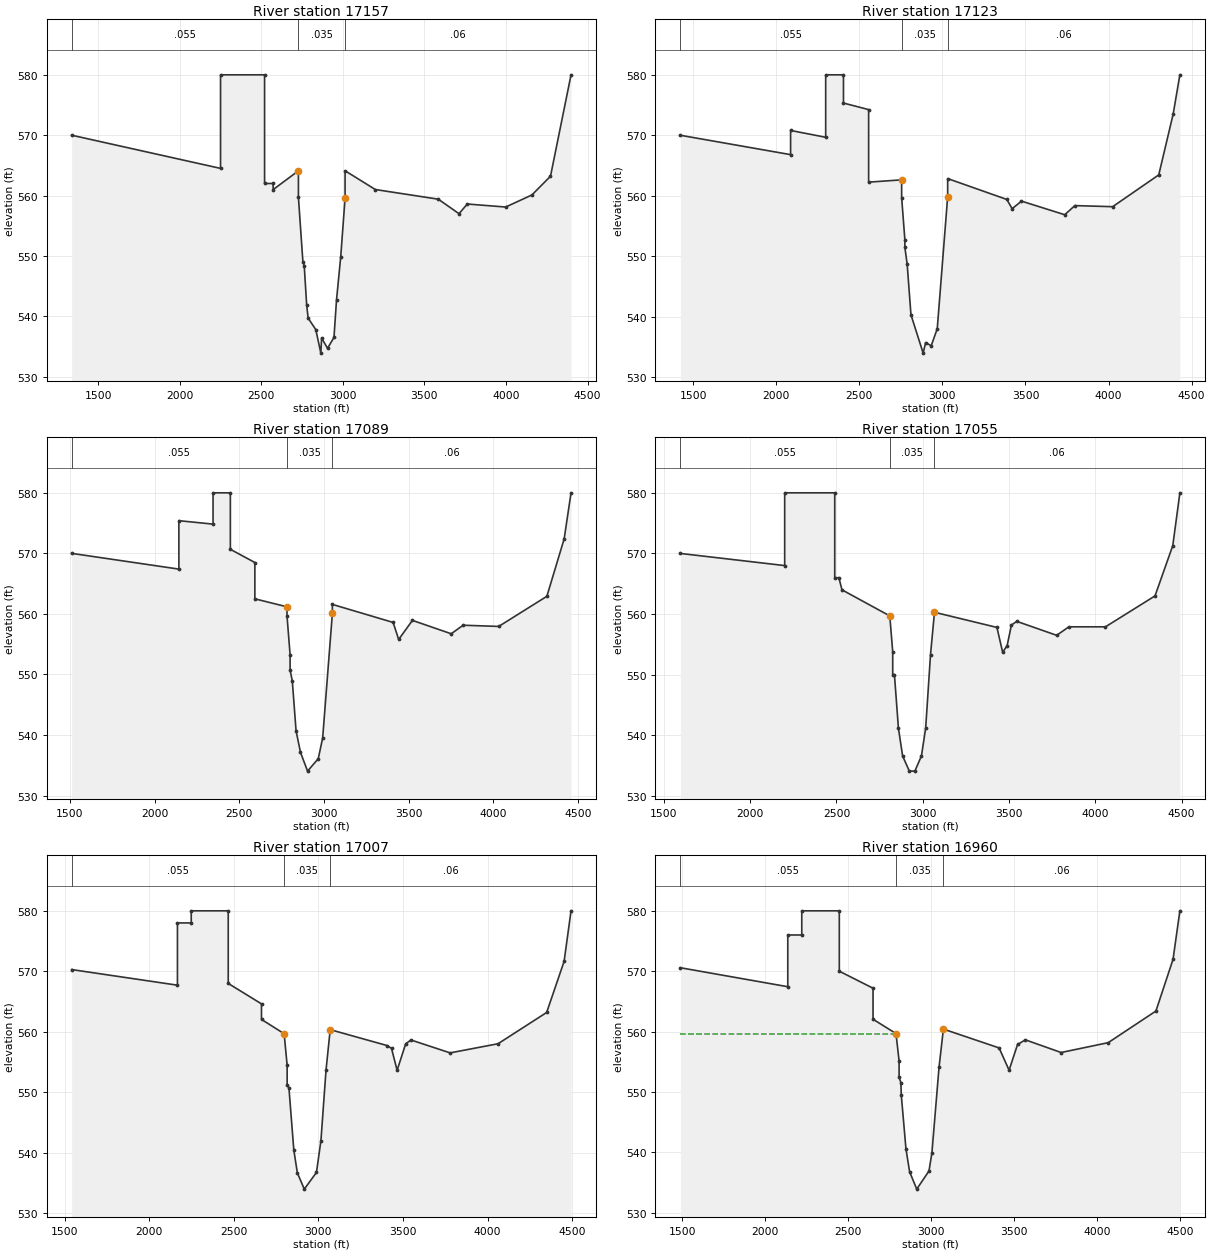
Type RM Length L Ch R = 1 ,17157   ,34.2,34.2,34.2
BEGIN DESCRIPTION:
This cross section corresponds to cross section 17162 of the non-georeferenced CDC model which was the source of this model.
One-foot downstream of Rogers Road.  Duplication of following bridge cross-section without bridge piers.
Ineffective flow areas defined in LOB due to structures.
Channel data from 1975 USACE field survey.
END DESCRIPTION:
XS GIS Cut Line= 5
  2316983.749422 6949390.4178902 2317366.7883623 6948722.7197502
 2317564.2413723 6948376.9517402 2317662.6621123 6948207.4297702
 2318285.5293023 6946612.8647202
#Sta/Elev= 30
    1337     570    2250   564.5    2250     580    2520     580    2520     562
    2572     562    2573     561  2727.5   564.1  2727.5   559.7    2755     549
    2763   548.4    2778   541.9    2787   539.7    2834   537.8    2865   533.9
  2869.5   536.4    2906   534.7  2945.5   536.5    2961   542.7    2987   549.9
  3013.5   559.6  3013.5  564.11    3199     561    3585   559.4    3712     557
    3763   558.6    3998   558.1    4159   560.1    4273   563.2    4399     580
#Mann= 3 ,0,0
    1337    .055       0  2727.5    .035       0  3013.5     .06       0
#XS Ineff= 2 , 0
          2728.4     559  3012.8           557.1
Permanent Ineff=
       F       F
Bank Sta=2727.5,3013.5
XS Rating Curve= 0 ,0
Exp/Cntr=0.5,0.3

Type RM Length L Ch R = 1 ,17123   ,33.4,34.3,33.6
XS GIS Cut Line= 6
2317042.111049016949358.024927262317348.879786826948823.27794949
2317554.765424726948463.116204462317656.830763356948286.21667063
2317703.262957646948196.258103352318313.179535886946632.85648087
#Sta/Elev= 30
 1423.33     570 2086.26   566.8 2086.26   570.8 2297.48  569.67 2297.48     580
 2404.55     580 2404.55  575.33    2556  574.25    2556  562.25 2754.67  562.63
 2754.67   559.7 2774.08  552.73 2774.08  551.47 2788.09  548.65 2810.69  540.32
 2884.13  533.97 2898.95  535.71 2932.59  535.19 2968.99     538 3031.67  559.83
 3031.67  562.84 3387.47  559.39 3419.91  557.86 3476.03  559.11  3736.3  556.86
 3797.34  558.37 4024.81  558.19 4302.23  563.45 4389.03  573.51 4429.33     580
#Mann= 3 ,0,0
 1423.33    .055       0 2754.67    .035       0 3031.67     .06       0
#XS Ineff= 2 , 0
        2755.267559.2333  3031.2          556.97
Permanent Ineff=
       F       F
Bank Sta=2754.67,3031.67
XS Rating Curve= 0 ,0
Exp/Cntr=0.5,0.3

Type RM Length L Ch R = 1 ,17089   ,35.5,34.2,33.6
XS GIS Cut Line= 6
2317100.472676026949325.631964322317401.073906286948801.63593855
   2317602.743236948448.671061442317702.986269216948275.46030972
2317743.863802986948185.086436492318340.829769466946652.84824153
#Sta/Elev= 30
 1509.67     570 2143.13   567.4 2143.13   575.4 2344.97  574.83 2344.97     580
 2447.27     580 2447.27  570.67 2591.99  568.49 2591.99  562.49 2781.83  561.17
 2781.83   559.7 2800.04  553.27 2800.04  550.73 2813.19  548.91 2835.38  540.68
  2861.5  537.13 2903.27  534.03 2966.49  536.09 2992.49  539.51 3049.83  560.07
 3049.83  561.57 3408.74  558.59 3441.45  555.78 3522.75  558.93 3751.78  556.72
 3822.17  558.13 4032.35  557.93  4316.9  562.91 4419.02   572.4 4459.67     580
#Mann= 3 ,0,0
 1509.67    .055       0 2781.83    .035       0 3049.83     .06       0
#XS Ineff= 2 , 0
        2782.133559.4667  3049.6          556.84
Permanent Ineff=
       F       F
Bank Sta=2781.83,3049.83
XS Rating Curve= 0 ,0
Exp/Cntr=0.5,0.3

Type RM Length L Ch R = 1 ,17055   ,50.6,47.9,41.3
BEGIN DESCRIPTION:
This cross section corresponds to cross section 17057 of the non-georeferenced CDC model which was the source of this model.
106 feet downstream of Rogers Road.
Ineffective flow areas defined in LOB due to structures.
Channel data from 1975 USACE field survey.
END DESCRIPTION:
XS GIS Cut Line= 5
2317158.834296616949293.23900495   2317453.26802   6948779.99393
   2317650.72103   6948434.22592   2317749.14177   6948264.70395
      2318368.48      6946672.84
#Sta/Elev= 30
    1596     570    2200     568    2200     580    2490     580    2490     566
    2514     566    2532     564    2809   559.7    2826   553.8    2826     550
    2836     550    2859   541.2  2883.4   536.6  2922.4   534.1  2954.4   534.1
  2992.4   536.6    3017   541.2    3045   553.3    3068   560.3    3430   557.8
    3463   553.7    3489   554.8    3514   558.2    3545   558.8    3776   556.5
    3847   557.9    4059   557.9    4346     563    4449   571.3    4490     580
#Mann= 3 ,0,0
    1596    .055       0    2809    .035       0    3068     .06       0
#XS Ineff= 2 , 0
            2809   559.7    3068          556.71
Permanent Ineff=
       F       F
Bank Sta=2809,3068
XS Rating Curve= 0 ,0
Exp/Cntr=0.3,0.1

Type RM Length L Ch R = 1 ,17007   ,51.6,46.9,40.4
XS GIS Cut Line= 6
2317161.885196986949338.103267752317472.667803696948821.68976239
2317681.219704566948473.845263542317784.93089106 6948303.2011182
2317815.284832076948234.408656022318373.582475486946668.23168312
#Sta/Elev= 30
 1542.14  570.29 2167.41  567.71 2167.41     578  2248.9     578  2248.9     580
 2467.62     580 2467.62     568 2664.15  564.62 2664.15  562.05 2797.86  559.69
 2815.73  554.47 2815.73  551.21 2826.25  550.75 2855.07  540.47 2876.08  536.68
 2917.09     534 2989.01  536.76 3015.41  542.03 3045.46  553.68 3070.14  560.36
 3405.45  557.74 3432.47  557.26  3465.5  553.65 3516.55  558.03 3547.57  558.65
 3778.78  556.52 4062.04  558.03  4349.3   563.2 4452.39  571.64 4493.43     580
#Mann= 3 ,0,0
 1542.14    .055       0 2797.86    .035       0 3070.14     .06       0
#XS Ineff= 2 , 0
        2797.857559.68573070.143        556.7015
Permanent Ineff=
       F       F
Bank Sta=2797.86,3070.14
XS Rating Curve= 0 ,0
Exp/Cntr=0.3,0.1

Type RM Length L Ch R = 1 ,16960   ,49.3,45.7,39.6
XS GIS Cut Line= 6
2317164.936097356949382.967530562317492.067587386948863.38559478
2317711.718379116948513.464607072317820.72001213 6948341.6982864
2317854.551678936948273.192382242318378.684950966946663.62336623
#Sta/Elev= 30
 1488.29  570.57 2134.82  567.43 2134.82     576 2219.08     576 2219.08     580
 2445.25     580 2445.25     570 2648.46  567.18 2648.46  562.04 2786.71  559.67
 2805.46  555.14 2805.46  552.43 2816.49   551.5 2818.34  549.56 2846.72  540.58
 2868.77  536.77 2911.78   533.9 2985.62  536.91  3003.3  539.95 3045.92  554.05
 3072.29  560.41 3407.89  557.29    3468   553.6 3519.09  557.86 3566.06  558.63
 3781.57  556.53 4065.08  558.16  4352.6   563.4 4455.78  571.97 4496.86     580
#Mann= 3 ,0,0
 1488.29    .055       0 2786.71    .035       0 3072.29     .06       0
#XS Ineff= 2 , 0
        2786.714559.67143072.286        556.6929
Permanent Ineff=
       F       F
Bank Sta=2786.71,3072.29
XS Rating Curve= 0 ,0
Exp/Cntr=0.3,0.1

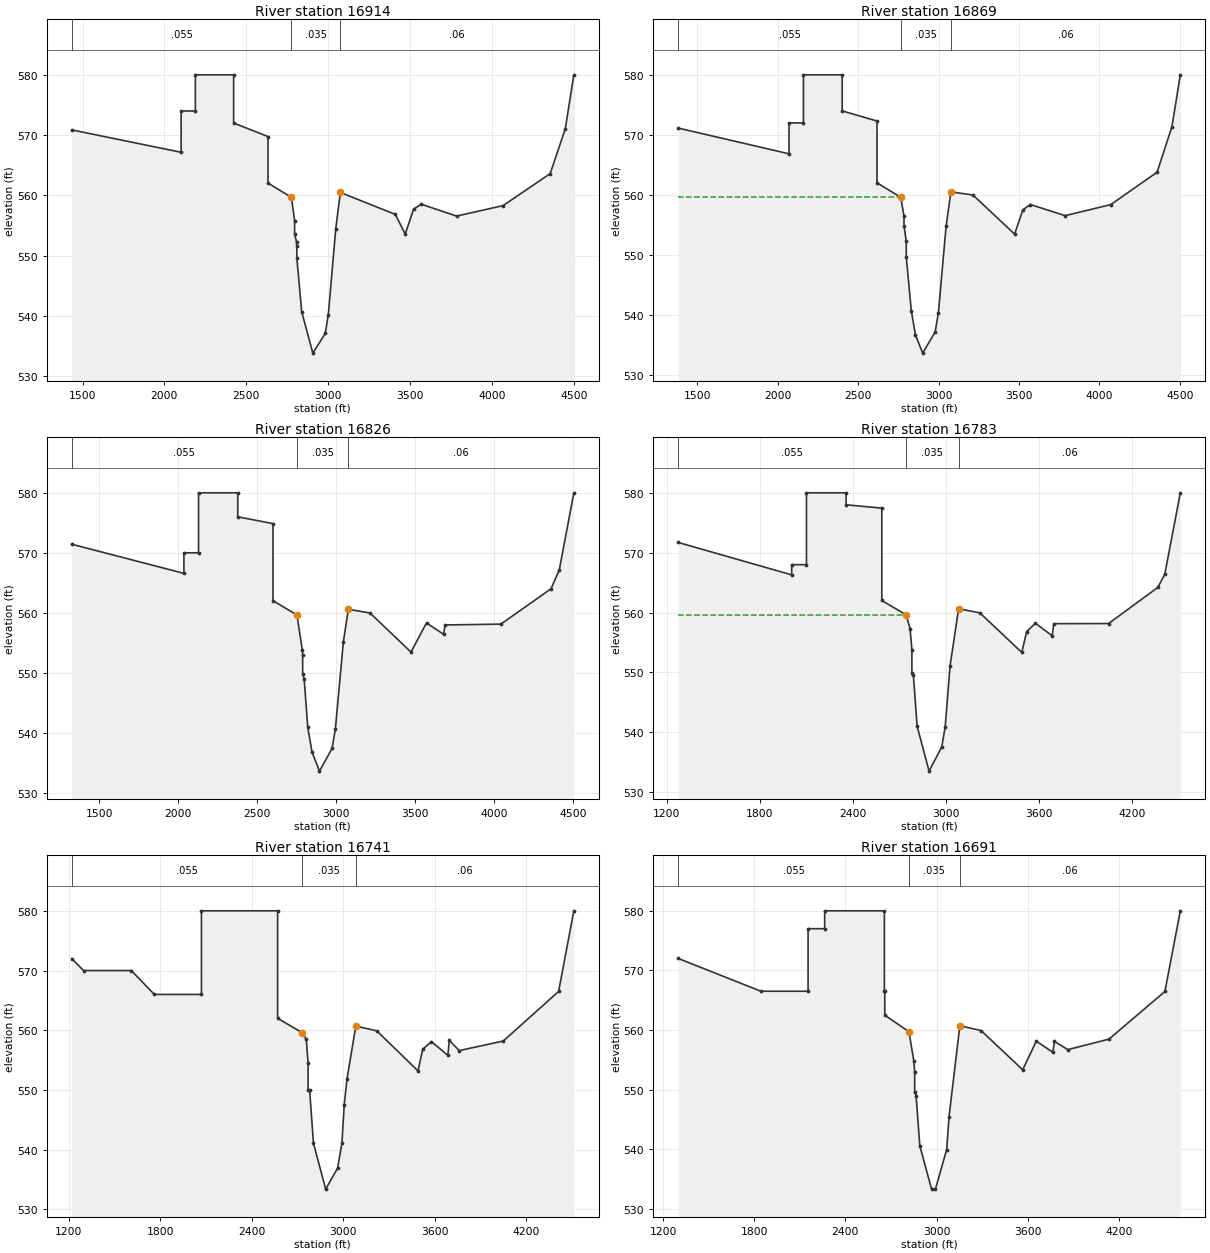
Type RM Length L Ch R = 1 ,16914   ,48.3,44.8,38.8
XS GIS Cut Line= 6
2317167.98699824 6949427.83180112317511.467374426948905.08143435
2317742.217058936948553.083957442317856.509139366948380.19546123
2317893.818532556948311.976115142318383.787427326946659.01504856
#Sta/Elev= 30
 1434.43  570.86 2102.24  567.14 2102.24     574 2189.26     574 2189.26     580
 2422.87     580 2422.87     572 2632.76  569.75 2632.76  562.03 2775.57  559.66
 2795.19  555.81 2795.19  553.64 2806.74  552.25 2808.67  551.58 2808.67  549.65
 2838.38  540.68 2906.47   533.8 2982.23  537.07 3001.04  540.18 3046.38  554.43
 3074.43  560.47 3410.34  556.83  3470.5  553.55 3521.64   557.7 3568.65  558.52
 3784.35  556.55 4068.12  558.29  4355.9   563.6 4448.14  571.05 4500.29     580
#Mann= 3 ,0,0
 1434.43    .055       0 2775.57    .035       0 3074.43     .06       0
#XS Ineff= 2 , 0
        2775.572559.65723074.428        556.6843
Permanent Ineff=
       F       F
Bank Sta=2775.57,3074.43
XS Rating Curve= 0 ,0
Exp/Cntr=0.3,0.1

Type RM Length L Ch R = 1 ,16869   ,47.3,43.7,38
XS GIS Cut Line= 6
2317171.037898086949472.696056172317530.867154776948946.77725956
2317772.715728236948592.703294152317892.298254266948418.69262279
2317933.085372656948350.759834672318388.889901926946654.40673247
#Sta/Elev= 30
 1380.57  571.14 2069.65  566.86 2069.65     572 2159.45     572 2159.45     580
  2400.5     580  2400.5     574 2617.07  572.31 2617.07  562.02 2764.43  559.64
 2784.93  556.49 2784.93  554.86    2799  552.31    2799  549.74 2830.03  540.79
 2855.94  536.73 2901.15   533.7 2978.85  537.23 2998.78  540.41 3046.84   554.8
 3076.57  560.53  3214.2     560    3473   553.5 3524.18  557.53 3571.23  558.42
 3787.13  556.57 4071.16  558.41 4359.19   563.8 4451.53  571.36 4503.71     580
#Mann= 3 ,0,0
 1380.57    .055       0 2764.43    .035       0 3076.57     .06       0
#XS Ineff= 2 , 0
        2764.428559.64283076.572        556.6757
Permanent Ineff=
       F       F
Bank Sta=2764.43,3076.57
XS Rating Curve= 0 ,0
Exp/Cntr=0.3,0.1

Type RM Length L Ch R = 1 ,16826   ,46.8,42.7,37.3
XS GIS Cut Line= 6
2317174.088797926949517.560311252317550.266935116948988.47308476
2317803.214397536948632.322630862317928.087369166948457.18978436
2317972.35221275 6948389.54355422318393.992376526946649.79841638
#Sta/Elev= 30
 1326.71  571.43 2037.06  566.57 2037.06     570 2129.63     570 2129.63     580
 2378.12     580 2378.12     576 2601.38  574.87 2601.38  562.02 2753.29  559.63
 2787.23  553.76 2789.34  553.04 2789.34  549.82 2798.58  549.01 2821.69  540.89
  2848.7  536.79 2895.84   533.6 2975.46  537.38 2996.52  540.64  3047.3  555.18
 3078.71  560.59 3216.47  559.96  3475.5  553.45 3573.82  558.31 3681.63  556.42
 3691.61  557.97 4044.97  558.11 4362.49     564 4414.73  567.12 4507.14     580
#Mann= 3 ,0,0
 1326.71    .055       0 2753.29    .035       0 3078.71     .06       0
#XS Ineff= 2 , 0
        2753.286559.62853078.714        556.6672
Permanent Ineff=
       F       F
Bank Sta=2753.29,3078.71
XS Rating Curve= 0 ,0
Exp/Cntr=0.3,0.1

Type RM Length L Ch R = 1 ,16783   ,45,41.8,36.8
XS GIS Cut Line= 6
2317177.139697776949562.424566332317569.666715466949030.16890997
2317833.713066846948671.941967572317963.876484066948495.68694593
2318011.619052846948428.327273742318399.094851126946645.19010029
#Sta/Elev= 30
 1272.86  571.71 2004.47  566.29 2004.47     568 2099.82     568 2099.82     580
 2355.74     580 2355.74     578 2585.69  577.44 2585.69  562.01 2742.14  559.61
 2768.12  557.29 2779.67  553.77 2779.67  549.91 2789.29  549.51 2813.34     541
 2890.53   533.5 2972.07  537.54 2994.26  540.87 3025.66  551.05 3080.86  560.64
 3218.73  559.93 3488.49  553.33 3519.46  556.81 3576.41  558.21 3684.31  556.11
 3694.31  558.14 4047.99  558.16 4365.79   564.2 4410.66  566.42 4510.57     580
#Mann= 3 ,0,0
 1272.86    .055       0 2742.14    .035       0 3080.86     .06       0
#XS Ineff= 2 , 0
        2742.143559.61433080.857        556.6586
Permanent Ineff=
       F       F
Bank Sta=2742.14,3080.86
XS Rating Curve= 0 ,0
Exp/Cntr=0.3,0.1

Type RM Length L Ch R = 1 ,16741   ,53.9,50.3,44
BEGIN DESCRIPTION:
This cross section corresponds to cross section 16746 of the non-georeferenced CDC model which was the source of this model.
Ineffective flow areas defined in LOB due to structures.
Channel data from 1975 USACE field survey.
END DESCRIPTION:
XS GIS Cut Line= 5
2317180.190599716949607.28885232      2317196.26   6949586.24593
   2318050.88592   6948467.11102   2318399.16901    6946666.5769
2318404.197329246946640.58178102
#Sta/Elev= 30
    1219     572    1296     570    1610     570    1761     566    2070     566
    2070     580    2570     580    2570     562    2731   559.6    2758   558.5
    2770   554.5    2770     550    2780     550    2805   541.1 2885.22   533.4
 2963.22   536.9    2992   541.1    3007   547.5    3025   551.8    3083   560.7
    3221   559.9    3491   553.2    3522   556.8    3579   558.1    3687   555.8
    3697   558.3    3762   556.6    4051   558.2    4414   566.5    4514     580
#Mann= 3 ,0,0
    1219    .055       0    2731    .035       0    3083     .06       0
#XS Ineff= 2 , 0
            2731   559.6    3083          556.65
Permanent Ineff=
       F       F
Bank Sta=2731,3083
XS Rating Curve= 0 ,0
Exp/Cntr=0.3,0.1

Type RM Length L Ch R = 1 ,16691   ,53.7,50.3,44.3
BEGIN DESCRIPTION:
This cross section corresponds to cross section 16696.2 of the non-georeferenced CDC model which was the source of this model.
END DESCRIPTION:
XS GIS Cut Line= 6
2317216.983382566949621.114022752317520.057997366949230.78166904
2317951.809141856948676.465912922318100.783570686948485.68941624
2318109.067830986948460.485132532318402.510697536946645.94175388
#Sta/Elev= 30
  1300.5     572 1844.65   566.5 2154.88   566.5 2154.88     577 2264.07     577
 2264.07     580 2656.86     580 2656.86   566.5 2659.39  566.49 2659.39  562.49
  2818.5   559.7 2850.96  554.72 2856.16  552.98 2856.16  549.61 2865.82  548.89
 2889.96  540.54 2967.43  533.28 2992.68  533.28 3066.83  539.93 3082.35  545.44
  3153.5  560.72 3293.38  559.89 3567.06  553.32 3656.26  558.12 3765.73  556.25
 3775.87  558.08 3863.85   556.7 4134.69  558.46 4502.64  566.46    4604     580
#Mann= 3 ,0,0
  1300.5    .055       0  2818.5    .035       0  3153.5     .06       0
#XS Ineff= 2 , 0
          2818.5   559.7  3153.5        556.6125
Permanent Ineff=
       F       F
Bank Sta=2818.5,3153.5
XS Rating Curve= 0 ,0
Exp/Cntr=0.3,0.1

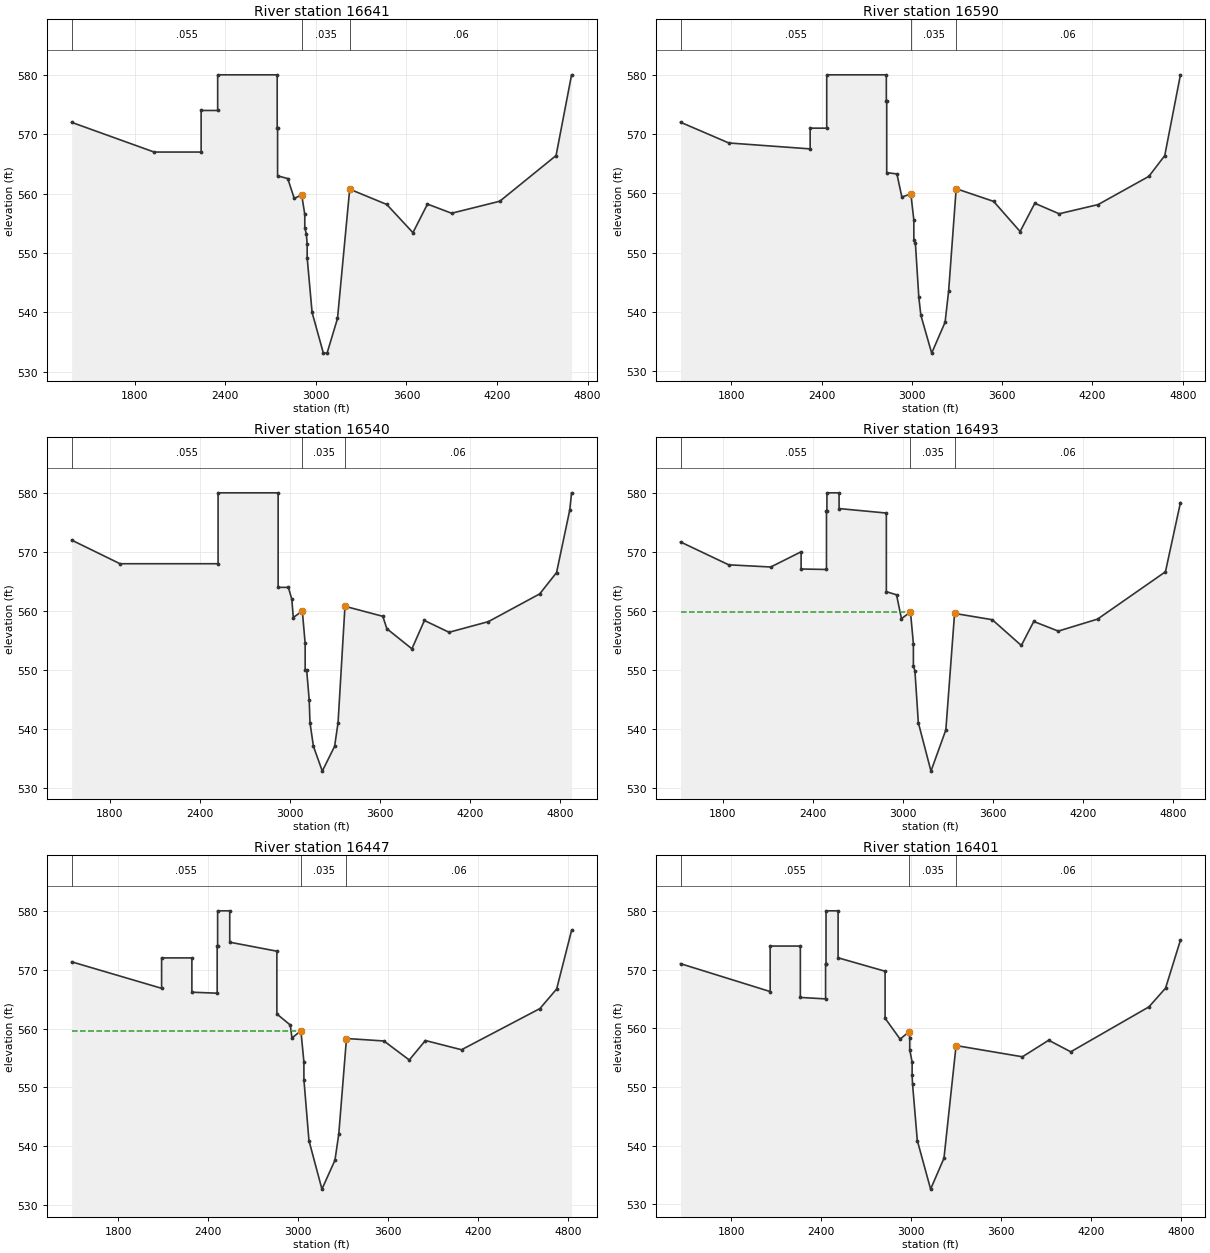
Type RM Length L Ch R = 1 ,16641   ,53,50.4,44.6
BEGIN DESCRIPTION:
This cross section corresponds to cross section 16646.5 of the non-georeferenced CDC model which was the source of this model.
END DESCRIPTION:
XS GIS Cut Line= 6
2317254.546627086949634.109011752317558.632694916949248.81807602
2317998.633481236948694.762905282318150.681221366948504.26781248
2318162.124173996948480.357115022318401.015710296946652.49365458
#Sta/Elev= 30
    1382     572  1928.3     567 2239.75     567 2239.75     574 2349.38     574
 2349.38     580 2743.72     580 2743.72     571 2746.26  570.99 2746.26  562.99
 2813.73  562.54 2856.61  559.19    2906   559.8 2926.51   556.5 2926.51  554.25
 2937.31  553.15 2942.32  551.46 2942.32  549.21 2974.92  539.99 3049.63  533.15
 3074.13  533.15 3143.23  538.98    3224  560.75 3469.49  558.18 3643.12  553.43
 3739.33  558.24 3899.09   556.7 4218.38  558.72 4591.27  566.41    4694     580
#Mann= 3 ,0,0
    1382    .055       0    2906    .035       0    3224     .06       0
#XS Ineff= 2 , 0
            2906   559.8    3224         556.575
Permanent Ineff=
       F       F
Bank Sta=2906,3224
XS Rating Curve= 0 ,0
Exp/Cntr=0.3,0.1

Type RM Length L Ch R = 1 ,16590   ,53.4,50.2,44.8
BEGIN DESCRIPTION:
This cross section corresponds to cross section 16596.7 of the non-georeferenced CDC model which was the source of this model.
END DESCRIPTION:
XS GIS Cut Line= 6
2317292.888139986949646.303405072317597.207392456949266.85448301
2318045.457820626948713.059897642318200.578872056948522.84620872
2318215.180516996948500.229097512318399.811838716946660.21549545
#Sta/Elev= 30
  1463.5     572 1784.24   568.5 2324.63   567.5 2324.63     571 2434.69     571
 2434.69     580 2830.58     580 2830.58   575.5 2833.13   575.5 2833.13   563.5
 2900.86  563.27 2933.73  559.38  2993.5   559.9 3013.26   555.5 3013.26  552.12
 3023.65  551.57 3046.53  542.42 3059.88  539.43 3131.83  533.03 3220.91  538.25
 3244.56  543.55  3294.5  560.78 3543.24  558.64 3719.18  553.55 3816.66  558.32
 3978.54  556.55 4237.16   558.1 4574.74  562.87 4679.91  566.37    4784     580
#Mann= 3 ,0,0
  1463.5    .055       0  2993.5    .035       0  3294.5     .06       0
#XS Ineff= 2 , 0
          2993.5   559.9  3294.5        556.5375
Permanent Ineff=
       F       F
Bank Sta=2993.5,3294.5
XS Rating Curve= 0 ,0
Exp/Cntr=0.3,0.1

Type RM Length L Ch R = 1 ,16540   ,48.6,46.8,46.1
BEGIN DESCRIPTION:
This cross section corresponds to cross section 16547 of the non-georeferenced CDC model which was the source of this model.
Ineffective flow areas defined in LOB due to structures.
Channel data from 1975 USACE field survey.
END DESCRIPTION:
XS GIS Cut Line= 5
   2317330.55894   6949659.51284   2317635.78209   6949284.89089
   2318092.28216   6948731.35689   2318268.23686   6948520.10108
   2318399.15458   6946666.78064
#Sta/Elev= 30
    1545     572    1867     568    2520     568    2520     580    2920     580
    2920     564    2988     564    3011     562    3021   558.9    3081     560
    3100   554.5    3100     550    3110     550    3127   544.9    3132   541.1
 3155.04   537.1 3214.04   532.9 3296.04   537.1    3319   541.1    3365   560.8
    3617   559.1    3644     557    3811   553.6    3894   558.4    4058   556.4
    4320   558.2    4662   562.9    4774   566.5    4862   577.1    4874     580
#Mann= 3 ,0,0
    1545    .055       0    3081    .035       0    3365     .06       0
#XS Ineff= 2 , 0
            3081     560    3365           556.5
Permanent Ineff=
       F       F
Bank Sta=3081,3365
XS Rating Curve= 0 ,0
Exp/Cntr=0.3,0.1

Type RM Length L Ch R = 1 ,16493   ,48.5,46.5,46
BEGIN DESCRIPTION:
This cross section corresponds to cross section 16500.5 of the non-georeferenced CDC model which was the source of this model.
END DESCRIPTION:
XS GIS Cut Line= 6
2317363.723243856949670.64276253  2318011.1160416948902.81187127
2318135.37229325 6948756.86120822318309.671520446948553.78924933
2318314.667289776948546.153947072318423.094274266946690.73186918
#Sta/Elev= 30
 1516.83  571.67 1838.06  567.79 2118.03  567.42 2320.45     570 2320.45  567.08
 2489.51     567 2489.51     577 2492.51     577 2492.51     580 2573.48     580
 2573.48  577.33 2888.55  576.57 2888.55  563.24 2956.39   562.7 2989.31  558.65
 3049.17   559.8 3068.69  554.42 3068.69  550.67 3078.96  549.79 3101.56  541.03
 3185.84   532.8 3284.99  539.79 3343.17  559.55  3594.5  558.48 3787.98  554.11
 3870.76  558.18 4034.33  556.55 4295.64  558.58 4748.43  566.61 4848.17  578.33
#Mann= 3 ,0,0
 1516.83    .055       0 3049.17    .035       0 3343.17     .06       0
#XS Ineff= 2 , 0
        3049.167   559.83343.167        555.9667
Permanent Ineff=
       F       F
Bank Sta=3049.17,3343.17
XS Rating Curve= 0 ,0
Exp/Cntr=0.3,0.1

Type RM Length L Ch R = 1 ,16447   ,48.7,46.3,45.8
BEGIN DESCRIPTION:
This cross section corresponds to cross section 16454 of the non-georeferenced CDC model which was the source of this model.
END DESCRIPTION:
XS GIS Cut Line= 6
2317395.972126146949683.532546172317712.235618936949321.06303387
 2318050.97986086948927.510717022318357.100224356948580.28081346
2318361.097719556948572.206814132318447.457950596946712.77085645
#Sta/Elev= 30
 1488.67  571.33 2088.42  566.83 2088.42     572 2290.36     572 2290.36  566.17
 2459.01     566 2459.01     574 2462.01     574 2462.01     580 2542.78     580
 2542.78  574.67  2857.1  573.14  2857.1  562.47 2946.66  560.59 2957.62   558.4
 3017.33   559.6 3037.37  554.33 3037.37  551.33 3071.12  540.95 3157.65   532.7
 3244.44  537.61 3270.04  542.09 3321.33   558.3 3570.99  557.88  3740.1  554.65
 3847.53  557.96 4088.51  556.39 4611.46  563.39 4722.86  566.72 4822.33  576.67
#Mann= 3 ,0,0
 1488.67    .055       0 3017.33    .035       0 3321.33     .06       0
#XS Ineff= 2 , 0
        3017.333   559.63321.333        555.4333
Permanent Ineff=
       F       F
Bank Sta=3017.33,3321.33
XS Rating Curve= 0 ,0
Exp/Cntr=0.3,0.1

Type RM Length L Ch R = 1 ,16401   ,48.7,46.1,45.8
BEGIN DESCRIPTION:
This cross section corresponds to cross section 16407.5 of the non-georeferenced CDC model which was the source of this model.
END DESCRIPTION:
XS GIS Cut Line= 6
2317428.737706576949696.43568384 2317745.3072517 6949345.4000154
 2318090.84368066948952.209562762318404.52892827 6948606.7723776
2318407.52814932 6948598.25968122318472.091214636946735.15577868
#Sta/Elev= 30
  1460.5     571 2058.82  566.25 2058.82     574 2260.27     574 2260.27  565.25
 2428.52     565 2428.52     571  2431.5     571  2431.5     580 2512.09     580
 2512.09     572 2825.65  569.71 2825.65  561.71 2925.93  558.15  2985.5   559.4
 2990.15  558.41 2990.15  556.31 3006.06  554.25 3006.06     552 3008.74  550.55
 3040.68  540.88 3129.45   532.6 3218.64  537.87  3299.5  557.05 3741.95  555.14
 3917.55  557.96 4064.63  555.99 4586.19  563.64 4697.29  566.83  4796.5     575
#Mann= 3 ,0,0
  1460.5    .055       0  2985.5    .035       0  3299.5     .06       0
#XS Ineff= 2 , 0
          2985.5   559.4  3299.5           554.9
Permanent Ineff=
       F       F
Bank Sta=2985.5,3299.5
XS Rating Curve= 0 ,0
Exp/Cntr=0.3,0.1