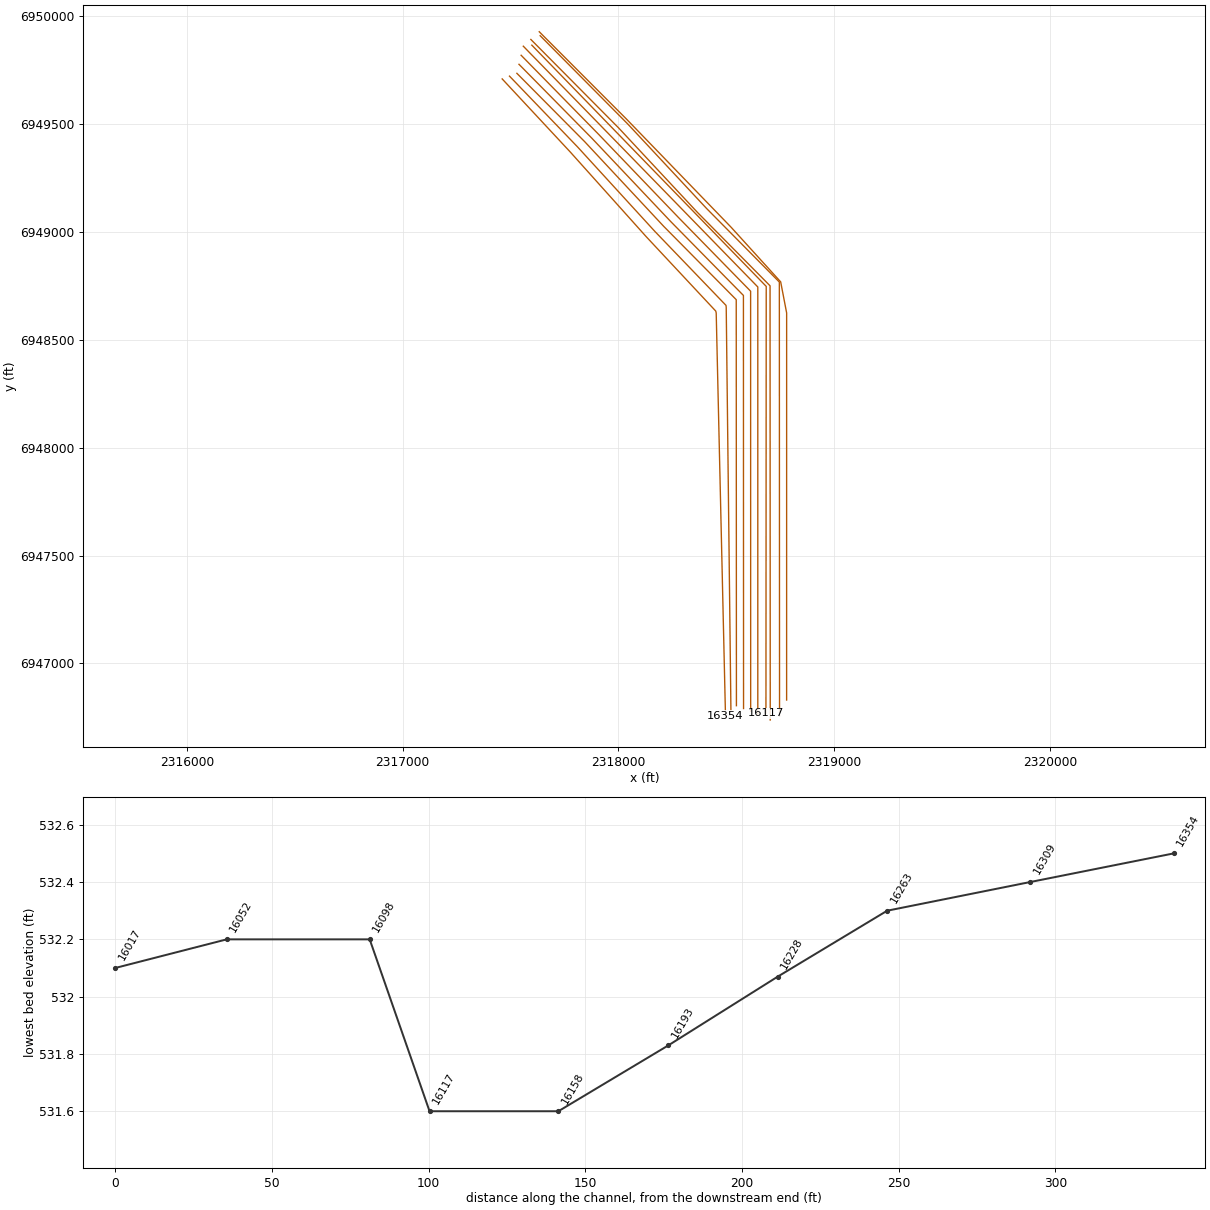
HEC-RAS study CDC_Consolidated_Model.prj: Upper Trinity CDC Consolidated Model

--- CDC_Consolidated_Model.g11 (geometry) --- (continued)

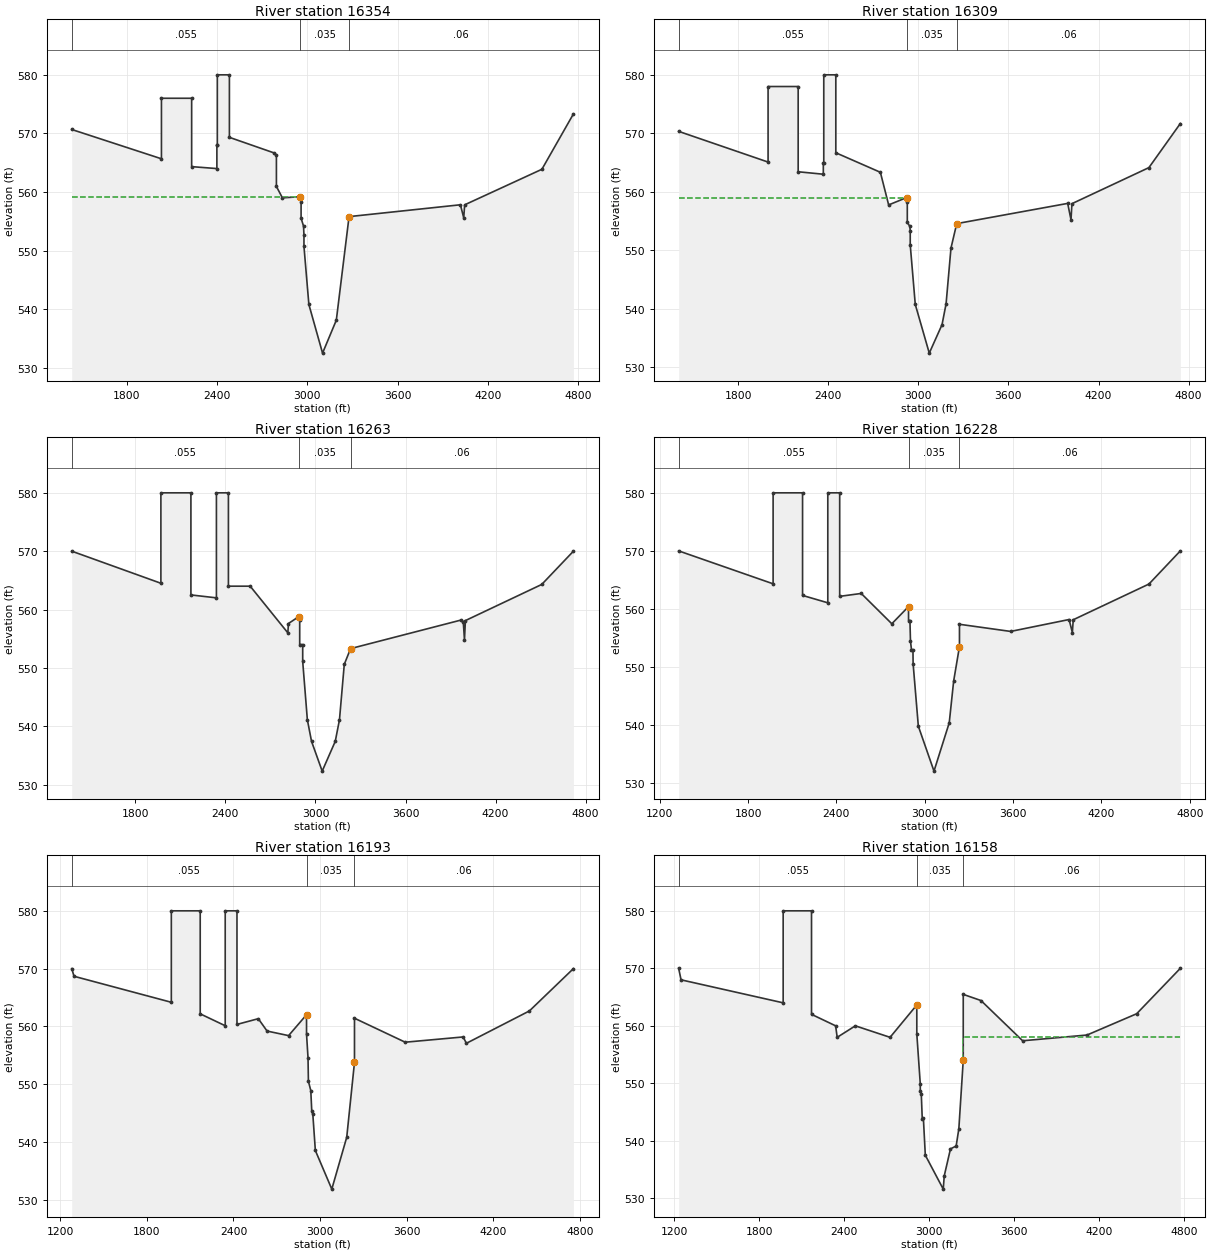
Type RM Length L Ch R = 1 ,16354   ,48.3,45.8,45.7
BEGIN DESCRIPTION:
This cross section corresponds to cross section 16361 of the non-georeferenced CDC model which was the source of this model.
END DESCRIPTION:
XS GIS Cut Line= 6
2317462.020460676949709.361755352317778.378884466949369.73699694
 2318130.70750046948976.908408512318451.957632186948633.26394173
2318453.958579096948624.312548262318496.999062386946757.88466095
#Sta/Elev= 30
 1432.33  570.67 2029.21  565.67 2029.21     576 2230.18     576 2230.18  564.33
 2398.02     564 2398.02     568    2401     568    2401     580 2481.39     580
 2481.39  569.33 2778.82  566.67  2794.2  566.28  2794.2  560.95 2834.09     559
 2953.67   559.2 2958.43  558.34 2958.43  555.54 2974.74  554.17 2977.49  552.67
 2977.49  550.73 3010.24   540.8 3101.25   532.5 3192.83  538.12 3277.67   555.8
 4018.64  557.82 4040.76  555.59 4046.79  557.81 4560.91  563.88 4770.67  573.33
#Mann= 3 ,0,0
 1432.33    .055       0 2953.67    .035       0 3277.67     .06       0
#XS Ineff= 2 , 0
        2953.667   559.23277.667        554.3666
Permanent Ineff=
       F       F
Bank Sta=2953.67,3277.67
XS Rating Curve= 0 ,0
Exp/Cntr=0.3,0.1

Type RM Length L Ch R = 1 ,16309   ,48,45.6,45.3
BEGIN DESCRIPTION:
This cross section corresponds to cross section 16314.5 of the non-georeferenced CDC model which was the source of this model.
END DESCRIPTION:
XS GIS Cut Line= 6
 2317495.81863226949722.321723472317811.450517236949394.07397847
 2318170.57132026949001.607254252318499.386336096948659.75550587
2318500.389008866948650.365415332318522.186265416946780.95293965
#Sta/Elev= 30
 1404.17  570.33 1999.61  565.08 1999.61     578 2200.09     578 2200.09  563.42
 2367.53     563 2367.53     565  2370.5     565  2370.5     580  2450.7     580
  2450.7  566.67 2747.41  563.33 2802.55  557.75 2921.83     559 2926.72  558.27
 2926.72  554.77 2943.43  554.08 2946.25  553.33 2946.25  550.92  2979.8  540.73
 3073.06   532.4 3158.06  537.27    3185  540.84 3217.54  550.36 3255.83  554.55
 3994.82  558.01 4016.88   555.2 4022.89  557.96 4535.64  564.13 4744.83  571.67
#Mann= 3 ,0,0
 1404.17    .055       0 2921.83    .035       0 3255.83     .06       0
#XS Ineff= 2 , 0
        2921.833     5593255.833        553.8333
Permanent Ineff=
       F       F
Bank Sta=2921.83,3255.83
XS Rating Curve= 0 ,0
Exp/Cntr=0.3,0.1

Type RM Length L Ch R = 1 ,16263   ,34.7,34.9,36.4
BEGIN DESCRIPTION:
This cross section corresponds to cross section 16268 of the non-georeferenced CDC model which was the source of this model.
108 feet upstream of University Drive.
Ineffective flow areas defined in LOB due to structures.
Channel data from 1975 USACE field survey.
END DESCRIPTION:
XS GIS Cut Line= 5
2317530.107920766949735.34816572   2317844.52215   6949418.41096
   2318210.43514    6949026.3061   2318546.81504   6948686.24707
2318547.65724894 6946804.3247693
#Sta/Elev= 30
    1376     570    1970   564.5    1970     580    2170     580    2170   562.5
    2340     562    2340     580    2420     580    2420     564    2565     564
    2816     556    2820   557.6    2890   558.8    2895   558.2    2895     554
    2915     554    2915   551.1    2946   541.1 2973.86   537.4 3044.86   532.3
 3131.86   537.4    3160   541.1    3192   550.6    3234   553.3    3971   558.2
    3985   557.9    3993   554.8    3999   558.1    4508   564.3    4719     570
#Mann= 3 ,0,0
    1376    .055       0    2890    .035       0    3234     .06       0
#XS Ineff= 2 , 0
            2890   558.8    3234           553.3
Permanent Ineff=
       F       F
Bank Sta=2890,3234
XS Rating Curve= 0 ,0
Exp/Cntr=0.3,0.1

Type RM Length L Ch R = 1 ,16228   ,34.7,34.9,38.7
BEGIN DESCRIPTION:
This cross section corresponds to cross section 16232.3 of the non-georeferenced CDC model which was the source of this model.
END DESCRIPTION:
XS GIS Cut Line= 6
2317539.874232156949777.11795383 2317875.8790967 6949436.3403548
 2318244.6818324  6949046.746615 2318579.7971141 6948706.2169211
 2318580.1286945 6948705.6457327 2318580.69970856946791.11289564
#Sta/Elev= 30
 1328.33     570    1970  564.33    1970     580    2170     580    2170  562.33
 2341.53  561.06 2341.53     580 2422.25     580 2422.25  562.17 2568.55  562.67
  2776.4  557.45    2890  560.41    2890     558  2899.5     558 2903.18  554.42
    2910     553    2920     553 2921.05  550.58 2956.53  539.81 3062.91  532.07
 3166.46  540.39 3196.53  547.59    3236  553.53    3236  557.36 3583.55  556.13
 3980.61  558.18 4002.84  555.94  4008.9  558.14 4523.15  564.29 4736.33     570
#Mann= 3 ,0,0
 1328.33    .055       0    2890    .035       0    3236     .06       0
#XS Ineff= 2 , 0
            2890   559.2    3236        552.2267
Permanent Ineff=
       F       F
Bank Sta=2890,3236
XS Rating Curve= 0 ,0
Exp/Cntr=0.3,0.1

Type RM Length L Ch R = 1 ,16193   ,35.1,35.1,34.6
BEGIN DESCRIPTION:
This cross section corresponds to cross section 16196.6 of the non-georeferenced CDC model which was the source of this model.
END DESCRIPTION:
XS GIS Cut Line= 6
 2317549.80821686949818.99579946 2317907.2360435 6949454.2697496
 2318278.9285247 6949067.1871299 2318613.2765588 6948725.6839616
  2318613.442349 6948725.04439542318613.732617436946777.94222292
#Sta/Elev= 30
 1280.67     570 1296.57  568.67    1970  564.17    1970     580    2170     580
    2170  562.17 2343.06  560.11 2343.06     580  2424.5     580  2424.5  560.34
  2572.1  561.33 2632.91  559.19 2781.81   558.4    2906  562.02    2906  558.67
 2916.37  554.55 2918.98   550.5 2935.55  548.88 2942.12  545.37 2949.62  544.77
 2967.06  538.52 3080.95  531.83 3184.32  540.81    3238  553.77    3238  561.41
  3589.1  557.26 3990.22  558.17 4012.67  557.07 4448.75  562.67 4753.67     570
#Mann= 3 ,0,0
 1280.67    .055       0    2906    .035       0    3238     .06       0
#XS Ineff= 2 , 0
            2906   559.6    3238        551.1533
Permanent Ineff=
       F       F
Bank Sta=2906,3238
XS Rating Curve= 0 ,0
Exp/Cntr=0.5,0.3

Type RM Length L Ch R = 1 ,16158   ,41,41.1,39.9
BEGIN DESCRIPTION:
This cross section corresponds to cross section 16161 of the non-georeferenced CDC model which was the source of this model.
END DESCRIPTION:
XS GIS Cut Line= 5
2317559.910063136949860.98069581     2317572.538     6949848.016
     2318646.756     6948745.151     2318646.756     6946782.911
     2318646.7566946764.81270928
#Sta/Elev= 30
    1233     570    1250     568    1970     564    1970     580    2170     580
    2170     562    2340     560    2351     558    2479     560    2724     558
  2912.5  563.63  2912.5   558.6    2937   549.9  2937.1   548.7    2944   548.2
    2951   543.8    2959   543.9  2972.5   537.5    3099   531.6    3106   533.9
    3150   538.6    3190   539.1    3209   542.1    3240     554    3240  565.47
    3365   564.4    3659   557.4    4113   558.4    4463   562.1    4771     570
#Mann= 3 ,0,0
    1233    .055       0  2912.5    .035       0    3240     .06       0
#XS Ineff= 2 , 0
          2912.5     560    3240          557.98
Permanent Ineff=
       F       F
Bank Sta=2912.5,3240
XS Rating Curve= 0 ,0
Exp/Cntr=0.5,0.3

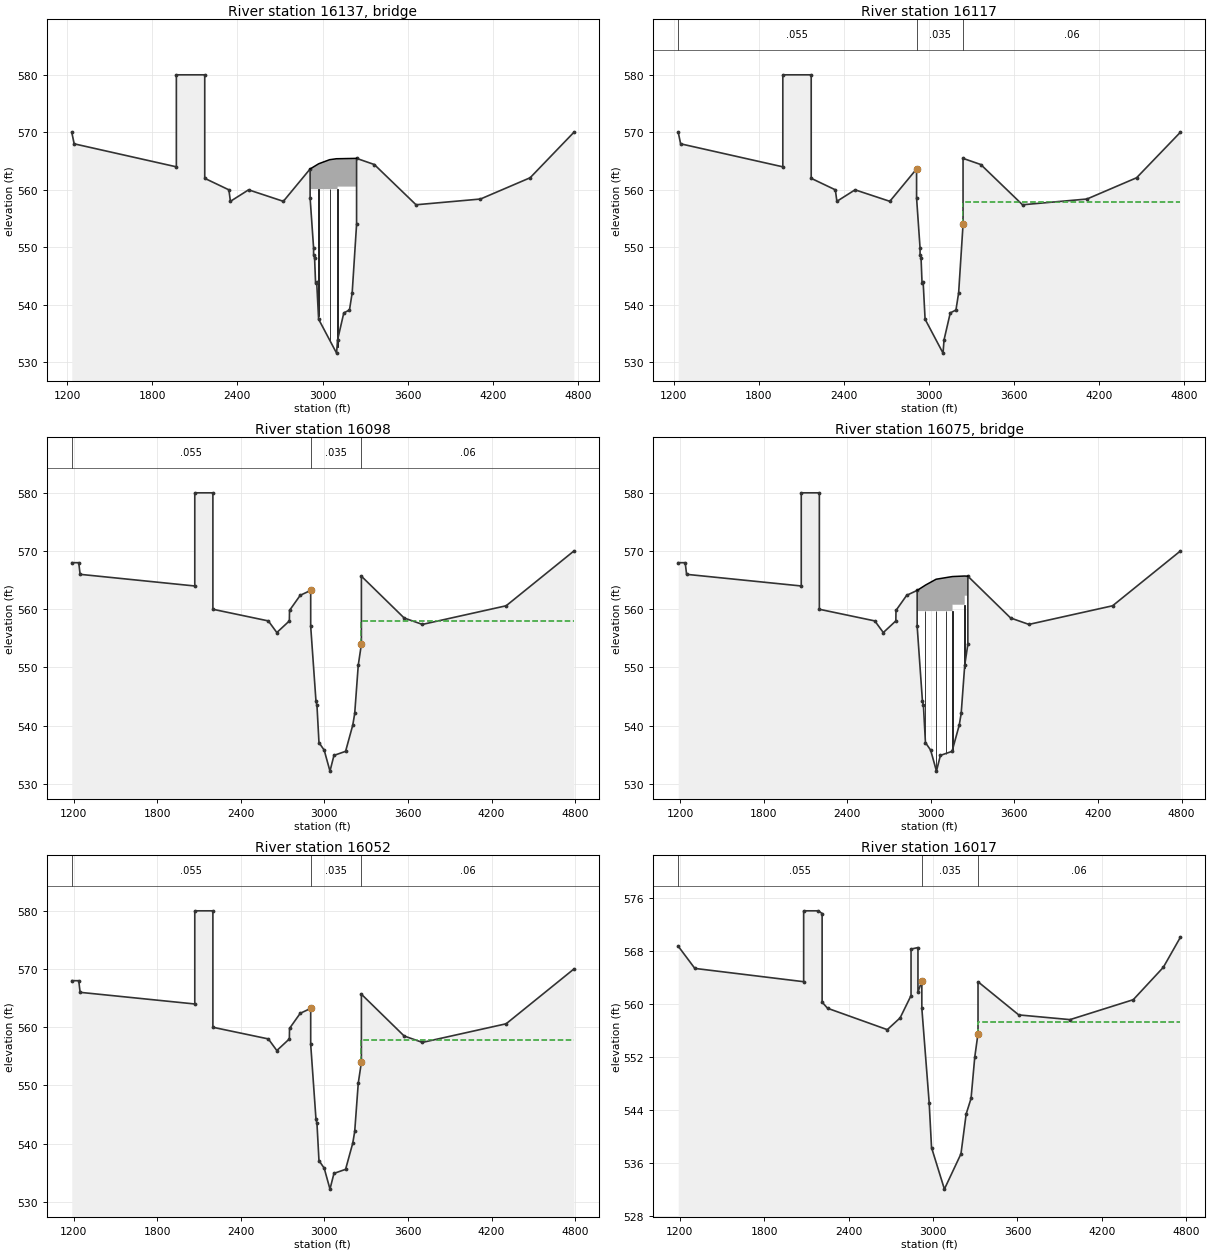
Type RM Length L Ch R = 3 ,16137   ,,,
BEGIN DESCRIPTION:
University Drive - south bound
Downstream face of bridge.  Bridge data from July 1975 survey.  Upstream bridge: minimum low chord elev. 560.12.  Bridge width 40 feet.  Ineffective flow areas defined in LOB due to structures.
Channel data from 1975 USACE field survey.
END DESCRIPTION:
Node Name=University Drive
Bridge Culvert--1,0,-1,-1, 0
Deck Dist Width WeirC Skew NumUp NumDn MinLoCord MaxHiCord MaxSubmerge Is_Ogee
2,38,2.6,0, 9, 9, , , 0.95, 0, 0,0,,
  2912.5    2970  2972.5    3051  3053.5    3099    3106    3106    3240
  563.63  564.49  564.53  565.25  565.25  565.41  565.41  565.41  565.47
  560.12  560.12  560.12  560.12  560.12  560.12  560.12  560.56  560.56
  2912.5    2970  2972.5    3051  3053.5    3099    3106    3106    3240
  563.63  564.49  564.53  565.25  565.25  565.41  565.41  565.41  565.47
  560.12  560.12  560.12  560.12  560.12  560.12  560.12  560.56  560.56
Pier Skew, UpSta & Num, DnSta & Num=  ,2971.25, 2 ,2971.25, 2 , 0 , 0 , 0 ,,
     2.5     2.5
       0     561
     2.5     2.5
       0     561
Pier Skew, UpSta & Num, DnSta & Num=  ,3052.25, 2 ,3052.25, 2 , 0 , 0 , 0 ,,
     2.5     2.5
       0     561
     2.5     2.5
       0     561
Pier Skew, UpSta & Num, DnSta & Num=  ,3102.5, 2 ,3102.5, 2 , 0 , 0 , 0 ,,
       7       7
       0     561
       7       7
       0     561
BR Coef=-1 , 0 , 0 ,1.05, 0 ,,,0.8,-1,0.5,1,
WSPro=,,,, 1 ,,,, 0 ,,,, 0 ,,,,-1 ,-1 ,-1 , 0 , 0 , 0 , 0 , 0
BC Design=,, 0 ,, 0 ,,,,,,
BC HTab HWMax=580
BC Use User HTab Curves=0
BC User HTab FreeFlow(D)= 0

Type RM Length L Ch R = 1 ,16117   ,18.8,19.1,18.8
BEGIN DESCRIPTION:
This cross section corresponds to cross section 16120 of the non-georeferenced CDC model which was the source of this model.
Downstream of University Drive South.
END DESCRIPTION:
XS GIS Cut Line= 5
2317599.391096016949865.82642534     2317612.902     6949851.922
     2318685.819     6948747.755     2318684.517      6946788.12
2318684.504118726946768.73244201
#Sta/Elev= 30
    1233     570    1250     568    1970     564    1970     580    2170     580
    2170     562    2340     560    2351     558    2479     560    2724     558
  2912.5  563.63  2912.5   558.6    2937   549.9  2937.1   548.7    2944   548.2
    2951   543.8    2959   543.9  2972.5   537.5    3099   531.6    3106   533.9
    3150   538.6    3190   539.1    3209   542.1    3240     554    3240  565.47
    3365   564.4    3659   557.4    4113   558.4    4463   562.1    4771     570
#Mann= 3 ,0,0
    1233    .055       0  2912.5    .035       0    3240     .06       0
#XS Ineff= 2 , 0
          2912.5     560    3240          557.87
Permanent Ineff=
       F       F
Bank Sta=2912.5,3240
XS Rating Curve= 0 ,0
Exp/Cntr=0.5,0.3

Type RM Length L Ch R = 1 ,16098   ,45.4,45.6,44.4
BEGIN DESCRIPTION:
This cross section corresponds to cross section 16100 of the non-georeferenced CDC model which was the source of this model.
END DESCRIPTION:
XS GIS Cut Line= 6
2317594.906185376949892.29728648 2318001.2283611 6949482.7146309
 2318367.1413511 6949090.6097709 2318703.5212511 6948750.5507409
 2318704.3982211 6946790.95459092318704.421862166946738.12845331
#Sta/Elev= 30
    1187     568    1237     568    1247     566    2070     564    2070     580
    2200     580    2200     560    2598     558    2659     556    2749     558
    2750   559.8    2827   562.4    2902  563.24    2902   557.1    2940   544.2
    2947   543.5  2961.5   537.1    2999   535.8  3040.5   532.2    3069   534.9
  3152.5   535.6    3204   540.1    3218   542.1  3243.5   550.4    3266     554
    3266  565.68    3573   558.5    3704   557.4    4305   560.6    4791     570
#Mann= 3 ,0,0
    1187    .055       0    2902    .035       0    3266     .06       0
#XS Ineff= 2 , 0
            2902     560    3266          557.93
Permanent Ineff=
       F       F
Bank Sta=2902,3266
XS Rating Curve= 0 ,0
Exp/Cntr=0.5,0.3

Type RM Length L Ch R = 3 ,16075   ,,,
BEGIN DESCRIPTION:
University Drive - north bound
Downstream face of bridge.  Bridge data from July 1975 survey, bridge plans.
Double bridges - both bridges represented.  Downstream bridge: minimum low chord elev. 559.69.  Bridge width 45 feet.  Ineffective flow areas defined in LOB due to structures.
Channel data from 1975 USACE field survey.
END DESCRIPTION:
Node Name=University Drive
Bridge Culvert--1,0,-1,-1, 0
Deck Dist Width WeirC Skew NumUp NumDn MinLoCord MaxHiCord MaxSubmerge Is_Ogee
3,40,2.6,0, 15, 15, , , 0.95, 0, 0,0,,
    2902    2950    2959  2961.5    3038  3040.5  3106.5    3109  3152.5    3156
    3156    3240  3243.5  3243.5    3266
  563.24  563.97  564.11  564.15  565.16  565.17  565.43  565.44  565.61  565.62
  565.62  565.71  565.71  565.71  565.68
  559.69  559.69  559.69  559.69  559.69  559.69  559.69  559.69  559.69  559.69
  560.78  560.78  560.78  562.33  562.33
    2902    2950    2959  2961.5    3038  3040.5  3106.5    3109  3152.5    3156
    3156    3240  3243.5  3243.5    3266
  563.24  563.97  564.11  564.15  565.16  565.17  565.43  565.44  565.61  565.62
  565.62  565.71  565.71  565.71  565.68
  559.69  559.69  559.69  559.69  559.69  559.69  559.69  559.69  559.69  559.69
  560.78  560.78  560.78  562.33  562.33
Pier Skew, UpSta & Num, DnSta & Num=  ,2960.25, 2 ,2960.25, 2 , 0 , 0 , 0 ,,
     2.5     2.5
       0     560
     2.5     2.5
       0     560
Pier Skew, UpSta & Num, DnSta & Num=  ,3039.25, 2 ,3039.25, 2 , 0 , 0 , 0 ,,
     2.5     2.5
       0     560
     2.5     2.5
       0     560
Pier Skew, UpSta & Num, DnSta & Num=  ,3107.75, 2 ,3107.75, 2 , 0 , 0 , 0 ,,
     2.5     2.5
       0     560
     2.5     2.5
       0     560
Pier Skew, UpSta & Num, DnSta & Num=  ,3154.25, 2 ,3154.25, 2 , 0 , 0 , 0 ,,
     3.5     3.5
       0     561
     3.5     3.5
       0     561
Pier Skew, UpSta & Num, DnSta & Num=  ,3241.75, 2 ,3241.75, 2 , 0 , 0 , 0 ,,
     3.5     3.5
       0     563
     3.5     3.5
       0     563
BR Coef=-1 , 0 , 0 ,1.05, 0 ,,,0.8,-1,0.5,1,
WSPro=,,,, 1 ,,,, 0 ,,,, 0 ,,,,-1 ,-1 ,-1 , 0 , 0 , 0 , 0 , 0
BC Design=,, 0 ,, 0 ,,,,,,
BC HTab HWMax=580
BC Use User HTab Curves=0
BC User HTab FreeFlow(D)= 0

Type RM Length L Ch R = 1 ,16052   ,38.3,35.6,34.6
BEGIN DESCRIPTION:
This cross section corresponds to cross section 16054 of the non-georeferenced CDC model which was the source of this model.
One-foot downstream of University Drive North.  Duplication of following bridge cross-section without bridge piers.
Ineffective flow areas defined in LOB due to structures.
Channel data from 1975 USACE field survey.
END DESCRIPTION:
XS GIS Cut Line= 6
2317638.01927849 6949909.6738694  2317675.223434  6949872.171174
 2318044.3414547  6949500.091214 2318410.2544447  6949107.986354
 2318746.6343447  6948767.9273242318747.534955766946755.50503662
#Sta/Elev= 30
    1187     568    1237     568    1247     566    2070     564    2070     580
    2200     580    2200     560    2598     558    2659     556    2749     558
    2750   559.8    2827   562.4    2902  563.24    2902   557.1    2940   544.2
    2947   543.5  2961.5   537.1    2999   535.8  3040.5   532.2    3069   534.9
  3152.5   535.6    3204   540.1    3218   542.1  3243.5   550.4    3266     554
    3266  565.68    3573   558.5    3704   557.4    4305   560.6    4791     570
#Mann= 3 ,0,0
    1187    .055       0    2902    .035       0    3266     .06       0
#XS Ineff= 2 , 0
            2902     560    3266          557.84
Permanent Ineff=
       F       F
Bank Sta=2902,3266
XS Rating Curve= 0 ,0
Exp/Cntr=0.5,0.3

Type RM Length L Ch R = 1 ,16017   ,41.5,37,34.5
XS GIS Cut Line= 6
 2317633.7660927 6949928.0677724 2318037.1491205  6949524.227695
 2318523.7696377 6949021.1848148     2318752.796     6948768.765
 2318780.4328865 6948624.6725961 2318780.3468006 6946830.5589481
#Sta/Elev= 30
 1190.67  568.67 1308.62  565.33 2081.39  563.33 2081.39     574  2186.4     574
 2212.53  573.59 2212.53  560.25 2251.27  559.33 2675.54  556.11 2766.33  557.88
    2844  561.24    2844  568.24 2893.14  568.47 2893.14  561.77 2920.67  563.43
 2920.67  559.33 2972.73  545.13 2989.51  538.36 3080.92   532.1 3198.54  537.41
 3235.44  543.41 3270.27  545.76 3296.51  551.97 3319.67  555.53 3319.67  563.32
 3608.88  558.33 3973.01  557.62 4422.25  560.62 4635.47  565.49 4756.33     570
#Mann= 3 ,0,0
 1190.67    .055       0 2920.67    .035       0 3319.67     .06       0
#XS Ineff= 2 , 0
        2920.667     5603319.667        557.3267
Permanent Ineff=
       F       F
Bank Sta=2920.67,3319.67
XS Rating Curve= 0 ,0
Exp/Cntr=0.5,0.3