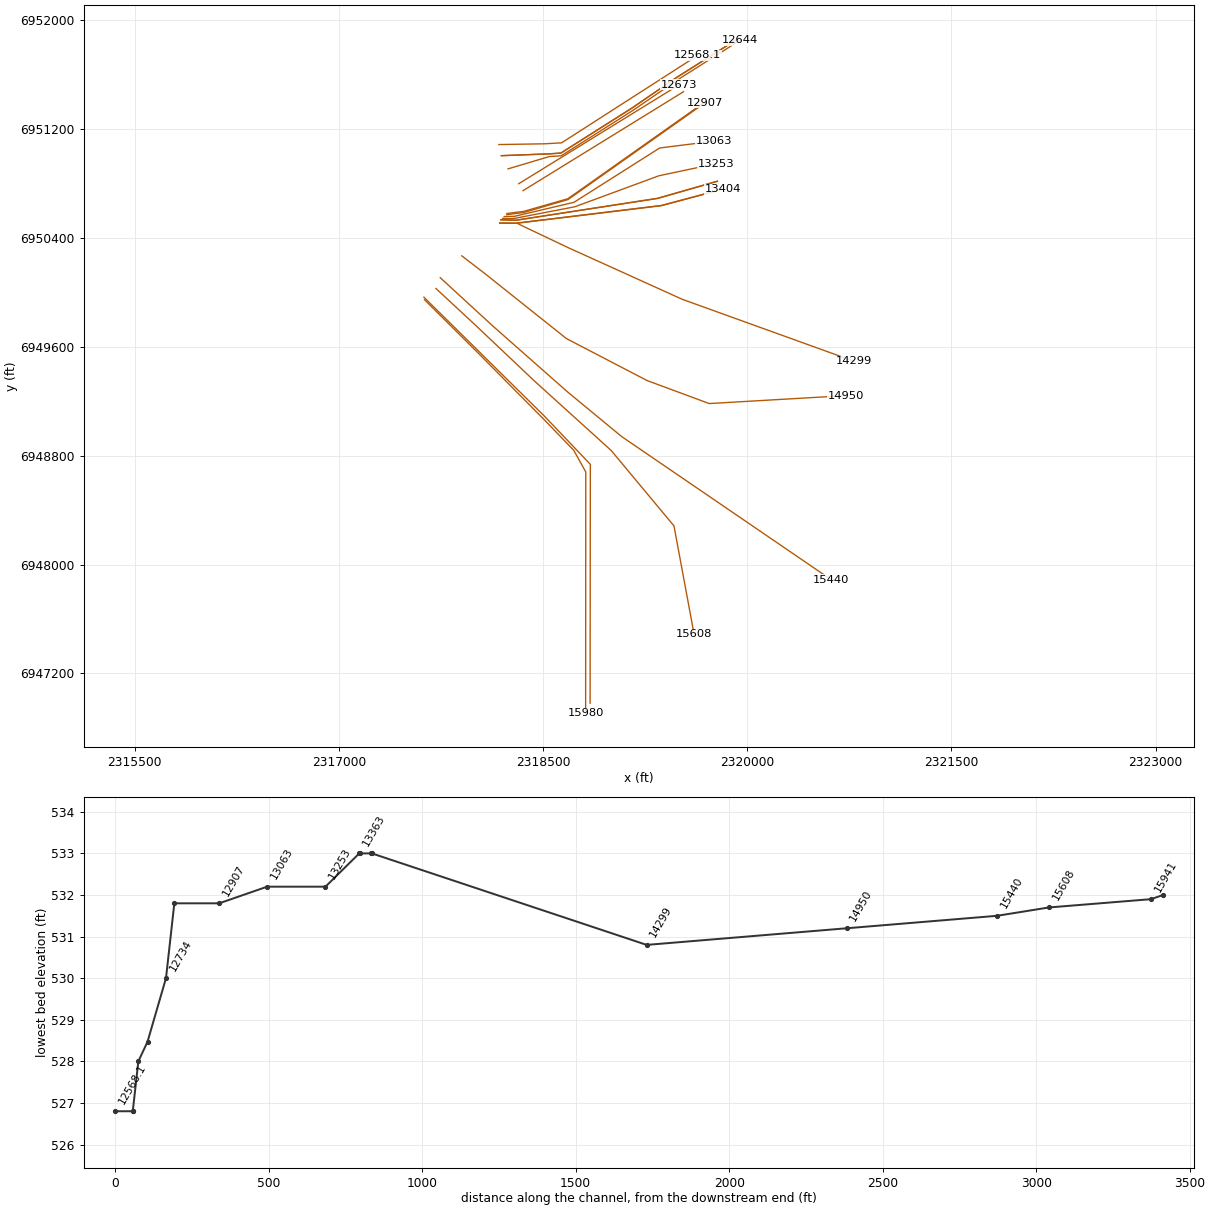
HEC-RAS study CDC_Consolidated_Model.prj: Upper Trinity CDC Consolidated Model

--- CDC_Consolidated_Model.g11 (geometry) --- (continued)

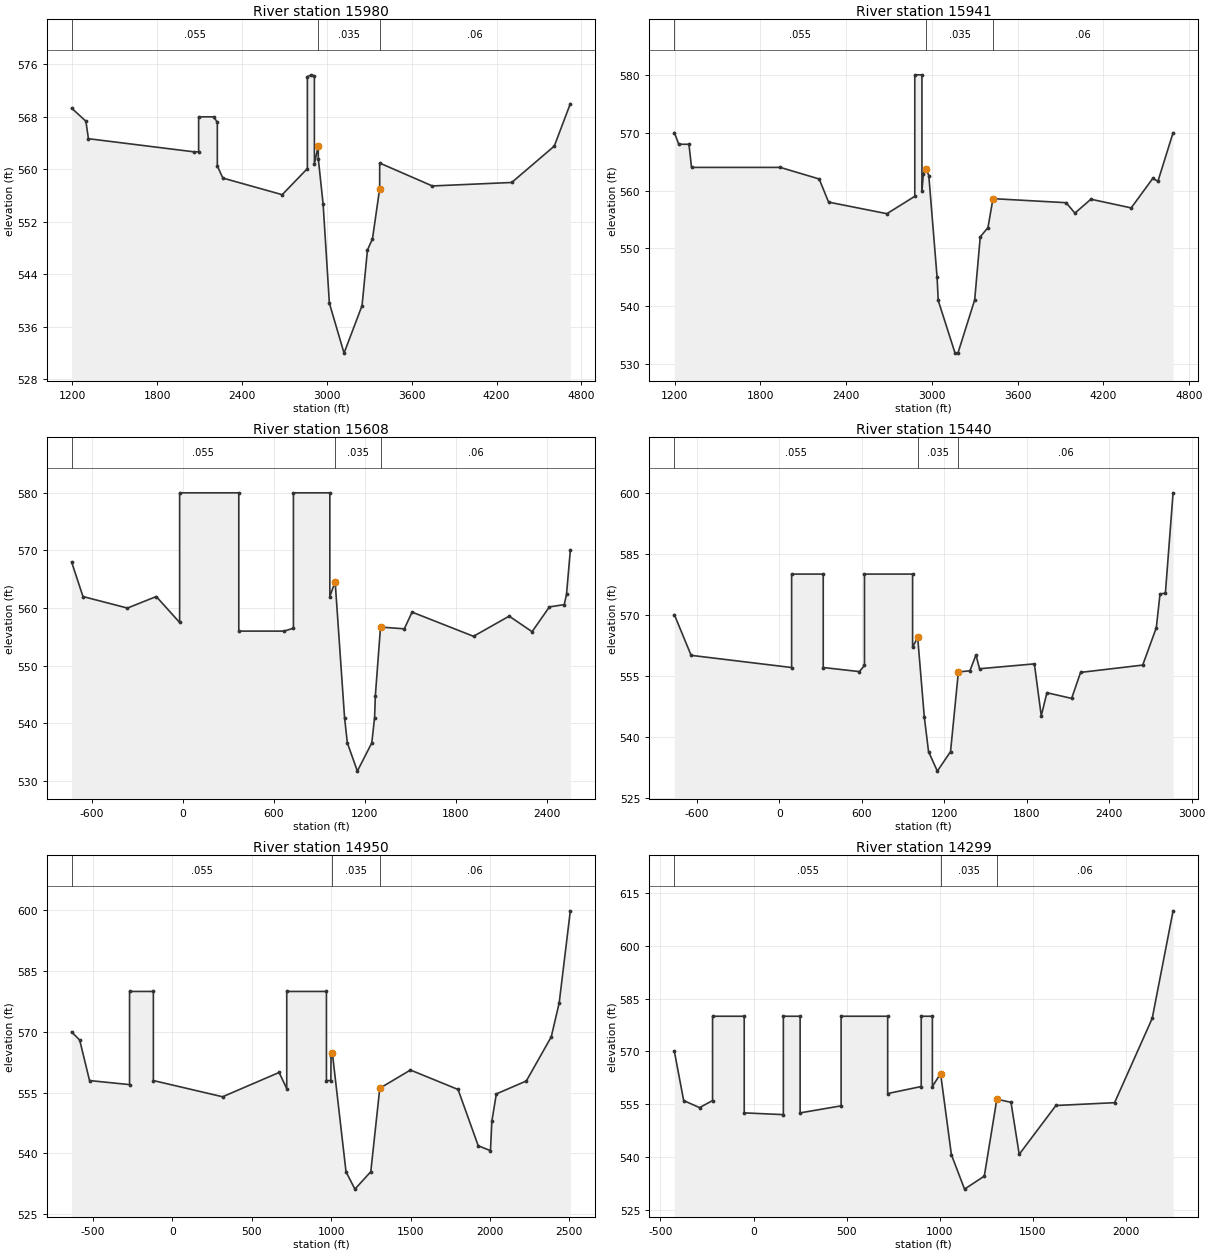
Type RM Length L Ch R = 1 ,15980   ,42.2,38.7,34.5
XS GIS Cut Line= 6
2317629.512906856949946.461675332318029.956786226949548.36417601
2318516.872264216949056.112845582318725.537466526948839.79972802
2318814.142361476948680.438290112318813.158645486946905.61285955
#Sta/Elev= 30
 1194.33  569.33 1295.46  567.33 1313.31  564.67  2058.9  562.67 2092.78  562.67
 2092.78     568  2198.7     568 2225.05  567.18 2225.05  560.51 2264.14  558.67
 2683.94  556.14    2862  560.12    2862  574.12 2890.49   574.4 2911.57  574.23
 2911.57  560.83 2939.33  563.61 2939.33  561.57 2973.28  554.71 3017.52  539.61
 3121.34     532 3248.77  539.25 3286.72   547.7 3322.53  549.43 3373.33  557.07
 3373.33  560.96 3745.73  557.47 4307.54     558 4608.24  563.54 4721.67     570
#Mann= 3 ,0,0
 1194.33    .055       0 2939.33    .035       0 3373.33     .06       0
#XS Ineff= 2 , 0
        2939.333     5603373.333        556.8134
Permanent Ineff=
       F       F
Bank Sta=2939.33,3373.33
XS Rating Curve= 0 ,0
Exp/Cntr=0.5,0.3

Type RM Length L Ch R = 1 ,15941   ,229.5,332.9,475.6
BEGIN DESCRIPTION:
This cross section corresponds to cross section 15948 of the non-georeferenced CDC model which was the source of this model.
107 feet downstream of University Drive.  Forest Park
area in ROB.  Ineffective flow areas defined in LOB due to structures.
Channel data from 1975 USACE field survey.
Downstream limit of Rogers Road trailhead project. PRoject consists of lower and upper trails and fishing pier.
END DESCRIPTION:
XS GIS Cut Line= 6
2317625.259720596949964.85558023   2318040.44204   6949555.05209
   2318509.97489   6949091.04088   2318847.85184   6948736.20399
   2318845.97094   6946981.083162318845.970493786946980.66677889
#Sta/Elev= 30
    1198     570    1229     568    1300     568    1318     564    1939     564
    2211     562    2277     558    2685     556    2880     559    2880     580
    2930     580    2930   559.9    2940   562.9    2958   563.8    2978   562.6
    3036     545    3044     541 3161.76   531.9 3181.76   531.9    3299   541.1
    3338     552    3392   553.6    3427   558.6    3939   557.9    4000   556.1
    4112   558.5    4394     557    4545   562.1    4581   561.6    4687     570
#Mann= 3 ,0,0
    1198    .055       0    2958    .035       0    3427     .06       0
#XS Ineff= 2 , 0
            2958     560    3427           556.3
Permanent Ineff=
       F       F
Bank Sta=2958,3427
XS Rating Curve= 0 ,0
Exp/Cntr=0.3,0.1

Type RM Length L Ch R = 1 ,15608   ,136,168.2,230.3
BEGIN DESCRIPTION:
This cross section corresponds to cross section 15613 of the non-georeferenced CDC model which was the source of this model.
Forest Park area in ROB.
Ineffective flow areas defined in LOB due to structures.
Channel data from 1975 USACE field survey.
END DESCRIPTION:
XS GIS Cut Line= 6
2317713.435885536950028.96856099   2318004.04611   6949759.11796
   2318435.84807   6949350.02986   2319001.02804   6948838.04696
   2319462.18099   6948283.821042319610.39107188 6947485.4434045
#Sta/Elev= 30
    -732     568    -657     562    -364     560    -174     562     -20   557.5
     -20     580     370     580     370     556     668     556     730   556.5
     730     580     970     580     970     562    1005   564.6    1067     541
 1085.46   536.6 1151.46   531.7 1246.46   536.6    1265     541    1270   544.8
    1304   556.7    1461   556.4    1512   559.3    1917   555.1    2152   558.6
    2303   555.9    2417   560.2    2515   560.6    2530   562.4    2555     570
#Mann= 3 ,0,0
    -732    .055       0    1005    .035       0    1304     .06       0
#XS Ineff= 2 , 0
            1005     560    1512          557.17
Permanent Ineff=
       F       F
Bank Sta=1005,1304
XS Rating Curve= 0 ,0
Exp/Cntr=0.3,0.1

Type RM Length L Ch R = 1 ,15440   ,460.1,489.8,543
BEGIN DESCRIPTION:
This cross section corresponds to cross section 15442 of the non-georeferenced CDC model which was the source of this model.
Forest Park area in ROB.
Ineffective flow areas defined in LOB due to structures.
Channel data from 1975 USACE field survey.
END DESCRIPTION:
XS GIS Cut Line= 5
   2317745.28088   6950108.14908   2318127.78799   6949756.36206
   2318680.07987   6949268.90896   2319077.32907   6948940.89092
   2320617.25414   6947888.42386
#Sta/Elev= 30
    -763     570    -641     560      90     557      90     580     320     580
     320     557     583     556     620   557.5     620     580     970     580
     970     562    1007   564.4    1055   544.9 1086.07   536.3 1150.07   531.5
 1246.07   536.3    1303   555.9    1387   556.2    1431   560.1    1457   556.7
    1856   557.9    1906   545.1    1947   550.8    2127   549.4    2192   555.8
    2644   557.6    2743   566.8    2770   575.1    2809   575.3    2865     600
#Mann= 3 ,0,0
    -763    .055       0    1007    .035       0    1303     .06       0
#XS Ineff= 2 , 0
            1007     560    1414          557.22
Permanent Ineff=
       F       F
Bank Sta=1007,1303
XS Rating Curve= 0 ,0
Exp/Cntr=0.3,0.1

Type RM Length L Ch R = 1 ,14950   ,650.4,651.5,653.9
BEGIN DESCRIPTION:
This cross section corresponds to cross section 14949 of the non-georeferenced CDC model which was the source of this model.
Forest Park area in ROB.  Old Clear Fork channel in ROB.
Ineffective flow areas defined in LOB due to structures.
Channel data from 1975 USACE field survey.
END DESCRIPTION:
XS GIS Cut Line= 6
2317903.653431026950268.95445459   2318080.05909   6950132.94792
   2318672.07299   6949660.78285   2319264.10888   6949352.45505
   2319721.08796   6949183.104022320725.533828776949241.54996478
#Sta/Elev= 30
    -635     570    -584     568    -522     558    -270     557    -270     580
    -120     580    -120     558     316     554     672     560     720     556
     720     580     970     580     970     558     998     558     999     564
    1007   564.9 1093.33   535.5 1149.33   531.2 1249.33   535.5    1306   556.1
    1499   560.6    1799   555.8    1926   541.9    2003   540.7    2012     548
    2040   554.7    2229   557.9    2386   568.8    2436   577.2    2506   599.9
#Mann= 3 ,0,0
    -635    .055       0    1007    .035       0    1306     .06       0
#XS Ineff= 2 , 0
            1007     560    1389          556.86
Permanent Ineff=
       F       F
Bank Sta=1007,1306
XS Rating Curve= 0 ,0
Exp/Cntr=0.3,0.1

Type RM Length L Ch R = 1 ,14299   ,823,895,1175
BEGIN DESCRIPTION:
This cross section corresponds to cross section 14297 of the non-georeferenced CDC model which was the source of this model.
Forest Park area in ROB.  Old Clear Fork channel in ROB.
Ineffective flow areas defined in LOB due to structures.
Channel data from 1975 USACE field survey.
END DESCRIPTION:
XS GIS Cut Line= 6
      2318310.29      6950508.57     2318343.781   6950491.35894
    2318687.4099     6950328.043   2319522.80587   6949949.57886
   2320700.21395   6949524.753922320784.918225846949494.19145868
#Sta/Elev= 30
    -425     570    -375     556    -290     554    -220     556    -220     580
     -50     580     -50   552.5     160     552     160     580     250     580
     250   552.5     470   554.5     470     580     720     580     720     558
     900     560     900     580     960     580     960     560    1004   563.7
    1062   540.6 1132.66   530.8 1238.66   534.5    1306   556.4    1382   555.5
    1426   540.7    1623   554.6    1938   555.4    2140   579.4    2252     610
#Mann= 3 ,0,0
    -425    .055       0    1004    .035       0    1306     .06       0
#XS Ineff= 2 , 0
            1004     560    1306             555
Permanent Ineff=
       F       F
Bank Sta=1004,1306
XS Rating Curve= 0 ,0
Exp/Cntr=0.5,0.3

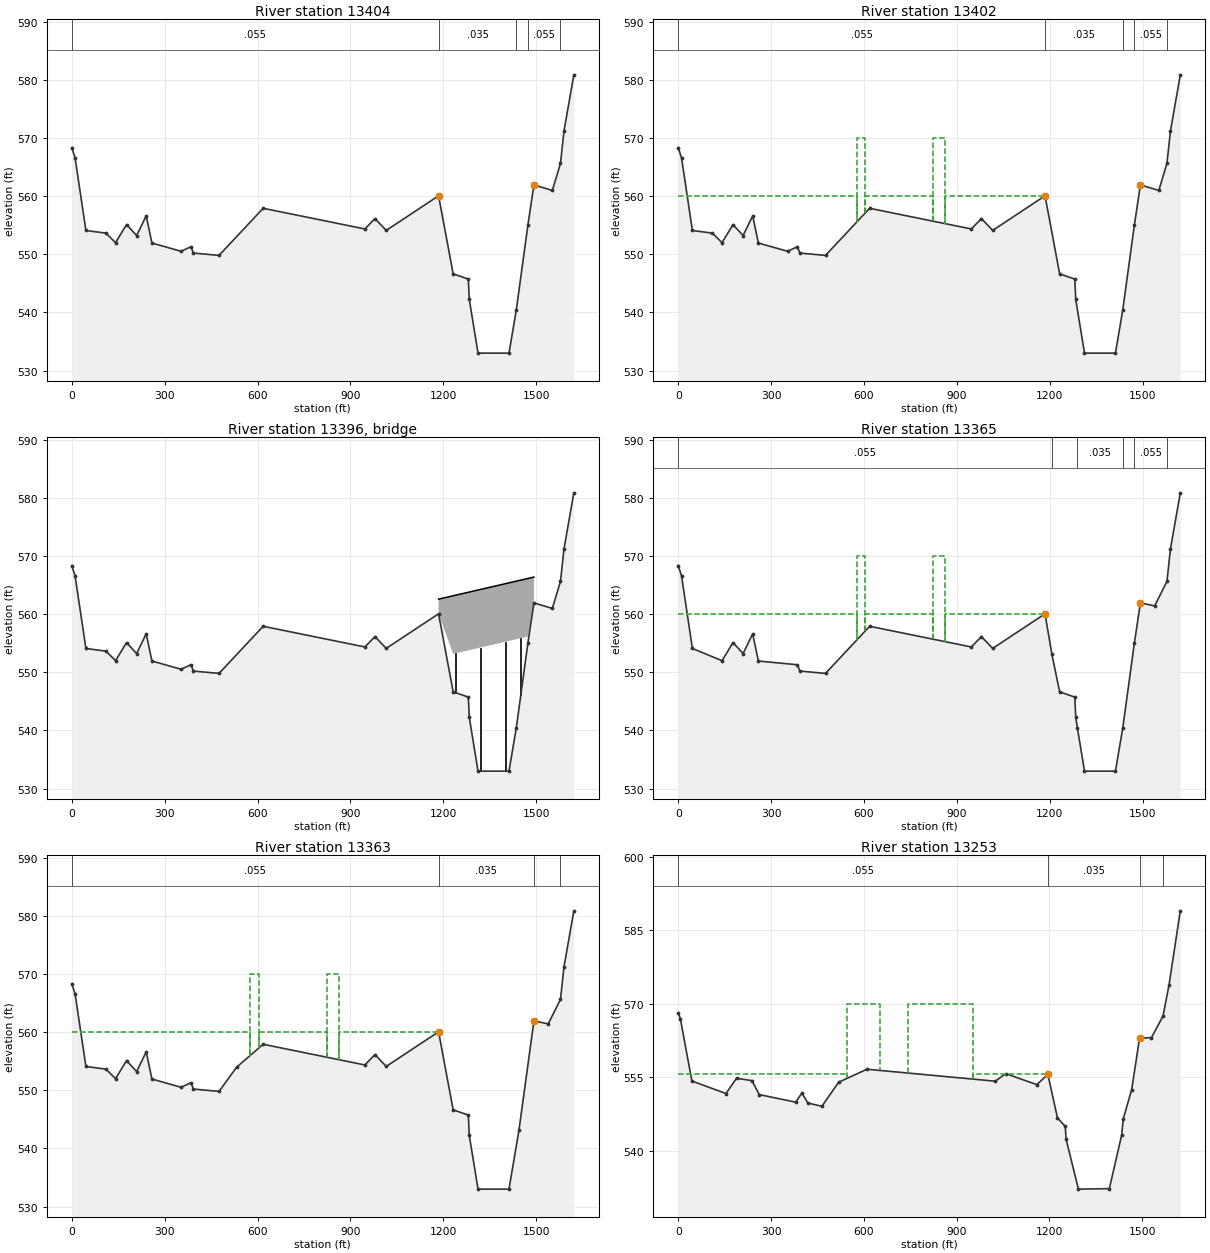
Type RM Length L Ch R = 1 ,13404   ,2,2,2
BEGIN DESCRIPTION:
Copy of 13402.
**********************************************Upstream end of mapping for the Central City project.  The CDC Model (with modifications) is used upstream of this point.
*********************************************
END DESCRIPTION:
XS GIS Cut Line= 4
2318181.774239466950509.046183642318303.717296166950507.91806204
2319370.867338166950637.800340342319821.310921766950758.44049584
#Sta/Elev= 30
       0  568.37    10.7   566.6   45.68  554.11  110.45  553.65  141.36  552.01
  176.88  555.12   209.5  553.24  240.43  556.63  258.85  551.95  352.94  550.53
  384.72  551.31  393.02  550.22  475.61  549.82   618.1  557.93  946.55  554.37
  979.19  556.16  1015.5  554.12 1184.59  560.08 1231.73  546.65 1280.65  545.74
 1283.79  542.24    1312     533    1412     533 1435.83   540.5 1472.99     555
 1492.58  561.96    1552     561 1578.33  565.66  1589.6  571.23 1621.46   580.9
#Mann= 5 ,-1,0
       0    .055       0 1184.59    .035       0 1435.83    .018       0
 1472.99    .055       0 1578.33     .15       0
Bank Sta=1184.59,1492.58
XS Rating Curve= 0 ,0
Exp/Cntr=0.5,0.3

Type RM Length L Ch R = 1 ,13402   ,37,37,37
BEGIN DESCRIPTION:
Upstream of Miniature Railroad.
**********************************************Upstream end of mapping for the Central City project.  The CDC Model (with modifications) is used upstream of this point.
*********************************************
END DESCRIPTION:
XS GIS Cut Line= 4
  2318181.517876 6950510.7984107 2318303.4609327 6950509.6702891
 2319370.6109747 6950639.5525674 2319821.0545583 6950760.1927229
#Sta/Elev= 30
       0  568.37    10.7   566.6   45.68  554.11  110.45  553.65  141.36  552.01
  176.88  555.12   209.5  553.24  240.43  556.63  258.85  551.95  352.94  550.53
  384.72  551.31  393.02  550.22  475.61  549.82   618.1  557.93  946.55  554.37
  979.19  556.16  1015.5  554.12 1184.59  560.08 1231.73  546.65 1280.65  545.74
 1283.79  542.24    1312     533    1412     533 1435.83   540.5 1472.99     555
 1492.58  561.96    1552     561 1578.33  565.66  1589.6  571.23 1621.46   580.9
#Mann= 5 ,-1,0
       0    .055       0 1184.59    .035       0 1435.83    .018       0
 1472.99    .055       0 1578.33     .15       0
#XS Ineff= 5 ,-1
       0  576.08  560.08  576.08  603.85     570  603.85  823.03  560.08
  823.03  861.57     570  861.57 1184.59  560.08
Permanent Ineff=
       F       F       F       F       F
Bank Sta=1184.59,1492.58
XS Rating Curve= 0 ,0
Exp/Cntr=0.5,0.3

Type RM Length L Ch R = 3 ,13396   ,,,
BEGIN DESCRIPTION:
Pedestrian Bridge and Miniature Railroad
Parallel bridges modeled as one bridge with bridge width of 35 feet.
MR data from bridge plans. PB from bridge plans.  Bridges are skewed - modeled bridge is a representation of the two bridges skewed and projected across the river channel.
END DESCRIPTION:
Node Name=Min RR/Ped bridg
Bridge Culvert--1,0,-1,-1, 0
Deck Dist Width WeirC Skew NumUp NumDn MinLoCord MaxHiCord MaxSubmerge Is_Ogee
1,35,2.6,0, 2, 2, , , 0.95, 0, 0,0,,
 1184.59 1492.58
   562.6   566.4
   552.6   556.4
 1184.59 1492.58
   562.6   566.4
   552.6   556.4
Pier Skew, UpSta & Num, DnSta & Num=  ,1240, 2 ,1240, 2 , 0 , 0 , 0 ,,
     3.5     3.5
     450     554
     3.5     3.5
     450     554
Pier Skew, UpSta & Num, DnSta & Num=  ,1320, 2 ,1320, 2 , 0 , 0 , 0 ,,
     3.5     3.5
     450     556
     3.5     3.5
     450     556
Pier Skew, UpSta & Num, DnSta & Num=  ,1400, 2 ,1400, 2 , 0 , 0 , 0 ,,
     3.5     3.5
     450     556
     3.5     3.5
     450     556
Pier Skew, UpSta & Num, DnSta & Num=  ,1450, 2 ,1450, 2 , 0 , 0 , 0 ,,
     3.5     3.5
     450     556
     3.5     3.5
     450     556
BR Coef=-1 , 0 , 0 ,, 0 ,,,0.8,-1,,0,
WSPro=,,,, 1 ,,,, 0 ,,,, 0 ,,,,-1 ,-1 ,-1 , 0 , 0 , 0 , 0 , 0
BC Design=,, 0 ,, 0 ,,,,,,
BC Use User HTab Curves=0
BC User HTab FreeFlow(D)= 0

Type RM Length L Ch R = 1 ,13365   ,2,2,2
BEGIN DESCRIPTION:
Downstream of Pedestrian Bridge.
END DESCRIPTION:
XS GIS Cut Line= 4
  2318190.071127 6950533.5706271  2318300.975837 6950530.0492809
 2319341.9315595 6950690.7510344 2319781.4438673 6950816.7424496
#Sta/Elev= 30
       0  568.37    10.7   566.6   45.68  554.11  141.36  552.01  176.88  555.12
   209.5  553.24  240.43  556.63  258.85  551.95  384.72  551.31  393.02  550.22
  475.61  549.82   618.1  557.93  946.55  554.37  979.19  556.16  1015.5  554.12
 1184.59  560.08 1206.74  553.11 1231.73  546.65 1280.65  545.74 1283.79  542.24
 1288.97   540.5    1312     533    1412     533 1435.83   540.5 1472.99     555
 1492.58  561.96  1538.7  561.44 1578.33  565.66  1589.6  571.23 1621.46   580.9
#Mann= 6 ,-1,0
       0    .055       0 1206.74    .018       0 1288.97    .035       0
 1435.83    .018       0 1472.99    .055       0 1578.33     .15       0
#XS Ineff= 5 ,-1
       0  576.08  560.08  576.08  603.85     570  603.85  823.03  560.08
  823.03  861.57     570  861.57 1184.59  560.08
Permanent Ineff=
       F       F       F       F       F
Bank Sta=1184.59,1492.58
XS Rating Curve= 0 ,0
Exp/Cntr=0.5,0.3

Type RM Length L Ch R = 1 ,13363   ,110,110,110
BEGIN DESCRIPTION:
Copy of 13425
END DESCRIPTION:
XS GIS Cut Line= 4
  2318189.783857 6950534.8680926 2318300.6885667 6950531.3467464
 2319341.6442892 6950692.0484999  2319781.156597 6950818.0399151
#Sta/Elev= 30
       0  568.37    10.7   566.6   45.68  554.11  110.45  553.65  141.36  552.01
  176.88  555.12   209.5  553.24  240.43  556.63  258.85  551.95  352.94  550.53
  384.72  551.31  393.02  550.22  475.61  549.82  532.67     554   618.1  557.93
  946.55  554.37  979.19  556.16  1015.5  554.12 1184.59  560.08 1231.73  546.65
 1280.65  545.74 1283.79  542.24    1312     533    1412     533  1444.1   543.1
 1492.58  561.96  1538.7  561.44 1578.33  565.66  1589.6  571.23 1621.46   580.9
#Mann= 4 ,-1,0
       0    .055       0 1184.59    .035       0 1492.58    .055       0
 1578.33     .15       0
#XS Ineff= 5 ,-1
       0  576.08  560.08  576.08  603.85     570  603.85  823.03  560.08
  823.03  861.57     570  861.57 1184.59  560.08
Permanent Ineff=
       F       F       F       F       F
Bank Sta=1184.59,1492.58
XS Rating Curve= 0 ,0
Exp/Cntr=0.5,0.3

Type RM Length L Ch R = 1 ,13253   ,187.3,190,176
BEGIN DESCRIPTION:
This cross section corresponds to cross section 13253.36 of the non-georeferenced CDC model which was the source of this model.
END DESCRIPTION:
XS GIS Cut Line= 5
 2318203.2053612 6950543.8905581 2318281.9800391 6950542.7763229
  2318733.595832 6950629.5690866 2319351.5889127 6950857.5834798
 2319768.4874964 6950945.8471117
#Sta/Elev= 30
       0  568.11    6.85  566.97   44.08  554.25  154.49  551.69   188.4   554.8
  238.06  554.33  262.18  551.47  379.66  549.94  399.84  551.79  419.34  549.75
  464.53   549.1  518.62     554  610.37  556.65 1025.29  554.21 1058.82  555.75
 1159.51  553.51 1195.18  555.61 1226.23  546.73 1251.32     545 1254.36  542.35
    1294   532.2    1394   532.3 1433.81  543.19 1439.01  546.51 1466.31  552.51
 1491.67  562.96 1530.35  563.11 1567.67   567.5 1587.17   573.9 1623.52  588.95
#Mann= 4 ,-1,0
       0    .055       0 1195.18    .035       0 1491.67    .055       0
 1567.67     .15       0
#XS Ineff= 5 ,-1
       0  546.05  555.61  546.05  652.11     570  652.11  743.64  555.61
  743.64  954.08     570  954.08 1195.18  555.61
Permanent Ineff=
       F       F       F       F       F
Bank Sta=1195.18,1491.67
XS Rating Curve= 0 ,0
Exp/Cntr=0.3,0.1

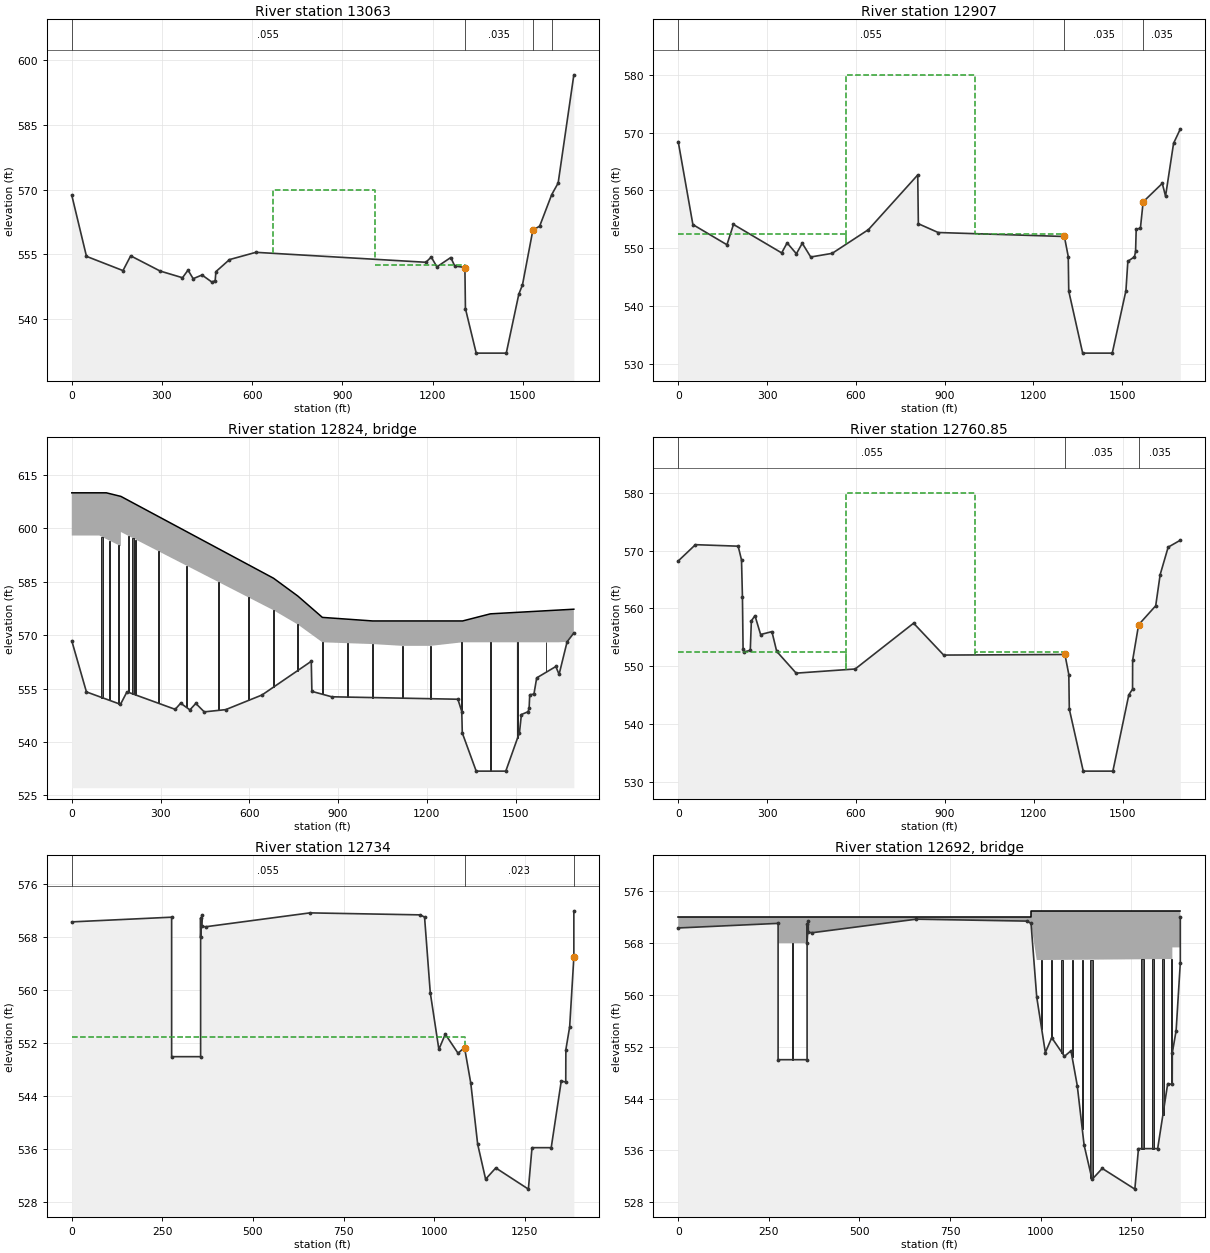
Type RM Length L Ch R = 1 ,13063   ,103.52,156,230.18
BEGIN DESCRIPTION:
This cross section corresponds to cross section 13062.82 of the non-georeferenced CDC model which was the source of this model.
END DESCRIPTION:
XS GIS Cut Line= 5
 2318214.9321194 6950557.4936909 2318290.9828521 6950559.6447677
 2318727.4254711 6950662.4199032 2319357.0484707 6951061.7114967
 2319753.6349163 6951111.6058985
#Sta/Elev= 30
       0  568.68    48.9  554.56  170.29  551.27  195.93  554.68  294.11  551.16
  368.22  549.62  386.65  551.38  403.72   549.4  433.13  550.25  465.96  548.62
   476.9  548.93  479.34  551.03  524.46  553.81  612.32  555.49 1177.79  553.19
 1195.44   554.4 1214.31  552.14 1260.46  554.29  1273.6  552.34 1307.42  551.98
 1309.19  542.48    1345   532.2    1445   532.2 1486.78  545.84 1498.88  547.97
 1533.42  560.62 1556.06  561.54  1596.1  568.82 1617.54   571.5 1669.73   596.5
#Mann= 4 ,-1,0
       0    .055       0 1307.42    .035       0 1533.42    .055       0
  1596.1     .15       0
#XS Ineff= 3 ,-1
       0  669.18  552.57  669.18 1007.63     570 1007.63 1307.42  552.57
Permanent Ineff=
       F       F       F
Bank Sta=1307.42,1533.42
XS Rating Curve= 0 ,0
Exp/Cntr=0.3,0.1

Type RM Length L Ch R = 1 ,12907   ,146.1,146.1,146.1
BEGIN DESCRIPTION:
Upstream of Rosedale Street.
At USGS gaging station 08048000 - Clear Fork at Trinity River Gage - located on left bank of Clear Fork at Fort Worth pumping station.  Gage datum elev. 532.91 MSL.
END DESCRIPTION:
Node Name=CF Gage
XS GIS Cut Line= 5
 2318233.9293414 6950571.2318326 2318359.2859677 6950587.9888604
  2318683.553314  6950682.742234 2318753.2063553 6950731.7946253
 2319692.9640904 6951396.1822523
#Sta/Elev= 30
       0  568.42   49.54  554.06  164.66  550.57  186.68  554.09   349.6  549.16
  368.07  550.89  399.33  549.01  419.24  550.83  447.78  548.45  520.29  549.08
   642.9  553.19  809.53  562.66   811.6  554.21  878.59  552.69 1305.16     552
 1318.26  548.53 1319.95  542.54    1367   531.8    1467   531.8 1513.21  542.61
 1519.74   547.7 1542.14  548.49 1545.87  549.44 1547.91  553.24  1562.2  553.46
 1571.45     558 1636.14   561.2 1647.14  558.98 1674.25  568.14 1697.04  570.62
#Mann= 3 ,0,0
       0    .055       0 1305.16    .035       0 1571.45    .035       0
#XS Ineff= 3 ,-1
       0  567.78  552.49  567.78 1003.13     580 1003.13 1305.16  552.49
Permanent Ineff=
       F       F       F
Bank Sta=1305.16,1571.45
XS Rating Curve= 0 ,0
Exp/Cntr=0.5,0.3

Type RM Length L Ch R = 3 ,12824   ,,,
BEGIN DESCRIPTION:
Rosedale Street and Vickery Connection
Data from TXDOT bridge plans.  Eastbound connection represented.
END DESCRIPTION:
Node Name=Rosedale Street
Bridge Culvert--1,0,-1,-1, 0
Deck Dist Width WeirC Skew NumUp NumDn MinLoCord MaxHiCord MaxSubmerge Is_Ogee
18.03253,120,2.6,0, 14, 14, , , 0.95, 0, 0,0,,
       0   93.04  117.04  166.04  166.04  682.04  764.04  847.04 1017.04 1117.04
 1213.04 1321.04 1415.04 1697.04
     610     610     610     609     609     586     581     575     574     574
     574     574     576   577.3
     598     598     597     595     599     577     573     568   567.5     567
     567     568     568     568
       0   93.04  117.04  166.04  166.04  682.04  764.04  847.04 1017.04 1117.04
 1213.04 1321.04 1415.04 1697.04
     610     610     610     609     609     586     581     575     574     574
     574     574     576   577.3
     598     598     597     595     599     577     573     568   567.5     567
     567     568     568     568
Pier Skew, UpSta & Num, DnSta & Num=  ,102, 4 ,102, 4 , 0 , 0 , 0 ,,
     4.5     4.5       3       3
     500     577     577     605
     4.5     4.5       3       3
     500     577     577     605
Pier Skew, UpSta & Num, DnSta & Num=  ,127, 4 ,127, 4 , 0 , 0 , 0 ,,
     4.5     4.5       3       3
     500     577     577     605
     4.5     4.5       3       3
     500     577     577     605
Pier Skew, UpSta & Num, DnSta & Num=  ,157, 4 ,157, 4 , 0 , 0 , 0 ,,
     4.5     4.5       3       3
     500     577     577     605
     4.5     4.5       3       3
     500     577     577     605
Pier Skew, UpSta & Num, DnSta & Num=  ,192, 2 ,192, 2 , 0 , 0 , 0 ,,
     3.5     3.5
     500     605
     3.5     3.5
     500     605
Pier Skew, UpSta & Num, DnSta & Num=  ,207, 2 ,207, 2 , 0 , 0 , 0 ,,
     3.5     3.5
     500     605
     3.5     3.5
     500     605
Pier Skew, UpSta & Num, DnSta & Num=  ,217, 2 ,217, 2 , 0 , 0 , 0 ,,
     3.5     3.5
     500     605
     3.5     3.5
     500     605
Pier Skew, UpSta & Num, DnSta & Num=  ,292, 2 ,292, 2 , 0 , 0 , 0 ,,
     3.5     3.5
     500     605
     3.5     3.5
     500     605
Pier Skew, UpSta & Num, DnSta & Num=  ,387, 2 ,387, 2 , 0 , 0 , 0 ,,
     3.5     3.5
     500     605
     3.5     3.5
     500     605
Pier Skew, UpSta & Num, DnSta & Num=  ,497, 2 ,497, 2 , 0 , 0 , 0 ,,
     3.5     3.5
     500     605
     3.5     3.5
     500     605
Pier Skew, UpSta & Num, DnSta & Num=  ,597, 2 ,597, 2 , 0 , 0 , 0 ,,
       3       3
     500     605
       3       3
     500     605
Pier Skew, UpSta & Num, DnSta & Num=  ,682, 2 ,682, 2 , 0 , 0 , 0 ,,
       3       3
     500     605
       3       3
     500     605
Pier Skew, UpSta & Num, DnSta & Num=  ,764, 2 ,764, 2 , 0 , 0 , 0 ,,
       3       3
     500     605
       3       3
     500     605
Pier Skew, UpSta & Num, DnSta & Num=  ,847, 2 ,847, 2 , 0 , 0 , 0 ,,
       3       3
     500     605
       3       3
     500     605
Pier Skew, UpSta & Num, DnSta & Num=  ,932, 2 ,932, 2 , 0 , 0 , 0 ,,
       3       3
     500     605
       3       3
     500     605
Pier Skew, UpSta & Num, DnSta & Num=  ,1017, 2 ,1017, 2 , 0 , 0 , 0 ,,
       3       3
     500     605
       3       3
     500     605
Pier Skew, UpSta & Num, DnSta & Num=  ,1117, 2 ,1117, 2 , 0 , 0 , 0 ,,
     3.5     3.5
     500     605
     3.5     3.5
     500     605
Pier Skew, UpSta & Num, DnSta & Num=  ,1213, 2 ,1213, 2 , 0 , 0 , 0 ,,
     3.5     3.5
     500     605
     3.5     3.5
     500     605
Pier Skew, UpSta & Num, DnSta & Num=  ,1317, 2 ,1317, 2 , 0 , 0 , 0 ,,
     3.5     3.5
     500     605
     3.5     3.5
     500     605
Pier Skew, UpSta & Num, DnSta & Num=  ,1415, 2 ,1415, 2 , 0 , 0 , 0 ,,
     3.5     3.5
     500     605
     3.5     3.5
     500     605
Pier Skew, UpSta & Num, DnSta & Num=  ,1507, 2 ,1507, 2 , 0 , 0 , 0 ,,
     3.5     3.5
     500     605
     3.5     3.5
     500     605
Pier Skew, UpSta & Num, DnSta & Num=  ,1603, 2 ,1603, 2 , 0 , 0 , 0 ,,
       3       3
     500     605
       3       3
     500     605
BR Coef=-1 , 0 , 0 ,, 0 ,,,0.8,-1,,0,
WSPro=,,,, 1 ,,,, 0 ,,,, 0 ,,,,-1 ,-1 ,-1 , 0 , 0 , 0 , 0 , 0
BC Design=,, 0 ,, 0 ,,,,,,
BC Use User HTab Curves=0
BC User HTab FreeFlow(D)= 0

Type RM Length L Ch R = 1 ,12760.85,27.2,27.2,27.2
BEGIN DESCRIPTION:
Downstream of Rosedale Street.
Copy of cross-section 12901.55
RevEx - Section relocated DS of BR and recut from 2009 LiDAR and supplemented with survey
END DESCRIPTION:
XS GIS Cut Line= 5
  2318234.538687 6950580.0673562 2318359.8953142 6950596.2150379
 2318680.5065817 6950688.2263523 2318748.8583262 6950735.2103798
 2319687.6151862 6951399.0782252
#Sta/Elev= 30
       0   568.2   58.07  571.02  202.25  570.76  213.57  568.38  216.71  561.92
  218.84  552.97  221.36  552.43  243.17  552.73  246.81  557.83  259.04  558.72
  278.01  555.46  316.17  555.96  332.36  552.54  397.98  548.77  597.21  549.49
  794.37  557.42  895.92   551.9 1305.16     552 1318.26  548.53 1319.95  542.54
    1367   531.8    1467   531.8  1520.7     545  1533.4     546  1533.7     551
 1553.83  557.15 1611.57  560.44 1626.57  565.83 1653.59  570.59  1694.6  571.79
#Mann= 3 ,0,0
       0    .055       0 1305.16    .035       0 1553.83    .035       0
#XS Ineff= 3 ,-1
       0  567.78  552.49  567.78 1003.13     580 1003.13 1305.16  552.49
Permanent Ineff=
       F       F       F
Bank Sta=1305.16,1553.83
XS Rating Curve= 0 ,0
Exp/Cntr=0.5,0.3

Type RM Length L Ch R = 1 ,12734   ,60.1,60.2,60
BEGIN DESCRIPTION:
Upstream of Union Pacific Railroad.
Copy of cross-section 12673.49..
---------------------------------------------------------------------
CDC FW072209-1 UNION PACIFIC RAILROAD BRIDGE
CROSS-SECTION 12617.5 - 12733.65
UPSTREAM END.
---------------------------------------------------------------------
END DESCRIPTION:
XS GIS Cut Line= 2
 2318353.2774795 6950748.1628615 2319532.4170336 6951475.5693008
#Sta/Elev= 30
       0  570.35  275.56  571.06  275.56     550  355.56     550  355.56   570.9
   355.6     568  358.75  571.36  358.95  569.66  370.36  569.62  657.13  571.71
  961.51  571.41  973.51  571.08  989.24  559.68 1013.03   551.1 1030.66   553.4
 1065.84  550.52 1083.79  551.38 1101.07     546    1120   536.8    1142   531.5
    1170   533.2    1260     530    1270  536.26    1323  536.26 1350.67   546.3
 1363.13  546.18 1363.43  551.06 1373.91   554.5 1385.46     565 1385.46  572.02
#Mann= 3 ,0,0
       0    .055       0 1083.79    .023       0 1385.46    .055       0
#XS Ineff= 2 , 0
         1083.79     553
Permanent Ineff=
       F       F
Bank Sta=1083.79,1385.46
XS Rating Curve= 0 ,0
Exp/Cntr=0.5,0.3

Type RM Length L Ch R = 3 ,12692   ,,,
BEGIN DESCRIPTION:
Union Pacific Railroad
Two parallel bridges represented as one bridge.  Older upstream bridge data from USACE 1975 survey, Fort Worth Floodway as-builts plans. Newer downstream bridge data from bridge plans.
END DESCRIPTION:
Node Name=UP RR
Bridge Culvert--1,0,-1,-1, 0
Deck Dist Width WeirC Skew NumUp NumDn MinLoCord MaxHiCord MaxSubmerge Is_Ogee
20,40,2.6,0, 12, 12, , , 0.95, 0, 0,0,,
       0  275.56  275.56  355.56  355.56  973.51  973.51  1363.5  1363.5    1385
    1385 1385.46
     572     572     572     572     572     572     573     573     573     573
     573     573
     450     450     568     568     450     450  565.39  565.55  567.35  567.35
     450     450
       0  275.56  275.56  355.56  355.56  973.51  973.51  1363.5  1363.5    1385
    1385 1385.46
     572     572     572     572     572     572     573     573     573     573
     573     573
     450     450     568     568     450     450  565.39  565.55  567.35  567.35
     450     450
Pier Skew, UpSta & Num, DnSta & Num=  ,315.56, 2 ,315.56, 2 , 0 , 0 , 0 ,,
       4       4
     450     571
       4       4
     450     571
Pier Skew, UpSta & Num, DnSta & Num=  ,1003, 2 ,1003, 2 , 0 , 0 , 0 ,,
       3       3
     450     568
       3       3
     450     568
Pier Skew, UpSta & Num, DnSta & Num=  ,1031, 2 ,1031, 2 , 0 , 0 , 0 ,,
       3       3
     450     568
       3       3
     450     568
Pier Skew, UpSta & Num, DnSta & Num=  ,1059, 2 ,1059, 2 , 0 , 0 , 0 ,,
       3       3
     450     568
       3       3
     450     568
Pier Skew, UpSta & Num, DnSta & Num=  ,1087, 2 ,1087, 2 , 0 , 0 , 0 ,,
       3       3
     450     568
       3       3
     450     568
Pier Skew, UpSta & Num, DnSta & Num=  ,1115, 2 ,1115, 2 , 0 , 0 , 0 ,,
       3       3
     450     568
       3       3
     450     568
Pier Skew, UpSta & Num, DnSta & Num=  ,1141.3, 2 ,1141.3, 2 , 0 , 0 , 0 ,,
       8     6.5
     536     568
       8     6.5
     536     568
Pier Skew, UpSta & Num, DnSta & Num=  ,1280.3, 2 ,1280.3, 2 , 0 , 0 , 0 ,,
       8     6.5
     536     568
       8     6.5
     536     568
Pier Skew, UpSta & Num, DnSta & Num=  ,1309.76, 2 ,1309.76, 2 , 0 , 0 , 0 ,,
     5.5     5.5
     450     570
     5.5     5.5
     450     570
Pier Skew, UpSta & Num, DnSta & Num=  ,1337.5, 2 ,1337.5, 2 , 0 , 0 , 0 ,,
       4       4
     450     567
       4       4
     450     567
Pier Skew, UpSta & Num, DnSta & Num=  ,1362, 2 ,1362, 2 , 0 , 0 , 0 ,,
       3       3
     450  565.55
       3       3
     450  565.55
BR Coef=-1 , 0 , 0 ,, 0 ,,,0.8,-1,,0,
WSPro=,,,, 1 ,,,, 0 ,,,, 0 ,,,,-1 ,-1 ,-1 , 0 , 0 , 0 , 0 , 0
BC Design=,, 0 ,, 0 ,,,,,,
BC Use User HTab Curves=0
BC User HTab FreeFlow(D)= 0

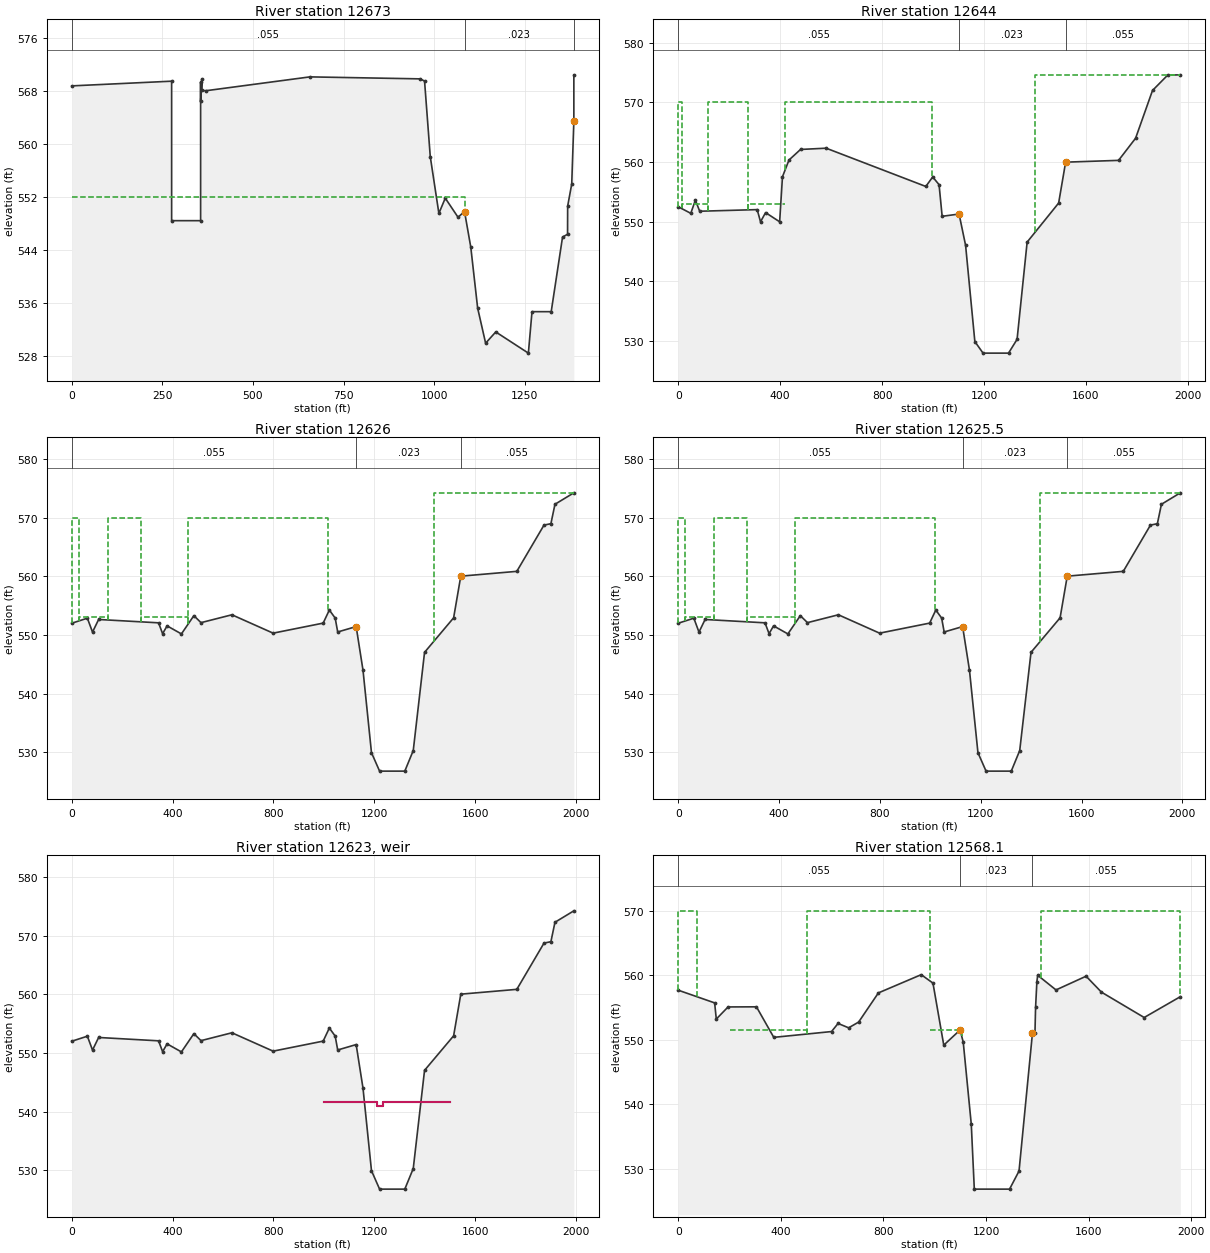
Type RM Length L Ch R = 1 ,12673   ,20.9,29.8,35.3
BEGIN DESCRIPTION:
Downstream of Union Pacific Railroad.
Added cross-section from ground points generated through centerline of railroad bridge.
Data from Fort Worth Floodway as-builts.
END DESCRIPTION:
XS GIS Cut Line= 2
 2318321.7758014 6950799.2278909 2319500.9153555 6951526.6343302
#Sta/Elev= 30
       0  568.82  275.56  569.53  275.56  548.47  355.56  548.47  355.56  569.37
   355.6  566.47  358.75  569.83  358.95  568.13  370.36  568.09  657.13  570.18
  961.51  569.88  973.51  569.55  989.24  558.15 1013.03  549.57 1030.66  551.87
 1065.84  548.99 1083.79  549.85 1101.07  544.47    1120  535.27    1142  529.97
    1170  531.67    1260  528.47    1270  534.73    1323  534.73 1354.26  545.99
 1368.12  546.42 1368.38  550.67 1379.62     554 1385.46  563.47 1385.46  570.49
#Mann= 3 ,0,0
       0    .055       0 1083.79    .023       0 1385.46    .055       0
#XS Ineff= 2 , 0
         1083.79     552
Permanent Ineff=
       F       F
Bank Sta=1083.79,1385.46
XS Rating Curve= 0 ,0
Exp/Cntr=0.5,0.3

Type RM Length L Ch R = 1 ,12644   ,18.2,18.2,18.2
BEGIN DESCRIPTION:
This cross section corresponds to cross section 12643.73 of the non-georeferenced CDC model which was the source of this model.
END DESCRIPTION:
XS GIS Cut Line= 6
 2318243.1166305 6950908.3446387 2318546.5320128 6950998.8029055
 2318633.9443146 6951004.6242821 2319163.1561204 6951339.8461205
 2319485.2754863  6951560.921661 2319949.3936592 6951854.5120687
#Sta/Elev= 30
       0  552.52    49.2  551.42   67.23  553.61   84.27  551.77  309.89  552.04
  322.93     550  342.87  551.54     398     550   409.1  557.55  434.74  560.35
  479.94  562.12  580.54  562.33  971.68  555.92  998.71  557.51 1023.69  556.22
 1035.79  550.92 1102.22   551.3  1127.8  546.06 1164.15  529.94 1196.34     528
 1296.34     528 1329.89  530.31 1369.37   546.6    1493  553.14 1520.44  559.99
 1728.19  560.29 1795.03     564 1861.42     572  1920.9  574.57 1970.53  574.62
#Mann= 3 ,0,0
       0    .055       0 1102.22    .023       0 1520.44    .055       0
#XS Ineff= 7 ,-1
       0   12.88     570   12.88  115.07     553  115.07  272.54     570
  272.54  419.42     553  419.42  996.46     570  996.46    1030     553
 1401.93 1970.53 574.617
Permanent Ineff=
       F       F       F       F       F       F       F
Bank Sta=1102.22,1520.44
XS Rating Curve= 0 ,0
Exp/Cntr=0.3,0.1

Type RM Length L Ch R = 1 ,12626   ,0.5,0.5,0.5
BEGIN DESCRIPTION:
This cross section corresponds to cross section 12625.52 of the non-georeferenced CDC model which was the source of this model.
END DESCRIPTION:
XS GIS Cut Line= 6
 2318193.9413285 6951005.3112317 2318543.5032895 6951018.5813256
 2318631.1372716 6951024.4174808 2319153.4360226 6951355.2602906
 2319475.5629075 6951576.34101672319936.462825286951867.89561415
#Sta/Elev= 30
       0     552   61.93  552.86   82.29  550.49  106.58  552.64  344.34  552.07
  360.35  550.22  378.22  551.55  435.02  550.18   484.4  553.29  512.75   552.1
  635.38  553.44  798.83  550.31  997.44  552.02 1021.88  554.25 1045.07  552.88
 1055.08  550.51 1128.31  551.43 1155.46     544 1189.11  529.94  1221.3   526.8
  1321.3   526.8 1354.85  530.31 1399.64  547.04    1515  552.92 1543.39  560.02
  1765.7  560.84 1873.55  568.72 1900.93  568.96 1917.07  572.27 1991.98  574.22
#Mann= 3 ,0,0
       0    .055       0 1128.31    .023       0 1543.39    .055       0
#XS Ineff= 7 ,-1
       0   27.31     570   27.31  143.47     553  143.47  274.17     570
  274.17  463.04     553  463.04  1017.7     570  1017.7 1021.88     553
  1435.6 1996.35 574.215
Permanent Ineff=
       F       F       F       F       F       F       F
Bank Sta=1128.31,1543.39
XS Rating Curve= 0 ,0
Exp/Cntr=0.3,0.1

Type RM Length L Ch R = 1 ,12625.5 ,63.1,57.4,53.9
BEGIN DESCRIPTION:
Upstream of City Dam No. 2
Copy of cross-section 12625.52.
---------------------------------------------------------------------
CDC FW072209-1 UNION PACIFIC RAILROAD BRIDGE
CROSS-SECTION 12617.5 - 12733.65
DOWNSTREAM END.
---------------------------------------------------------------------
END DESCRIPTION:
XS GIS Cut Line= 6
 2318193.9413285 6951005.3112317 2318543.5032895 6951018.5813256
 2318631.1372716 6951024.4174808 2319153.4360226 6951355.2602906
 2319475.5629075 6951576.34101672319936.462825286951867.89561415
#Sta/Elev= 30
       0     552   61.93  552.86   82.29  550.49  106.58  552.64  344.34  552.07
  360.35  550.22  378.22  551.55  435.02  550.18   484.4  553.29  512.75   552.1
  635.38  553.44  798.83  550.31  997.44  552.02 1021.88  554.25 1045.07  552.88
 1055.08  550.51 1128.31  551.43 1155.46     544 1189.11  529.94  1221.3   526.8
  1321.3   526.8 1354.85  530.31 1399.64  547.04    1515  552.92 1543.39  560.02
  1765.7  560.84 1873.55  568.72 1900.93  568.96 1917.07  572.27 1991.98  574.22
#Mann= 3 ,0,0
       0    .055       0 1128.31    .023       0 1543.39    .055       0
#XS Ineff= 7 ,-1
       0   27.31     570   27.31  143.47     553  143.47  274.17     570
  274.17  463.04     553  463.04  1017.7     570  1017.7 1021.88     553
  1435.6 1996.35 574.215
Permanent Ineff=
       F       F       F       F       F       F       F
Bank Sta=1128.31,1543.39
XS Rating Curve= 0 ,0
Exp/Cntr=0.3,0.1

Type RM Length L Ch R = 5 ,12623   ,,,
BEGIN DESCRIPTION:
City Dam No. 2
Ogee weir.  Structure weir length 224.7 feet.  Crest elev. 541.6 feet, notch length 20 feet - minimum weir crest elev. 541.0
Data from project plans, design computations.
END DESCRIPTION:
Node Name=City Dam No. 2
IW Pilot Flow=0
#Inline Weir SE= 6
    1000   541.6 1212.83   541.6 1212.83     541 1232.83     541 1232.83   541.6
    1500   541.6
IW Dist,WD,Coef,Skew,MaxSub,Min_El,Is_Ogee,SpillHt,DesHd
1.5,2,3.88,0,0.95,,-1 ,14.8,15,0,0,
Inline Weir Flap Gates= 0
IW Outlet Rating Curve= 0 ,False,,

Type RM Length L Ch R = 1 ,12568.1 ,0.1,0.1,0.1
BEGIN DESCRIPTION:
RevEx - Relocated XS to DS side of BR, recut from LiDAR and updated with surve
---------------------------------------------------------------------
CDC FW111809-01 SH121/SOUTHWEST PARKWAY
CROSS-SECTION 12348 - 12568.12
DOWNSTREAM END.
---------------------------------------------------------------------
Copy of cross-section 12568.12.  Modified portion of ineffective flow area.
Channel side slopes from bridge plans.  Concrete paved side slopes.
END DESCRIPTION:
XS GIS Cut Line= 4
 2318175.8498825 6951087.0822236  2318513.444089 6951092.6452324
 2318636.5410854 6951099.68559132319636.145662856951741.98465636
#Sta/Elev= 30
       0  557.68  141.97  555.71   148.4   553.2  194.29  555.08  304.97   555.1
  372.54  550.36  597.78  551.26  623.22  552.52   664.5  551.84  703.38  552.73
   780.5  557.26  947.43  560.09  993.28  558.78 1035.43  549.15 1099.14  551.51
 1111.37   549.6  1142.7  536.86  1154.5   526.8    1292   526.8 1328.92  529.61
  1381.2     551    1391     551  1393.4     555  1398.5     559  1401.6     560
 1473.03  557.72 1590.34  559.85 1650.13  557.38 1816.89  553.44 1957.78  556.67
#Mann= 3 ,0,0
       0    .055       0 1099.14    .023       0  1381.2    .055       0
#XS Ineff= 6 ,-1
       0      72     570      72     163  551.44     200  503.07  551.44
  503.07  982.21     570  982.21 1105.22  551.44 1414.73 1957.85     570
Permanent Ineff=
       F       F       F       F       F       F
Bank Sta=1099.14,1381.2
XS Rating Curve= 0 ,0
Exp/Cntr=0.3,0.1