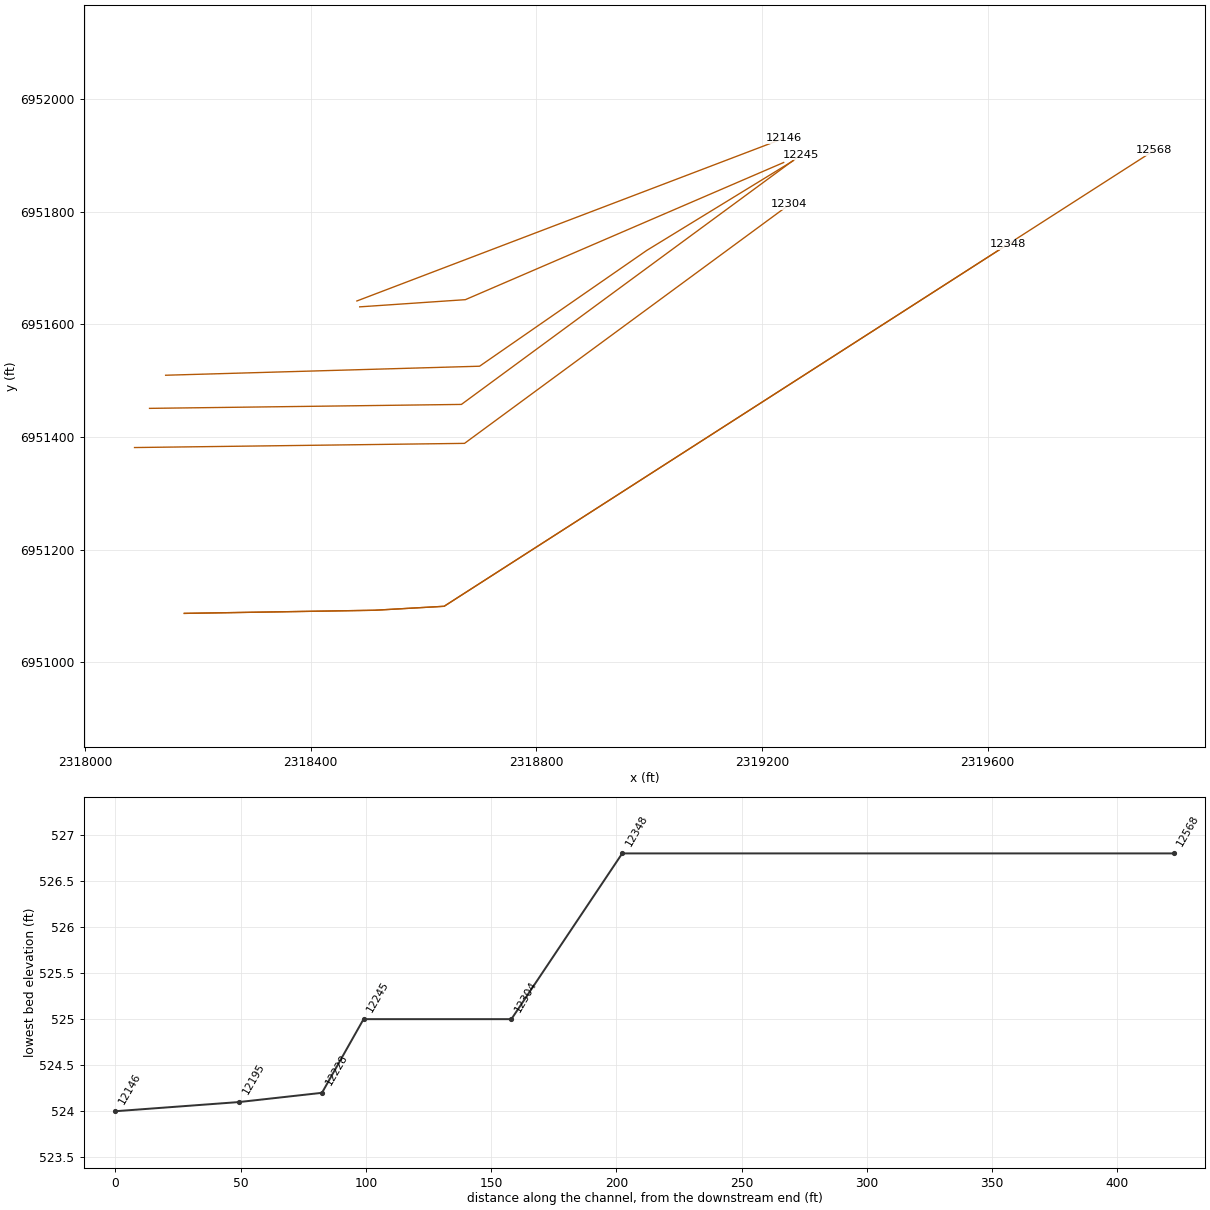
HEC-RAS study CDC_Consolidated_Model.prj: Upper Trinity CDC Consolidated Model

--- CDC_Consolidated_Model.g11 (geometry) --- (continued)

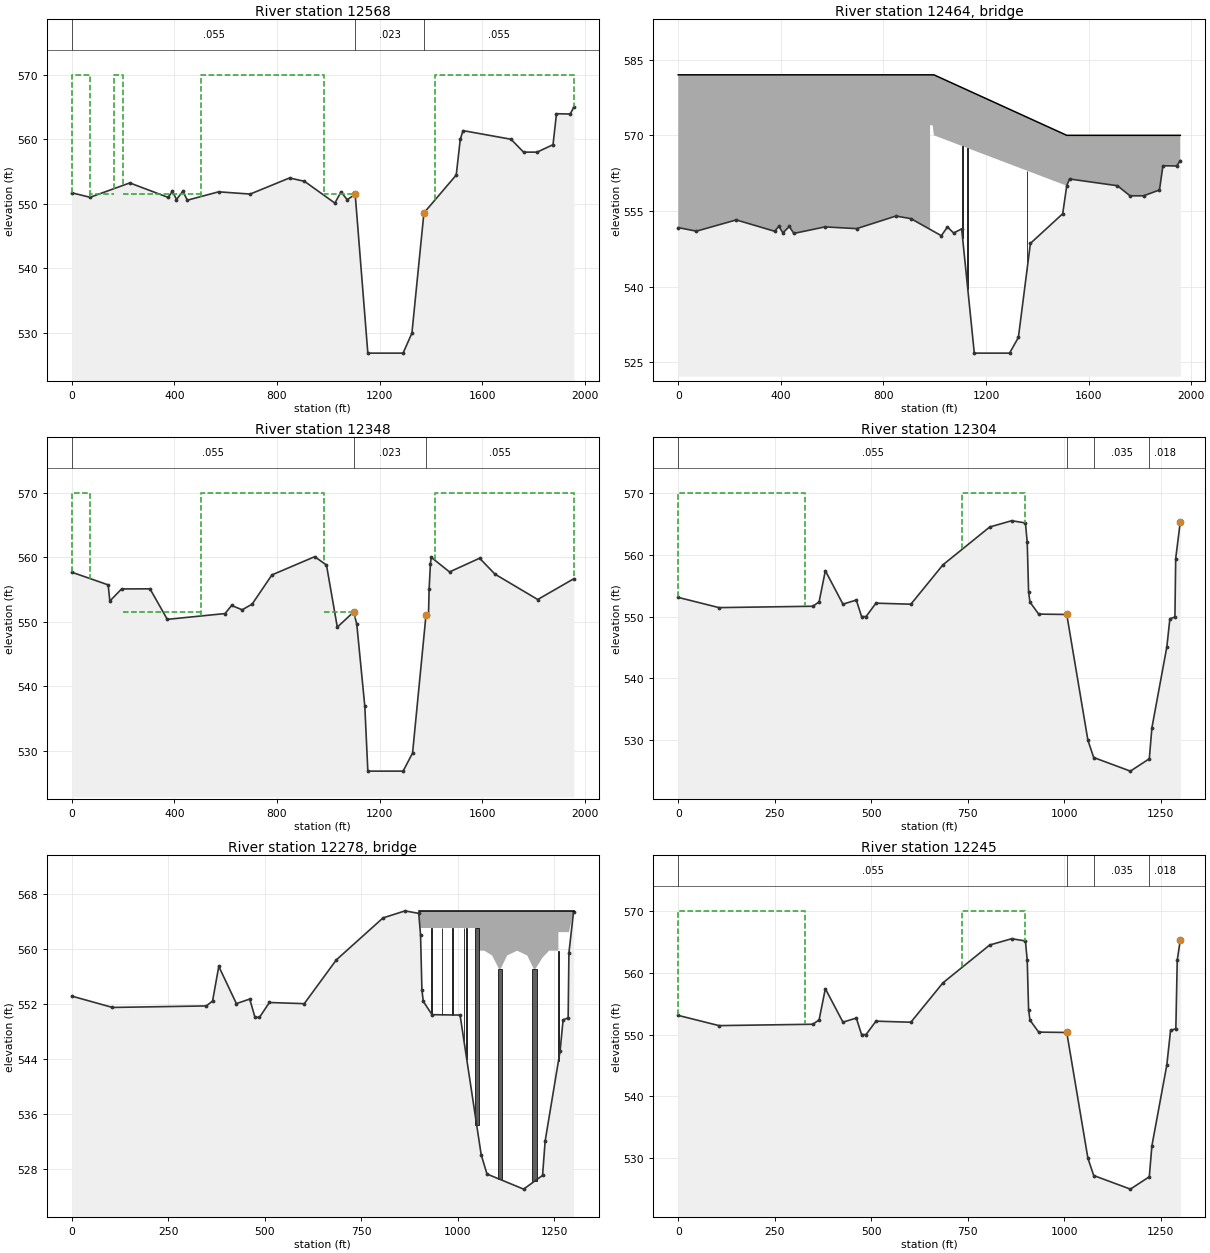
Type RM Length L Ch R = 1 ,12568   ,206.87,220.12,225.9
BEGIN DESCRIPTION:
Upstream of SH121/Southwest Parkway.
---------------------------------------------------------------------
CDC FW111809-01 SH121/SOUTHWEST PARKWAY
CROSS-SECTION 12348 - 12568.12
UPSTREAM END.
---------------------------------------------------------------------
Channel side slopes from bridge plans.  Concrete paved side slopes.
END DESCRIPTION:
XS GIS Cut Line= 4
 2318175.8498825 6951087.0822236  2318513.444089 6951092.6452324
 2318636.5410854 6951099.6855913 2319895.8869056 6951908.8822088
#Sta/Elev= 30
       0  551.69   71.14  550.99  226.28  553.22  376.07  550.97   392.3  551.94
  408.29  550.64  433.05  551.92  450.66  550.54  572.73  551.84   695.7  551.49
  849.07  553.99  907.46  553.47    1026  550.09 1049.85  551.83 1073.85  550.62
 1105.22  551.44  1154.5   526.8    1292   526.8 1326.43  529.91 1373.23  548.56
 1499.26  554.45    1515     560  1525.8  561.34 1712.87     560 1761.76     558
 1814.62     558 1876.67  559.16 1890.11  563.96 1943.69  563.92 1957.85  564.99
#Mann= 3 ,0,0
       0    .055       0 1105.22    .023       0 1373.23    .055       0
#XS Ineff= 7 ,-1
       0      72     570      72     163  551.44     163     200     570
     200  503.07  551.44  503.07  982.21     570  982.21 1105.22  551.44
 1414.73 1957.85     570
Permanent Ineff=
       F       F       F       F       F       F       F
Bank Sta=1105.22,1373.23
XS Rating Curve= 0 ,0
Exp/Cntr=0.3,0.1

Type RM Length L Ch R = 3 ,12464   ,,,
BEGIN DESCRIPTION:
SH 121/Southwest Parkway
Data from bridge plans.  Concrete paved side slopes.  12-foot bike trail on right side slope.
END DESCRIPTION:
Node Name=SH 121/Southwest
Bridge Culvert--1,0,-1,-1, 0
Deck Dist Width WeirC Skew NumUp NumDn MinLoCord MaxHiCord MaxSubmerge Is_Ogee
1,206,2.6,0, 8, 8, , , 0.98, 0, 0,0,,
       0     982     982     992     997    1515    1515 1957.85
     582     582     582     582     582     570     570     570
     520     520     572     572     570     560     520     520
       0     982     982     992     997    1515    1515 1957.85
     582     582     582     582     582     570     570     570
     520     520     572     572     570     560     520     520
Pier Skew, UpSta & Num, DnSta & Num=  ,1109, 2 ,1109, 2 , 0 , 0 , 0 ,,
    3.25    3.25
     500     575
    3.25    3.25
     500     575
Pier Skew, UpSta & Num, DnSta & Num=  ,1129, 2 ,1129, 2 , 0 , 0 , 0 ,,
    3.25    3.25
     500     575
    3.25    3.25
     500     575
Pier Skew, UpSta & Num, DnSta & Num=  ,1360, 2 ,1360, 2 , 0 , 0 , 0 ,,
    3.25    3.25
     500     575
    3.25    3.25
     500     575
BR Coef=-1 , 0 , 0 ,, 0 ,,,0.8,-1,,0,
WSPro=,,,, 1 ,,,, 0 ,,,, 0 ,,,,-1 ,-1 ,-1 , 0 , 0 , 0 , 0 , 0
BC Design=,, 0 ,, 0 ,,,,,,
BC Use User HTab Curves=0
BC User HTab FreeFlow(D)= 0

Type RM Length L Ch R = 1 ,12348   ,38.74,44.25,48.54
BEGIN DESCRIPTION:
Downstream of SH121/Southwest Parkway.
RevEx - Relocated XS to DS side of BR, recut from LiDAR and updated with surve
---------------------------------------------------------------------
CDC FW111809-01 SH121/SOUTHWEST PARKWAY
CROSS-SECTION 12348 - 12568.12
DOWNSTREAM END.
---------------------------------------------------------------------
Copy of cross-section 12568.12.  Modified portion of ineffective flow area.
Channel side slopes from bridge plans.  Concrete paved side slopes.
END DESCRIPTION:
XS GIS Cut Line= 4
  2318175.849882 6951087.0822236  2318513.444089 6951092.6452324
 2318636.5410854 6951099.6855913 2319636.1456629 6951741.9846564
#Sta/Elev= 30
       0  557.68  141.97  555.71   148.4   553.2  194.29  555.08  304.97   555.1
  372.54  550.36  597.78  551.26  623.22  552.52   664.5  551.84  703.38  552.73
   780.5  557.26  947.43  560.09  993.28  558.78 1035.43  549.15 1099.14  551.51
 1111.37   549.6  1142.7  536.86  1154.5   526.8    1292   526.8 1328.92  529.61
  1381.2     551    1391     551  1393.4     555  1398.5     559  1401.6     560
 1473.03  557.72 1590.34  559.85 1650.13  557.38 1816.89  553.44 1957.78  556.67
#Mann= 3 ,0,0
       0    .055       0 1099.14    .023       0  1381.2    .055       0
#XS Ineff= 6 ,-1
       0      72     570      72     163  551.44     200  503.07  551.44
  503.07  982.21     570  982.21 1105.22  551.44 1414.73 1957.85     570
Permanent Ineff=
       F       F       F       F       F       F
Bank Sta=1099.14,1381.2
XS Rating Curve= 0 ,0
Exp/Cntr=0.3,0.1

Type RM Length L Ch R = 1 ,12304   ,59,59,59
BEGIN DESCRIPTION:
Upstream of Vickery Boulevard.
Copy of cross-section 12244.75
END DESCRIPTION:
XS GIS Cut Line= 3
 2318087.6374574 6951381.3279494 2318672.7053095 6951388.7389422
 2319248.7763257 6951812.5790409
#Sta/Elev= 30
       0  553.09  105.53  551.44  348.79  551.66  364.84  552.38  380.99  557.41
   426.6     552   461.2  552.66   474.8     550  486.47     550  512.09  552.16
  602.48  551.99  685.58  558.36  806.59  564.47  863.51  565.49   899.2  565.13
  903.84     562   907.4     554   910.9  552.33  933.51  550.39 1006.24  550.33
    1061     530    1076   527.2    1171     525    1220     527 1226.73     532
 1265.39  545.08 1273.29  549.63 1286.36  549.93 1288.36  559.38 1300.31  565.36
#Mann= 4 ,-1,0
       0    .055       0 1006.24    .018       0    1076    .035       0
    1220    .018       0
#XS Ineff= 4 ,-1
       0     329     570     329     735  550.33     735   899.3     570
   899.3 1006.24  550.33
Permanent Ineff=
       F       F       F       F
Bank Sta=1006.24,1300.31
XS Rating Curve= 0 ,0
Exp/Cntr=0.5,0.3

Type RM Length L Ch R = 3 ,12278   ,,,
BEGIN DESCRIPTION:
Vickery Boulevard
Bridge data from USACE 1975 survey, Fort Worth Floodway as-built plans.
END DESCRIPTION:
Node Name=Vickery Blvd.
Bridge Culvert--1,0,-1,-1, 0
Deck Dist Width WeirC Skew NumUp NumDn MinLoCord MaxHiCord MaxSubmerge Is_Ogee
1,50,2.6,0, 18, 18, , , 0.95, 0, 0,0,,
   899.3   899.3  1049.3  1049.3  1069.3  1089.3 1107.55 1111.05  1128.3  1154.3
  1180.3 1197.55 1201.05 1220.05 1237.05 1261.05 1261.05  1301.1
   565.5   565.5   565.5   565.5   565.5   565.5   565.5   565.5   565.5   565.5
   565.5   565.5   565.5   565.5   565.5   565.5   565.5   565.5
     450     563     563   559.7   559.7     559     557     557     559   559.7
     559     557     557   558.7   559.7   559.7   562.4   562.4
   899.3   899.3  1049.3  1049.3  1069.3  1089.3 1107.55 1111.05  1128.3  1154.3
  1180.3 1197.55 1201.05 1220.05 1237.05 1261.05 1261.05  1301.1
   565.5   565.5   565.5   565.5   565.5   565.5   565.5   565.5   565.5   565.5
   565.5   565.5   565.5   565.5   565.5   565.5   565.5   565.5
     450     563     563   559.7   559.7     559     557     557     559   559.7
     559     557     557   558.7   559.7   559.7   562.4   562.4
Pier Skew, UpSta & Num, DnSta & Num=  ,932.2, 2 ,932.2, 2 , 0 , 0 , 0 ,,
     1.5     1.5
     450     564
     1.5     1.5
     450     564
Pier Skew, UpSta & Num, DnSta & Num=  ,959.3, 2 ,959.3, 2 , 0 , 0 , 0 ,,
     1.5     1.5
     450     564
     1.5     1.5
     450     564
Pier Skew, UpSta & Num, DnSta & Num=  ,987.3, 2 ,987.3, 2 , 0 , 0 , 0 ,,
     1.5     1.5
     450     564
     1.5     1.5
     450     564
Pier Skew, UpSta & Num, DnSta & Num=  ,1016.3, 2 ,1016.3, 2 , 0 , 0 , 0 ,,
     1.5     1.5
     450     564
     1.5     1.5
     450     564
Pier Skew, UpSta & Num, DnSta & Num=  ,1023.3, 2 ,1023.3, 2 , 0 , 0 , 0 ,,
     1.5     1.5
     450     564
     1.5     1.5
     450     564
Pier Skew, UpSta & Num, DnSta & Num=  ,1049.3, 4 ,1049.3, 4 , 0 , 0 , 0 ,,
      10      10       5       5
     450   543.2   543.2     564
      10      10       5       5
     450   543.2   543.2     564
Pier Skew, UpSta & Num, DnSta & Num=  ,1109.3, 5 ,1109.3, 5 , 0 , 0 , 0 ,,
      12      12       8       4     3.5
     450     536     537     537     557
      12      12       8       4     3.5
     450     536     537     537     557
Pier Skew, UpSta & Num, DnSta & Num=  ,1199.3, 5 ,1199.3, 5 , 0 , 0 , 0 ,,
      12      12       8       4     3.5
     450     536     537     537     557
      12      12       8       4     3.5
     450     536     537     537     557
Pier Skew, UpSta & Num, DnSta & Num=  ,1261.05, 2 ,1261.05, 2 , 0 , 0 , 0 ,,
       3       3
     450     563
       3       3
     450     563
BR Coef=-1 , 0 , 0 ,, 0 ,,,0.8,-1,,0,
WSPro=,,,, 1 ,,,, 0 ,,,, 0 ,,,,-1 ,-1 ,-1 , 0 , 0 , 0 , 0 , 0
BC Design=,, 0 ,, 0 ,,,,,,
BC Use User HTab Curves=0
BC User HTab FreeFlow(D)= 0

Type RM Length L Ch R = 1 ,12245   ,27.1,16.6,4.9
BEGIN DESCRIPTION:
Downstream of Vickery Boulevard.
Added cross-section from ground points generated through centerline of Vickery Boulevard roadway and bridge.
END DESCRIPTION:
XS GIS Cut Line= 4
 2318114.2387045 6951450.8396317   2318667.18547 6951457.8435625
 2319243.2615283 6951881.6873511 2319269.1335925  6951900.722535
#Sta/Elev= 30
       0  553.09  105.53  551.44  348.79  551.66  364.84  552.38  380.99  557.41
   426.6     552   461.2  552.66   474.8     550  486.47     550  512.09  552.16
  602.48  551.99  685.58  558.36  806.59  564.47  863.51  565.49   899.2  565.13
  903.84     562   907.4     554   910.9  552.33  933.51  550.39 1006.24  550.33
    1061     530    1076   527.2    1171     525    1220     527 1226.73     532
 1265.39  545.08 1275.06  550.66 1288.73  550.94 1292.38     562 1300.31  565.36
#Mann= 4 ,-1,0
       0    .055       0 1006.24    .018       0    1076    .035       0
    1220    .018       0
#XS Ineff= 4 ,-1
       0     329     570     329     735  550.33     735   899.3     570
   899.3 1006.24  550.33
Permanent Ineff=
       F       F       F       F
Bank Sta=1006.24,1300.31
XS Rating Curve= 0 ,0
Exp/Cntr=0.5,0.3

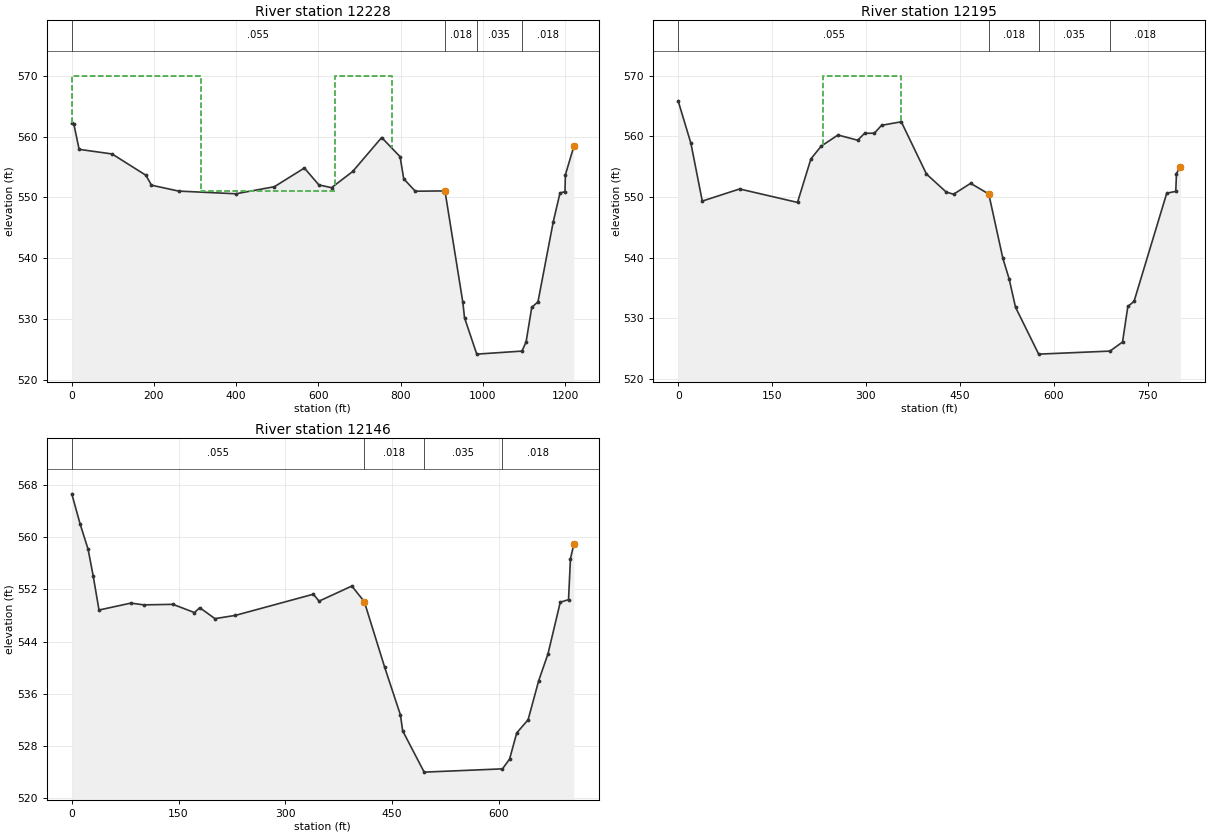
Type RM Length L Ch R = 1 ,12228   ,60.6,33,13.2
BEGIN DESCRIPTION:
This cross section corresponds to cross section 12228.18 of the non-georeferenced CDC model which was the source of this model.
END DESCRIPTION:
XS GIS Cut Line= 5
 2318142.7654589  6951509.620043 2318699.4036551   6951525.62562
  2318995.905853 6951731.1550193  2319216.822207 6951866.5175384
 2319254.7147512 6951889.7355127
#Sta/Elev= 30
       0  562.21    5.18     562   17.93   557.9   98.09  557.14  180.21  553.64
  193.92     552  260.12  551.03  399.27  550.59  492.77  551.75  565.73  554.83
  601.01  552.05  631.79  551.59   683.3  554.26  753.79  559.85  798.57  556.69
  807.36  553.05  835.57  551.01   907.7  551.06  951.15  532.74  955.27  530.19
     985   524.2    1095   524.7    1105   526.2 1118.78   531.9 1133.89   532.8
 1171.16     546 1187.46  550.71  1199.6  550.94 1200.64  553.72 1221.17   558.4
#Mann= 4 ,-1,0
       0    .055       0   907.7    .018       0     985    .035       0
    1095    .018       0
#XS Ineff= 4 ,-1
       0  315.47     570  315.47  639.86  551.06  639.86  778.58     570
  778.58   907.7  551.06
Permanent Ineff=
       F       F       F       F
Bank Sta=907.7,1221.17
XS Rating Curve= 0 ,0
Exp/Cntr=0.3,0.1

Type RM Length L Ch R = 1 ,12195   ,56.5,49.5,44.4
BEGIN DESCRIPTION:
This cross section corresponds to cross section 12195.16 of the non-georeferenced CDC model which was the source of this model.
END DESCRIPTION:
XS GIS Cut Line= 4
 2318486.8607319 6951630.9371151 2318674.2212916 6951643.7060301
 2319216.5305218 6951877.5712053 2319238.5227554 6951887.0551257
#Sta/Elev= 30
       0  565.82   20.26  558.87   38.41  549.34   98.08  551.34  190.59  549.12
  212.02   556.3  228.31  558.39  255.26  560.24  286.79  559.38  297.83  560.52
  313.48  560.54  324.91  561.84  356.44  562.42  396.69   553.8  428.14  550.84
  439.98  550.47  467.23  552.27  496.25  550.51  518.68  539.94  528.83  536.49
  538.97  531.84     576   524.1     690   524.6     710   526.1  718.46  531.96
  728.43  532.81  780.67  550.65  795.05  550.94  796.21  553.88  802.33  555.03
#Mann= 4 ,-1,0
       0    .055       0  496.25    .018       0     576    .035       0
     690    .018       0
#XS Ineff= 3 ,-1
       0  230.81  550.51  230.81  356.44     570  356.44  496.25  550.51
Permanent Ineff=
       F       F       F
Bank Sta=496.25,802.33
XS Rating Curve= 0 ,0
Exp/Cntr=0.3,0.1

Type RM Length L Ch R = 1 ,12146   ,136.1,135.1,135.2
BEGIN DESCRIPTION:
Upstream of IH 30.
Copy of cross-section 12010.59
END DESCRIPTION:
XS GIS Cut Line= 2
  2318481.854387 6951641.3820168 2319238.8104213 6951929.9597273
#Sta/Elev= 30
       0  566.61   11.71     562   22.94  558.12   30.15     554   38.26  548.82
   83.06  549.88  101.09  549.61  142.12  549.69  172.36  548.43  179.78  549.18
  201.12   547.5   229.8     548  339.33  551.24  347.34  550.18  393.43  552.49
  410.91   550.1  439.64  540.02  461.69  532.75  464.79  530.33     495     524
     605   524.5     615     526     625     530  640.99  532.02  655.88     538
  668.93  542.11  686.19  550.02  697.77   550.4  700.49  556.69  705.25  558.91
#Mann= 4 ,-1,0
       0    .055       0  410.91    .018       0     495    .035       0
     605    .018       0
#XS Ineff= 2 , 0
          410.91   550.1
Permanent Ineff=
       F       F
Bank Sta=410.91,705.25
XS Rating Curve= 0 ,0
Exp/Cntr=0.5,0.3