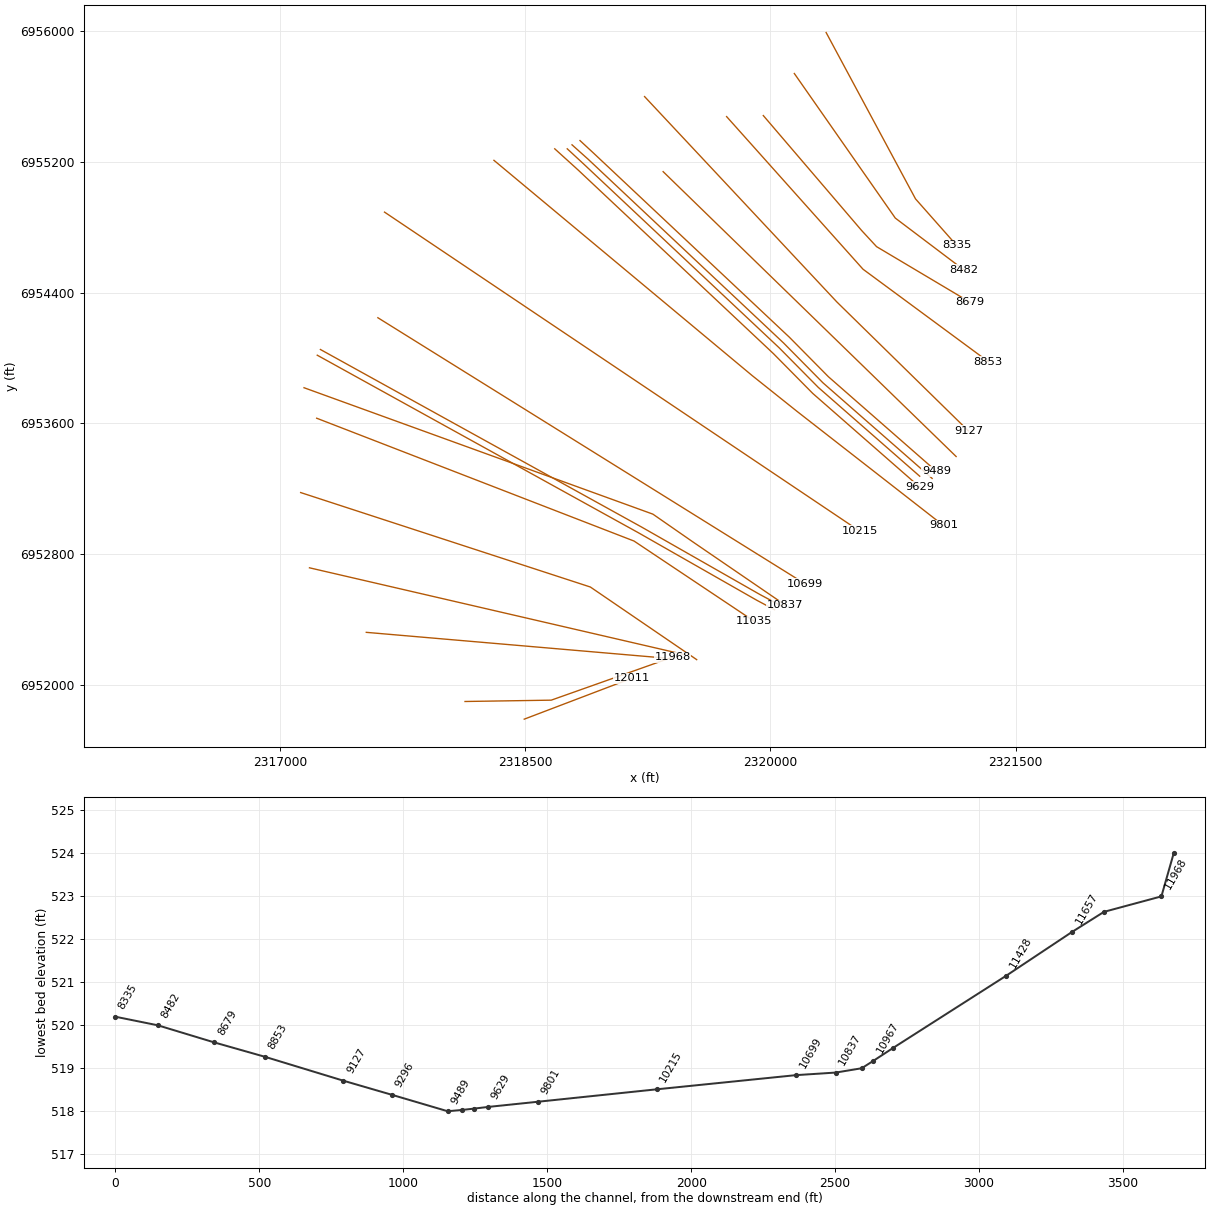
HEC-RAS study CDC_Consolidated_Model.prj: Upper Trinity CDC Consolidated Model

--- CDC_Consolidated_Model.g11 (geometry) --- (continued)

Type RM Length L Ch R = 3 ,12079   ,,,
BEGIN DESCRIPTION:
IH 30
Bridge data from USACE 1975 survey.  Double bridges - total bridge width set at 130 feet.
END DESCRIPTION:
Node Name=IH 30
Bridge Culvert--1,0,-1,-1, 0
Deck Dist Width WeirC Skew NumUp NumDn MinLoCord MaxHiCord MaxSubmerge Is_Ogee
2,130,2.6,0, 7, 7, , , 0.95, 0, 0,0,,
       0      12      12     300     698     698  705.25
     574     574     574     574     568     568     568
     450     450  565.15   563.2   560.8     450     450
       0      12      12     300     698     698  705.25
     574     574     574     574     568     568     568
     450     450  565.15   563.2   560.8     450     450
Pier Skew, UpSta & Num, DnSta & Num=  ,54, 2 ,54, 2 , 0 , 0 , 0 ,,
     2.5     2.5
     450     570
     2.5     2.5
     450     570
Pier Skew, UpSta & Num, DnSta & Num=  ,110, 2 ,110, 2 , 0 , 0 , 0 ,,
     2.5     2.5
     450     570
     2.5     2.5
     450     570
Pier Skew, UpSta & Num, DnSta & Num=  ,163, 2 ,163, 2 , 0 , 0 , 0 ,,
     2.5     2.5
     450     570
     2.5     2.5
     450     570
Pier Skew, UpSta & Num, DnSta & Num=  ,203, 2 ,203, 2 , 0 , 0 , 0 ,,
     2.5     2.5
     450     570
     2.5     2.5
     450     570
Pier Skew, UpSta & Num, DnSta & Num=  ,241, 2 ,241, 2 , 0 , 0 , 0 ,,
     2.5     2.5
     450     570
     2.5     2.5
     450     570
Pier Skew, UpSta & Num, DnSta & Num=  ,279, 2 ,279, 2 , 0 , 0 , 0 ,,
     2.5     2.5
     450     570
     2.5     2.5
     450     570
Pier Skew, UpSta & Num, DnSta & Num=  ,328, 2 ,328, 2 , 0 , 0 , 0 ,,
     2.5     2.5
     450     570
     2.5     2.5
     450     570
Pier Skew, UpSta & Num, DnSta & Num=  ,378, 2 ,378, 2 , 0 , 0 , 0 ,,
     2.5     2.5
     450     570
     2.5     2.5
     450     570
Pier Skew, UpSta & Num, DnSta & Num=  ,428, 2 ,428, 2 , 0 , 0 , 0 ,,
     2.5     2.5
     450     570
     2.5     2.5
     450     570
Pier Skew, UpSta & Num, DnSta & Num=  ,499, 2 ,499, 2 , 0 , 0 , 0 ,,
     2.5     2.5
     450     570
     2.5     2.5
     450     570
Pier Skew, UpSta & Num, DnSta & Num=  ,588, 2 ,588, 2 , 0 , 0 , 0 ,,
     2.5     2.5
     450     570
     2.5     2.5
     450     570
Pier Skew, UpSta & Num, DnSta & Num=  ,658, 2 ,658, 2 , 0 , 0 , 0 ,,
     2.5     2.5
     450     570
     2.5     2.5
     450     570
BR Coef=-1 , 0 , 0 ,, 0 ,,,0.8,-1,,0,
WSPro=,,,, 1 ,,,, 0 ,,,, 0 ,,,,-1 ,-1 ,-1 , 0 , 0 , 0 , 0 , 0
BC Design=,, 0 ,, 0 ,,,,,,
BC Use User HTab Curves=0
BC User HTab FreeFlow(D)= 0

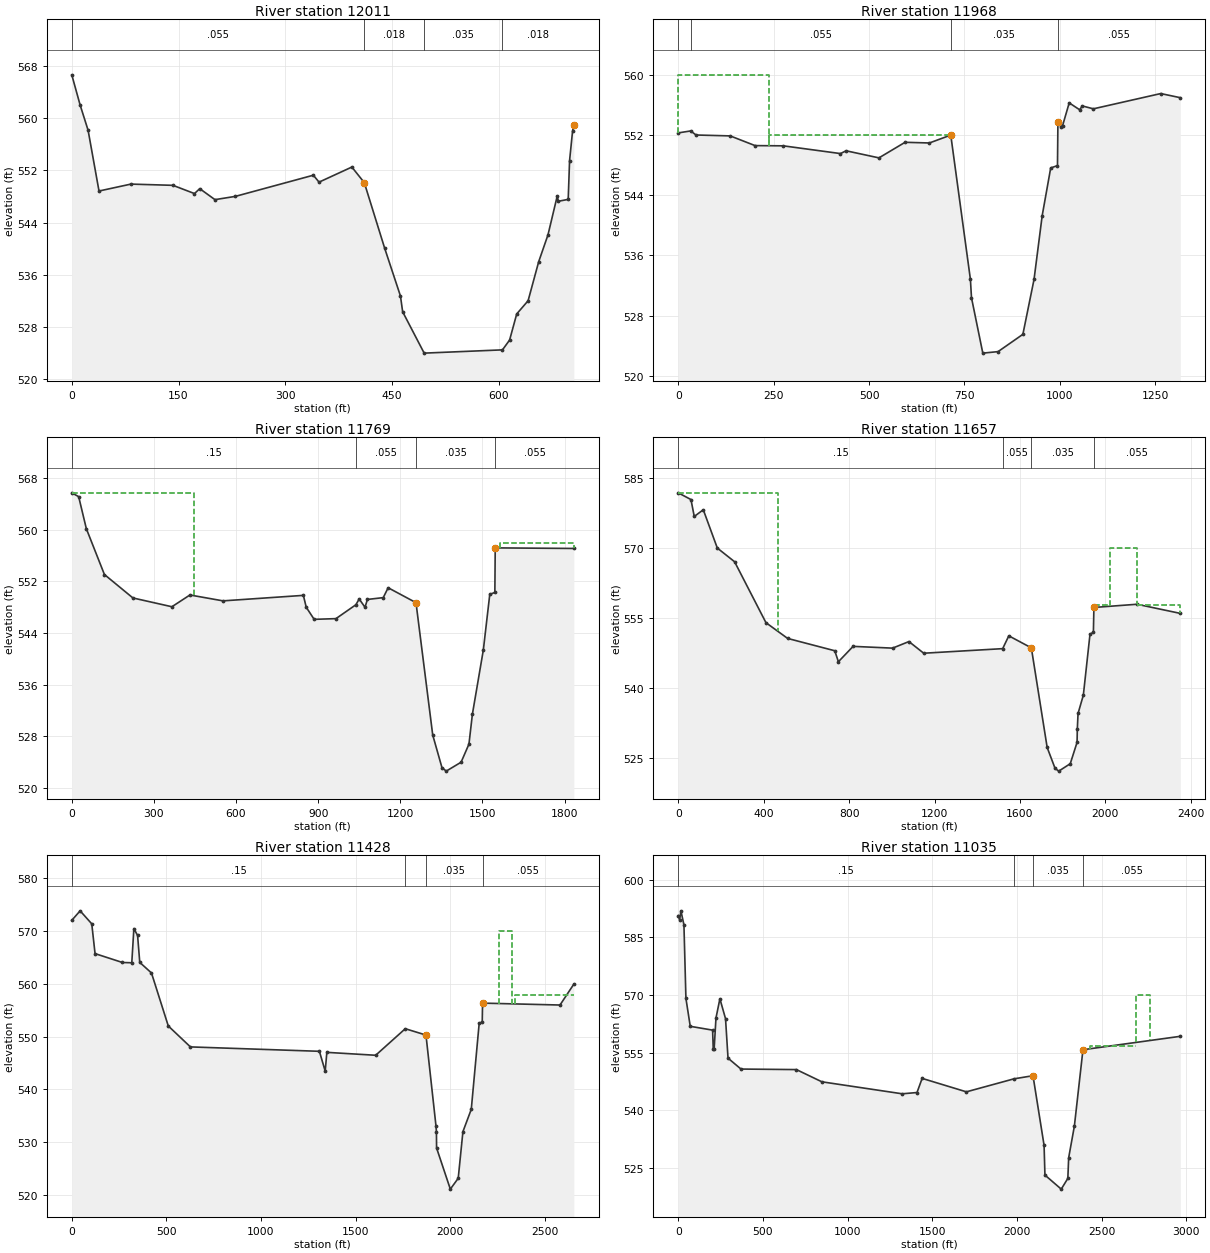
Type RM Length L Ch R = 1 ,12011   ,47.2,42.6,39.2
BEGIN DESCRIPTION:
Downstream of IH 30.
Added cross-section from ground points generated through centerline of IH 30 bridge.
END DESCRIPTION:
XS GIS Cut Line= 2
 2318492.6729042 6951788.7952679   2319151.78703 6952039.6781495
#Sta/Elev= 30
       0  566.61   11.71     562   22.94  558.12   38.26  548.82   83.06  549.88
  142.12  549.69  172.36  548.43  179.78  549.18  201.12   547.5   229.8     548
  339.33  551.24  347.34  550.18  393.43  552.49  410.91   550.1  439.64  540.02
  461.69  532.75  464.79  530.33     495     524     605   524.5     615     526
     625     530  640.99  532.02  655.88     538  668.93  542.11     682  548.09
   683.4  547.25  697.33  547.54  699.26  553.49  703.47     558  705.25  558.91
#Mann= 4 ,-1,0
       0    .055       0  410.91    .018       0     495    .035       0
     605    .018       0
#XS Ineff= 2 , 0
          410.91   550.1
Permanent Ineff=
       F       F
Bank Sta=410.91,705.25
XS Rating Curve= 0 ,0
Exp/Cntr=0.5,0.3

Type RM Length L Ch R = 1 ,11968   ,296.8,199.4,135.6
BEGIN DESCRIPTION:
This cross section corresponds to cross section 11968.02 of the non-georeferenced CDC model which was the source of this model.
END DESCRIPTION:
XS GIS Cut Line= 4
 2318130.2204281 6951896.9267698 2318658.0279994 6951905.1023652
 2319268.5432429 6952121.3835267 2319400.4316943 6952168.1063362
#Sta/Elev= 30
       0  552.28   32.62  552.54   46.62     552  136.17  551.88  201.32  550.59
   275.2  550.56  425.08  549.53  439.81   549.9  525.88  548.96  594.33  551.03
  658.08  550.94  714.06  551.99  765.49  532.82  768.36  530.36     798     523
     838   523.2     903   525.5  932.24   532.8  953.63  541.29  975.89  547.62
  993.67  547.93  994.81  553.79 1002.48   553.1 1007.13  553.26 1024.38  556.27
 1051.58  555.36 1058.93  555.86 1087.72  555.48 1264.26  557.51 1315.48  556.96
#Mann= 4 ,-1,0
       0     .15       0   32.62    .055       0  714.06    .035       0
  994.81    .055       0
#XS Ineff= 3 ,-1
       0  236.65     560  236.65  714.06  551.99 1024.38 1315.48  556.27
Permanent Ineff=
       F       F       F
Bank Sta=714.06,994.81
XS Rating Curve= 0 ,0
Exp/Cntr=0.3,0.1

Type RM Length L Ch R = 1 ,11769   ,164.1,111.5,91.3
BEGIN DESCRIPTION:
Trinity Park in LOB.
END DESCRIPTION:
XS GIS Cut Line= 2
 2317525.8898544 6952320.1670954 2319353.2404957 6952162.8628841
#Sta/Elev= 30
       0  565.71   25.18  565.12   53.22  560.16  119.22  553.07  223.36  549.44
  365.73  548.08   431.7   549.9  552.47  548.99  846.07  549.84   856.5     548
  885.46  546.13   965.1  546.24 1037.92  548.39 1049.88  549.28  1071.3     548
  1079.9  549.21 1137.85  549.49 1155.73  551.02 1257.49  548.71 1318.59  528.23
  1352.2   523.2 1367.88  522.64 1422.23  524.02 1450.92  526.82 1463.59  531.47
 1503.49  541.39 1527.01     550 1545.56  550.29 1546.93  557.19 1834.11   557.1
#Mann= 4 ,-1,0
       0     .15       0 1037.92    .055       0 1257.49    .035       0
 1546.93    .055       0
#XS Ineff= 3 ,-1
       0  448.15 565.709  448.15 1257.49  548.71 1565.26 1834.11  557.91
Permanent Ineff=
       F       F       F
Bank Sta=1257.49,1546.93
XS Rating Curve= 0 ,0
Exp/Cntr=0.3,0.1

Type RM Length L Ch R = 1 ,11657   ,300.1,228.9,172
BEGIN DESCRIPTION:
Trinity Park in LOB.
END DESCRIPTION:
XS GIS Cut Line= 3
  2317178.170303 6952715.1799998  2319067.700578 6952277.7505465
2319468.354562286952184.99847171
#Sta/Elev= 30
       0  581.84   59.53   580.4   75.03  576.77  117.28  578.21  182.96     570
  263.92  567.06   410.7     554  512.34  550.62  732.83  547.98   749.9  545.62
  818.72  548.92 1003.52  548.54 1080.15  549.95 1149.36  547.45 1519.11  548.43
 1547.75  551.18 1653.28   548.6 1727.33  527.25 1764.37  522.76 1781.65  522.17
 1835.45  523.76 1867.38  528.35  1868.5  531.14 1871.95  534.53 1896.71  538.45
  1927.8  551.48 1943.82  551.96  1946.2  557.26 2148.02  557.95 2350.75  555.99
#Mann= 4 ,-1,0
       0     .15       0 1519.11    .055       0 1653.28    .035       0
  1946.2    .055       0
#XS Ineff= 5 ,-1
       0  466.54 581.836  466.54 1653.28   548.6 1954.92 2023.76  557.72
 2023.76  2148.4     570  2148.4 2374.72  557.72
Permanent Ineff=
       F       F       F       F       F
Bank Sta=1653.28,1946.2
XS Rating Curve= 0 ,0
Exp/Cntr=0.3,0.1

Type RM Length L Ch R = 1 ,11428   ,374.2,392.7,397.7
BEGIN DESCRIPTION:
Trinity Park in LOB.
END DESCRIPTION:
XS GIS Cut Line= 4
 2317124.1707968 6953175.7743634 2318897.4349452 6952597.6177512
 2319228.7571247 6952371.34891532319548.251164246952153.15783462
#Sta/Elev= 30
       0  571.97    44.2  573.77   105.6  571.31  123.05  565.68  267.95     564
  317.15  563.95   328.2  570.41  347.82  569.12  359.32  564.02  421.23  562.02
  510.05     552  627.01  548.04 1308.57  547.21 1339.29  543.46 1347.97  547.01
 1605.99  546.46 1762.47  551.48 1871.82  550.28 1924.47  533.17 1927.06     532
 1927.85  528.93  2000.5  521.15 2042.23   523.2 2067.06  532.02 2111.23  536.24
 2152.91  552.47 2169.15  552.79 2170.85  556.32 2580.09  555.96 2653.24  559.91
#Mann= 4 ,-1,0
       0     .15       0 1762.47    .055       0 1871.82    .035       0
 2170.85    .055       0
#XS Ineff= 3 ,-1
       0 1871.82  550.28 2255.38 2325.21     570  2344.6 2657.92  557.78
Permanent Ineff=
       F       F       F
Bank Sta=1871.82,2170.85
XS Rating Curve= 0 ,0
Exp/Cntr=0.3,0.1

Type RM Length L Ch R = 1 ,11035   ,112,68.5,80
BEGIN DESCRIPTION:
Trinity Park in LOB.
END DESCRIPTION:
XS GIS Cut Line= 6
 2317222.2500694 6953630.8197191 2319164.9093393 6952878.9182549
 2319536.5932442 6952630.7375079 2319876.3871487 6952403.8503494
 2319895.6896152 6952390.96170812319898.384139436952389.16252059
#Sta/Elev= 30
       0  590.65    8.28  589.54    15.8   591.9   33.67  588.25   45.41   569.1
   70.93  561.84  202.98  560.85  206.66     556  212.11     556  222.89     564
  246.03  569.01  279.33  563.83  293.98  553.56  370.49  550.72  697.91  550.58
  848.37   547.4 1322.68  544.28 1410.03  544.61 1440.45  548.29  1701.7  544.79
 1982.33  548.17 2095.08  548.99 2160.52  530.86 2165.56  523.13 2261.86  519.47
 2300.84  522.26 2305.72  527.63 2339.42  535.86 2390.14  555.75 2965.05  559.24
#Mann= 4 ,-1,0
       0     .15       0 1982.33    .055       0 2095.08    .035       0
 2390.14    .055       0
#XS Ineff= 4 ,-1
       0 2095.08  548.99 2433.28 2702.62  556.61 2702.62 2787.14     570
 2787.14 2975.58  556.61
Permanent Ineff=
       F       F       F       F
Bank Sta=2095.08,2390.14
XS Rating Curve= 0 ,0
Exp/Cntr=0.3,0.1

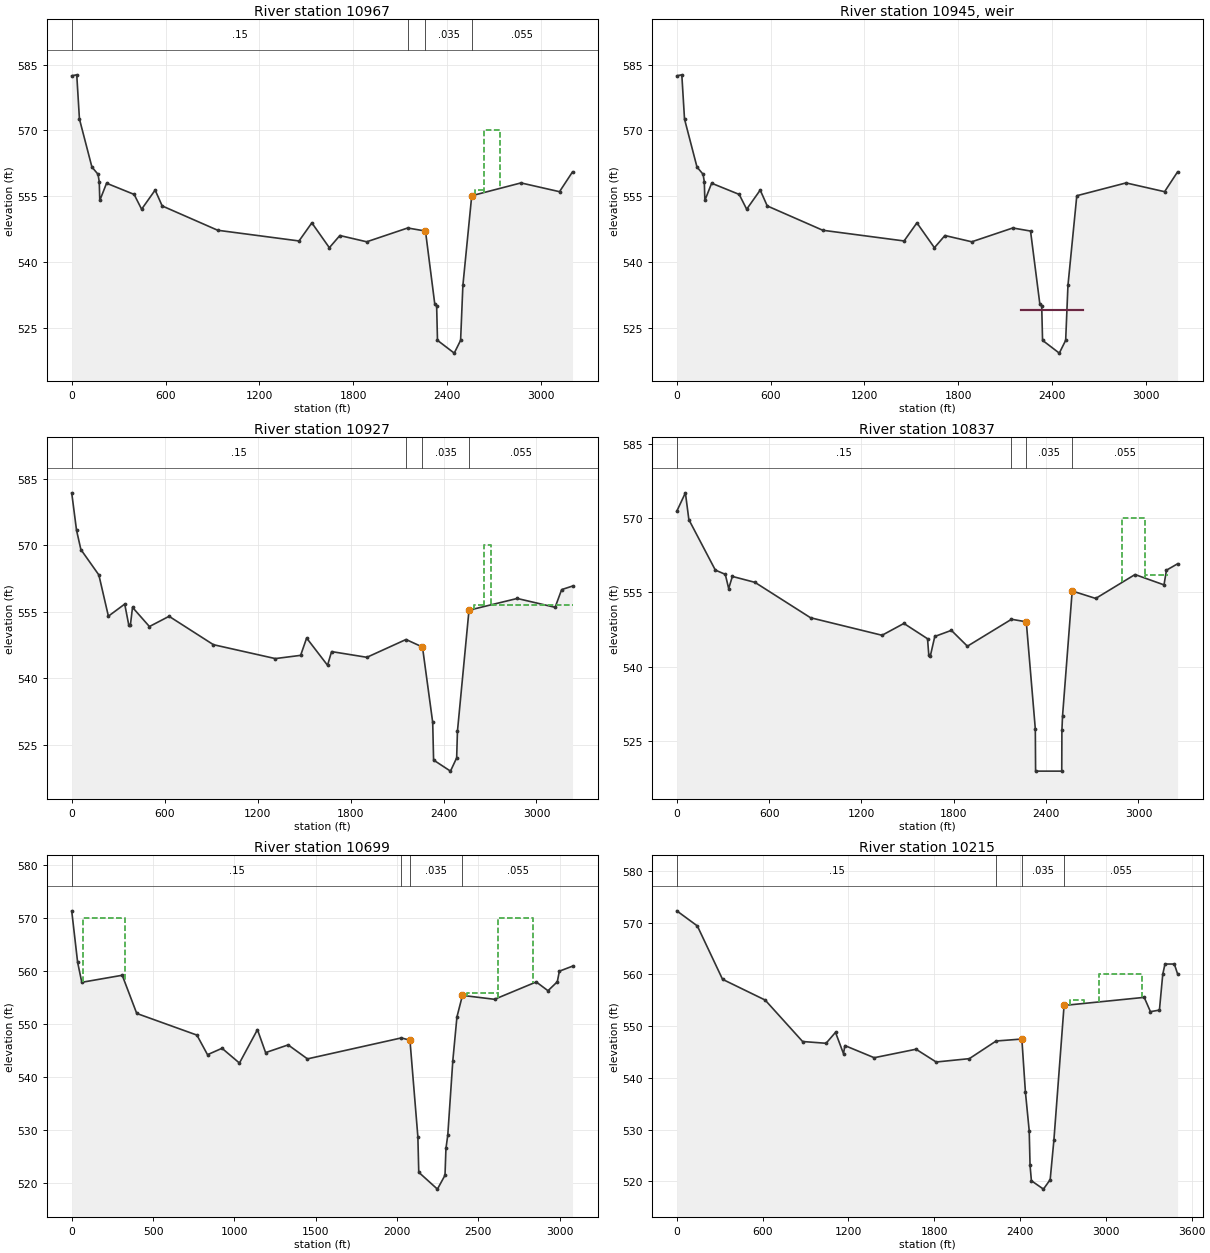
Type RM Length L Ch R = 1 ,10967   ,40,40,40.3
BEGIN DESCRIPTION:
Upstream of Trinity Park channel dam.
Trinity Park in LOB.
END DESCRIPTION:
XS GIS Cut Line= 6
 2317225.8276783 6954016.4661771 2319192.1408844 6952929.4019893
 2319916.0681097 6952516.6554387 2319957.5397197 6952494.4950087
  2319974.306162 6952485.53582982320025.002336576952458.44623707
#Sta/Elev= 30
       0  582.45   32.26  582.66   49.52  572.57  129.25  561.63   168.4  559.97
  176.16  558.26  179.68     554  223.01  557.93  399.27  555.38   447.2     552
  533.73  556.37  578.78  552.75  934.01   547.2 1454.12  544.76  1536.1  548.89
 1648.12  543.22 1715.36     546 1887.12  544.57 2149.34  547.72 2263.02  547.02
 2322.46   530.4 2334.47     530 2339.85  522.09 2447.03  519.17 2487.77  522.09
 2502.33   534.6 2558.96  555.08 2873.96     558 3120.53     556 3203.63  560.52
#Mann= 4 ,-1,0
       0     .15       0 2149.34    .055       0 2263.02    .035       0
 2558.96    .055       0
#XS Ineff= 5 ,-1
       0 2263.02  547.02 2263.02 2558.96     529 2581.56 2634.71  556.32
 2634.71 2737.69     570 2737.69 3240.85  556.32
Permanent Ineff=
       F       T       F       F       F
Bank Sta=2263.02,2558.96
XS Rating Curve= 0 ,0
Exp/Cntr=0.3,0.1

Type RM Length L Ch R = 5 ,10945   ,,,
BEGIN DESCRIPTION:
Trinity Park channel dam
Data from TRWD survey May 2007.
END DESCRIPTION:
Node Name=channel dam
IW Pilot Flow=0
#Inline Weir SE= 2
    2200     529    2600     529
IW Dist,WD,Coef,Skew,MaxSub,Min_El,Is_Ogee,SpillHt,DesHd
12,20,3,0,0.95,, 0 ,,,2,2,
Inline Weir Flap Gates= 0
IW Outlet Rating Curve= 0 ,False,,

Type RM Length L Ch R = 1 ,10927   ,34.9,90.1,75.4
BEGIN DESCRIPTION:
Downstream of Trinity Park channel dam.
Trinity Park in LOB.
END DESCRIPTION:
XS GIS Cut Line= 6
 2317245.1807574 6954051.4727374 2319211.7241999 6952964.2812454
  2319935.403558 6952551.6759999 2320058.6535732 6952485.8172132
 2320066.0003195 6952481.8914709 2320070.05751336952479.72350477
#Sta/Elev= 30
       0  581.86   31.13  573.41   59.26  569.05  175.29  563.31   236.8     554
  342.23  556.73  368.36     552  378.91     552  392.48  555.99   501.6  551.66
  628.64  553.97  914.72  547.56 1314.26  544.42 1477.75  545.15 1516.43  549.06
 1651.45  542.91 1677.59     546 1905.36  544.71 2158.03  548.73 2264.31  547.03
  2330.3     530    2336   521.5    2445     519    2485     522    2490     528
 2564.55  555.35  2875.8     558 3120.54     556 3162.63     560 3232.77   560.8
#Mann= 4 ,-1,0
       0     .15       0 2158.03    .055       0 2264.31    .035       0
 2564.55    .055       0
#XS Ineff= 4 ,-1
       0 2264.31  547.03 2595.88 2664.29  556.56 2664.29 2706.51     570
 2706.51 3240.28  556.56
Permanent Ineff=
       F       F       F       F
Bank Sta=2264.31,2564.55
XS Rating Curve= 0 ,0
Exp/Cntr=0.3,0.1

Type RM Length L Ch R = 1 ,10837   ,220.6,137.9,146.5
BEGIN DESCRIPTION:
--------------------------------------------------------------------
CDC FW121015-01 East Bank/Mistletoe Extension of the Trinity Trails
Cross-section 10837 - 13403.58
Includes new pedestrian bridge d/s of Miniature Railroad
---------------------------------------------------------------------
Section added with 2009 LiDAR
END DESCRIPTION:
XS GIS Cut Line= 5
2317144.838750556953817.447839522319280.183014296953043.69105475
  2319402.7100336952958.627067662319525.236861316952873.56323442
2320090.545157716952486.92776799
#Sta/Elev= 30
       0   571.4   56.04  575.13   78.59  569.71  250.62  559.52  315.25  558.66
  337.37  555.79  361.24  558.24  508.06  557.04  869.33  549.89 1333.89  546.35
 1476.04  548.74 1629.51  545.65 1637.76  542.32 1648.03  542.21 1676.65  546.11
 1784.46  547.34 1888.59  544.14 2175.16  549.58 2271.21  549.07 2329.93  527.43
 2331.74   518.9 2501.77   518.9 2502.74  527.11 2506.64  529.94 2569.53   555.3
 2722.35  553.79  2977.8  558.62 3166.17  556.53 3182.13   559.5 3254.41  560.79
#Mann= 4 ,-1,0
       0     .15       0 2175.16    .055       0 2271.21    .035       0
 2569.53    .055       0
#XS Ineff= 4 ,-1
  794.31 2271.21  549.07 2601.03 2852.36  554.91    2895    3042     570
    3042 3193.45  558.49
Permanent Ineff=
       F       F       F       F
Bank Sta=2271.21,2569.53
XS Rating Curve= 0 ,0
Exp/Cntr=0.3,0.1

Type RM Length L Ch R = 1 ,10699   ,504.1,483.9,478.1
BEGIN DESCRIPTION:
Trinity Park in LOB.
END DESCRIPTION:
XS GIS Cut Line= 2
 2317596.8431069 6954245.8233566  2320210.993655 6952617.5981467
#Sta/Elev= 30
       0   571.4   36.39  561.68   61.98   557.9  310.71  559.23  399.92  552.02
  769.98  547.93  835.19  544.23  924.39  545.44 1031.54  542.65 1142.24  548.96
 1192.43  544.62 1331.05  546.08 1449.77  543.44  2027.4   547.4 2080.09  546.96
 2128.78  528.73 2134.27  522.02 2249.01  518.84 2295.64  521.46 2301.48  526.53
 2312.66  529.02 2343.76  543.12 2369.05  551.36 2402.88  555.43 2600.21  554.69
 2856.85  557.97 2928.95  556.31 2986.23     558 2998.97     560 3079.76  560.95
#Mann= 4 ,-1,0
       0     .15       0  2027.4    .055       0 2080.09    .035       0
 2402.88    .055       0
#XS Ineff= 5 ,-1
   69.34   325.9     570   325.9 2080.09  546.96 2431.39 2619.36  555.96
 2619.36 2835.28     570 2835.28 3079.79  555.96
Permanent Ineff=
       F       F       F       F       F
Bank Sta=2080.09,2402.88
XS Rating Curve= 0 ,0
Exp/Cntr=0.3,0.1

Type RM Length L Ch R = 1 ,10215   ,472.9,413.6,397.2
BEGIN DESCRIPTION:
Trinity Park in LOB.
END DESCRIPTION:
XS GIS Cut Line= 3
 2317637.5045891 6954892.3395618 2320471.6323015 6952989.7084276
 2320544.7946652 6952940.5924367
#Sta/Elev= 30
       0  572.28  143.85  569.36  320.03  559.05  618.01  555.04  879.82  547.03
 1043.83  546.69 1109.84   548.8 1165.99  544.66 1175.02  546.25 1380.54   543.9
 1672.85  545.54 1813.67  543.07  2045.7  543.72 2233.01  547.13 2412.84  547.51
 2437.56  537.32 2464.27  529.78 2470.16  523.09  2479.6  520.13  2563.8  518.51
 2610.85  520.34 2636.96     528 2708.06     554 3268.39  555.56 3311.85   552.8
 3374.77   553.1 3397.97     560 3413.55     562 3478.93     562 3501.67   560.1
#Mann= 4 ,-1,0
       0     .15       0 2233.01    .055       0 2412.84    .035       0
 2708.06    .055       0
#XS Ineff= 4 ,-1
       0 2412.84  547.51 2752.58 2849.49  555.12 2949.49 3253.65     560
 3253.65 3501.67  555.12
Permanent Ineff=
       F       F       F       F
Bank Sta=2412.84,2708.06
XS Rating Curve= 0 ,0
Exp/Cntr=0.3,0.1

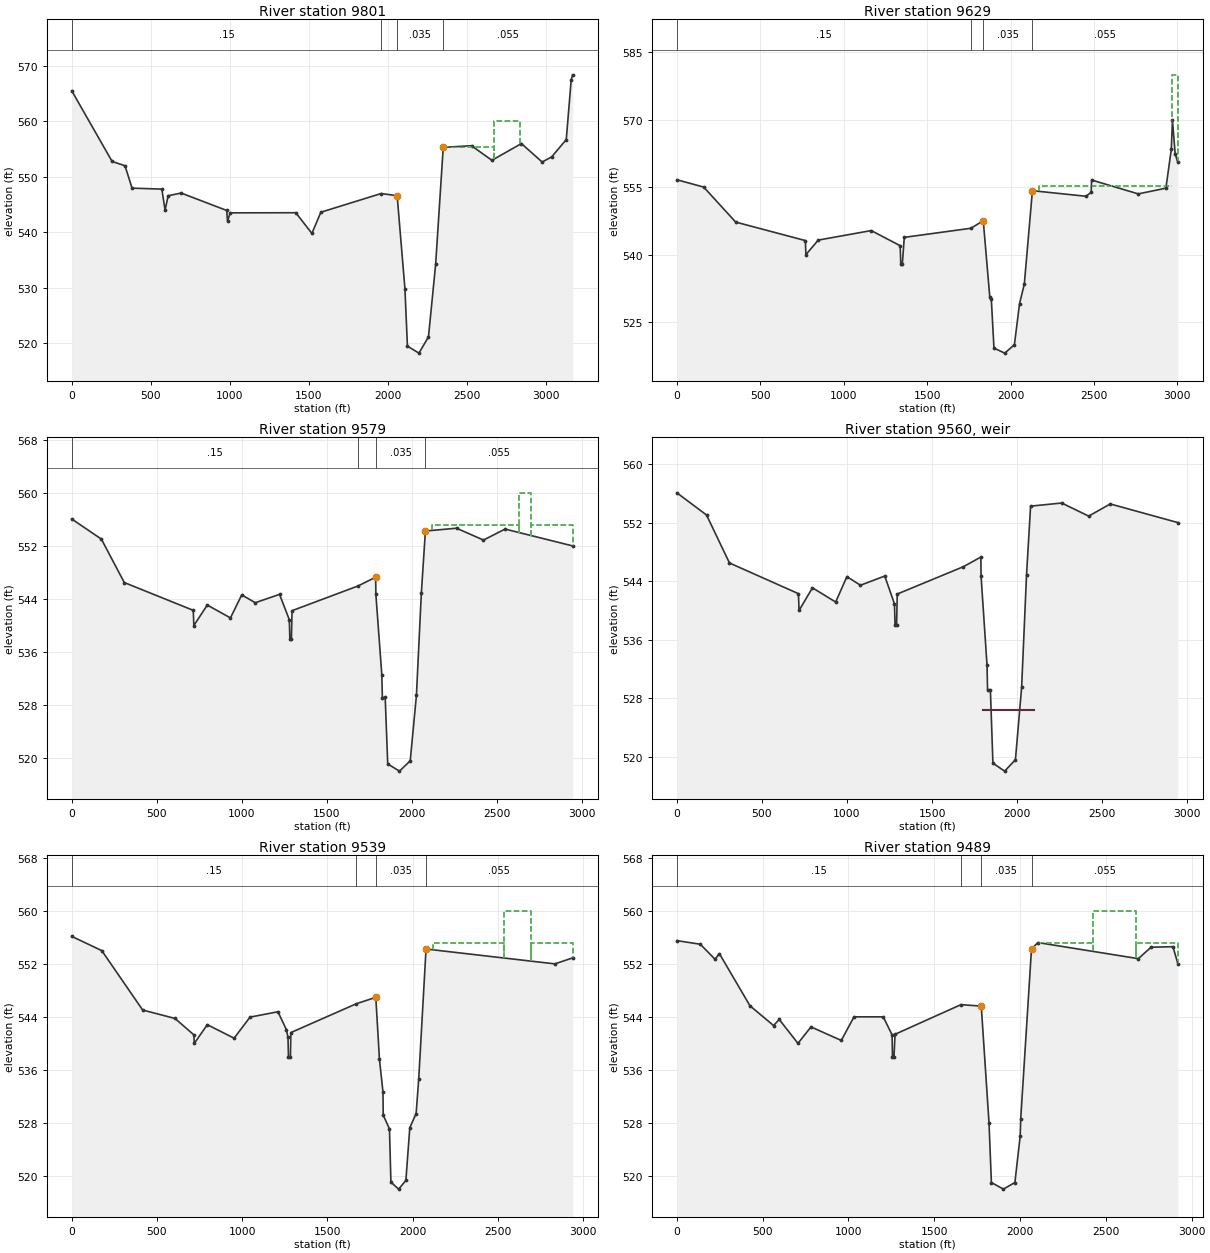
Type RM Length L Ch R = 1 ,9801    ,215.4,171.9,147.2
BEGIN DESCRIPTION:
Trinity Park in LOB.
END DESCRIPTION:
XS GIS Cut Line= 6
 2318307.3098006 6955209.3325384 2319886.8499979 6953892.6030224
 2320164.4989993 6953671.0906031 2320762.5950414 6953204.8764495
 2320975.3219189 6953039.0564571 2321057.7797855  6952974.780786
#Sta/Elev= 30
       0  565.52  255.73  552.77  337.25     552  381.86  547.96  570.24  547.79
  590.99     544  610.22  546.59  692.53  547.08  980.76  543.94  986.19     542
 1002.72  543.51 1418.28  543.53 1519.87   539.8 1576.54  543.62 1958.05  546.99
 2059.45   546.6  2108.6  529.86 2124.56  519.48 2197.19  518.22 2257.57  521.13
 2303.06  534.23 2351.09  555.31 2530.07  555.61 2658.99  552.98 2845.79     556
 2977.13  552.67  3037.8  553.61 3129.66  556.72 3160.75  567.45 3169.91  568.39
#Mann= 4 ,-1,0
       0     .15       0 1958.05    .055       0 2059.45    .035       0
 2351.09    .055       0
#XS Ineff= 4 ,-1
       0 2059.45   546.6 2351.09    2670  555.31    2670    2838     560
    2838 3169.91  555.31
Permanent Ineff=
       F       F       F       F
Bank Sta=2059.45,2351.09
XS Rating Curve= 0 ,0
Exp/Cntr=0.3,0.1

Type RM Length L Ch R = 1 ,9629    ,50.2,50.1,50.1
BEGIN DESCRIPTION:
Trinity Park in LOB.
END DESCRIPTION:
XS GIS Cut Line= 6
 2318679.4551505 6955279.8356891 2318821.1630508 6955151.3980124
 2320018.3036934 6954025.8358644 2320258.6623088 6953782.6104431
 2320880.2801865 6953238.2932639 2320912.2168048 6953210.3280933
#Sta/Elev= 30
       0  556.66  160.75  555.03  352.16  547.25  770.32  543.13  773.11     540
  847.27  543.24 1164.84  545.36 1338.53  541.99 1341.83     538 1351.49     538
 1362.98  543.85 1762.25  545.87 1836.37  547.56 1875.55  530.56 1884.64  530.11
  1900.6  519.22  1965.1   518.1    2023  519.96  2053.9  529.11  2082.5  533.46
 2131.05  554.23 2452.48  552.99  2483.3  553.88 2485.86   556.6 2765.73  553.52
 2931.17  554.79 2963.67  563.44 2970.39  570.02 2986.66  562.43 3002.64  560.51
#Mann= 4 ,-1,0
       0     .15       0 1762.25    .055       0 1836.37    .035       0
 2131.05    .055       0
#XS Ineff= 3 ,-1
       0 1836.37  547.56 2170.75 2969.13  555.19 2969.13 3002.64     580
Permanent Ineff=
       F       F       T
Bank Sta=1836.37,2131.05
XS Rating Curve= 0 ,0
Exp/Cntr=0.3,0.1

Type RM Length L Ch R = 1 ,9579    ,40.1,40.1,40.2
BEGIN DESCRIPTION:
Upstream of Trinity Park channel dam.
Trinity Park in LOB.
END DESCRIPTION:
XS GIS Cut Line= 5
 2318755.9142417 6955279.8356891 2318855.4125275 6955187.8256601
 2320053.2223595 6954061.6342512 2320292.9585847  6953819.038739
 2320913.2191567 6953275.9100773
#Sta/Elev= 30
       0  556.06  174.28  553.03  309.12  546.48  714.65  542.29   718.1     540
  796.94  543.09  933.35  541.15  999.67  544.62 1079.32  543.44 1222.02   544.7
 1279.29  540.89 1282.62     538 1291.61     538 1295.55  542.24 1684.03  545.97
 1787.11  547.29 1788.29  544.69 1823.42  532.52  1826.5  529.14  1843.1  529.18
 1858.05  519.14 1927.04  518.06 1990.38  519.62 2026.78  529.49 2055.57  544.83
 2079.51  554.24 2262.48  554.67 2421.07  552.88 2547.83  554.54 2945.13     552
#Mann= 4 ,-1,0
       0     .15       0 1684.03    .055       0 1787.11    .035       0
 2079.51    .055       0
#XS Ineff= 5 ,-1
       0 1787.11  547.29 1787.11 2079.51  526.42 2118.37 2629.39   555.2
 2629.39 2700.87     560 2700.87 2945.13   555.2
Permanent Ineff=
       F       T       F       F       F
Bank Sta=1787.11,2079.51
XS Rating Curve= 0 ,0
Exp/Cntr=0.3,0.1

Type RM Length L Ch R = 5 ,9560    ,,,
BEGIN DESCRIPTION:
Trinity Park channel dam
Structure reconstructed by TRWD.  Structure survey data from TRWD May 2007.
END DESCRIPTION:
Node Name=channel dam
IW Pilot Flow=0
#Inline Weir SE= 2
    1800  526.42    2100  526.42
IW Dist,WD,Coef,Skew,MaxSub,Min_El,Is_Ogee,SpillHt,DesHd
9,20,3,0,0.95,, 0 ,,,2,2,
Inline Weir Flap Gates= 0
IW Outlet Rating Curve= 0 ,False,,

Type RM Length L Ch R = 1 ,9539    ,50,50.2,50.2
BEGIN DESCRIPTION:
Downstream of Trinity Park channel dam.
Trinity Park in LOB.
END DESCRIPTION:
XS GIS Cut Line= 6
  2318785.196524 6955304.2375046 2318882.8122125 6955216.9676746
 2320081.1574478 6954090.2730125 2320320.3956054  6953848.181272
 2320939.5703328 6953306.0036318 2320989.4125882  6953262.359479
#Sta/Elev= 30
       0  556.15  176.43     554  416.33  545.04  605.79  543.77  716.99  541.29
  718.99     540  795.56  542.83  952.85  540.79 1046.22  543.97 1210.03  544.78
 1259.25   542.1 1269.06  540.92 1271.74     538 1283.21     538 1285.95  541.64
 1668.54  545.97 1784.28  546.96 1805.68  537.59 1826.35  532.69 1827.79  529.19
 1864.42  527.11 1872.92  519.08 1918.26  518.03 1960.68  519.34 1983.72  527.29
 2020.85  529.42 2036.27   534.7    2079  554.24 2834.72     552 2939.13   552.9
#Mann= 4 ,-1,0
       0     .15       0 1668.54    .055       0 1784.28    .035       0
    2079    .055       0
#XS Ineff= 4 ,-1
       0 1784.28  546.96 2117.41 2536.99   555.2 2536.99 2696.88     560
 2696.88 2939.13   555.2
Permanent Ineff=
       F       F       F       F
Bank Sta=1784.28,2079
XS Rating Curve= 0 ,0
Exp/Cntr=0.3,0.1

Type RM Length L Ch R = 1 ,9489    ,196.5,192.5,195.1
BEGIN DESCRIPTION:
Trinity Park in LOB.
Large mound of material removed in LOB.
END DESCRIPTION:
XS GIS Cut Line= 6
  2318834.000155 6955330.2661424 2318917.0616893 6955253.3953223
 2320116.0761139 6954126.0713993 2320354.6918813 6953884.6095679
  2320972.509303 6953343.6204452 2321015.1443051 6953306.2872922
#Sta/Elev= 30
       0   555.5  136.37  554.96   222.3  552.69  247.69  553.54  425.82  545.67
  563.43  542.69  596.44  543.61  705.56     540  781.63  542.48  958.06  540.44
 1032.38     544 1202.59     544 1254.08  541.29 1256.48     538 1265.23     538
 1271.55  541.37 1655.41  545.84 1773.95  545.62 1819.14     528    1833     519
    1903     518    1970     519 2000.82     526 2004.02  528.64 2066.78  554.25
 2104.47  555.21 2689.52  552.78 2763.46  554.51 2891.06  554.59 2919.59  552.05
#Mann= 4 ,-1,0
       0     .15       0 1655.41    .055       0 1773.95    .035       0
 2066.78    .055       0
#XS Ineff= 4 ,-1
       0 1773.95  545.62 2104.47  2423.4  555.21  2423.4  2673.8     560
  2673.8 2919.59  555.21
Permanent Ineff=
       F       F       F       F
Bank Sta=1773.95,2066.78
XS Rating Curve= 0 ,0
Exp/Cntr=0.3,0.1

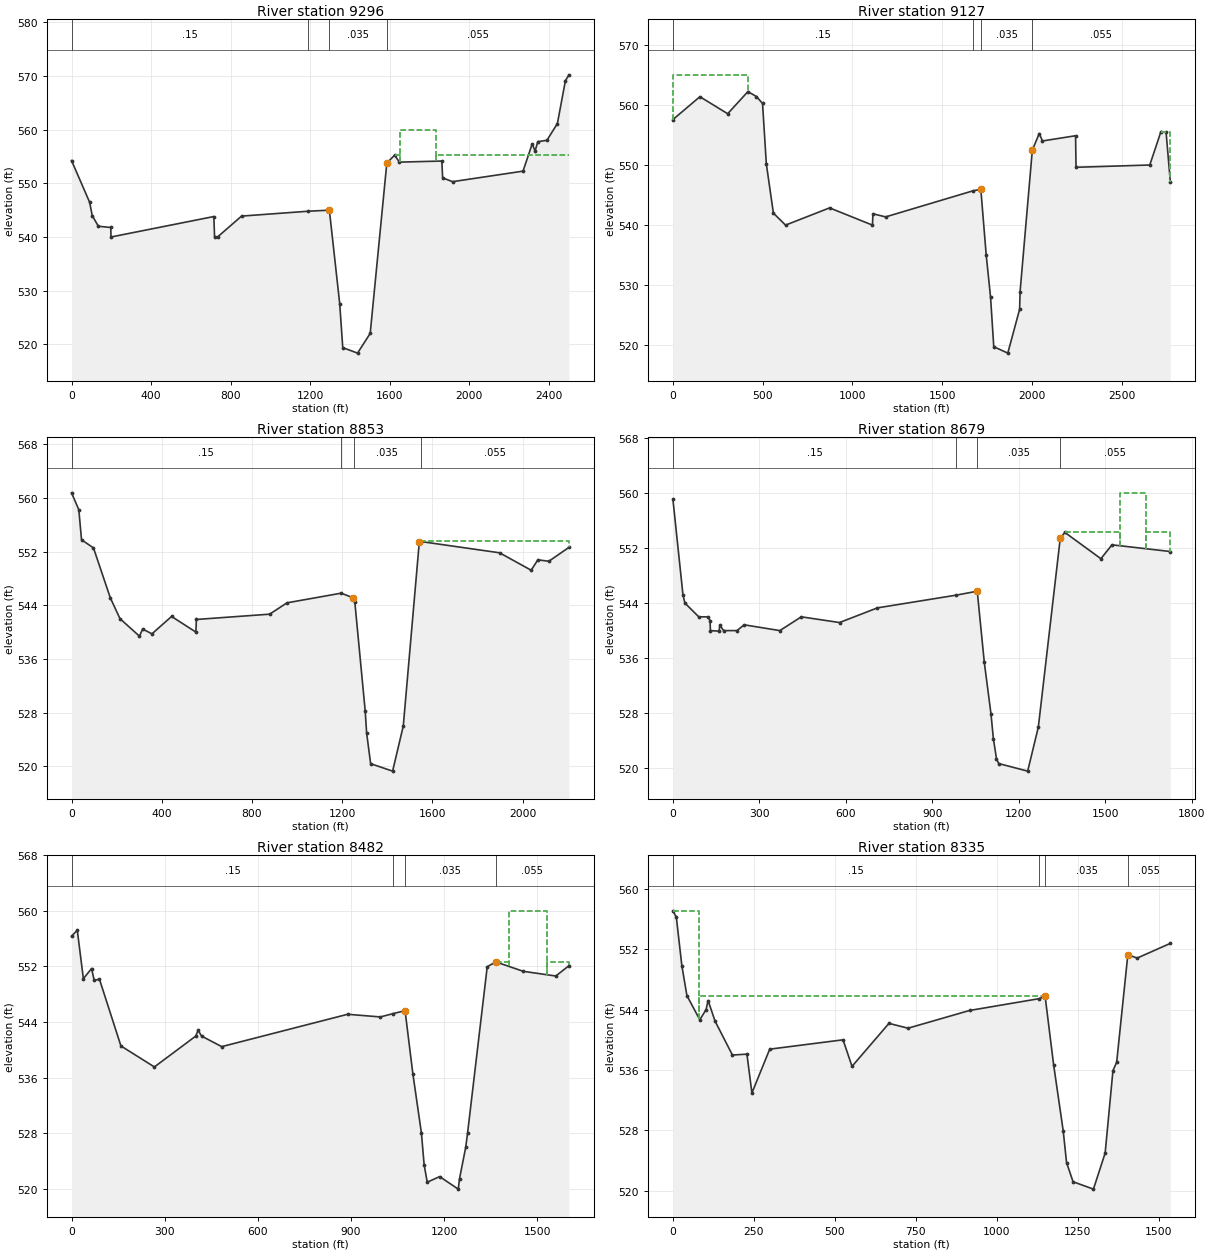
Type RM Length L Ch R = 1 ,9296    ,195.7,169.4,168.4
BEGIN DESCRIPTION:
Trinity Park in LOB.
END DESCRIPTION:
XS GIS Cut Line= 2
  2319342.920824 6955140.0556297 2321136.2750413 6953396.3788009
#Sta/Elev= 30
       0  554.23   90.93  546.47  103.94     544  134.76     542  197.31  541.77
  198.45     540  715.61  543.81   719.2     540  734.09     540  854.98  543.89
 1191.12   544.8 1296.44  544.99 1348.39   527.6 1363.73  519.41 1438.06  518.38
 1501.75  522.05 1585.29  553.75 1623.99  555.22 1648.92  553.94 1862.03  554.14
 1865.95  551.01  1915.8   550.3 2270.16  552.26 2316.38  557.34 2330.91     556
 2344.35  557.74 2390.35     558 2443.04  561.12 2483.26  569.09 2501.31  570.19
#Mann= 4 ,-1,0
       0     .15       0 1191.12    .055       0 1296.44    .035       0
 1585.29    .055       0
#XS Ineff= 4 ,-1
       0 1296.44  544.99 1623.99    1650  555.22    1650    1834     560
    1834 2501.31  555.22
Permanent Ineff=
       F       F       F       F
Bank Sta=1296.44,1585.29
XS Rating Curve= 0 ,0
Exp/Cntr=0.3,0.1

Type RM Length L Ch R = 1 ,9127    ,265.5,274.2,304
BEGIN DESCRIPTION:
Trinity Park in LOB.
END DESCRIPTION:
XS GIS Cut Line= 4
   2319229.26326 6955599.5496293 2320406.3546697  6954342.329088
 2321155.8022237 6953607.5900867 2321210.9862907 6953553.4890545
#Sta/Elev= 30
       0  557.56  150.41  561.36  305.19  558.53  417.88  562.21  465.42  561.39
  499.38  560.24  520.49  550.19  559.85     542  627.55     540  872.94  542.87
 1111.92     540 1114.39  541.89  1185.3  541.37    1670  545.69 1715.66  545.96
 1745.65  535.03 1769.99  527.99 1787.75  519.78 1865.94  518.71  1931.8     526
 1934.46  528.96 2002.59  552.46 2041.08  555.24 2059.31     554  2243.6  554.87
 2246.18  549.62 2657.13     550 2719.24  555.56 2747.98  555.44 2771.78  547.11
#Mann= 4 ,-1,0
       0     .15       0    1670    .055       0 1715.66    .035       0
 2002.59    .055       0
#XS Ineff= 4 ,-1
       0  417.88     565  417.88 1715.66  545.96 2041.08 2719.18  555.24
 2719.18 2771.78  555.55
Permanent Ineff=
       T       F       F       T
Bank Sta=1715.66,2002.59
XS Rating Curve= 0 ,0
Exp/Cntr=0.3,0.1

Type RM Length L Ch R = 1 ,8853    ,158.5,173.7,197.8
BEGIN DESCRIPTION:
Effective flow limit in LOB set at Clear Fork Levee Loop.
Trinity Park in LOB.
END DESCRIPTION:
XS GIS Cut Line= 3
 2319731.3537127 6955477.0562256 2320566.2875426 6954542.8542166
 2321333.2002633 6953977.1455366
#Sta/Elev= 30
       0  560.76    32.3  558.24   44.27  553.76   97.27  552.55  171.78  545.12
  214.81     542  301.11  539.39  315.34  540.45  356.58  539.74  443.66  542.33
  551.37     540  553.65  541.88  878.52  542.67  955.41  544.36 1195.61   545.8
 1246.14  545.15 1250.98  544.82 1256.32  544.44 1302.34  528.21 1308.54  524.95
 1326.37  520.38 1423.78  519.27  1471.1     526    1542  553.37 1548.56   553.5
 1898.05  551.82 2038.24  549.22 2067.88  550.77 2116.61  550.56 2205.92  552.63
#Mann= 4 ,-1,0
       0     .15       0 1195.61    .055       0 1250.98    .035       0
 1548.56    .055       0
#XS Ineff= 2 , 0
         1246.14  545.15 1549.38          553.51
Permanent Ineff=
       F       F
Bank Sta=1246.14,1542
XS Rating Curve= 0 ,0
Exp/Cntr=0.3,0.1

Type RM Length L Ch R = 1 ,8679    ,242,196.9,177.9
BEGIN DESCRIPTION:
Effective flow limit in LOB set at Clear Fork Levee Loop.
Trinity Park in LOB.
END DESCRIPTION:
XS GIS Cut Line= 4
 2319956.0632545 6955483.3638728 2320557.9514559 6954779.7550082
 2320649.2104942 6954681.0226214 2321221.3525699   6954340.65067
#Sta/Elev= 30
       0  559.05   34.83  545.21    41.5     544   89.69     542   122.2     542
  128.69  541.46  130.25     540   160.2  539.92   162.6  540.78  176.01     540
  222.17     540  247.38  540.84  371.07     540  445.52     542  578.16  541.17
  709.66   543.3  983.53  545.15 1055.97  545.72  1080.5  535.38 1103.63  527.91
    1112   524.3  1122.8   521.4  1130.4   520.7    1231   519.6 1267.99     526
 1344.07  553.42 1360.04  554.25 1485.04  550.44 1523.63  552.45  1726.1  551.48
#Mann= 4 ,-1,0
       0     .15       0  983.53    .055       0 1055.97    .035       0
 1344.07    .055       0
#XS Ineff= 4 ,-1
       0 1055.97  545.72 1360.04    1550  554.25    1550    1641     560
    1641  1726.1  554.25
Permanent Ineff=
       F       F       F       F
Bank Sta=1055.97,1344.07
XS Rating Curve= 0 ,0
Exp/Cntr=0.3,0.1

Type RM Length L Ch R = 1 ,8482    ,206.1,147.6,117.5
BEGIN DESCRIPTION:
Effective flow limit in LOB set at Clear Fork Levee Loop.
Trinity Park in LOB.
END DESCRIPTION:
XS GIS Cut Line= 4
 2320145.8922438 6955740.8074278 2320755.7871228 6954867.5487038
 2320763.6635146 6954856.0087534 2321181.4069465 6954540.3787866
#Sta/Elev= 30
       0  556.35   18.52  557.21   38.12  550.25   64.56  551.71   73.04     550
   89.85  550.18  159.13  540.58  266.94  537.56  400.24     542  407.87  542.84
  418.88     542  483.85  540.48  889.43  545.13  994.92  544.75 1037.27  545.24
 1074.58  545.65 1099.58  536.61 1127.24  528.07    1136   523.5    1146     521
    1186   521.8    1246     520    1250   521.5 1269.93     526  1275.8     528
 1339.26  551.96 1366.81  552.66 1455.16  551.31 1560.21  550.63  1602.7  552.12
#Mann= 4 ,-1,0
       0     .15       0 1037.27    .055       0 1074.58    .035       0
 1366.81    .055       0
#XS Ineff= 4 ,-1
       0 1074.58  545.65 1366.81  1409.7  552.66  1409.7  1532.7     560
  1532.7  1602.7  552.66
Permanent Ineff=
       F       F       F       F
Bank Sta=1074.58,1366.81
XS Rating Curve= 0 ,0
Exp/Cntr=0.3,0.1

Type RM Length L Ch R = 1 ,8335    ,150.8,89.7,48
BEGIN DESCRIPTION:
Effective flow limit in LOB set at Clear Fork Levee Loop.
Trinity Park in LOB.
END DESCRIPTION:
XS GIS Cut Line= 3
 2320340.5994961 6955991.4347673  2320887.686642 6954973.3118564
 2321139.2526874 6954689.0421331
#Sta/Elev= 30
       0   557.1   10.52  556.27   27.53  549.84   43.15  545.87   82.97  542.66
  102.26     544  108.65   545.2  130.06  542.48   183.7  537.98  228.47   538.1
  243.82  532.95   298.8  538.76  525.12     540  552.83  536.48  666.82  542.18
  725.69  541.54  915.58  543.89 1129.29  545.45 1148.79  545.77  1175.2  536.65
  1204.8  527.88 1214.96  523.73 1235.04  521.18 1297.95   520.2 1334.09  524.98
 1358.18  535.91 1369.68  537.03 1404.12  551.28 1433.03  550.84  1535.4  552.79
#Mann= 4 ,-1,0
       0     .15       0 1129.29    .055       0 1148.79    .035       0
 1404.12    .055       0
#XS Ineff= 3 ,-1
       0    81.9 557.104    81.9 1148.79  545.77 1404.12  1535.4  551.28
Permanent Ineff=
       F       F       F
Bank Sta=1148.79,1404.12
XS Rating Curve= 0 ,0
Exp/Cntr=0.3,0.1