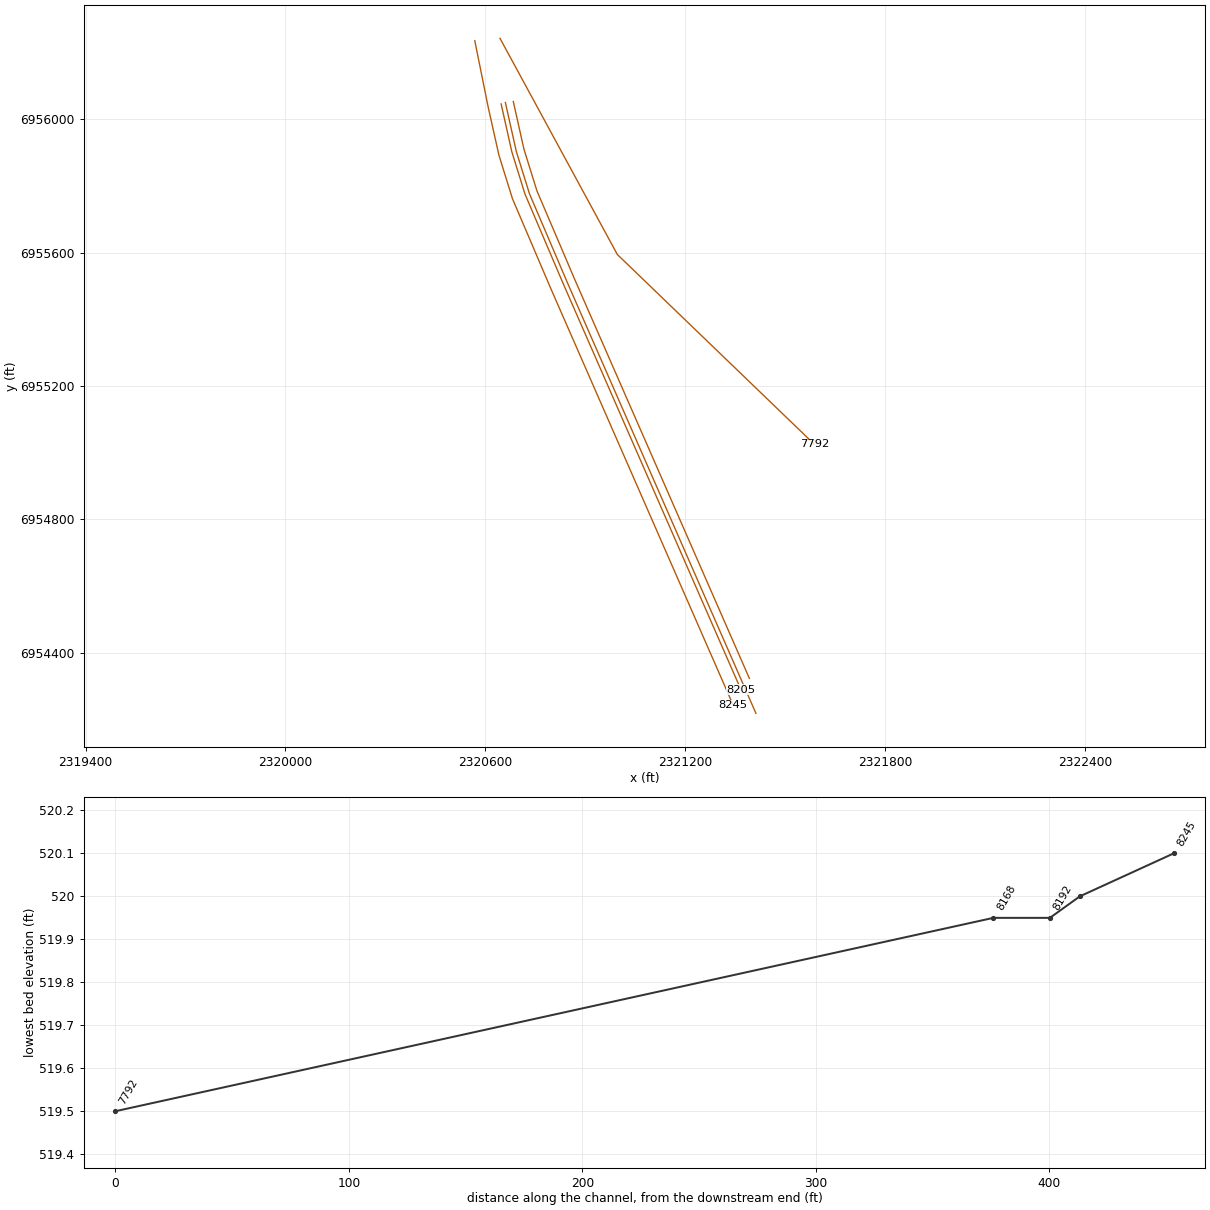
HEC-RAS study CDC_Consolidated_Model.prj: Upper Trinity CDC Consolidated Model

--- CDC_Consolidated_Model.g11 (geometry) --- (continued)

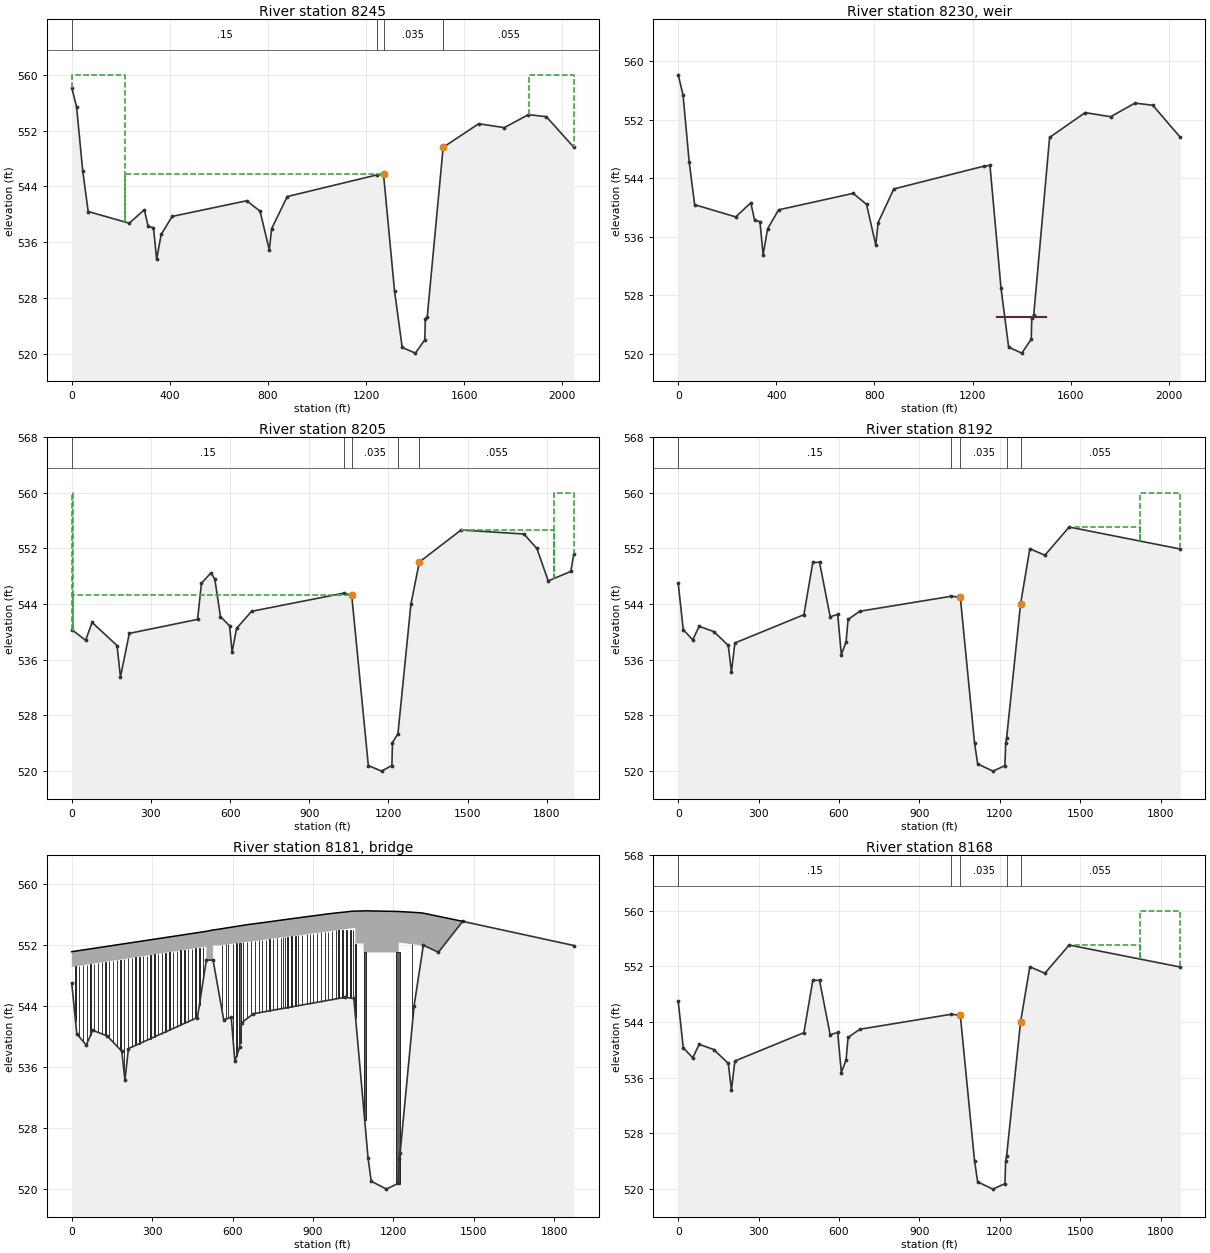
Type RM Length L Ch R = 1 ,8245    ,40.3,40.2,40.4
BEGIN DESCRIPTION:
Upstream of Trinity Park channel dam.
Effective flow limit in LOB set at Clear Fork Levee Loop.
Trinity Park in LOB.
END DESCRIPTION:
XS GIS Cut Line= 6
  2320568.185826 6956236.2190808 2320608.1992498 6956037.9701292
  2320640.562629 6955893.0667917  2320681.204147 6955762.3551419
 2320796.9989165 6955490.9938235 2321343.9301084 6954241.5988561
#Sta/Elev= 30
       0  558.16   19.63   555.4   44.52  546.28      67   540.4  234.35  538.73
  295.86  540.66   311.6  538.26  333.22  538.09  346.13  533.56  364.45  537.11
   409.5   539.7  713.56  541.95  767.94  540.44  805.51  534.89  814.94  537.94
  878.82  542.55 1245.19  545.66  1271.2  545.77 1316.11  529.02 1347.42  520.91
 1401.11   520.1 1439.44     522 1441.64  524.93  1449.5  525.28 1514.36   549.6
 1659.29  552.99 1763.35  552.43 1862.26  554.29 1935.11     554 2047.34  549.61
#Mann= 4 ,-1,0
       0     .15       0 1245.19    .055       0  1271.2    .035       0
 1514.36    .055       0
#XS Ineff= 4 ,-1
       0  216.27     560  216.27  1271.2  545.77  1271.2 1514.36     525
 1863.37 2047.34     560
Permanent Ineff=
       F       F       T       F
Bank Sta=1271.2,1514.36
XS Rating Curve= 0 ,0
Exp/Cntr=0.3,0.1

Type RM Length L Ch R = 5 ,8230    ,,,
BEGIN DESCRIPTION:
Trinity Park channel dam
Structure reconstructed by TRWD.  Structure survey data from TRWD May 2007.
END DESCRIPTION:
Node Name=channel dam
IW Pilot Flow=0
#Inline Weir SE= 2
    1300     525    1500     525
IW Dist,WD,Coef,Skew,MaxSub,Min_El,Is_Ogee,SpillHt,DesHd
5,20,3,0,0.95,, 0 ,,,2,2,
Inline Weir Flap Gates= 0
IW Outlet Rating Curve= 0 ,False,,

Type RM Length L Ch R = 1 ,8205    ,12.8,12.8,12.8
BEGIN DESCRIPTION:
Downstream of Trinity Park channel dam.
Effective flow limit in LOB set at Clear Fork Levee Loop.
Trinity Park in LOB.
END DESCRIPTION:
XS GIS Cut Line= 5
 2320647.2375395 6956046.6890358 2320679.2444154 6955903.3815372
 2320718.7949033 6955776.1786587 2320833.7164339 6955506.8640588
 2321366.9263599 6954288.8133561
#Sta/Elev= 30
       0  540.34   52.43  538.81   77.11  541.37  171.57  538.05  184.52  533.53
  218.09   539.8  476.74  541.81  491.39  547.01  527.71   548.5  542.01  547.58
  563.39  542.21  597.97  540.88  607.49  537.12   624.5  540.52   681.4  542.97
 1030.62  545.58 1060.72  545.28 1123.79   520.8 1173.79     520    1213   520.8
 1215.25  524.11  1235.9  525.37 1285.13     544 1316.99  550.05 1475.26  554.66
 1713.18  554.08 1762.58     552 1805.38  547.34 1891.08  548.71  1902.5  551.25
#Mann= 5 ,-1,0
       0     .15       0 1030.62    .055       0 1060.72    .035       0
  1235.9    .025       0 1316.99    .055       0
#XS Ineff= 4 ,-1
       0    5.68     560    5.68 1060.72  545.28 1475.26    1827  554.66
    1827  1902.5     560
Permanent Ineff=
       F       F       F       F
Bank Sta=1060.72,1316.99
XS Rating Curve= 0 ,0
Exp/Cntr=0.3,0.1

Type RM Length L Ch R = 1 ,8192    ,24.2,24.2,24.3
BEGIN DESCRIPTION:
Upstream of BNSF Railroad.
Copy of cross-section 8167.88.
Effective flow limit in LOB set at Clear Fork Levee Loop.
Trinity Park in LOB.
END DESCRIPTION:
XS GIS Cut Line= 6
 2320660.0074916 6956050.8115116 2320692.8043789 6955904.0512451
 2320732.3548669 6955776.8483665 2320847.2763975 6955507.5337666
 2321394.1329181  6954258.309143 2321411.8899292 6954217.7454948
#Sta/Elev= 30
       0  546.96   18.74  540.31   54.16  538.84   78.02  540.79  132.48  540.04
  186.78  538.04  198.44  534.22  211.39  538.39  468.84  542.46   502.3     550
  527.29     550  566.98  542.17  594.98   542.5  608.61  536.73  626.35  538.54
  633.76  541.78  677.72  542.96 1019.68  545.12 1052.65  544.96 1105.79     524
  1117.4  520.99  1174.4  519.95  1219.2  520.74  1221.8  523.94 1225.51  524.74
 1277.42  543.99 1312.04  551.95 1368.22  551.02 1458.79  555.08 1873.61  551.91
#Mann= 5 ,-1,0
       0     .15       0 1019.68    .055       0 1052.65    .035       0
 1225.51    .025       0 1277.42    .055       0
#XS Ineff= 3 ,-1
       0 1052.65  544.96 1480.53    1725  555.09    1725 1873.61     560
Permanent Ineff=
       F       F       F
Bank Sta=1052.65,1277.42
XS Rating Curve= 0 ,0
Exp/Cntr=0.5,0.3

Type RM Length L Ch R = 3 ,8181    ,,,
BEGIN DESCRIPTION:
BNSF Railroad
Main channel bridge: bridge data from 1975 USACE survey, low chord elev. 551.0, length 761 feet.  Left bank relief bridge: data from USACE May 2007 field measurement.
END DESCRIPTION:
Node Name=BNSF RR
Bridge Culvert--1,0,-1,-1, 0
Deck Dist Width WeirC Skew NumUp NumDn MinLoCord MaxHiCord MaxSubmerge Is_Ogee
6,10,2.6,0, 54, 54, , , 0.95, 0, 0,0,,
       0   502.3   502.3  527.29  527.29  545.04  557.04  558.04  571.04  572.04
  584.04  585.04  599.04  600.04  612.04  613.04  624.04  629.04  639.04  640.04
  652.04  653.04  666.04  667.04  738.04  748.04  878.04  888.04  954.04  955.04
  968.04  969.04  982.04  983.04 1015.04 1019.04 1050.04 1051.04 1058.04 1058.04
 1060.54 1089.04 1089.04 1097.04 1211.04 1220.04 1220.04 1266.04 1267.04 1269.04
 1270.04 1306.04  1306.4 1458.79
   551.1  553.77  553.77  553.95  553.95  554.03   554.1   554.1  554.18  554.18
  554.25  554.25  554.33  554.34  554.41  554.41  554.47   554.5  554.56  554.56
  554.63  554.63   554.7   554.7  555.03  555.08   555.7  555.74  556.05  556.06
  556.11  556.11  556.17  556.17  556.29   556.3  556.42  556.42  556.42  556.42
  556.43  556.45  556.45  556.46  556.38  556.37  556.37  556.28  556.28  556.27
  556.27  556.19  556.19  555.08
   549.1  551.77     550     550  551.95  551.91  551.96  551.97  552.02  552.03
  552.08  552.08  552.14  552.15   552.2  552.21  552.25  552.28  552.32  552.32
  552.38  552.38  552.44  552.44  552.75   552.8  553.38  553.43  553.73  553.74
   553.8   553.8  553.87  553.87  554.02  554.04  554.19   554.2  554.23  552.17
  552.17  552.18     551     551     551     551  552.29   552.1  552.09  552.08
  552.08  551.93     546     546
       0   502.3   502.3  527.29  527.29  545.04  557.04  558.04  571.04  572.04
  584.04  585.04  599.04  600.04  612.04  613.04  624.04  629.04  639.04  640.04
  652.04  653.04  666.04  667.04  738.04  748.04  878.04  888.04  954.04  955.04
  968.04  969.04  982.04  983.04 1015.04 1019.04 1050.04 1051.04 1058.04 1058.04
 1060.54 1089.04 1089.04 1097.04 1211.04 1220.04 1220.04 1266.04 1267.04 1269.04
 1270.04 1306.04  1306.4 1458.79
   551.1  553.77  553.77  553.95  553.95  554.03   554.1   554.1  554.18  554.18
  554.25  554.25  554.33  554.34  554.41  554.41  554.47   554.5  554.56  554.56
  554.63  554.63   554.7   554.7  555.03  555.08   555.7  555.74  556.05  556.06
  556.11  556.11  556.17  556.17  556.29   556.3  556.42  556.42  556.42  556.42
  556.43  556.45  556.45  556.46  556.38  556.37  556.37  556.28  556.28  556.27
  556.27  556.19  556.19  555.08
   549.1  551.77     550     550  551.95  551.91  551.96  551.97  552.02  552.03
  552.08  552.08  552.14  552.15   552.2  552.21  552.25  552.28  552.32  552.32
  552.38  552.38  552.44  552.44  552.75   552.8  553.38  553.43  553.73  553.74
   553.8   553.8  553.87  553.87  554.02  554.04  554.19   554.2  554.23  552.17
  552.17  552.18     551     551     551     551  552.29   552.1  552.09  552.08
  552.08  551.93     546     546
Pier Skew, UpSta & Num, DnSta & Num=  ,560.04, 2 ,560.04, 2 , 0 , 0 , 0 ,,
       1       1
     500     553
       1       1
     500     553
Pier Skew, UpSta & Num, DnSta & Num=  ,575.04, 2 ,575.04, 2 , 0 , 0 , 0 ,,
       1       1
     500     553
       1       1
     500     553
Pier Skew, UpSta & Num, DnSta & Num=  ,582.04, 2 ,582.04, 2 , 0 , 0 , 0 ,,
       1       1
     500     553
       1       1
     500     553
Pier Skew, UpSta & Num, DnSta & Num=  ,602.04, 2 ,602.04, 2 , 0 , 0 , 0 ,,
       1       1
     500     553
       1       1
     500     553
Pier Skew, UpSta & Num, DnSta & Num=  ,615.04, 2 ,615.04, 2 , 0 , 0 , 0 ,,
       1       1
     500     553
       1       1
     500     553
Pier Skew, UpSta & Num, DnSta & Num=  ,627.54, 2 ,627.54, 2 , 0 , 0 , 0 ,,
       5       5
     500     553
       5       5
     500     553
Pier Skew, UpSta & Num, DnSta & Num=  ,640.04, 2 ,640.04, 2 , 0 , 0 , 0 ,,
       1       1
     500     553
       1       1
     500     553
Pier Skew, UpSta & Num, DnSta & Num=  ,655.04, 2 ,655.04, 2 , 0 , 0 , 0 ,,
       1       1
     500     553
       1       1
     500     553
Pier Skew, UpSta & Num, DnSta & Num=  ,670.04, 2 ,670.04, 2 , 0 , 0 , 0 ,,
       1       1
     500     553
       1       1
     500     553
Pier Skew, UpSta & Num, DnSta & Num=  ,682.54, 2 ,682.54, 2 , 0 , 0 , 0 ,,
       1       1
     500     553
       1       1
     500     553
Pier Skew, UpSta & Num, DnSta & Num=  ,697.54, 2 ,697.54, 2 , 0 , 0 , 0 ,,
       1       1
     500     553
       1       1
     500     553
Pier Skew, UpSta & Num, DnSta & Num=  ,710.04, 2 ,710.041, 2 , 0 , 0 , 0 ,,
       1       1
     500     553
       1       1
     500     553
Pier Skew, UpSta & Num, DnSta & Num=  ,725.04, 2 ,725.041, 2 , 0 , 0 , 0 ,,
       1       1
     500     553
       1       1
     500     553
Pier Skew, UpSta & Num, DnSta & Num=  ,737.54, 2 ,737.541, 2 , 0 , 0 , 0 ,,
       1       1
     500     553
       1       1
     500     553
Pier Skew, UpSta & Num, DnSta & Num=  ,750.04, 2 ,750.04, 2 , 0 , 0 , 0 ,,
       1       1
     500     553
       1       1
     500     553
Pier Skew, UpSta & Num, DnSta & Num=  ,765.04, 2 ,765.04, 2 , 0 , 0 , 0 ,,
       1       1
     500   553.5
       1       1
     500   553.5
Pier Skew, UpSta & Num, DnSta & Num=  ,780.04, 2 ,780.04, 2 , 0 , 0 , 0 ,,
       1       1
     500   553.5
       1       1
     500   553.5
Pier Skew, UpSta & Num, DnSta & Num=  ,787.5, 2 ,787.5, 2 , 0 , 0 , 0 ,,
       1       1
     500     553
       1       1
     500     553
Pier Skew, UpSta & Num, DnSta & Num=  ,795.04, 2 ,795.04, 2 , 0 , 0 , 0 ,,
       1       1
     500   553.5
       1       1
     500   553.5
Pier Skew, UpSta & Num, DnSta & Num=  ,805.04, 2 ,805.041, 2 , 0 , 0 , 0 ,,
       1       1
     500   553.5
       1       1
     500   553.5
Pier Skew, UpSta & Num, DnSta & Num=  ,820.04, 2 ,820.041, 2 , 0 , 0 , 0 ,,
       1       1
     500   553.5
       1       1
     500   553.5
Pier Skew, UpSta & Num, DnSta & Num=  ,835.04, 2 ,835.041, 2 , 0 , 0 , 0 ,,
       1       1
     500   553.5
       1       1
     500   553.5
Pier Skew, UpSta & Num, DnSta & Num=  ,845.04, 2 ,845.041, 2 , 0 , 0 , 0 ,,
       1       1
     500   553.5
       1       1
     500   553.5
Pier Skew, UpSta & Num, DnSta & Num=  ,860.04, 2 ,860.041, 2 , 0 , 0 , 0 ,,
       1       1
     500   553.5
       1       1
     500   553.5
Pier Skew, UpSta & Num, DnSta & Num=  ,877.54, 2 ,877.541, 2 , 0 , 0 , 0 ,,
       1       1
     500   553.5
       1       1
     500   553.5
Pier Skew, UpSta & Num, DnSta & Num=  ,890.04, 2 ,890.041, 2 , 0 , 0 , 0 ,,
       1       1
     500   553.5
       1       1
     500   553.5
Pier Skew, UpSta & Num, DnSta & Num=  ,900.04, 2 ,900.041, 2 , 0 , 0 , 0 ,,
       1       1
     500     554
       1       1
     500     554
Pier Skew, UpSta & Num, DnSta & Num=  ,915.04, 2 ,915.041, 2 , 0 , 0 , 0 ,,
       1       1
     500     554
       1       1
     500     554
Pier Skew, UpSta & Num, DnSta & Num=  ,930.04, 2 ,930.04, 2 , 0 , 0 , 0 ,,
       1       1
     500     554
       1       1
     500     554
Pier Skew, UpSta & Num, DnSta & Num=  ,945.04, 2 ,945.041, 2 , 0 , 0 , 0 ,,
       1       1
     500     554
       1       1
     500     554
Pier Skew, UpSta & Num, DnSta & Num=  ,955.04, 2 ,955.041, 2 , 0 , 0 , 0 ,,
       1       1
     500     554
       1       1
     500     554
Pier Skew, UpSta & Num, DnSta & Num=  ,970.04, 2 ,970.04, 2 , 0 , 0 , 0 ,,
       1       1
     500     554
       1       1
     500     554
Pier Skew, UpSta & Num, DnSta & Num=  ,985.04, 2 ,985.04, 2 , 0 , 0 , 0 ,,
       1       1
     500     554
       1       1
     500     554
Pier Skew, UpSta & Num, DnSta & Num=  ,995.04, 2 ,995.04, 2 , 0 , 0 , 0 ,,
       1       1
     500     554
       1       1
     500     554
Pier Skew, UpSta & Num, DnSta & Num=  ,1010.04, 2 ,1010.04, 2 , 0 , 0 , 0 ,,
       1       1
     500     554
       1       1
     500     554
Pier Skew, UpSta & Num, DnSta & Num=  ,1025.04, 2 ,1025.04, 2 , 0 , 0 , 0 ,,
       1       1
     500     554
       1       1
     500     554
Pier Skew, UpSta & Num, DnSta & Num=  ,1040.04, 2 ,1040.04, 2 , 0 , 0 , 0 ,,
       1       1
     500     554
       1       1
     500     554
Pier Skew, UpSta & Num, DnSta & Num=  ,1050.04, 2 ,1050.041, 2 , 0 , 0 , 0 ,,
       1       1
     500     554
       1       1
     500     554
Pier Skew, UpSta & Num, DnSta & Num=  ,1059.29, 2 ,1059.29, 2 , 0 , 0 , 0 ,,
     2.5     2.5
     500     554
     2.5     2.5
     500     554
Pier Skew, UpSta & Num, DnSta & Num=  ,1093.04, 2 ,1093.04, 2 , 0 , 0 , 0 ,,
       8       8
     500     553
       8       8
     500     553
Pier Skew, UpSta & Num, DnSta & Num=  ,1216.04, 4 ,1216.04, 4 , 0 , 0 , 0 ,,
    14.5    14.5       8       8
     500   525.5   525.5     553
    14.5    14.5       8       8
     500   525.5   525.5     553
Pier Skew, UpSta & Num, DnSta & Num=  ,1270.04, 2 ,1270.04, 2 , 0 , 0 , 0 ,,
       2       2
     500     554
       2       2
     500     554
Pier Skew, UpSta & Num, DnSta & Num=  ,14, 2 ,14, 2 , 0 , 0 , 0 ,,
     1.5     1.5
  519.95  554.23
     1.5     1.5
  519.95  554.23
Pier Skew, UpSta & Num, DnSta & Num=  ,28, 2 ,28, 2 , 0 , 0 , 0 ,,
     1.5     1.5
  519.95  554.23
     1.5     1.5
  519.95  554.23
Pier Skew, UpSta & Num, DnSta & Num=  ,42, 2 ,42, 2 , 0 , 0 , 0 ,,
     1.5     1.5
  519.95  554.23
     1.5     1.5
  519.95  554.23
Pier Skew, UpSta & Num, DnSta & Num=  ,56, 2 ,56, 2 , 0 , 0 , 0 ,,
     1.5     1.5
  519.95  554.23
     1.5     1.5
  519.95  554.23
Pier Skew, UpSta & Num, DnSta & Num=  ,70, 2 ,70, 2 , 0 , 0 , 0 ,,
     1.5     1.5
  519.95  554.23
     1.5     1.5
  519.95  554.23
Pier Skew, UpSta & Num, DnSta & Num=  ,84, 2 ,84, 2 , 0 , 0 , 0 ,,
     1.5     1.5
  519.95  554.23
     1.5     1.5
  519.95  554.23
Pier Skew, UpSta & Num, DnSta & Num=  ,98, 2 ,98, 2 , 0 , 0 , 0 ,,
     1.5     1.5
  519.95  554.23
     1.5     1.5
  519.95  554.23
Pier Skew, UpSta & Num, DnSta & Num=  ,112, 2 ,112, 2 , 0 , 0 , 0 ,,
     1.5     1.5
  519.95  554.23
     1.5     1.5
  519.95  554.23
Pier Skew, UpSta & Num, DnSta & Num=  ,126, 2 ,126, 2 , 0 , 0 , 0 ,,
     1.5     1.5
  519.95  554.23
     1.5     1.5
  519.95  554.23
Pier Skew, UpSta & Num, DnSta & Num=  ,140, 2 ,140, 2 , 0 , 0 , 0 ,,
     1.5     1.5
  519.95  554.23
     1.5     1.5
  519.95  554.23
Pier Skew, UpSta & Num, DnSta & Num=  ,154, 2 ,154, 2 , 0 , 0 , 0 ,,
     1.5     1.5
  519.95  554.23
     1.5     1.5
  519.95  554.23
Pier Skew, UpSta & Num, DnSta & Num=  ,168, 2 ,168, 2 , 0 , 0 , 0 ,,
     1.5     1.5
  519.95  554.23
     1.5     1.5
  519.95  554.23
Pier Skew, UpSta & Num, DnSta & Num=  ,182, 2 ,182, 2 , 0 , 0 , 0 ,,
     1.5     1.5
  519.95  554.23
     1.5     1.5
  519.95  554.23
Pier Skew, UpSta & Num, DnSta & Num=  ,196, 2 ,196, 2 , 0 , 0 , 0 ,,
     1.5     1.5
  519.95  554.23
     1.5     1.5
  519.95  554.23
Pier Skew, UpSta & Num, DnSta & Num=  ,210, 2 ,210, 2 , 0 , 0 , 0 ,,
     1.5     1.5
  519.95  554.23
     1.5     1.5
  519.95  554.23
Pier Skew, UpSta & Num, DnSta & Num=  ,224, 2 ,224, 2 , 0 , 0 , 0 ,,
     1.5     1.5
  519.95  554.23
     1.5     1.5
  519.95  554.23
Pier Skew, UpSta & Num, DnSta & Num=  ,238, 2 ,238, 2 , 0 , 0 , 0 ,,
     1.5     1.5
  519.95  554.23
     1.5     1.5
  519.95  554.23
Pier Skew, UpSta & Num, DnSta & Num=  ,252, 2 ,252, 2 , 0 , 0 , 0 ,,
     1.5     1.5
  519.95  554.23
     1.5     1.5
  519.95  554.23
Pier Skew, UpSta & Num, DnSta & Num=  ,266, 2 ,266, 2 , 0 , 0 , 0 ,,
     1.5     1.5
  519.95  554.23
     1.5     1.5
  519.95  554.23
Pier Skew, UpSta & Num, DnSta & Num=  ,280, 2 ,280, 2 , 0 , 0 , 0 ,,
     1.5     1.5
  519.95  554.23
     1.5     1.5
  519.95  554.23
Pier Skew, UpSta & Num, DnSta & Num=  ,294, 2 ,294, 2 , 0 , 0 , 0 ,,
     1.5     1.5
  519.95  554.23
     1.5     1.5
  519.95  554.23
Pier Skew, UpSta & Num, DnSta & Num=  ,308, 2 ,308, 2 , 0 , 0 , 0 ,,
     1.5     1.5
  519.95  554.23
     1.5     1.5
  519.95  554.23
Pier Skew, UpSta & Num, DnSta & Num=  ,322, 2 ,322, 2 , 0 , 0 , 0 ,,
     1.5     1.5
  519.95  554.23
     1.5     1.5
  519.95  554.23
Pier Skew, UpSta & Num, DnSta & Num=  ,336, 2 ,336, 2 , 0 , 0 , 0 ,,
     1.5     1.5
  519.95  554.23
     1.5     1.5
  519.95  554.23
Pier Skew, UpSta & Num, DnSta & Num=  ,350, 2 ,350, 2 , 0 , 0 , 0 ,,
     1.5     1.5
  519.95  554.23
     1.5     1.5
  519.95  554.23
Pier Skew, UpSta & Num, DnSta & Num=  ,364, 2 ,364, 2 , 0 , 0 , 0 ,,
     1.5     1.5
  519.95  554.23
     1.5     1.5
  519.95  554.23
Pier Skew, UpSta & Num, DnSta & Num=  ,378, 2 ,378, 2 , 0 , 0 , 0 ,,
     1.5     1.5
  519.95  554.23
     1.5     1.5
  519.95  554.23
Pier Skew, UpSta & Num, DnSta & Num=  ,392, 2 ,392, 2 , 0 , 0 , 0 ,,
     1.5     1.5
  519.95  554.23
     1.5     1.5
  519.95  554.23
Pier Skew, UpSta & Num, DnSta & Num=  ,406, 2 ,406, 2 , 0 , 0 , 0 ,,
     1.5     1.5
  519.95  554.23
     1.5     1.5
  519.95  554.23
Pier Skew, UpSta & Num, DnSta & Num=  ,420, 2 ,420, 2 , 0 , 0 , 0 ,,
     1.5     1.5
  519.95  554.23
     1.5     1.5
  519.95  554.23
Pier Skew, UpSta & Num, DnSta & Num=  ,434, 2 ,434, 2 , 0 , 0 , 0 ,,
     1.5     1.5
  519.95  554.23
     1.5     1.5
  519.95  554.23
Pier Skew, UpSta & Num, DnSta & Num=  ,448, 2 ,448, 2 , 0 , 0 , 0 ,,
     1.5     1.5
  519.95  554.23
     1.5     1.5
  519.95  554.23
Pier Skew, UpSta & Num, DnSta & Num=  ,462, 2 ,462, 2 , 0 , 0 , 0 ,,
     1.5     1.5
  519.95  554.23
     1.5     1.5
  519.95  554.23
Pier Skew, UpSta & Num, DnSta & Num=  ,476, 2 ,476, 2 , 0 , 0 , 0 ,,
     1.5     1.5
  519.95  554.23
     1.5     1.5
  519.95  554.23
Pier Skew, UpSta & Num, DnSta & Num=  ,490, 2 ,490, 2 , 0 , 0 , 0 ,,
     1.5     1.5
  519.95  554.23
     1.5     1.5
  519.95  554.23
BR Coef=-1 , 0 , 0 ,, 0 ,,,0.8,-1,,0,
WSPro=,,,, 1 ,,,, 0 ,,,, 0 ,,,,-1 ,-1 ,-1 , 0 , 0 , 0 , 0 , 0
BC Design=,, 0 ,, 0 ,,,,,,
BC Use User HTab Curves=0
BC User HTab FreeFlow(D)= 0

Type RM Length L Ch R = 1 ,8168    ,212.6,376,430.1
BEGIN DESCRIPTION:
Downstream of BNSF Railroad.
Effective flow limit in LOB set at Clear Fork Levee Loop.
Effective flow limit in LOB set at Water Works Levee.
Trinity Park in LOB.
Rock riprap and concrete paving on right bank slope from downstream cross-section to up[stream channel dam.
END DESCRIPTION:
XS GIS Cut Line= 5
  2320683.743618 6956054.0028004 2320715.5722421 6955911.4932213
  2320754.577215 6955786.0447284 2320869.0621262 6955517.7534877
 2321392.1972701 6954322.7172403
#Sta/Elev= 30
       0  546.96   18.74  540.31   54.16  538.84   78.02  540.79  132.48  540.04
  186.78  538.04  198.44  534.22  211.39  538.39  468.84  542.46   502.3     550
  527.29     550  566.98  542.17  594.98   542.5  608.61  536.73  626.35  538.54
  633.76  541.78  677.72  542.96 1019.68  545.12 1052.65  544.96 1105.79     524
  1117.4  520.99  1174.4  519.95  1219.2  520.74  1221.8  523.94 1225.51  524.74
 1277.42  543.99 1312.04  551.95 1368.22  551.02 1458.79  555.08 1873.61  551.91
#Mann= 5 ,-1,0
       0     .15       0 1019.68    .055       0 1052.65    .035       0
 1225.51    .025       0 1277.42    .055       0
#XS Ineff= 3 ,-1
       0 1052.65  544.96 1480.53    1725  555.09    1725 1873.61     560
Permanent Ineff=
       F       F       F
Bank Sta=1052.65,1277.42
XS Rating Curve= 0 ,0
Exp/Cntr=0.5,0.3

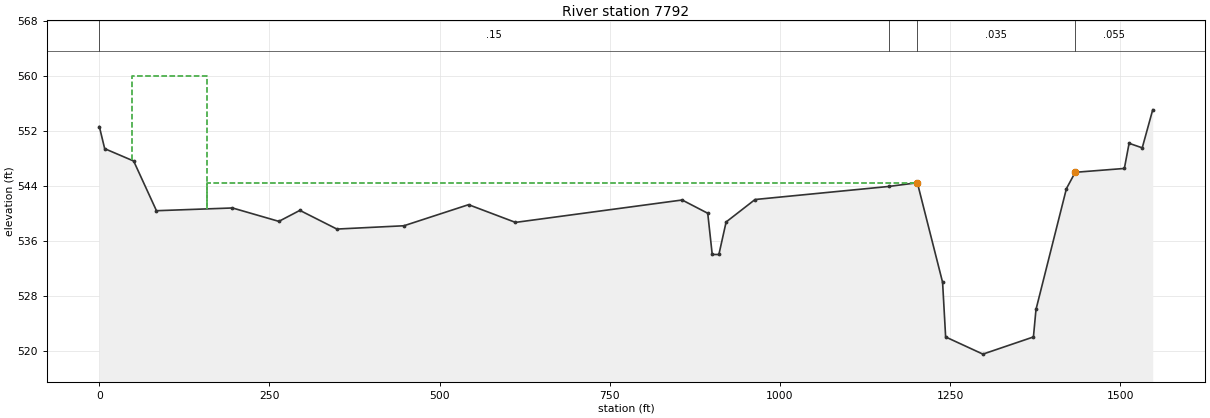
Type RM Length L Ch R = 1 ,7792    ,515,597.5,633
BEGIN DESCRIPTION:
Effective flow limit in LOB set at Clear Fork Levee Loop.
Effective flow limit in LOB set at Water Works Levee.
Trinity Park in LOB.
END DESCRIPTION:
XS GIS Cut Line= 3
 2320643.8217184 6956243.5017324  2320995.966579 6955594.8138381
 2321586.6552582 6955025.7357472
#Sta/Elev= 30
       0  552.62    7.85   549.4   50.44   547.6   83.93  540.37  195.63  540.77
  263.77  538.82  294.65  540.42  349.03   537.7  447.47  538.18   542.5  541.25
  611.43  538.67   856.3  541.93   893.9     540   900.5     534  910.28     534
  920.91  538.73  963.42     542 1159.86   543.9 1201.88  544.44 1238.96  529.95
 1243.43     522  1298.2   519.5 1372.43     522 1376.19     526 1420.89  543.58
  1433.8  545.96 1506.02  546.52 1512.98  550.18 1532.29  549.52 1547.73  555.07
#Mann= 4 ,-1,0
       0     .15       0 1159.86    .055       0 1201.88    .035       0
  1433.8    .055       0
#XS Ineff= 2 ,-1
    47.7  158.85     560  158.85 1201.88  544.44
Permanent Ineff=
       F       F
Bank Sta=1201.88,1433.8
XS Rating Curve= 0 ,0
Exp/Cntr=0.3,0.1