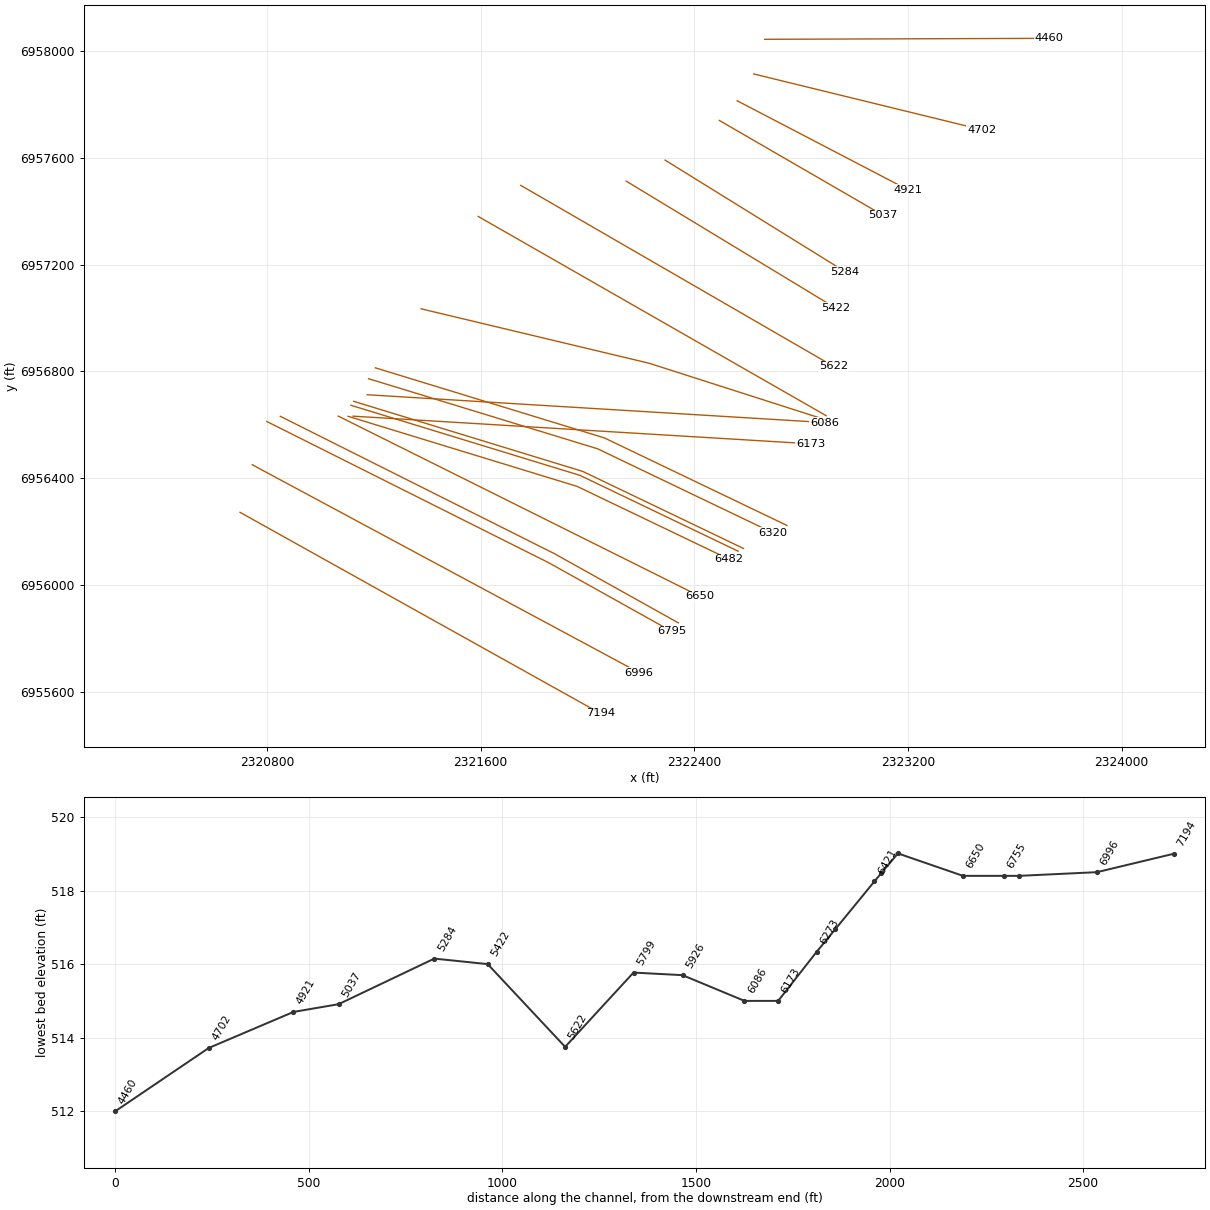
HEC-RAS study CDC_Consolidated_Model.prj: Upper Trinity CDC Consolidated Model

--- CDC_Consolidated_Model.g11 (geometry) --- (continued)

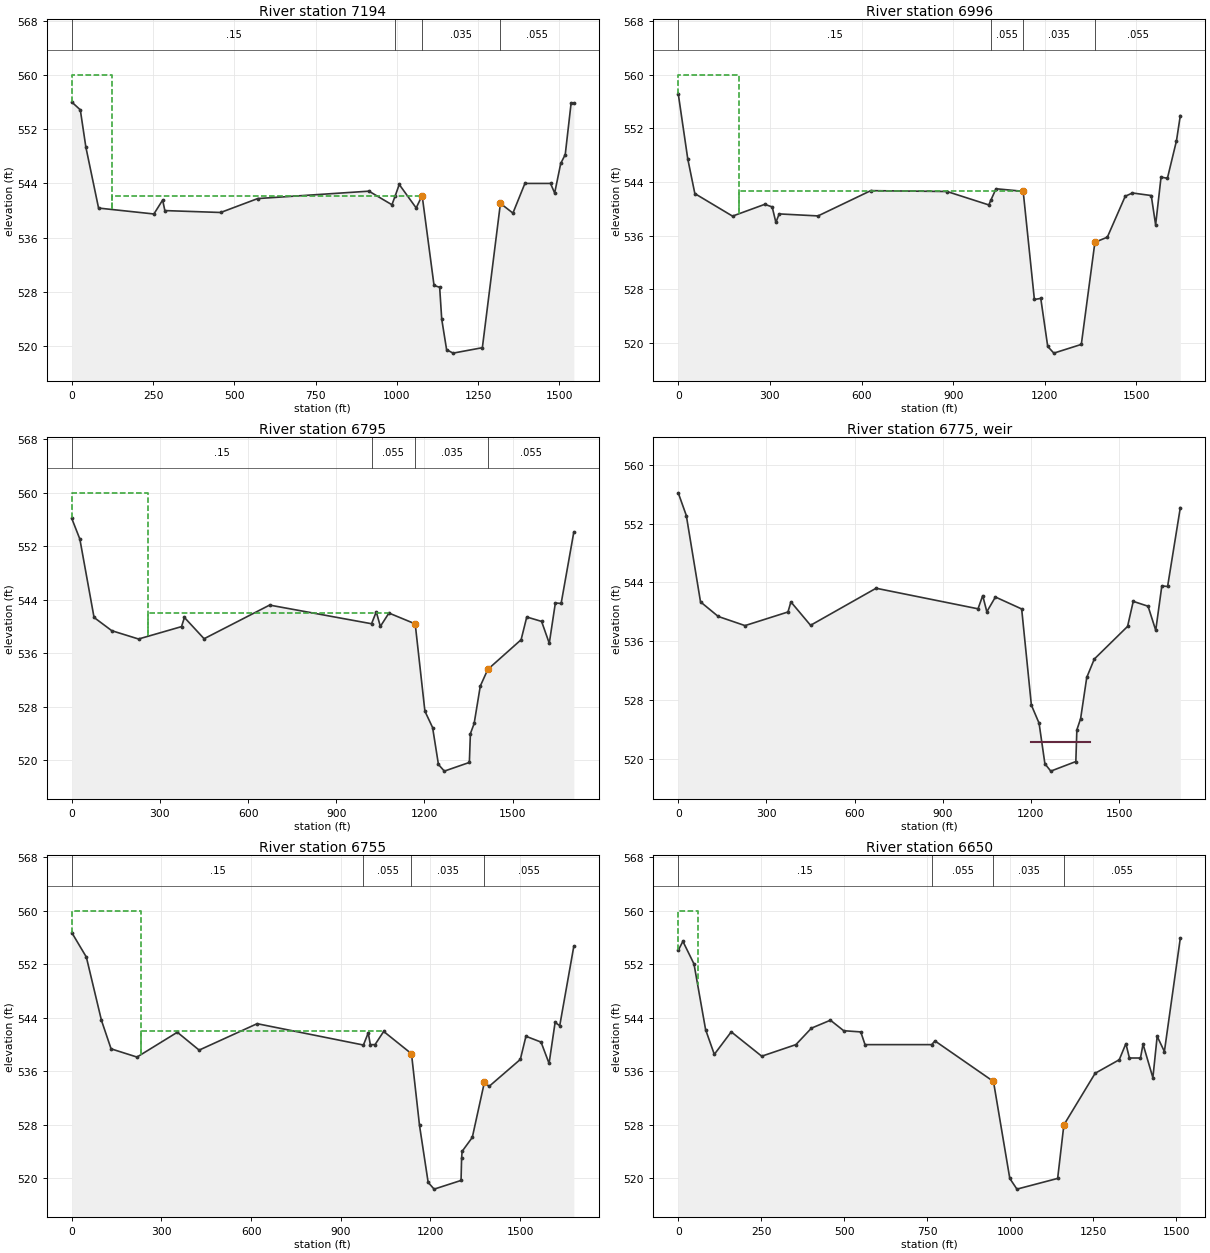
Type RM Length L Ch R = 1 ,7194    ,194.2,198.2,200.4
BEGIN DESCRIPTION:
Effective flow limit in LOB set at Clear Fork Levee Loop.
Effective flow limit in LOB set at Water Works Levee.
Trinity Park in LOB.
END DESCRIPTION:
XS GIS Cut Line= 2
 2320698.8124336 6956272.5812615 2322047.9338491  6955519.756648
#Sta/Elev= 30
       0  555.99   26.28  554.84   43.37  549.35   82.47  540.37  252.72   539.5
  279.63  541.55  286.43     540  458.19  539.72  572.18  541.77  914.43  542.86
  985.19  540.86  995.41  542.18 1007.64  543.85 1059.74  540.39 1078.13  542.22
 1114.74  528.97 1132.03   528.7  1138.4     524 1153.45   519.5 1173.45     519
 1263.45   519.8 1319.03  541.06  1357.5  539.63 1394.37     544 1473.18     544
  1485.9  542.59 1504.63  546.95 1518.46  548.25 1536.61  555.86 1544.95  555.87
#Mann= 4 ,-1,0
       0     .15       0  995.41    .055       0 1078.13    .035       0
 1319.03    .055       0
#XS Ineff= 2 ,-1
       0  122.76     560  122.76 1078.13  542.22
Permanent Ineff=
       F       F
Bank Sta=1078.13,1319.03
XS Rating Curve= 0 ,0
Exp/Cntr=0.3,0.1

Type RM Length L Ch R = 1 ,6996    ,199.3,200.8,198.5
BEGIN DESCRIPTION:
Effective flow limit in LOB set at Clear Fork Levee Loop.
Effective flow limit in LOB set at Water Works Levee.
Trinity Park in LOB.
END DESCRIPTION:
XS GIS Cut Line= 2
 2320744.4680748 6956450.8315387 2322192.1879614 6955672.8052456
#Sta/Elev= 30
       0  557.19   31.13  547.48   54.38  542.29   177.7  538.93  283.33  540.69
  307.51   540.3  319.62     538  330.46  539.26  457.61  538.96  630.28  542.73
  879.97   542.6 1016.62   540.6  1023.1  541.28 1040.26  543.01 1129.16  542.63
 1165.86   526.5 1186.77  526.66  1209.5   519.5  1229.5   518.5  1319.5   519.8
 1363.96  535.03 1404.65  535.79 1463.29   541.9 1486.95  542.38 1548.42     542
 1562.73  537.62 1580.47  544.75 1601.32  544.57 1630.94  550.16 1643.54  553.92
#Mann= 4 ,-1,0
       0     .15       0  1023.1    .055       0 1129.16    .035       0
 1363.96    .055       0
#XS Ineff= 2 ,-1
       0  199.36     560  199.36 1129.16  542.63
Permanent Ineff=
       F       F
Bank Sta=1129.16,1363.96
XS Rating Curve= 0 ,0
Exp/Cntr=0.3,0.1

Type RM Length L Ch R = 1 ,6795    ,40.5,40,40.1
BEGIN DESCRIPTION:
Upstream of Trinity Park channel dam.
Effective flow limit in LOB set at Clear Fork Levee Loop.
Effective flow limit in LOB set at Water Works Levee.
Trinity Park in LOB.
END DESCRIPTION:
XS GIS Cut Line= 3
 2320798.9380358 6956612.7608307 2321855.3766364 6956083.4633345
 2322315.4712471 6955826.6407436
#Sta/Elev= 30
       0  556.17   27.48  553.09   75.83  541.37  136.18  539.39  227.25  538.15
  373.48     540  383.36  541.37   450.3  538.19  673.25  543.22 1020.17  540.43
 1036.16  542.22 1050.11  540.03 1079.31  542.03 1168.68  540.41 1201.72  527.36
  1227.9  524.91 1247.75   519.4 1267.75   518.4    1353   519.7 1356.49     524
 1369.27  525.52  1390.2  531.12 1415.82  533.61 1529.07  538.04 1548.33  541.44
 1598.78  540.78 1624.92  537.51 1645.65  543.54 1665.29  543.46 1708.54  554.16
#Mann= 4 ,-1,0
       0     .15       0 1020.17    .055       0 1168.68    .035       0
 1415.82    .055       0
#XS Ineff= 3 ,-1
       0  259.74     560  259.74 1078.68     542 1168.68 1415.82   522.3
Permanent Ineff=
       F       F       T
Bank Sta=1168.68,1415.82
XS Rating Curve= 0 ,0
Exp/Cntr=0.3,0.1

Type RM Length L Ch R = 5 ,6775    ,,,
BEGIN DESCRIPTION:
Trinity Park channel dam
Structure reconstructed by TRWD.  Survey data from TRWD May 2007.
END DESCRIPTION:
Node Name=channel dam
IW Pilot Flow=0
#Inline Weir SE= 2
    1200   522.3    1400   522.3
IW Dist,WD,Coef,Skew,MaxSub,Min_El,Is_Ogee,SpillHt,DesHd
10,20,3,0,0.95,, 0 ,,,2,2,
Inline Weir Flap Gates= 0
IW Outlet Rating Curve= 0 ,False,,

Type RM Length L Ch R = 1 ,6755    ,100.9,105.2,113.3
BEGIN DESCRIPTION:
Downstream of Trinity Park channel dam.
Effective flow limit in LOB set at Clear Fork Levee Loop.
Effective flow limit in LOB set at Water Works Levee.
Trinity Park in LOB.
END DESCRIPTION:
XS GIS Cut Line= 3
 2320849.7142326 6956632.0604991 2321874.0929356 6956118.8256204
 2322340.1630619 6955858.6678429
#Sta/Elev= 30
       0  556.75   48.75  553.09   99.28  543.63  131.51  539.37  218.26  538.14
  353.14  541.85  426.06  539.18  620.03  543.13  975.63  539.94  991.73  541.75
  998.78     540 1014.45     540 1043.37  541.97 1136.39  538.64 1163.26  527.92
  1192.2   519.4  1212.2   518.4  1302.2   519.7    1304     523 1305.82  524.05
 1339.81  526.13 1380.58  534.43 1395.83  533.75 1500.51  537.79 1519.26  541.25
  1569.8  540.38 1596.65  537.19 1616.83  543.32 1632.29  542.83 1679.52  554.73
#Mann= 4 ,-1,0
       0     .15       0  975.63    .055       0 1136.39    .035       0
 1380.58    .055       0
#XS Ineff= 2 ,-1
       0  231.37     560  231.37 1043.37     542
Permanent Ineff=
       F       F
Bank Sta=1136.39,1380.58
XS Rating Curve= 0 ,0
Exp/Cntr=0.3,0.1

Type RM Length L Ch R = 1 ,6650    ,151.8,168.1,169
BEGIN DESCRIPTION:
Effective flow limit in LOB set at Clear Fork Levee Loop.
Effective flow limit in LOB set at Water Works Levee.
Trinity Park in LOB.
END DESCRIPTION:
XS GIS Cut Line= 4
 2321066.4973425 6956632.9008101 2322317.2900947 6956009.7091124
 2322399.1968025 6955968.9001293 2322419.8547963 6955958.6075447
#Sta/Elev= 30
       0  554.09   14.02  555.44   47.44  552.06   82.42  542.24  108.64  538.54
  159.62  541.91  251.39  538.27  354.34     540  401.06  542.46  458.32  543.65
  498.29  542.08  549.69   541.9  562.51     540  763.12     540  773.22  540.55
  949.37  534.49  998.48     520    1020   518.4 1142.62     520 1161.37     528
 1255.62  535.72 1328.14  537.74 1348.13  540.15 1358.75     538 1392.05     538
  1399.8  540.07 1429.43  535.05 1442.35  541.24 1464.09  538.97 1512.03  555.92
#Mann= 4 ,-1,0
       0     .15       0  763.12    .055       0  949.37    .035       0
 1161.37    .055       0
#XS Ineff= 3 ,-1
       0   58.45     560   58.45  478.32     542 1348.13 1512.03  540.15
Permanent Ineff=
       F       F       F
Bank Sta=949.37,1161.37
XS Rating Curve= 0 ,0
Exp/Cntr=0.3,0.1

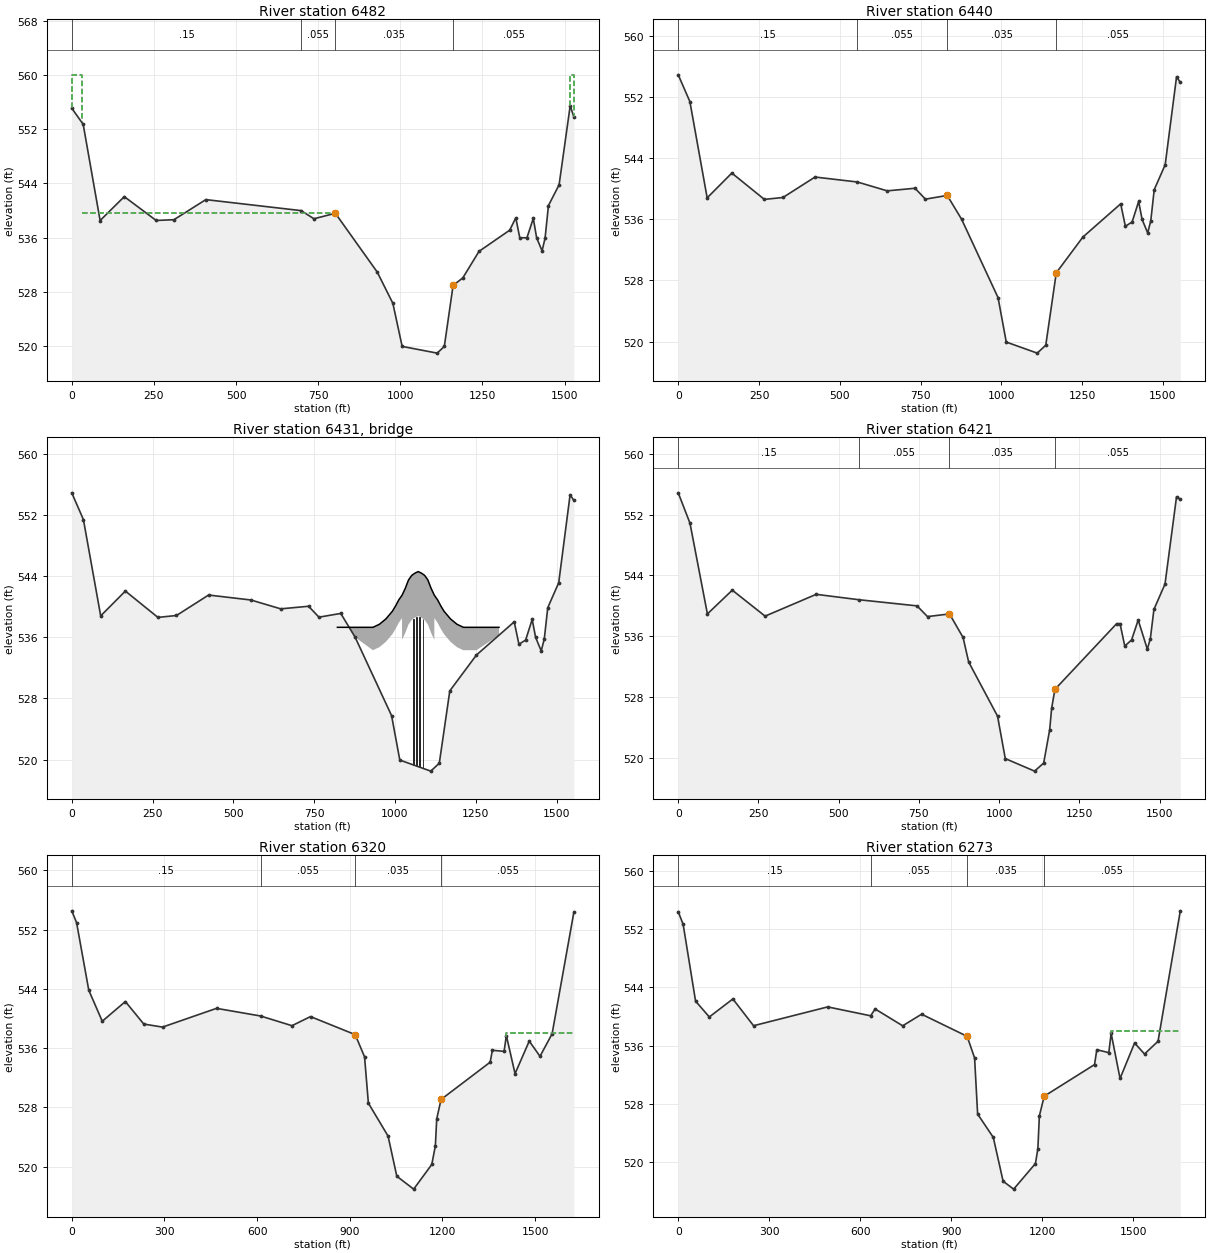
Type RM Length L Ch R = 1 ,6482    ,45,42.4,42
BEGIN DESCRIPTION:
Effective flow limit in LOB set at Clear Fork Levee Loop.
Effective flow limit in LOB set at Water Works Levee.
Trinity Park in LOB.
END DESCRIPTION:
XS GIS Cut Line= 3
 2321103.5022665 6956632.1273921 2321960.9341838 6956369.7928697
 2322530.4534314 6956096.7357618
#Sta/Elev= 30
       0  555.08   34.75  552.71   86.27  538.54  159.84  542.06  256.89  538.55
  310.93  538.66  408.02  541.62  697.96     540  737.22   538.8  802.23  539.61
  929.81  530.95  977.35  526.35 1005.64     520  1112.3  519.01 1134.01     520
 1160.71  528.98 1190.27  530.09  1239.6     534 1333.03  537.12  1351.6  538.94
 1363.65     536 1385.45     536  1404.8  538.85 1415.01     536 1431.58  534.07
  1440.7  535.95 1450.93  540.74 1483.42  543.81 1517.13  555.45 1528.26  553.81
#Mann= 4 ,-1,0
       0     .15       0  697.96    .055       0  802.23    .035       0
 1160.71    .055       0
#XS Ineff= 4 ,-1
       0   29.78     560   29.78  785.24   539.7  1351.6 1517.13  538.94
 1517.13 1528.26     560
Permanent Ineff=
       F       F       F       T
Bank Sta=802.23,1160.71
XS Rating Curve= 0 ,0
Exp/Cntr=0.3,0.1

Type RM Length L Ch R = 1 ,6440    ,18.2,18.2,18
BEGIN DESCRIPTION:
Effective flow limit in LOB set at Clear Fork Levee Loop.
Effective flow limit in LOB set at Water Works Levee.
Trinity Park in LOB.
Interpolated cross-section.
---------------------------------------------------------------------
CDC FW040910-01 TILLEY (LANCASTER) PEDESTRIAN BRIDGE
CROSS-SECTION 6273 - 6440
UPSTREAM END.
---------------------------------------------------------------------
END DESCRIPTION:
XS GIS Cut Line= 4
2321114.046940116956673.422515362321971.478857416956411.08799296
2322540.998105016956138.030885062322563.910733346956127.04538096
#Sta/Elev= 30
       0  554.94   36.06  551.43   89.51  538.82  165.85  542.07  266.54  538.62
  324.06  538.87  423.35  541.55   554.3   540.9  646.59  539.74  732.77  540.08
  764.92  538.65  832.38  539.14  876.88  536.02  989.69  525.75  1015.1  519.93
 1110.93  518.48 1137.35  519.52 1169.85     529 1252.23  533.69 1369.19  538.04
 1383.71   535.1 1404.54  535.66 1424.75  538.35 1435.41     536 1452.71  534.23
 1462.23   535.8 1472.92  539.89 1506.85  543.16 1542.05  554.68 1553.67  553.95
#Mann= 4 ,-1,0
       0     .15       0   554.3    .055       0  832.38    .035       0
 1169.85    .055       0
Bank Sta=832.38,1169.85
XS Rating Curve= 0 ,0
Exp/Cntr=0.3,0.1

Type RM Length L Ch R = 3 ,6431    ,,,
BEGIN DESCRIPTION:
Tilley Pedestrian Bridge
Data from bridge plans.  Concrete paving under bridge at river side slopes.
END DESCRIPTION:
Node Name=Tilley pedestria
Bridge Culvert--1,0,-1,-1, 0
Deck Dist Width WeirC Skew NumUp NumDn MinLoCord MaxHiCord MaxSubmerge Is_Ogee
2.5,13,2.6,0, 31, 31, , , 0.98, 0, 0,0,,
     822     932     942     952     962     972     992    1002    1012    1022
    1022    1032    1042    1052    1062    1072    1082    1092    1102    1112
    1122    1122    1132    1142    1152    1172    1182    1192    1202    1212
    1322
  537.32  537.32  537.52  537.72  538.07  538.42  539.42  540.12  540.92  541.52
  541.52  542.42  543.52  544.12  544.42  544.62  544.42  544.12  543.52  542.42
  541.52  541.52  540.92  540.12  539.42  538.42  538.07  537.72  537.52  537.32
  537.32
  534.32  534.32  534.52  534.72  535.07  535.42  536.42  537.12  537.92  538.52
  535.69  536.59  537.69  538.29  538.59  538.79  538.59  538.29  537.69  536.59
  535.69  538.52  537.92  537.12  536.42  535.42  535.07  534.72  534.52  534.32
  534.32
     822     932     942     952     962     972     992    1002    1012    1022
    1022    1032    1042    1052    1062    1072    1082    1092    1102    1112
    1122    1122    1132    1142    1152    1172    1182    1192    1202    1212
    1322
  537.32  537.32  537.52  537.72  538.07  538.42  539.42  540.12  540.92  541.52
  541.52  542.42  543.52  544.12  544.42  544.62  544.42  544.12  543.52  542.42
  541.52  541.52  540.92  540.12  539.42  538.42  538.07  537.72  537.52  537.32
  537.32
  534.32  534.32  534.52  534.72  535.07  535.42  536.42  537.12  537.92  538.52
  535.69  536.59  537.69  538.29  538.59  538.79  538.59  538.29  537.69  536.59
  535.69  538.52  537.92  537.12  536.42  535.42  535.07  534.72  534.52  534.32
  534.32
Pier Skew, UpSta & Num, DnSta & Num=  ,1057, 2 ,1070, 2 , 0 , 0 , 0 ,,
       2       2
     518     540
       2       2
     518     540
Pier Skew, UpSta & Num, DnSta & Num=  ,1067, 2 ,1080, 2 , 0 , 0 , 0 ,,
       2       2
     518     540
       2       2
     518     540
Pier Skew, UpSta & Num, DnSta & Num=  ,1077, 2 ,1090, 2 , 0 , 0 , 0 ,,
       2       2
     518     540
       2       2
     518     540
Pier Skew, UpSta & Num, DnSta & Num=  ,1087, 2 ,1100, 2 , 0 , 0 , 0 ,,
       2       2
     518     540
       2       2
     518     540
BR Coef=-1 , 0 , 0 ,, 0 ,,,0.8,-1,,0,
WSPro=,,,, 1 ,,,, 0 ,,,, 0 ,,,,-1 ,-1 ,-1 , 0 , 0 , 0 , 0 , 0
BR U #Sta/Elev= 495
       0  554.94     .74  554.91    2.45  554.82    5.03  554.56   11.36  553.93
   12.22  553.86   13.13  553.77   13.43  553.75   14.17  553.67   15.33  553.51
   16.27  553.39   18.88  553.03   19.93  552.91   22.36  552.59   23.02  552.52
    25.1  552.28   29.94  551.86   30.56  551.79   31.35  551.68   32.67  551.57
   34.01  551.51   36.06  551.43   37.11  551.21   37.87  551.02   38.77  550.84
   40.23  550.47   42.24     550   43.01  549.81   44.24  549.52   46.05  549.07
   47.23  548.75   47.87  548.59   49.67   548.1   50.35  547.92    51.8   547.6
   53.12  547.29   55.94  546.66   58.06  546.16   59.63  545.77   60.58  545.52
   63.38  544.82   64.32  544.59   65.89  544.19   68.04  543.66   69.11  543.38
   71.41  542.95   73.66  542.44   75.48  542.06   75.58  542.03   77.52   541.6
   80.35     541   84.43  540.05    87.9  539.24   89.01  538.96   89.51  538.82
   92.33   538.9   101.6  539.15  110.51  539.32  111.07  539.32  113.69  539.67
  118.65  540.27  120.89  540.41   122.8  540.52  126.01  540.72  129.02  540.84
  130.98  540.95  133.34  541.09  134.45  541.16  141.64  541.64  144.92  541.66
  148.36  541.69  148.83  541.69  150.33  541.72  156.25  541.91  157.38  541.96
  161.27  542.01  163.86  542.03  165.27  542.02  165.85  542.07  167.25  542.02
  168.27  541.99  169.66  541.94  171.43  541.91  172.63  541.86  176.23  541.75
  178.31  541.68  181.77  541.55  184.54  541.43  188.12  541.26  191.63  541.09
  192.55  541.04  197.14   540.8  199.24   540.7  204.63  540.45  206.29  540.35
  208.15  540.26  211.46  540.08  212.85  540.05  216.99  539.93  218.39   539.9
   220.2  539.87  224.99   539.8  226.68  539.76  234.14  539.62  248.93  539.17
  255.41  538.99  257.59  538.92  266.54  538.62  287.44  538.71  304.91  538.78
  310.22   538.8  314.56  538.81  316.57  538.82  320.31  538.82   321.6  538.83
  324.06  538.87  327.81  538.95  330.24  538.99  330.43     539  334.29  539.08
  337.25  539.15   346.8  539.41  368.15  540.06  382.66  540.51  387.82  540.64
  421.33  541.53  423.35  541.55  428.73  541.55  430.58  541.54  432.47  541.54
  436.05  541.52  437.71   541.5  443.06  541.47  471.01   541.6   486.4  541.58
  493.78  541.56  497.72  541.56  502.42  541.57  508.73  541.41  509.55  541.41
  512.39  541.39   514.6  541.37  518.71   541.3  519.04  541.29  529.08  541.14
  541.05  540.94     551  540.91  551.92   540.9   554.3   540.9  555.55  540.89
  559.44  540.88  560.68  540.88  562.37   540.9  563.05   540.9  567.19  540.94
  569.47  540.85  574.56  540.68  580.39  540.56   585.3  540.47  585.65  540.46
  587.18  540.44  587.81  540.44   589.9  540.41   590.6  540.41  594.51  540.37
   608.5   540.3  614.26  540.23   618.7  540.23  621.61  540.21  625.47  540.24
   627.1  540.22  627.44  540.23  630.56  540.28  634.29  540.33  635.03  540.32
   639.9  540.04  640.44     540  641.33  539.95  642.94  539.83  643.99  539.76
  646.08  539.75  646.59  539.74  648.24  539.76  649.07  539.76  650.74  539.78
  651.46  539.78  653.01   539.8  653.85   539.8  656.65  539.83  657.61  539.83
   658.1  539.84  659.69  539.85  660.22  539.86  661.02  539.86  664.12  539.89
  664.68  539.89  669.18  540.15  673.12  540.37  675.22  540.27  677.11  540.17
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BR U #Mann= 7
       0     .15   554.3    .055  832.38    .035  888.17    .014  1015.1    .035
 1137.35    .014 1268.37    .055
BR D #Sta/Elev= 495
       0  554.88    2.49  554.74    5.11  554.48   10.41  553.94   11.54  553.83
   12.41  553.76   13.01  553.69   13.64  553.64   14.39  553.56   16.52  553.24
   19.17  552.83   20.24  552.69   22.71  552.33   25.49  551.96    30.4  551.44
   31.03  551.36   31.84  551.23   33.18  551.09   34.54     551   36.62  550.88
   37.69  550.65   38.46  550.46   39.37  550.27   40.12  550.07   44.93  548.91
   46.76  548.45   47.96  548.12   48.84   547.9   50.72  547.38   51.13  547.29
    52.6     547   53.94  546.71   54.64  546.58   56.34  546.23   56.81  546.14
   58.96  545.68   60.56  545.32   61.52  545.09   64.36  544.44   65.32  544.23
   66.91  543.87    69.5  543.29   70.18  543.12   72.52  542.73    74.8  542.26
   76.65  541.91   78.72  541.49    81.6  540.94   85.74  540.07   88.23  539.55
   89.26  539.33    90.9  538.94   93.76  539.02  103.18  539.29  112.23  539.48
  112.79  539.48  115.45  539.81  120.49  540.39  122.77  540.53  124.71  540.64
  127.97  540.84  131.02  540.94  133.01  541.03  135.41  541.15  136.53  541.22
  143.84  541.66  147.17  541.68  150.66  541.71  151.14  541.71  152.66  541.74
  158.68  541.95  159.82  542.01  163.77  542.04   166.4  542.05  166.55  542.04
  167.84  542.03  168.42  542.07  170.88  541.99  172.29  541.93  174.14   541.9
   174.7  541.86  181.08  541.65  184.59  541.51   187.4  541.38  191.04   541.2
  195.54  540.97   200.2  540.71  202.33  540.61  206.51   540.4  207.81  540.34
  207.84  540.33  209.49  540.23  211.38  540.14  213.97  539.99  214.74  539.95
  216.15  539.92  220.36   539.8  221.78  539.77  223.62  539.75  228.48  539.69
   230.2  539.66  237.77  539.54  252.79  539.14  259.37  538.98  261.59  538.92
  270.68  538.65   291.9  538.77  309.64  538.85  312.08  538.87  315.03  538.88
  319.44  538.89  321.48   538.9  325.28   538.9  327.62  538.92  330.55  538.98
  331.02  538.98   332.9  539.02  335.36  539.06  336.99   539.1  339.48  539.14
  342.48  539.21  352.18  539.46  373.86  540.09   388.6  540.52  393.84  540.64
  427.87   541.5  429.92  541.52  438.56  541.52  439.18  541.51  442.82  541.49
   444.5  541.47  449.94  541.44  478.32  541.54  493.95   541.5  501.44  541.47
  510.22  541.47  513.05  541.41  515.77  541.33  517.46  541.32  520.34  541.29
  522.59  541.26  526.76  541.19  527.09  541.18  537.29  541.02  540.92  540.95
  549.45   540.8   560.1  540.81  560.49   540.8  561.55  540.81   562.9  540.81
  564.17  540.81  568.12  540.82  569.38  540.82  571.79  540.87  575.99  540.95
  577.62  540.88  578.31  540.84  583.48  540.63  585.49  540.59   589.4   540.5
  594.38   540.4  594.74  540.38  596.29  540.36  596.93  540.36  598.22  540.33
  599.77  540.32  603.74  540.27  617.94  540.19  623.79  540.12   628.3  540.12
  631.26   540.1  635.18  540.13  636.83  540.11  637.18  540.12  640.35  540.17
  644.13  540.21  644.89   540.2  649.83  539.93  651.28  539.84  652.92  539.72
  653.99  539.66  656.11  539.64  656.63  539.63   658.3  539.66  660.34  539.67
  661.22  539.69  663.49  539.71  664.62  539.73  665.97  539.74  666.84  539.76
  668.84  539.77  670.47   539.8  671.28   539.8  674.43  539.84     675  539.84
  679.57   540.1  681.78  540.22  683.57  540.33   685.7  540.24  687.62  540.15
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BR D #Mann= 7
       0     .15   562.9    .055   845.3    .035  894.61    .014 1019.16    .035
 1138.78    .014 1276.94    .055
BC Design=,, 0 ,, 0 ,,,,,,
BC Use User HTab Curves=0
BC User HTab FreeFlow(D)= 0

Type RM Length L Ch R = 1 ,6421    ,102.7,101.1,100.7
BEGIN DESCRIPTION:
Effective flow limit in LOB set at Clear Fork Levee Loop.
Effective flow limit in LOB set at Water Works Levee.
Trinity Park in LOB.
Interpolated cross-section.
END DESCRIPTION:
XS GIS Cut Line= 4
2321124.627604256956688.193429842321982.059521556956425.85890744
2322551.578769156956152.801799542322584.311095336956137.10822226
#Sta/Elev= 30
       0  554.88   36.62  550.88    90.9  538.94  168.42  542.07  270.68  538.65
  429.92  541.52   562.9  540.81  744.14     540  776.79  538.59   845.3  538.94
  887.64  535.84  904.95  532.62  994.98  525.49 1019.16   519.9 1110.34  518.25
 1138.78  519.31 1157.44  523.68 1163.69  526.54 1173.77  529.01 1365.95  537.65
 1376.73  537.66 1391.51  534.71 1412.72  535.52  1433.3  538.14 1461.77   534.3
 1471.23   535.7 1482.34  539.53 1516.89  542.88 1552.73  554.35 1564.56  554.01
#Mann= 4 ,-1,0
       0     .15       0   562.9    .055       0   845.3    .035       0
 1173.77    .055       0
Bank Sta=845.3,1173.77
XS Rating Curve= 0 ,0
Exp/Cntr=0.3,0.1

Type RM Length L Ch R = 1 ,6320    ,49,47.8,47.8
BEGIN DESCRIPTION:
Effective flow limit in LOB set at Clear Fork Levee Loop.
Effective flow limit in LOB set at Water Works Levee.
Trinity Park in LOB.
Interpolated cross-section.
END DESCRIPTION:
XS GIS Cut Line= 4
 2321180.08376416956772.95082626 2322037.51568146956510.61630386
  2322607.0349296956237.559195962322694.871092186956195.44597716
#Sta/Elev= 30
       0  554.53   15.62  552.93   55.07  543.81    98.7  539.62  173.53  542.28
  233.16  539.24  293.89  538.83  468.72  541.36  611.17  540.33  712.94  539.02
  773.06  540.25  917.79  537.81  948.02  534.81  960.38  528.56 1024.15  524.11
 1052.45  518.69 1107.03  516.95  1165.7  520.28 1177.31   522.8 1181.65  526.43
 1195.75  529.06 1354.67  534.09  1361.9   535.7 1399.77  535.55 1407.17  537.68
 1435.29  532.54 1481.27  536.94 1516.11  534.88 1555.31  537.93 1625.67  554.33
#Mann= 4 ,-1,0
       0     .15       0  611.17    .055       0  917.79    .035       0
 1195.75    .055       0
#XS Ineff= 2 , 0
                         1406.38          538.07
Permanent Ineff=
       F       F
Bank Sta=917.79,1195.75
XS Rating Curve= 0 ,0
Exp/Cntr=0.3,0.1

Type RM Length L Ch R = 1 ,6273    ,12.9,99.8,162.4
BEGIN DESCRIPTION:
Effective flow limit in LOB set at Clear Fork Levee Loop.
Effective flow limit in LOB set at Water Works Levee.
Trinity Park in LOB.
Interpolated cross-section.
---------------------------------------------------------------------
CDC FW040910-01 TILLEY (LANCASTER) PEDESTRIAN BRIDGE
CROSS-SECTION 6273 - 6440
DOWNSTREAM END.
---------------------------------------------------------------------
END DESCRIPTION:
XS GIS Cut Line= 4
2321205.684228266956813.593525862322063.116145566956551.25900346
2322632.635393166956278.201895562322746.657307216956223.53386771
#Sta/Elev= 30
       0  554.36   16.21  552.63   57.13  542.11   102.4  539.94  180.04  542.41
  248.24  538.74  492.58  541.32  634.11   540.1  648.87  541.04   739.7  538.73
  802.08  540.32  952.24  537.28  976.71  534.32  986.72  526.63 1038.35  523.43
 1070.73  517.42 1105.46  516.34 1177.29  519.85 1185.26  521.89 1190.18  526.38
 1206.19  529.08 1371.99  533.41 1379.53  535.45 1419.04  535.05 1426.76  537.69
  1456.1  531.51 1504.07  536.37 1536.74  534.86 1581.31  536.61 1654.71  554.49
#Mann= 4 ,-1,0
       0     .15       0  634.11    .055       0  952.24    .035       0
 1206.19    .055       0
#XS Ineff= 2 , 0
                         1426.88          538.07
Permanent Ineff=
       F       F
Bank Sta=952.24,1206.19
XS Rating Curve= 0 ,0
Exp/Cntr=0.3,0.1

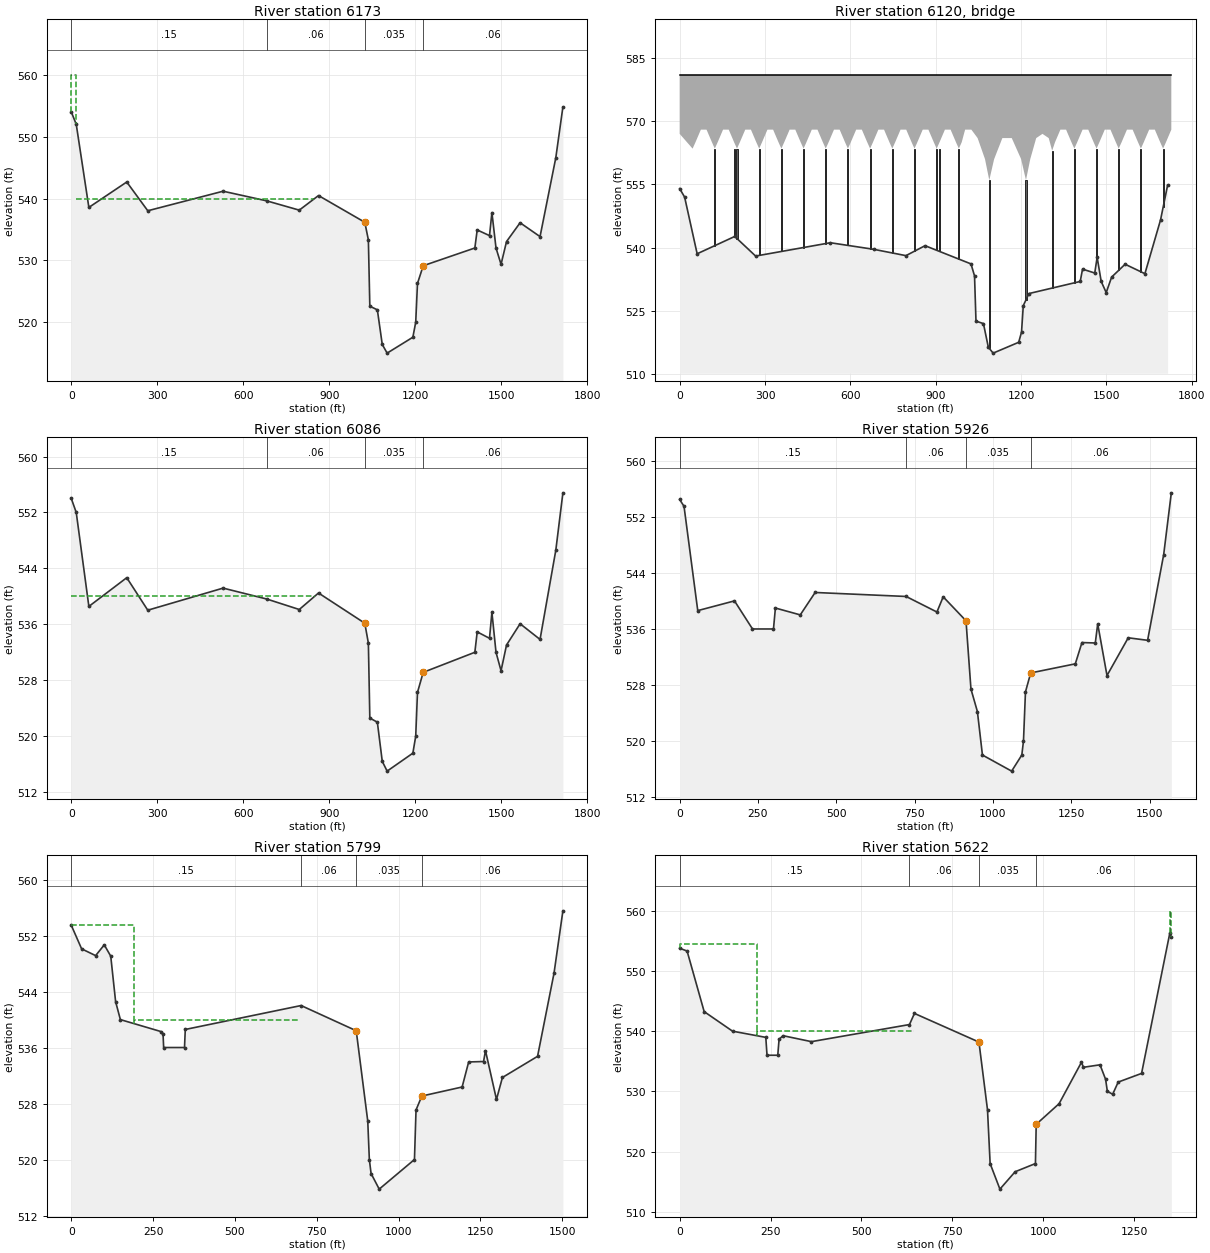
Type RM Length L Ch R = 1 ,6173    ,98.2,87,87
BEGIN DESCRIPTION:
Upstream of Lancaster Avenue.
Copy of cross-section 6085.75
Effective flow limit in LOB set at Clear Fork Levee Loop, set in ROB at Water Works Levee.
Trinity Park in LOB.
**********************************************
This is upper end of Clear Fork bathymetry developed for the Central City project.  From this point upstream, bathymetry from 1975 USACE cross-section survey data used.
**********************************************
END DESCRIPTION:
XS GIS Cut Line= 2
 2321122.2393077 6956632.6691477 2322834.5001845 6956529.2323772
#Sta/Elev= 30
       0  554.02   17.43     552   61.45  538.56  193.65  542.67     267  538.02
  529.81  541.18  682.04  539.62  795.57  538.12  862.69  540.48  1024.2  536.16
 1036.65  533.31 1041.74  522.59 1068.01     522 1085.12   516.4 1102.13     515
 1191.91  517.57 1201.86     520 1208.02  526.27 1228.01  529.13 1408.17     532
 1416.37  534.92 1459.29     534 1467.69  537.72 1481.98     532 1499.57  529.36
 1518.68  533.04 1566.04  536.08 1635.62  533.84  1690.6  546.59 1715.38  554.81
#Mann= 4 ,-1,0
       0     .15       0  682.04     .06       0  1024.2    .035       0
 1228.01     .06       0
#XS Ineff= 3 ,-1
       0   16.33     560   16.33  847.11     540 1467.69 1715.38  537.72
Permanent Ineff=
       F       F       F
Bank Sta=1024.2,1228.01
XS Rating Curve= 0 ,0
Skew Angle= 30
Exp/Cntr=0.5,0.3

Type RM Length L Ch R = 3 ,6120    ,,,
BEGIN DESCRIPTION:
Lancaster Avenue
Bridge data bridge plans, 1975 USACE survey.  Bridge piers and stairway structures represented.
END DESCRIPTION:
Node Name=Lancaster Avenue
Bridge Culvert--1,0,-1,-1, 0
Deck Dist Width WeirC Skew NumUp NumDn MinLoCord MaxHiCord MaxSubmerge Is_Ogee
28,50,2.6,0, 106, 106, , , 0.95, 0, 0,0,,
       0       0    45.5    55.5    74.5    94.5   113.5   123.5   133.5   152.5
   172.5   191.5   201.5   211.5   230.5   250.5   269.5   279.5   289.5   308.5
   328.5   347.5   357.5   367.5   386.5   406.5   425.5   435.5   445.5   464.5
   484.5   503.5   513.5   523.5   542.5   562.5   581.5   591.5   601.5   620.5
   640.5   659.5   669.5   679.5   698.5   718.5   737.5   747.5   757.5   776.5
   796.5   815.5   825.5   835.5   854.5   874.5   893.5   903.5   913.5   932.5
   952.5   971.5   981.5   991.5  1003.5  1025.5  1047.5  1073.5  1088.5  1105.5
  1134.5  1167.5  1200.5  1217.5  1232.5  1253.5  1275.5  1297.5  1309.5  1319.5
  1338.5  1358.5  1377.5  1387.5  1397.5  1416.5  1436.5  1455.5  1465.5  1475.5
  1494.5  1514.5  1533.5  1543.5  1553.5  1572.5  1592.5  1611.5  1621.5  1631.5
  1650.5  1670.5  1689.5  1699.5  1709.5  1728.5
     581     581     581     581     581     581     581     581     581     581
     581     581     581     581     581     581     581     581     581     581
     581     581     581     581     581     581     581     581     581     581
     581     581     581     581     581     581     581     581     581     581
     581     581     581     581     581     581     581     581     581     581
     581     581     581     581     581     581     581     581     581     581
     581     581     581     581     581     581     581     581     581     581
     581     581     581     581     581     581     581     581     581     581
     581     581     581     581     581     581     581     581     581     581
     581     581     581     581     581     581     581     581     581     581
     581     581     581     581     581     581
     500     567   563.5     565     568     568     565   563.5     565     568
     568     565   563.5     565     568     568     565   563.5     565     568
     568     565   563.5     565     568     568     565   563.5     565     568
     568     565   563.5     565     568     568     565   563.5     565     568
     568     565   563.5     565     568     568     565   563.5     565     568
     568     565   563.5     565     568     568     565   563.5     565     568
     568     565   563.5     565     568     568     566     561     556     561
     566     566     561     556     561     566     567     566     563     565
     568     568     565   563.5     565     568     568     565   563.5     565
     568     568     565   563.5     565     568     568     565   563.5     565
     568     568     565   563.5     565     568
       0       0    45.5    55.5    74.5    94.5   113.5   123.5   133.5   152.5
   172.5   191.5   201.5   211.5   230.5   250.5   269.5   279.5   289.5   308.5
   328.5   347.5   357.5   367.5   386.5   406.5   425.5   435.5   445.5   464.5
   484.5   503.5   513.5   523.5   542.5   562.5   581.5   591.5   601.5   620.5
   640.5   659.5   669.5   679.5   698.5   718.5   737.5   747.5   757.5   776.5
   796.5   815.5   825.5   835.5   854.5   874.5   893.5   903.5   913.5   932.5
   952.5   971.5   981.5   991.5  1003.5  1025.5  1047.5  1073.5  1088.5  1105.5
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Pier Skew, UpSta & Num, DnSta & Num=  ,30, 2 ,30, 2 , 0 , 0 , 0 ,,
      30      30
     500     575
      30      30
     500     575
Pier Skew, UpSta & Num, DnSta & Num=  ,123.5, 2 ,123.5, 2 , 0 , 0 , 0 ,,
       4       4
     500   563.5
       4       4
     500   563.5
Pier Skew, UpSta & Num, DnSta & Num=  ,191.5, 2 ,191.5, 2 , 0 , 0 , 0 ,,
       4       4
     500   563.5
       4       4
     500   563.5
Pier Skew, UpSta & Num, DnSta & Num=  ,201.5, 2 ,201.5, 2 , 0 , 0 , 0 ,,
       4       4
     500   563.5
       4       4
     500   563.5
Pier Skew, UpSta & Num, DnSta & Num=  ,279.5, 2 ,279.5, 2 , 0 , 0 , 0 ,,
       4       4
     500   563.5
       4       4
     500   563.5
Pier Skew, UpSta & Num, DnSta & Num=  ,357.5, 2 ,357.5, 2 , 0 , 0 , 0 ,,
       4       4
     500   563.5
       4       4
     500   563.5
Pier Skew, UpSta & Num, DnSta & Num=  ,435.5, 2 ,435.5, 2 , 0 , 0 , 0 ,,
       4       4
     500   563.5
       4       4
     500   563.5
Pier Skew, UpSta & Num, DnSta & Num=  ,513.5, 2 ,513.5, 2 , 0 , 0 , 0 ,,
       4       4
     500   563.5
       4       4
     500   563.5
Pier Skew, UpSta & Num, DnSta & Num=  ,591.5, 2 ,591.5, 2 , 0 , 0 , 0 ,,
       4       4
     500   563.5
       4       4
     500   563.5
Pier Skew, UpSta & Num, DnSta & Num=  ,669.5, 2 ,669.5, 2 , 0 , 0 , 0 ,,
       4       4
     500   563.5
       4       4
     500   563.5
Pier Skew, UpSta & Num, DnSta & Num=  ,747.5, 2 ,747.5, 2 , 0 , 0 , 0 ,,
       4       4
     500   563.5
       4       4
     500   563.5
Pier Skew, UpSta & Num, DnSta & Num=  ,825.5, 2 ,825.5, 2 , 0 , 0 , 0 ,,
       4       4
     500   563.5
       4       4
     500   563.5
Pier Skew, UpSta & Num, DnSta & Num=  ,903.5, 2 ,903.5, 2 , 0 , 0 , 0 ,,
       4       4
     500   563.5
       4       4
     500   563.5
Pier Skew, UpSta & Num, DnSta & Num=  ,913.5, 2 ,913.5, 2 , 0 , 0 , 0 ,,
       4       4
     500   563.5
       4       4
     500   563.5
Pier Skew, UpSta & Num, DnSta & Num=  ,981.5, 2 ,981.5, 2 , 0 , 0 , 0 ,,
     4.5     4.5
     500   563.5
     4.5     4.5
     500   563.5
Pier Skew, UpSta & Num, DnSta & Num=  ,1088.5, 2 ,1088.5, 2 , 0 , 0 , 0 ,,
     4.5     4.5
     500     556
     4.5     4.5
     500     556
Pier Skew, UpSta & Num, DnSta & Num=  ,1217.5, 2 ,1217.5, 2 , 0 , 0 , 0 ,,
     4.5     4.5
     500     556
     4.5     4.5
     500     556
Pier Skew, UpSta & Num, DnSta & Num=  ,1309.5, 2 ,1309.5, 2 , 0 , 0 , 0 ,,
     4.5     4.5
     500     563
     4.5     4.5
     500     563
Pier Skew, UpSta & Num, DnSta & Num=  ,1387.5, 2 ,1387.5, 2 , 0 , 0 , 0 ,,
       4       4
     500   563.5
       4       4
     500   563.5
Pier Skew, UpSta & Num, DnSta & Num=  ,1465.5, 2 ,1465.5, 2 , 0 , 0 , 0 ,,
       4       4
     500   563.5
       4       4
     500   563.5
Pier Skew, UpSta & Num, DnSta & Num=  ,1543.5, 2 ,1543.5, 2 , 0 , 0 , 0 ,,
       4       4
     500   563.5
       4       4
     500   563.5
Pier Skew, UpSta & Num, DnSta & Num=  ,1621.5, 2 ,1621.5, 2 , 0 , 0 , 0 ,,
       4       4
     500   563.5
       4       4
     500   563.5
Pier Skew, UpSta & Num, DnSta & Num=  ,1699.5, 2 ,1699.5, 2 , 0 , 0 , 0 ,,
       4       4
     500   563.5
       4       4
     500   563.5
BR Coef=-1 , 0 , 0 ,, 0 ,,,0.8,-1,,0,
WSPro=,,,, 1 ,,,, 0 ,,,, 0 ,,,,-1 ,-1 ,-1 , 0 , 0 , 0 , 0 , 0
BC Design=,, 0 ,, 0 ,,,,,,
BC Use User HTab Curves=0
BC User HTab FreeFlow(D)= 0

Type RM Length L Ch R = 1 ,6086    ,221.1,160,115.9
BEGIN DESCRIPTION:
Downstream of Lancaster Avenue.
Effective flow limit in LOB set at Clear Fork Levee Loop.
Effective flow limit in ROB set at Water Works Levee.
Trinity Park in LOB.
END DESCRIPTION:
XS GIS Cut Line= 2
 2321174.7701495 6956712.9205276 2322886.9949513 6956608.8995747
#Sta/Elev= 30
       0  554.02   17.43     552   61.45  538.56  193.65  542.67     267  538.02
  529.81  541.18  682.04  539.62  795.57  538.12  862.69  540.48  1024.2  536.16
 1036.65  533.31 1041.74  522.59 1068.01     522 1085.12   516.4 1102.13     515
 1191.91  517.57 1201.86     520 1208.02  526.27 1228.01  529.13 1408.17     532
 1416.37  534.92 1459.29     534 1467.69  537.72 1481.98     532 1499.57  529.36
 1518.68  533.04 1566.04  536.08 1635.62  533.84  1690.6  546.59 1715.38  554.81
#Mann= 4 ,-1,0
       0     .15       0  682.04     .06       0  1024.2    .035       0
 1228.01     .06       0
#XS Ineff= 2 , 0
          847.11     540 1467.69          537.72
Permanent Ineff=
       F       F
Bank Sta=1024.2,1228.01
XS Rating Curve= 0 ,0
Skew Angle= 30
Exp/Cntr=0.5,0.3

Type RM Length L Ch R = 1 ,5926    ,167.9,126.7,97.6
BEGIN DESCRIPTION:
Effective flow limit in LOB set at Clear Fork Levee Loop.
Effective flow limit in ROB set at Water Works Levee.
Trinity Park in LOB.
END DESCRIPTION:
XS GIS Cut Line= 3
 2321376.8412065 6957034.6485175 2322230.9654203 6956830.7609785
 2322889.2044946 6956619.8645824
#Sta/Elev= 30
       0  554.49    13.9  553.51   57.72  538.62  174.97  540.01  232.44     536
  299.45     536  305.55  538.99  384.93  538.01   432.4  541.21  722.83  540.64
  821.15  538.42  841.14  540.59  913.94  537.17  929.76  527.42   950.3  524.21
  966.39     518 1059.62   515.7 1092.11     518 1097.41     520 1103.74  527.01
 1120.46  529.72 1262.83  531.02 1284.05  534.06 1326.65     534 1334.34  536.73
    1364  529.35 1431.76  534.74 1493.59  534.38 1544.84  546.59 1569.32  555.44
#Mann= 4 ,-1,0
       0     .15       0  722.83     .06       0  913.94    .035       0
 1120.46     .06       0
#XS Ineff= 2 , 0
          746.78     540 1334.34          536.73
Permanent Ineff=
       F       F
Bank Sta=913.94,1120.46
XS Rating Curve= 0 ,0
Exp/Cntr=0.3,0.1

Type RM Length L Ch R = 1 ,5799    ,176.8,176.6,175.5
BEGIN DESCRIPTION:
Effective flow limit in LOB set at Clear Fork Levee Loop.
Effective flow limit in ROB set at Water Works Levee.
Trinity Park in LOB.
END DESCRIPTION:
XS GIS Cut Line= 2
 2321590.6550968 6957380.6170539  2322893.797166 6956634.3733636
#Sta/Elev= 30
       0  553.48   31.65   550.1   74.46  549.13  100.85  550.67  120.63  549.05
  135.55  542.54  150.07  539.99  274.13  538.28  280.34  537.95  282.26     536
  345.94     536  348.29  538.58  702.04     542  870.41   538.4  905.67  525.48
  910.47     520  915.78     518  940.65  515.77 1048.31     520 1053.08  527.08
 1070.87  529.07 1193.89  530.36 1213.87  533.94 1259.36     534  1265.2  535.56
 1298.82  528.58 1316.94  531.72 1424.27  534.74 1474.51   546.6 1501.69  555.53
#Mann= 4 ,-1,0
       0     .15       0  702.04     .06       0  870.41    .035       0
 1070.87     .06       0
#XS Ineff= 3 ,-1
       0  192.09 553.484  192.09     700     540  1265.2 1501.69  535.56
Permanent Ineff=
       F       F       F
Bank Sta=870.41,1070.87
XS Rating Curve= 0 ,0
Exp/Cntr=0.3,0.1

Type RM Length L Ch R = 1 ,5622    ,203.6,200.1,197.7
BEGIN DESCRIPTION:
Effective flow limit in LOB set at Clear Fork Levee Loop.
Effective flow limit in ROB set at Water Works Levee.
Trinity Park in LOB.
END DESCRIPTION:
XS GIS Cut Line= 2
 2321750.1053289 6957496.7937358 2322920.6177599 6956819.5685864
#Sta/Elev= 30
       0  553.79   20.44  553.31   67.37  543.25  145.41     540   236.9  538.97
  240.23     536  269.81     536  273.42  538.65  284.24  539.25  362.42  538.26
  632.07   541.1  645.75  542.95  823.17  538.19  846.72  526.92  853.92     518
  880.84  513.75  922.71  516.64  978.56     518  980.66  524.52  1043.6  527.95
 1105.13  534.83 1110.61     534 1156.19  534.41 1171.54     532 1176.34     530
 1190.98  529.52 1206.19  531.54 1270.46  532.98 1348.18  556.31 1352.31  555.65
#Mann= 4 ,-1,0
       0     .15       0  632.07     .06       0  823.17    .035       0
  980.66     .06       0
#XS Ineff= 3 ,-1
       0  213.87 554.416  213.87     645     540  1348.3 1352.31     560
Permanent Ineff=
       F       F       T
Bank Sta=823.17,980.66
XS Rating Curve= 0 ,0
Exp/Cntr=0.3,0.1

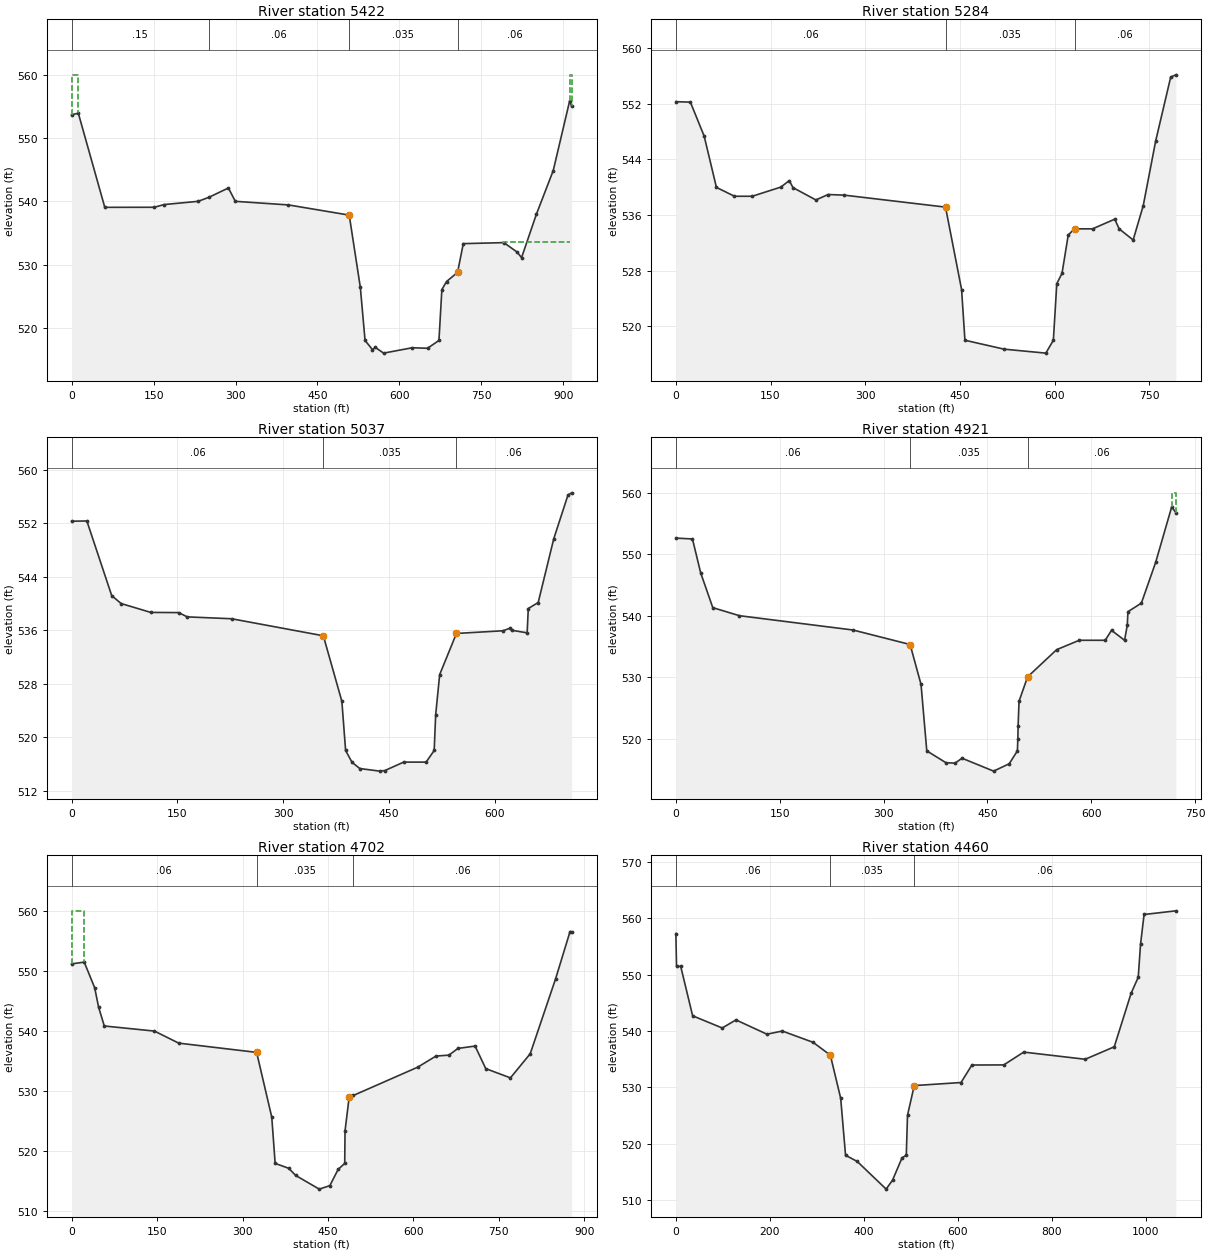
Type RM Length L Ch R = 1 ,5422    ,139.8,137.9,137.5
BEGIN DESCRIPTION:
Effective flow limit in LOB set at Clear Fork Levee Loop.
Effective flow limit in ROB set at Water Works Levee.
Trinity Park in LOB.
END DESCRIPTION:
XS GIS Cut Line= 3
 2322144.7631559 6957512.8196658  2322927.405844 6957038.5498316
 2322927.7067329 6957038.3689871
#Sta/Elev= 30
       0   553.7   12.21  553.92   60.63  539.05   151.2  539.06  169.37  539.49
  231.61     540   251.3  540.64  286.97  542.11  299.61     540  396.94  539.43
  508.17  537.82  528.54  526.38  537.15     518  550.76  516.55  556.03   516.9
  571.13     516  623.47  516.85  651.55  516.77  672.43     518  677.78  526.04
  686.33  527.32  706.49  528.76     717  533.31  791.31  533.47  815.15     532
  823.71   531.1  851.01     538  881.63  544.85  911.78  555.89  915.48  555.01
#Mann= 4 ,-1,0
       0     .15       0   251.3     .06       0  508.17    .035       0
  706.49     .06       0
#XS Ineff= 3 ,-1
       0   12.21     560  789.03  911.78   533.5  911.78  915.48     560
Permanent Ineff=
       T       F       T
Bank Sta=508.17,706.49
XS Rating Curve= 0 ,0
Exp/Cntr=0.3,0.1

Type RM Length L Ch R = 1 ,5284    ,241.4,247.3,251.9
BEGIN DESCRIPTION:
Effective flow limit in LOB set at Clear Fork Levee Loop.
Effective flow limit in ROB set at Water Works Levee.
END DESCRIPTION:
XS GIS Cut Line= 3
 2322290.5398619 6957591.4411122 2322946.0849372 6957185.2342601
 2322963.8432145 6957174.1857658
#Sta/Elev= 30
       0  552.26   22.96   552.2    44.8  547.32   64.24  539.95   92.85  538.68
  120.92  538.68  166.38     540  179.59  540.93  185.54  539.92  221.76  538.15
  241.19  538.93  266.71  538.84  427.13  537.12  452.59  525.28  457.87     518
  519.92  516.72  586.06  516.15  597.98     518   603.4  526.13  611.69  527.61
  621.54  533.12  631.52     534  660.04     534  695.22  535.39  702.18     534
  724.36   532.4  740.33  537.33  760.12  546.65  783.85   555.8  792.11  556.12
#Mann= 3 ,-1,0
       0     .06       0  427.13    .035       0  631.52     .06       0
Bank Sta=427.13,631.52
XS Rating Curve= 0 ,0
Exp/Cntr=0.3,0.1

Type RM Length L Ch R = 1 ,5037    ,108.3,116.5,124.4
BEGIN DESCRIPTION:
Effective flow limit in LOB set at Clear Fork Levee Loop.
Effective flow limit in ROB set at Water Works Levee.
END DESCRIPTION:
XS GIS Cut Line= 2
 2322493.5415873 6957740.0248612  2323107.149676 6957384.7496414
#Sta/Elev= 30
       0  552.32   21.53  552.36   56.76  541.19   70.05     540  112.09  538.67
   151.7  538.64  163.87     538  226.76  537.72  356.86  535.17  383.14  525.36
  388.45     518  397.57  516.23  408.55   515.3  436.72  514.91  444.25     515
  470.74  516.26  502.61  516.26  514.04     518  516.19  523.38  521.82  529.36
  545.61  535.52  611.57  535.92  621.11  536.29  623.91     536  645.87  535.61
  647.48  539.25  661.53  540.15  683.59  549.69  703.79  556.25  709.04  556.57
#Mann= 3 ,-1,0
       0     .06       0  356.86    .035       0  545.61     .06       0
Bank Sta=356.86,545.61
XS Rating Curve= 0 ,0
Exp/Cntr=0.3,0.1

Type RM Length L Ch R = 1 ,4921    ,177.1,218.8,265.7
BEGIN DESCRIPTION:
Effective flow limit in LOB set at Clear Fork Levee Loop.
Effective flow limit in ROB set at Water Works Levee.
END DESCRIPTION:
XS GIS Cut Line= 2
  2322560.430701 6957813.7147635 2323200.9359994 6957479.8348039
#Sta/Elev= 30
       0  552.63   23.95  552.49   35.82  546.97    53.3  541.31   91.76     540
  255.87  537.67  338.33  535.31  354.12  528.81  362.42     518  390.12  516.07
  403.25     516  413.34   516.8  458.96   514.7  481.52   515.9  493.32     518
  493.97     520  494.34     522  495.67  526.07  508.03  530.04     550  534.47
  582.69     536  620.19     536  629.26  537.62  648.14     536  652.08  538.48
  652.99  540.65  672.38  542.04  692.98  548.66   716.2  557.71   722.3  556.77
#Mann= 3 ,-1,0
       0     .06       0  338.33    .035       0  508.03     .06       0
#XS Ineff= 2 , 0
                           716.2             560
Permanent Ineff=
       F       T
Bank Sta=338.33,508.03
XS Rating Curve= 0 ,0
Exp/Cntr=0.3,0.1

Type RM Length L Ch R = 1 ,4702    ,201.3,241.4,285.7
BEGIN DESCRIPTION:
Effective flow limit in LOB set at Clear Fork Levee Loop.
Effective flow limit in ROB set at Water Works Levee.
END DESCRIPTION:
XS GIS Cut Line= 2
 2322622.6520831 6957914.0298958 2323475.5548515 6957705.5044419
#Sta/Elev= 30
       0  551.18   22.08  551.47   40.41   547.2   47.24     544   57.27  540.85
   145.4     540  187.92     538  324.78  536.46  351.35  525.69   357.3     518
  381.23  517.18  393.31     516  434.74  513.72  453.33   514.3  467.88     517
  479.46     518  480.01  523.41  487.24     529  494.68   529.3   607.6     534
  639.76  535.85  662.36     536  678.31  537.12   708.4  537.51  727.12  533.76
  770.43  532.22  805.17  536.23   849.8  548.71  875.12  556.56  878.02  556.49
#Mann= 3 ,-1,0
       0     .06       0  324.78    .035       0  494.68     .06       0
#XS Ineff= 2 , 0
           22.08     560
Permanent Ineff=
       T       F
Bank Sta=324.78,487.24
XS Rating Curve= 0 ,0
Exp/Cntr=0.3,0.1

Type RM Length L Ch R = 1 ,4460    ,114.2,114.2,110.7
BEGIN DESCRIPTION:
Upstream of 7th Street.
Copy of cross-section 4346.114
Effective flow limit in LOB set at Clear Fork Levee Loop.
END DESCRIPTION:
XS GIS Cut Line= 3
  2322663.331196 6958043.8410829 2323534.6548541 6958046.8198355
 2323727.7237333 6958047.4798708
#Sta/Elev= 30
       0  557.26    1.36  551.49   10.28  551.45   35.63   542.7   98.66  540.54
  127.89  541.97  193.86  539.44  226.48     540   292.1     538  328.78  535.73
  350.79   528.1  361.16     518  386.01   516.9  447.58     512  461.19  513.59
  481.45  517.55  490.48     518  493.05  525.09   507.4  530.34  606.99  530.88
  630.09  533.98  697.99     534  740.38  536.27  871.33     535  933.16  537.21
  969.12  546.71  984.21  549.52  989.06  555.36  996.63  560.64  1064.4  561.29
#Mann= 3 ,-1,0
       0     .06       0  328.78    .035       0   507.4     .06       0
Bank Sta=328.78,507.4
XS Rating Curve= 0 ,0
Exp/Cntr=0.5,0.3