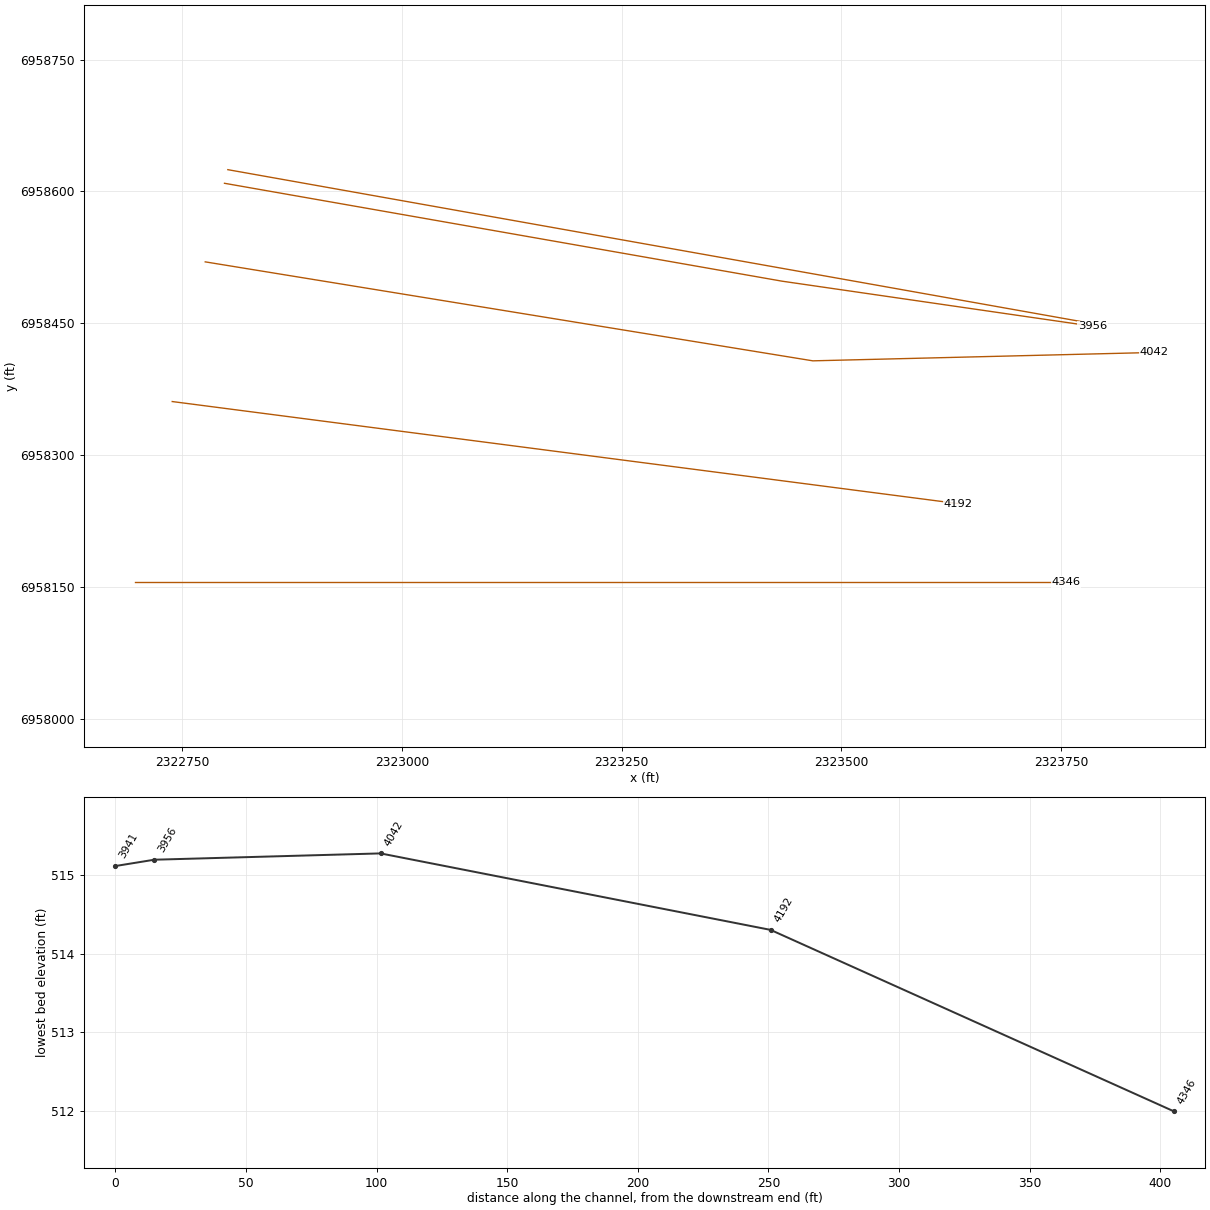
HEC-RAS study CDC_Consolidated_Model.prj: Upper Trinity CDC Consolidated Model

--- CDC_Consolidated_Model.g11 (geometry) --- (continued)

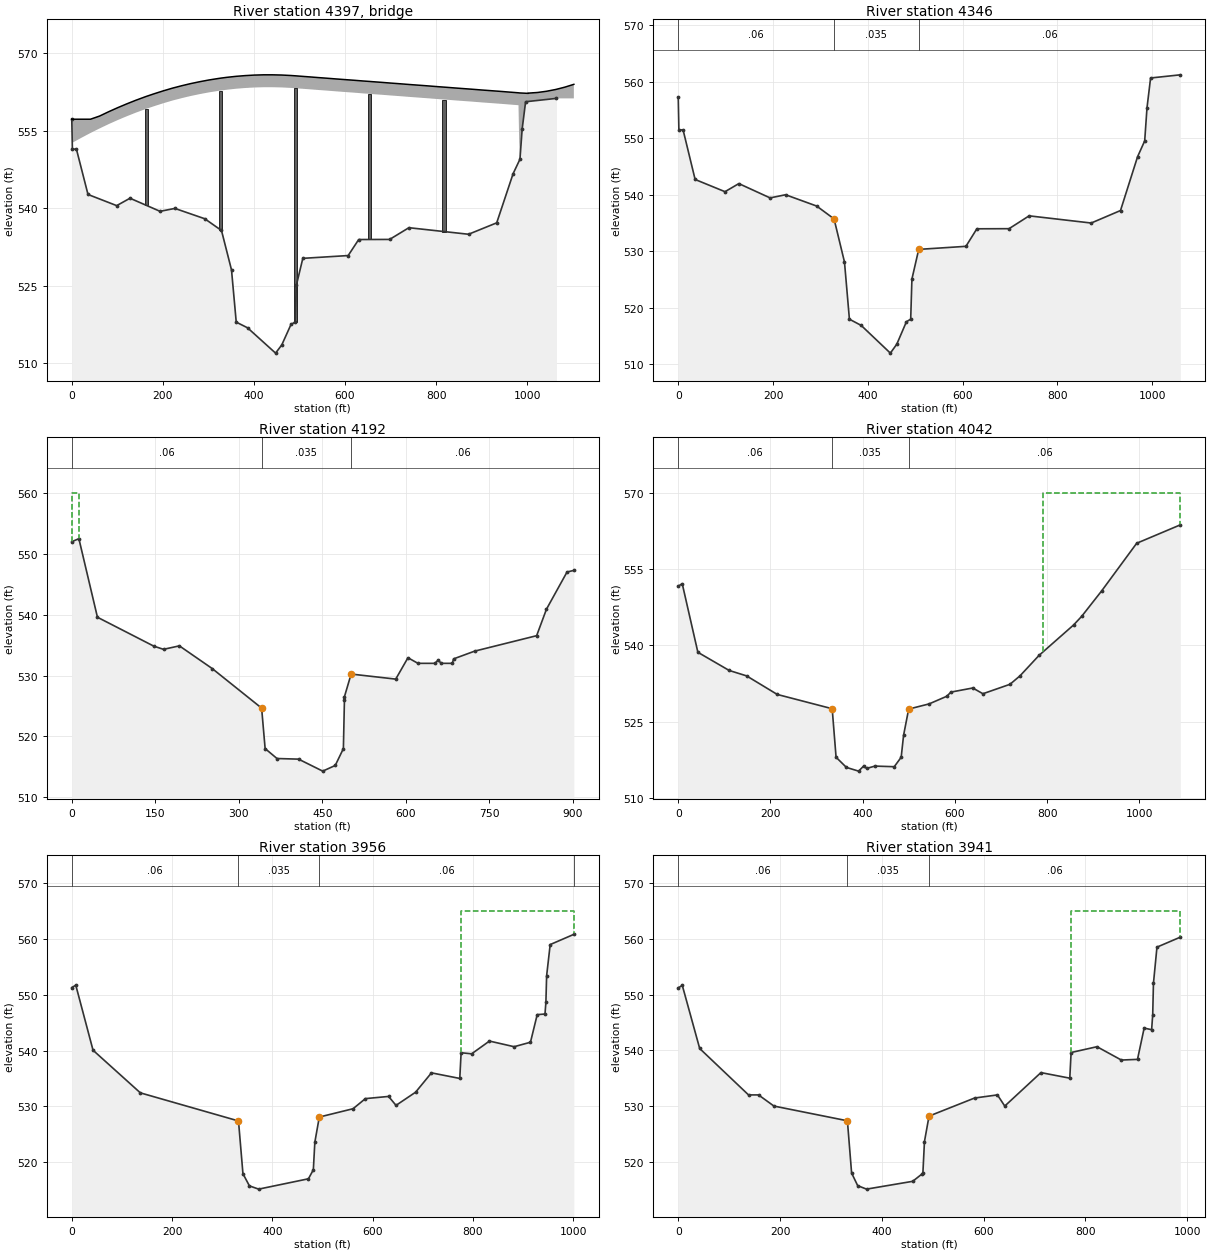
Type RM Length L Ch R = 3 ,4397    ,,,
BEGIN DESCRIPTION:
7th Street
Data from bridge plans and hydraulic report 2010.
------------------------------
CDC FW062310-01
------------------------------
END DESCRIPTION:
Node Name=7th Street
Bridge Culvert--1,0,-1,-1, 0
Deck Dist Width WeirC Skew NumUp NumDn MinLoCord MaxHiCord MaxSubmerge Is_Ogee
19,88,2.6,0, 61, 61, , , 0.98, 0, 0,0,,
       0       1      21      41      61      81     101     121     141     161
   163.5     181     201     221     241     261     281     301     321     327
     341     361     381     401     421     441     461     481     491     501
     521     541     561     581     621     641     654     661     681     701
     721     741     781     801   817.5     821     841     861     881     901
     921     941     981  982.55 1002.55 1002.55 1022.55 1042.55 1062.55 1082.55
 1102.55
  557.26  557.26  557.26  557.26  557.87  558.71   559.5  560.24  560.94  561.59
  561.67  562.19  562.75  563.27  563.73  564.15  564.52  564.85  565.13  565.21
  565.37  565.56   565.7   565.8  565.85  565.85  565.81  565.72  565.66  565.59
  565.46  565.32  565.19  565.05  564.79  564.65  564.57  564.52  564.39  564.25
  564.12  563.98  563.72  563.58  563.47  563.45  563.31  563.18  563.05  562.91
  562.78  562.65  562.37  562.35  562.26  562.31  562.43  562.67  563.01  563.46
  564.01
  552.65  552.69  553.66  554.59  555.47  556.31   557.1  557.84  558.54  559.19
  559.27  559.79  560.35  560.87  561.33  561.75  562.12  562.45  562.73  562.81
  562.97  563.16   563.3   563.4  563.45  563.45  563.41  563.32  563.26  563.19
  563.06  562.92  562.79  562.65  562.39  562.25  562.17  562.12  561.99  561.85
  561.72  561.58  561.32  561.18  561.07  561.05  560.91  560.78  560.65  560.51
  560.38  560.25  559.97
       0       1      21      41      61      81     101     121     141     161
   163.5     181     201     221     241     261     281     301     321     327
     341     361     381     401     421     441     461     481     491     501
     521     541     561     581     621     641     654     661     681     701
     721     741     781     801   817.5     821     841     861     881     901
     921     941     981  982.55 1002.55 1002.55 1022.55 1042.55 1062.55 1082.55
 1102.55
  557.26  557.26  557.26  557.26  557.87  558.71   559.5  560.24  560.94  561.59
  561.67  562.19  562.75  563.27  563.73  564.15  564.52  564.85  565.13  565.21
  565.37  565.56   565.7   565.8  565.85  565.85  565.81  565.72  565.66  565.59
  565.46  565.32  565.19  565.05  564.79  564.65  564.57  564.52  564.39  564.25
  564.12  563.98  563.72  563.58  563.47  563.45  563.31  563.18  563.05  562.91
  562.78  562.65  562.37  562.35  562.26  562.31  562.43  562.67  563.01  563.46
  564.01
  552.65  552.69  553.66  554.59  555.47  556.31   557.1  557.84  558.54  559.19
  559.27  559.79  560.35  560.87  561.33  561.75  562.12  562.45  562.73  562.81
  562.97  563.16   563.3   563.4  563.45  563.45  563.41  563.32  563.26  563.19
  563.06  562.92  562.79  562.65  562.39  562.25  562.17  562.12  561.99  561.85
  561.72  561.58  561.32  561.18  561.07  561.05  560.91  560.78  560.65  560.51
  560.38  560.25  559.97
Pier Skew, UpSta & Num, DnSta & Num=  ,163.5, 2 ,163.5, 2 , 0 , 0 , 0 ,,
       7       7
     510     565
       7       7
     510     565
Pier Skew, UpSta & Num, DnSta & Num=  ,327, 2 ,327, 2 , 0 , 0 , 0 ,,
       7       7
     510     565
       7       7
     510     565
Pier Skew, UpSta & Num, DnSta & Num=  ,490.5, 2 ,490.5, 2 , 0 , 0 , 0 ,,
       7       7
     510     565
       7       7
     510     565
Pier Skew, UpSta & Num, DnSta & Num=  ,654, 2 ,654, 2 , 0 , 0 , 0 ,,
       7       7
     510     565
       7       7
     510     565
Pier Skew, UpSta & Num, DnSta & Num=  ,817.5, 2 ,817.5, 2 , 0 , 0 , 0 ,,
       7       7
  535.27     565
       7       7
  535.27     565
BR Coef=-1 , 0 , 0 ,, 0 ,,,0.8,-1,,0,
WSPro=,,,, 1 ,,,, 0 ,,,, 0 ,,,,-1 ,-1 ,-1 , 0 , 0 , 0 , 0 , 0
BC Design=,, 0 ,, 0 ,,,,,,
BC Use User HTab Curves=0
BC User HTab FreeFlow(D)= 0

Type RM Length L Ch R = 1 ,4346    ,175.8,154.3,131.9
BEGIN DESCRIPTION:
Downstream of 7th Street.
Effective flow limit in LOB set at Clear Fork Levee Loop.
END DESCRIPTION:
XS GIS Cut Line= 2
 2322696.0002607 6958155.65520022323755.35167257 6958155.6552002
#Sta/Elev= 30
       0  557.26    1.36  551.49   10.28  551.45   35.63   542.7   98.66  540.54
  127.89  541.97  193.86  539.44  226.48     540   292.1     538  328.78  535.73
  350.79   528.1  361.16     518  386.01   516.9  447.58     512  461.19  513.59
  481.45  517.55  490.48     518  493.05  525.09   507.4  530.34  606.99  530.88
  630.09  533.98  697.99     534  740.38  536.27  871.33     535  933.16  537.21
  969.12  546.71  984.21  549.52  989.06  555.36  996.63  560.64 1059.35   561.2
#Mann= 3 ,-1,0
       0     .06       0  328.78    .035       0   507.4     .06       0
Bank Sta=328.78,507.4
XS Rating Curve= 0 ,0
Exp/Cntr=0.5,0.3

Type RM Length L Ch R = 1 ,4192    ,155.1,149.3,144.3
BEGIN DESCRIPTION:
Effective flow limit in LOB set at Clear Fork Levee Loop.
END DESCRIPTION:
XS GIS Cut Line= 2
 2322738.7456673 6958360.9657713 2323633.0028308 6958244.8343329
#Sta/Elev= 30
       0  551.97   12.78  552.47   46.11  539.57  147.41  534.82  164.77   534.3
  193.29  534.87  252.14  531.15  340.99  524.65   347.3     518  368.63  516.37
  407.32  516.27  450.73   514.3  473.23  515.23  487.85     518  489.74     526
  489.78  526.53  501.76  530.24  581.86  529.41  603.82  532.92  621.79     532
  652.14     532  657.97  532.52  663.75     532  683.56     532   685.7  532.73
  723.49     534  834.94  536.54  852.63   540.9  889.54     547  901.77  547.26
#Mann= 3 ,-1,0
       0     .06       0  340.99    .035       0  501.76     .06       0
#XS Ineff= 2 , 0
           12.78     560
Permanent Ineff=
       T       F
Bank Sta=340.99,501.76
XS Rating Curve= 0 ,0
Exp/Cntr=0.3,0.1

Type RM Length L Ch R = 1 ,4042    ,89.1,86.6,85
BEGIN DESCRIPTION:
Effective flow limit in LOB set at Clear Fork Levee Loop.
Pier 1 site in ROB - ineffective flow due to buildings.
END DESCRIPTION:
XS GIS Cut Line= 3
  2322776.288717 6958519.8445608 2323467.3844416 6958407.2679151
 2323855.9508569  6958416.822725
#Sta/Elev= 30
       0  551.64    8.66  552.13   42.59  538.64  110.42  535.07  148.27     534
  214.74  530.35  333.88  527.54  342.32     518  364.77     516  391.13  515.27
  402.38  516.29  408.51   515.8  426.61  516.26  468.48  516.14  483.52     518
  488.74  522.33  499.75  527.47  544.09  528.49  582.65     530   591.3  530.81
  638.76  531.62   660.8  530.49  719.37  532.34  741.13     534  782.49  538.03
  857.28     544  874.87   545.7   918.2   550.7  994.27  560.08 1088.89   563.7
#Mann= 3 ,-1,0
       0     .06       0  333.88    .035       0  499.75     .06       0
#XS Ineff= 2 , 0
                          790.44             570
Permanent Ineff=
       F       F
Bank Sta=333.88,499.75
XS Rating Curve= 0 ,0
Exp/Cntr=0.3,0.1

Type RM Length L Ch R = 1 ,3956    ,15.4,14.9,14.6
BEGIN DESCRIPTION:
Added cross-section.
END DESCRIPTION:
XS GIS Cut Line= 3
  2322798.186575 6958609.2262315 2323432.5236072 6958497.8595678
 2323785.3738193 6958446.6822452
#Sta/Elev= 30
       0  551.27    8.01  551.69   42.43  540.05  136.82  532.42  332.59  527.39
  341.47  517.95  354.38  515.77  372.86  515.19  472.13  517.04  481.91  518.66
  484.89  523.59  493.77  528.09  561.13  529.58  585.77  531.39     632  531.78
  646.82  530.18   685.9  532.54  717.52     536  774.01     535  776.68   539.6
  797.72  539.41  833.19  541.69  882.43  540.68  915.04  541.48  928.48  546.42
  943.99  546.53   945.8  548.61  947.27  553.38  954.37  558.96 1001.56  560.79
#Mann= 4 ,-1,0
       0     .06       0  332.59    .035       0  493.77     .06       0
 1001.56     .06       0
#XS Ineff= 2 , 0
                          776.68             565
Permanent Ineff=
       F       F
Bank Sta=332.59,493.77
XS Rating Curve= 0 ,0
Exp/Cntr=0.3,0.1

Type RM Length L Ch R = 1 ,3941    ,289.9,286.4,284.7
BEGIN DESCRIPTION:
Effective flow limit in LOB set at Clear Fork Levee Loop.
Pier 1 site in ROB - ineffective flow due to buildings.
END DESCRIPTION:
XS GIS Cut Line= 2
 2322801.9818527 6958624.7176216 2323773.1415975 6958451.8574167
#Sta/Elev= 30
       0   551.2    8.01  551.62   42.16  540.32   138.1     532  157.74     532
  188.02     530  332.37  527.36  340.61     518  352.59  515.73  369.95  515.11
  460.62  516.51  479.28  517.85  480.67     518  483.74  523.63  492.73   528.2
  582.18  531.44  627.12     532  641.53     530  712.58     536  769.28     535
  771.87   539.6  822.73  540.64   870.6  538.25  902.31  538.37  915.37  543.98
  930.07  543.69  932.21  546.41  933.64     552  940.54  558.49  986.42  560.28
#Mann= 3 ,-1,0
       0     .06       0  332.37    .035       0  492.73     .06       0
#XS Ineff= 2 , 0
                          771.87             565
Permanent Ineff=
       F       F
Bank Sta=332.37,492.73
XS Rating Curve= 0 ,0
Exp/Cntr=0.3,0.1