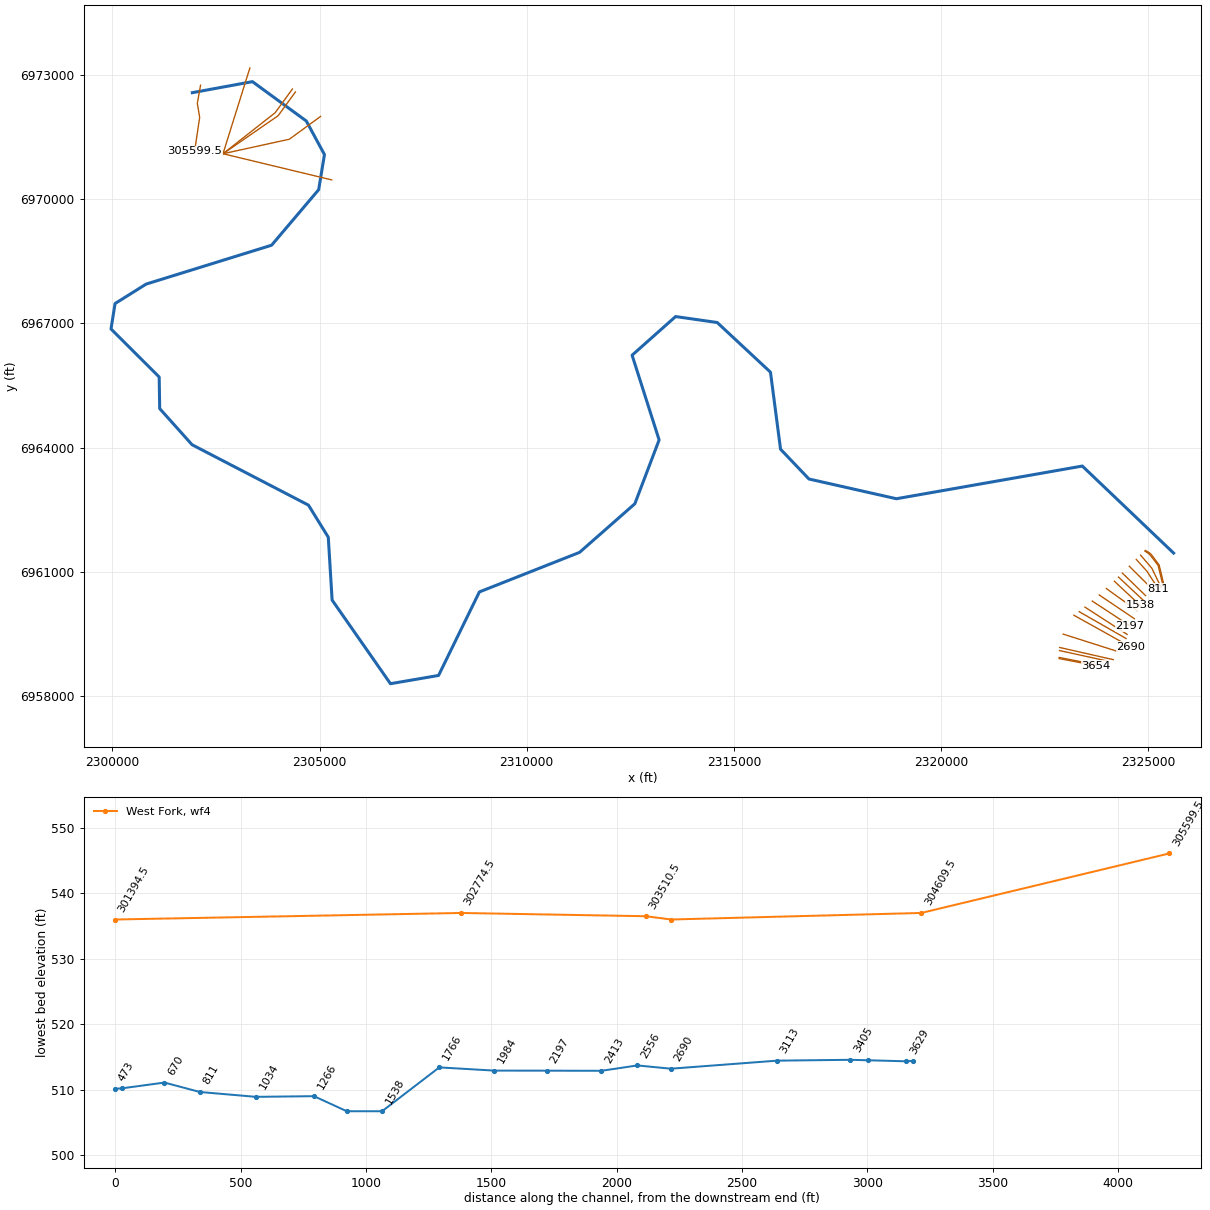
HEC-RAS study CDC_Consolidated_Model.prj: Upper Trinity CDC Consolidated Model

--- CDC_Consolidated_Model.g11 (geometry) --- (continued)

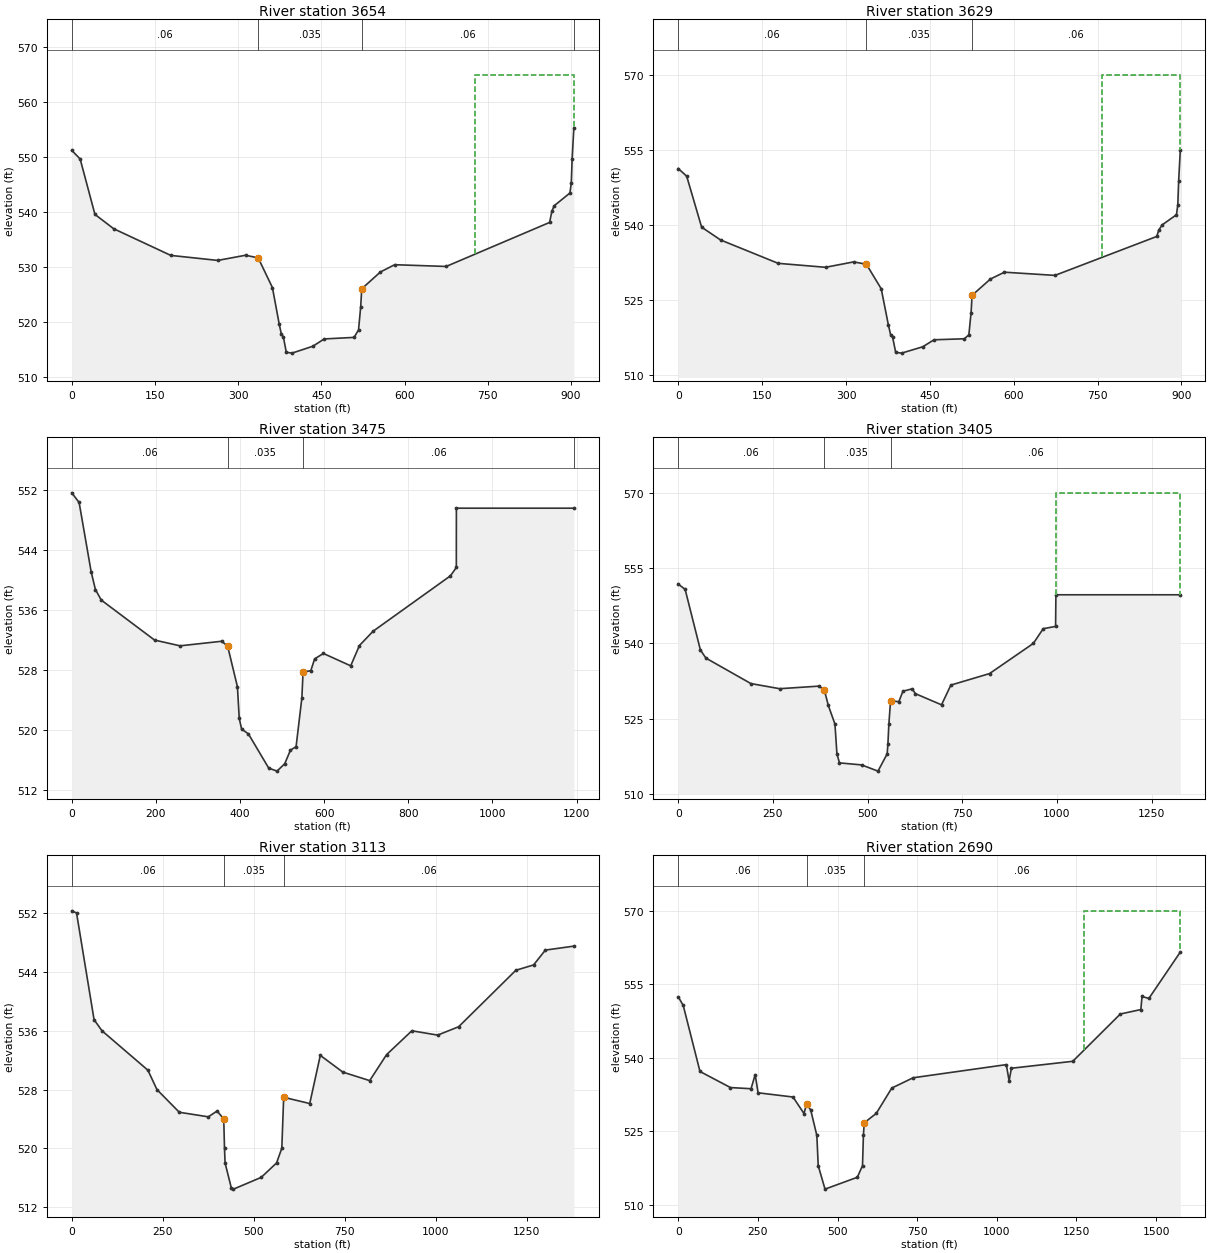
Type RM Length L Ch R = 1 ,3654    ,26.3,25.9,25.8
BEGIN DESCRIPTION:
Added cross-section.
END DESCRIPTION:
XS GIS Cut Line= 2
  2322846.158608 6958914.1084242 2323735.0519251 6958742.7666622
#Sta/Elev= 30
       0  551.26   15.12  549.69   41.77  539.62   75.59  537.01  178.59  532.16
  263.14  531.25   313.4  532.19  336.13  531.71  361.79  526.31  374.09  519.63
  378.04  517.79  381.46  517.36  386.79  514.55  397.05  514.39  434.62  515.64
  455.18  516.97  509.02  517.25  517.05  518.61  520.97  522.84  522.82  526.09
  556.56  529.15   582.2  530.47  674.99  530.15  861.61  538.16  865.56  540.16
  869.72  541.18  898.22  543.51  900.65  545.33  902.22  549.72  905.27  555.39
#Mann= 4 ,-1,0
       0     .06       0  336.13    .035       0  522.82     .06       0
  905.27     .06       0
#XS Ineff= 2 , 0
                          727.57             565
Permanent Ineff=
       F       F
Bank Sta=336.13,522.82
XS Rating Curve= 0 ,0
Exp/Cntr=0.3,0.1

Type RM Length L Ch R = 1 ,3629    ,160.2,153.4,150.6
BEGIN DESCRIPTION:
Effective flow limit in LOB set at Clear Fork Levee Loop.
Pier 1 site in ROB.
END DESCRIPTION:
XS GIS Cut Line= 2
 2322850.1678902 6958940.3722196 2323731.5950794 6958769.1682646
#Sta/Elev= 30
       0  551.26   15.14  549.72   41.81  539.53   75.67  536.97  178.77  532.29
  263.41   531.5  313.72  532.58  336.47  532.11  363.02   527.2  375.75     520
  379.84     518  383.38  517.53  388.89  514.48  399.51  514.33  437.26   515.6
   457.5     517  511.74   517.2  519.77     518   523.7  522.44  525.55   525.9
   558.4  529.16  583.36  530.52   673.7  529.88  855.79  537.67  859.38  538.95
  865.62     540  891.04  542.01  893.41     544  894.94  548.78   897.9  554.95
#Mann= 3 ,-1,0
       0     .06       0  336.47    .035       0  525.55     .06       0
#XS Ineff= 2 , 0
                          757.46             570
Permanent Ineff=
       F       F
Bank Sta=336.47,525.55
XS Rating Curve= 0 ,0
Exp/Cntr=0.3,0.1

Type RM Length L Ch R = 1 ,3475    ,71.7,69.9,69.1
BEGIN DESCRIPTION:
Added cross-section.
END DESCRIPTION:
XS GIS Cut Line= 2
  2322856.489352  6959106.906077 2324022.1105508 6958851.3925864
#Sta/Elev= 30
       0  551.65   17.48  550.36   46.03  541.12   56.19  538.74   70.13  537.33
  196.81  531.99  257.32  531.22  356.16  531.83  370.42  531.19  393.76  525.76
  398.08  521.52  403.67  520.11  419.88  519.46  468.07   514.9  487.85  514.49
  506.18  515.48  519.81  517.29  533.19  517.76  546.93  524.26  549.78  527.75
  568.11  527.89  577.29  529.48  598.11   530.2  662.99  528.55  683.74  531.26
   716.2  533.17  900.15  540.57  914.07  541.68   914.2   549.6  1193.4   549.6
#Mann= 4 ,-1,0
       0     .06       0  370.42    .035       0  549.78     .06       0
  1193.4     .06       0
Bank Sta=370.42,549.78
XS Rating Curve= 0 ,0
Exp/Cntr=0.3,0.1

Type RM Length L Ch R = 1 ,3405    ,313.5,292,288.1
BEGIN DESCRIPTION:
Effective flow limit in LOB set at Clear Fork Levee Loop.
Pier 1 site in ROB - ineffective flow due to buildings.
END DESCRIPTION:
XS GIS Cut Line= 2
 2322859.3190085 6959181.4511015 2324152.1530734 6958888.1983998
#Sta/Elev= 30
       0  551.82    18.2  550.77    58.5   538.7   73.01  537.08  191.92     532
  267.88  530.98  370.77  531.49  385.61  530.78  396.23  527.65  413.79  523.94
  419.01     518  425.76   516.2  484.03   515.8   527.4  514.56  551.65     518
  553.65     520  556.11  523.89  560.63  528.58  582.41  528.39  593.33  530.48
  618.07  530.96  625.89     530  695.19  527.77  719.86   531.7  821.92  533.99
  937.59     540  963.64  542.93  996.35  543.39  997.21  549.69 1325.68  549.69
#Mann= 3 ,-1,0
       0     .06       0  385.61    .035       0  560.63     .06       0
#XS Ineff= 2 , 0
                          997.21             570
Permanent Ineff=
       F       F
Bank Sta=385.61,560.63
XS Rating Curve= 0 ,0
Exp/Cntr=0.3,0.1

Type RM Length L Ch R = 1 ,3113    ,474.6,423.7,397.7
BEGIN DESCRIPTION:
At Sump 23C outfall.
Upstream of old Clear Fork channel (right bank).
Effective flow limit in LOB set at Clear Fork Levee Loop.
Pier 1 site in ROB.
CDC FW041423-1 Fort Worth City Hall Annex
Cross-sections 3113.178 - 4042.460
Located in ROB.
END DESCRIPTION:
XS GIS Cut Line= 2
 2322945.6707451 6959503.7454782 2324259.7275226 6959084.6958177
#Sta/Elev= 30
       0  552.34   13.11  552.05   61.27  537.51   83.05     536  209.16  530.63
     234  527.99  295.39   524.9  375.11  524.28  399.26  525.07  417.49  523.99
  419.57     520  421.16     518  438.55  514.55  444.23  514.43  520.42  516.03
  562.67     518  576.99     520  582.16  526.94  653.74  526.09  682.75  532.65
  744.62  530.37  818.41  529.21  864.82  532.75  934.25     536 1005.16  535.41
 1062.79  536.55 1219.93  544.24 1268.68  544.97 1300.98  546.99 1379.26  547.53
#Mann= 3 ,-1,0
       0     .06       0  417.49    .035       0  582.16     .06       0
#XS Ineff= 2 , 0
                         1362.92
Permanent Ineff=
       F       F
Bank Sta=417.49,582.16
XS Rating Curve= 0 ,0
Exp/Cntr=0.3,0.1

Type RM Length L Ch R = 1 ,2690    ,137.2,133.2,130.9
BEGIN DESCRIPTION:
Downstream of old Clear Fork channel (right bank).
Effective flow limit in LOB set at Clear Fork Levee Loop.
END DESCRIPTION:
XS GIS Cut Line= 3
 2323202.4162016 6959959.3206627 2323203.0318506 6959958.9855495
 2324578.9392467 6959191.4076583
#Sta/Elev= 30
       0  552.44   15.64   550.7   68.28  537.21  163.96  533.93  228.59  533.69
  241.54  536.56  250.67  532.86  360.36     532  394.74  528.63  403.09  530.63
  416.03  529.31  435.18  524.15  439.44     518  460.81   513.2   562.3  515.62
  578.52     518  581.31  524.15   583.9  526.73  621.71  528.66  670.44  533.83
  737.51  535.93 1029.92  538.61 1038.78  535.29 1045.89  537.87 1238.66  539.29
 1387.89  548.94 1452.32  549.85 1456.01  552.53 1477.43  552.11 1576.23  561.59
#Mann= 3 ,-1,0
       0     .06       0  403.09    .035       0   583.9     .06       0
#XS Ineff= 2 , 0
                            1274             570
Permanent Ineff=
       F       F
Bank Sta=403.09,583.9
XS Rating Curve= 0 ,0
Exp/Cntr=0.3,0.1

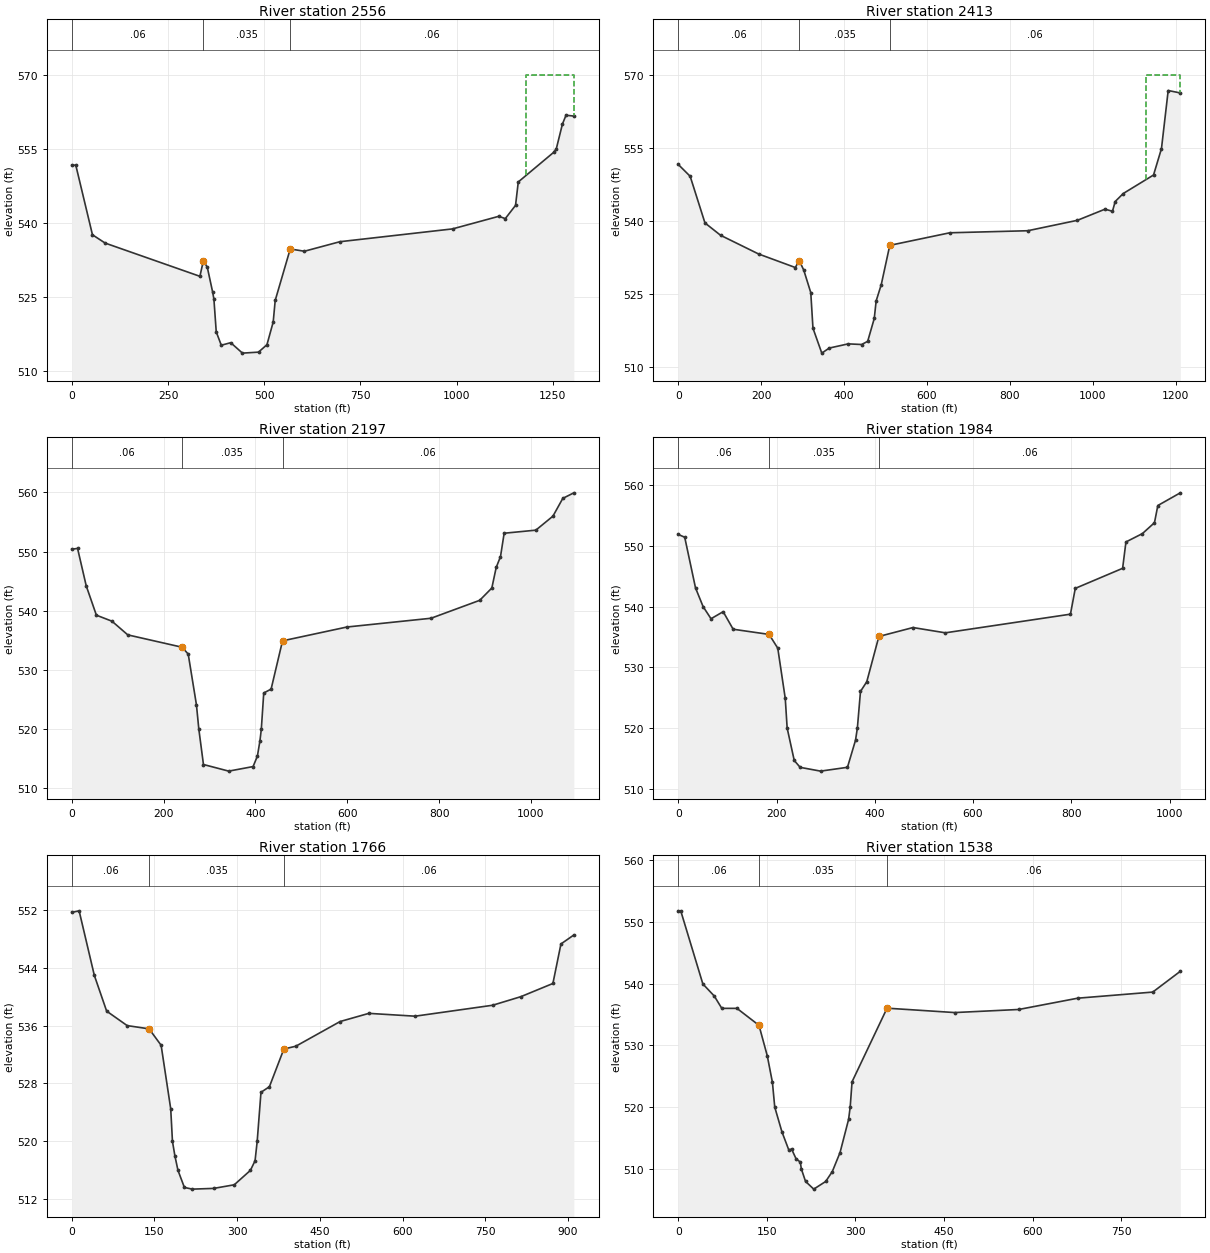
Type RM Length L Ch R = 1 ,2556    ,159.8,143.5,135.1
BEGIN DESCRIPTION:
Effective flow limit in LOB set at Clear Fork Levee Loop.
END DESCRIPTION:
XS GIS Cut Line= 2
 2323331.1515262 6960044.4123218 2324463.6028757 6959397.2973205
#Sta/Elev= 30
       0  551.68   10.39  551.74   53.75  537.64   86.76  535.96  332.85  529.24
  341.89  532.39  352.08  531.07  366.11     526  369.25  524.62  375.32     518
  388.39   515.3  412.97  515.81  443.41   513.7  485.09   513.9  507.03   515.4
  523.29     520  528.48  524.36  567.54  534.77  604.27  534.31  696.56  536.24
  989.08  538.83 1109.44  541.38 1126.18  540.91 1152.82  543.59 1159.95  548.33
 1251.45  554.29 1258.46  554.95 1274.65  560.04 1283.94  561.82  1304.3  561.66
#Mann= 3 ,-1,0
       0     .06       0  341.89    .035       0  567.54     .06       0
#XS Ineff= 2 , 0
                            1180             570
Permanent Ineff=
       F       F
Bank Sta=341.89,567.54
XS Rating Curve= 0 ,0
Exp/Cntr=0.3,0.1

Type RM Length L Ch R = 1 ,2413    ,219.5,216.1,215.7
BEGIN DESCRIPTION:
Effective flow limit in LOB set at Clear Fork Levee Loop.
END DESCRIPTION:
XS GIS Cut Line= 2
 2323469.8137206 6960154.8823564 2324486.5750478 6959497.1648142
#Sta/Elev= 30
       0  551.61   28.79  549.17   64.46   539.6  102.06  537.07  193.79  533.23
   282.4  530.45  291.78  531.89  302.82   529.9  319.67   525.3  324.95     518
  346.25  512.88  364.23  513.92  409.98  514.78  442.29  514.65  456.92   515.3
  472.81     520  477.35  523.59  489.64  526.93   510.2     535  654.99  537.58
  842.98     538  962.76  540.14 1029.15  542.42 1047.36     542  1053.9     544
 1073.33  545.64 1146.38  549.44 1165.49  554.85 1181.72  566.78 1210.95  566.28
#Mann= 3 ,-1,0
       0     .06       0  291.78    .035       0   510.2     .06       0
#XS Ineff= 2 , 0
                            1128             570
Permanent Ineff=
       F       F
Bank Sta=291.78,510.2
XS Rating Curve= 0 ,0
Exp/Cntr=0.3,0.1

Type RM Length L Ch R = 1 ,2197    ,217.2,212.5,210.3
BEGIN DESCRIPTION:
Effective flow limit in LOB set at Clear Fork Levee Loop.
END DESCRIPTION:
XS GIS Cut Line= 2
 2323645.7441329 6960300.9694149 2324559.8293677 6959701.0029614
#Sta/Elev= 30
       0  550.41   12.63  550.54   31.48  544.22   53.59  539.26   87.57  538.24
  121.97  535.93  240.34  533.84   253.6  532.68   271.5  524.11  276.69     520
  286.77  514.02  341.81   512.9  394.83  513.67  404.19  515.42  409.76     518
   412.8     520  418.08  526.11   434.1  526.76  458.96  534.92  599.29  537.26
  782.45  538.74  888.39  541.77  914.79  543.85  924.31  547.33  933.66  549.16
  941.61  553.11 1010.61  553.63 1047.88     556 1069.32     559 1093.39  559.94
#Mann= 3 ,-1,0
       0     .06       0  240.34    .035       0  458.96     .06       0
Bank Sta=240.34,458.96
XS Rating Curve= 0 ,0
Exp/Cntr=0.3,0.1

Type RM Length L Ch R = 1 ,1984    ,226.4,218.2,213.3
BEGIN DESCRIPTION:
Effective flow limit in LOB set at Clear Fork Levee Loop.
END DESCRIPTION:
XS GIS Cut Line= 2
 2323814.9536134 6960447.9972534 2324661.7483765 6959876.1764197
#Sta/Elev= 30
       0  551.88   13.18  551.42   35.19  543.07   50.59     540   66.71     538
   91.45  539.16  111.78  536.27  184.95  535.42  202.55  533.15  217.82  524.87
  221.65     520   236.1  514.66  248.17  513.53  289.73  512.91  344.41  513.54
  360.79     518  364.56     520   370.9  526.03   383.7  527.63  408.33  535.08
  477.79  536.55  543.59  535.68  798.19  538.75  808.03     543  904.36   546.3
  911.13  550.64  944.67  552.02  969.18  553.81  976.04  556.64 1021.78  558.73
#Mann= 3 ,-1,0
       0     .06       0  184.95    .035       0  408.33     .06       0
Bank Sta=184.95,408.33
XS Rating Curve= 0 ,0
Exp/Cntr=0.3,0.1

Type RM Length L Ch R = 1 ,1766    ,247.6,228.2,208.3
BEGIN DESCRIPTION:
Effective flow limit in LOB set at Clear Fork Levee Loop.
END DESCRIPTION:
XS GIS Cut Line= 2
 2323986.9398017  6960603.297008 2324725.4478866 6960070.4596274
#Sta/Elev= 30
       0  551.64   13.33  551.86   40.92  542.94   63.25     538  100.45     536
  140.22  535.55  162.08  533.28  179.47   524.5  182.63     520  187.04     518
   192.6     516  204.28  513.63   218.7   513.4  257.34   513.5  294.74     514
  323.98  515.99  332.45  517.32  336.31     520  343.18  526.78  358.46  527.55
  384.68  532.76   406.4  533.15  486.67  536.56  538.86  537.69  622.75   537.3
  763.29  538.81  814.65     540  872.67  541.82  887.26  547.28  910.66  548.52
#Mann= 3 ,-1,0
       0     .06       0  140.22    .035       0  384.68     .06       0
#Block Obstruct= 2 , 0
                             909             570
Bank Sta=140.22,384.68
XS Rating Curve= 0 ,0
Exp/Cntr=0.3,0.1

Type RM Length L Ch R = 1 ,1538    ,141,140.9,140.8
BEGIN DESCRIPTION:
Upstream of Henderson Street.
Copy of cross-section 1396.969.
Effective flow limit in LOB set at Clear Fork Levee Loop.
END DESCRIPTION:
XS GIS Cut Line= 3
 2324178.5161762 6960780.9688422 2324794.8782862 6960204.5688195
 2324799.2459906  6960200.484297
#Sta/Elev= 30
       0  551.81    4.26   551.8   41.67  539.96   60.98     538   73.76     536
   99.39     536  136.68  533.25  150.66  528.33  159.45     524  163.35     520
  175.48     516  187.01  513.08  191.91  513.18  199.36  511.64  206.64  511.08
  208.31     510  215.49  507.95  229.37   506.7   249.6  507.94  260.82  509.55
  273.89  512.63  288.35     518  291.06     520  294.23   524.1  353.44  536.03
  468.02  535.32  576.35  535.82  676.29  537.65  803.23  538.64  849.86  542.01
#Mann= 3 ,-1,0
       0     .06       0  136.68    .035       0  353.44     .06       0
#XS Ineff= 2 , 0
                          849.86
Permanent Ineff=
       F       F
Bank Sta=136.68,353.44
XS Rating Curve= 0 ,0
Exp/Cntr=0.5,0.3

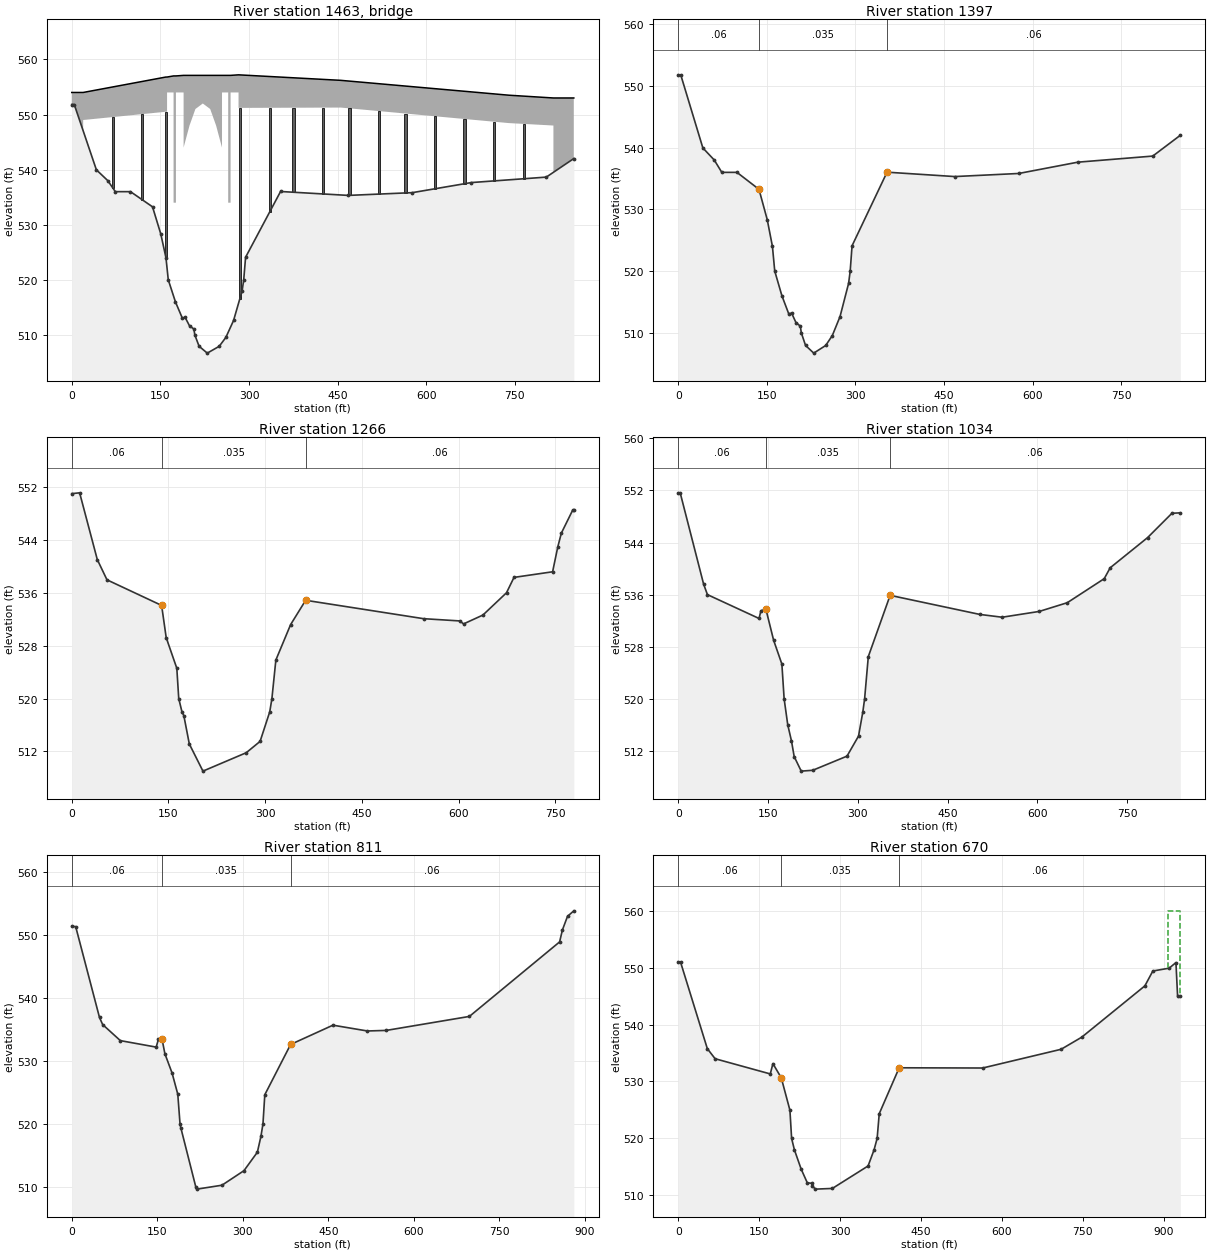
Type RM Length L Ch R = 3 ,1463    ,,,
BEGIN DESCRIPTION:
Henderson Street
Bridge data from bridge plans, 1975 USACE survey.
END DESCRIPTION:
Node Name=Henderson Street
Bridge Culvert--1,0,-1,-1, 0
Deck Dist Width WeirC Skew NumUp NumDn MinLoCord MaxHiCord MaxSubmerge Is_Ogee
38.5,73,2.6,0, 30, 30, , , 0.95, 0, 0,0,,
       0    19.3    19.3   159.3   161.3   161.3   172.3   172.3   176.3   176.3
   189.3   189.3   199.3   209.3   221.8   234.3   244.3   254.3   254.3   264.8
   264.8   268.8   268.8   282.3   282.3   455.3   740.3   815.3   815.3   849.8
     554     554     554   556.8   556.8   556.8     557     557     557     557
   557.1   557.1   557.1   557.1   557.1   557.1   557.1   557.1   557.1   557.1
   557.1   557.1   557.1   557.2   557.2   556.2   553.5     553     553     553
     545     545     549   550.5   550.5     554     554     534     534     554
     554     544     548     551     552     551     548     544     554     554
     534     534     554     554   551.2  551.26  548.44     548     535     535
       0    19.3    19.3   159.3   161.3   161.3   172.3   172.3   176.3   176.3
   189.3   189.3   199.3   209.3   221.8   234.3   244.3   254.3   254.3   264.8
   264.8   268.8   268.8   282.3   282.3   455.3   740.3   815.3   815.3   849.8
     554     554     554   556.8   556.8   556.8     557     557     557     557
   557.1   557.1   557.1   557.1   557.1   557.1   557.1   557.1   557.1   557.1
   557.1   557.1   557.1   557.2   557.2   556.2   553.5     553     553     553
     545     545     549   550.5   550.5     554     554     534     534     554
     554     544     548     551     552     551     548     544     554     554
     534     534     554     554   551.2  551.26  548.44     548     535     535
Pier Skew, UpSta & Num, DnSta & Num=  ,69.3, 2 ,69.3, 2 , 0 , 0 , 0 ,,
       4       4
     500     553
       4       4
     500     553
Pier Skew, UpSta & Num, DnSta & Num=  ,119.3, 2 ,119.3, 2 , 0 , 0 , 0 ,,
       4       4
     500     553
       4       4
     500     553
Pier Skew, UpSta & Num, DnSta & Num=  ,159.3, 2 ,159.3, 2 , 0 , 0 , 0 ,,
       4       4
     500     553
       4       4
     500     553
Pier Skew, UpSta & Num, DnSta & Num=  ,284.3, 2 ,284.3, 2 , 0 , 0 , 0 ,,
       4       4
     500     554
       4       4
     500     554
Pier Skew, UpSta & Num, DnSta & Num=  ,335.3, 2 ,335.3, 2 , 0 , 0 , 0 ,,
       4       4
     500     553
       4       4
     500     553
Pier Skew, UpSta & Num, DnSta & Num=  ,375.3, 2 ,375.3, 2 , 0 , 0 , 0 ,,
       4       4
     500     553
       4       4
     500     553
Pier Skew, UpSta & Num, DnSta & Num=  ,425.3, 2 ,425.3, 2 , 0 , 0 , 0 ,,
       4       4
     500     553
       4       4
     500     553
Pier Skew, UpSta & Num, DnSta & Num=  ,470, 2 ,470, 2 , 0 , 0 , 0 ,,
       4       4
     500     553
       4       4
     500     553
Pier Skew, UpSta & Num, DnSta & Num=  ,520, 2 ,520, 2 , 0 , 0 , 0 ,,
       4       4
     500     553
       4       4
     500     553
Pier Skew, UpSta & Num, DnSta & Num=  ,565, 2 ,565, 2 , 0 , 0 , 0 ,,
       4       4
     500     553
       4       4
     500     553
Pier Skew, UpSta & Num, DnSta & Num=  ,615, 2 ,615, 2 , 0 , 0 , 0 ,,
       4       4
     500     553
       4       4
     500     553
Pier Skew, UpSta & Num, DnSta & Num=  ,665, 2 ,665, 2 , 0 , 0 , 0 ,,
       4       4
     500     553
       4       4
     500     553
Pier Skew, UpSta & Num, DnSta & Num=  ,715, 2 ,715, 2 , 0 , 0 , 0 ,,
       4       4
     500     553
       4       4
     500     553
Pier Skew, UpSta & Num, DnSta & Num=  ,765, 2 ,765, 2 , 0 , 0 , 0 ,,
       4       4
     500     553
       4       4
     500     553
BR Coef=-1 , 0 , 0 ,, 0 ,,,0.8,-1,,0,
WSPro=,,,, 1 ,,,, 0 ,,,, 0 ,,,,-1 ,-1 ,-1 , 0 , 0 , 0 , 0 , 0
BC Design=,, 0 ,, 0 ,,,,,,
BC Use User HTab Curves=0
BC User HTab FreeFlow(D)= 0

Type RM Length L Ch R = 1 ,1397    ,132.6,130.5,127.4
BEGIN DESCRIPTION:
Downstream of Henderson Street.
Effective flow limit in LOB set at Clear Fork Levee Loop.
---------------------------------------------------------------------
RADIO SHACK RIVERFRONT CAMPUS CDC FW080602-01 IN ROB.
---------------------------------------------------------------------
END DESCRIPTION:
XS GIS Cut Line= 2
  2324279.296189 6960879.3880246 2324900.1270368 6960299.0133131
#Sta/Elev= 30
       0  551.81    4.26   551.8   41.67  539.96   60.98     538   73.76     536
   99.39     536  136.68  533.25  150.66  528.33  159.45     524  163.35     520
  175.48     516  187.01  513.08  191.91  513.18  199.36  511.64  206.64  511.08
  208.31     510  215.49  507.95  229.37   506.7   249.6  507.94  260.82  509.55
  273.89  512.63  288.35     518  291.06     520  294.23   524.1  353.44  536.03
  468.02  535.32  576.35  535.82  676.29  537.65  803.23  538.64  849.86  542.01
#Mann= 3 ,-1,0
       0     .06       0  136.68    .035       0  353.44     .06       0
#XS Ineff= 2 , 0
                          849.86
Permanent Ineff=
       F       F
Bank Sta=136.68,353.44
XS Rating Curve= 0 ,0
Exp/Cntr=0.5,0.3

Type RM Length L Ch R = 1 ,1266    ,233.7,232.1,230.6
BEGIN DESCRIPTION:
Effective flow limit in LOB set at Clear Fork Levee Loop.
---------------------------------------------------------------------
RADIO SHACK RIVERFRONT CAMPUS CDC FW080602-01 IN ROB.
---------------------------------------------------------------------
END DESCRIPTION:
XS GIS Cut Line= 2
 2324372.0990816 6960976.3744523  2324931.520986 6960434.5919475
#Sta/Elev= 30
       0  551.07   12.19  551.19    39.6  541.07   54.62     538  139.37  534.12
  146.48  529.23  162.94  524.59  165.92     520   170.9     518  173.86   517.4
  182.32  513.12  203.47     509  270.63  511.79  292.11  513.51  307.11     518
  310.44     520  316.56  525.84  339.44  531.21  362.78   534.9  545.75  532.11
  601.72  531.77  607.76  531.32  637.73  532.66  674.32  536.04  685.95  538.37
  745.82  539.22  753.81  542.97  759.39  545.08   777.1  548.59  778.77  548.57
#Mann= 3 ,-1,0
       0     .06       0  139.37    .035       0  362.78     .06       0
Bank Sta=139.37,362.78
XS Rating Curve= 0 ,0
Exp/Cntr=0.3,0.1

Type RM Length L Ch R = 1 ,1034    ,230.6,223,209
BEGIN DESCRIPTION:
Effective flow limit in LOB set at Clear Fork Levee Loop.
---------------------------------------------------------------------
RADIO SHACK RIVERFRONT CAMPUS CDC FW080602-01 IN ROB.
---------------------------------------------------------------------
END DESCRIPTION:
XS GIS Cut Line= 2
 2324539.6081056 6961140.5371409 2325135.3547255 6960550.2813216
#Sta/Elev= 30
       0  551.63    3.28  551.62   42.43   537.6   48.76     536  134.95  532.34
  138.13  533.51  146.34   533.8  159.31     529  173.11  525.34  176.89     520
  182.94     516  189.18  513.52  193.68  511.13  205.44   508.9  224.68  509.03
  281.88   511.2  301.15  514.28  308.36     518  311.31     520  317.47  526.48
  353.93  535.89  503.72  532.96  541.04  532.53  603.04  533.42  649.87  534.76
  711.56  538.45  721.49  540.12  784.06  544.76  824.65  548.49  838.64  548.56
#Mann= 3 ,-1,0
       0     .06       0  146.34    .035       0  353.93     .06       0
Bank Sta=146.34,353.93
XS Rating Curve= 0 ,0
Exp/Cntr=0.3,0.1

Type RM Length L Ch R = 1 ,811     ,144.7,141.3,130.6
BEGIN DESCRIPTION:
Effective flow limit in LOB set at Clear Fork Levee Loop.
---------------------------------------------------------------------
RADIO SHACK RIVERFRONT CAMPUS CDC FW080602-01 IN ROB.
---------------------------------------------------------------------
END DESCRIPTION:
XS GIS Cut Line= 3
 2324708.5334204 6961305.5650308 2324967.3296142 6961018.5481571
 2325234.5169906 6960602.6170588
#Sta/Elev= 30
       0  551.36    6.88   551.3   48.65  536.88   54.18  535.76   85.22  533.21
  148.12  532.18  152.11  533.46   158.5  533.39  163.37  531.13     176  528.06
  185.98  524.71  189.91     520  191.24   519.4  217.56     510  219.67  509.64
  263.46  510.26  302.11  512.57   325.6   515.5  331.82     518  335.43     520
  338.64  524.62  383.92   532.6   458.2  535.66  518.62  534.74  551.74  534.83
  697.57  537.05  855.87  548.88  860.73  550.77  869.73  552.94  880.82  553.81
#Mann= 3 ,-1,0
       0     .06       0   158.5    .035       0  383.92     .06       0
Bank Sta=158.5,383.92
XS Rating Curve= 0 ,0
Exp/Cntr=0.3,0.1

Type RM Length L Ch R = 1 ,670     ,175,168.4,151.3
BEGIN DESCRIPTION:
Effective flow limit in LOB set at Clear Fork Levee Loop.
---------------------------------------------------------------------
RADIO SHACK RIVERFRONT CAMPUS CDC FW080602-01 IN ROB.
---------------------------------------------------------------------
END DESCRIPTION:
XS GIS Cut Line= 3
 2324812.9117841 6961409.2452961 2325080.2644485 6961098.4289031
 2325308.8887867 6960630.1621973
#Sta/Elev= 30
       0  551.04    4.21  551.01   53.95  535.77   68.41     534  170.67  531.33
  175.59  533.14  191.06  530.65  207.12  524.95  210.24     520   215.4     518
  227.91  514.61   239.3   512.2  247.39   512.1  248.72  511.63  254.38  511.08
   285.8   511.2  352.05  515.15   363.2     518  368.86     520  372.75  524.34
  409.73  532.41  564.54  532.37  709.99  535.66  748.31  537.79  865.38  546.81
  880.12  549.42  910.36  549.92  922.98   550.9  926.03     545  931.08     545
#Mann= 3 ,-1,0
       0     .06       0  191.06    .035       0  409.73     .06       0
#XS Ineff= 2 , 0
                          908.43             560
Permanent Ineff=
       F       F
Bank Sta=191.06,409.73
XS Rating Curve= 0 ,0
Exp/Cntr=0.3,0.1

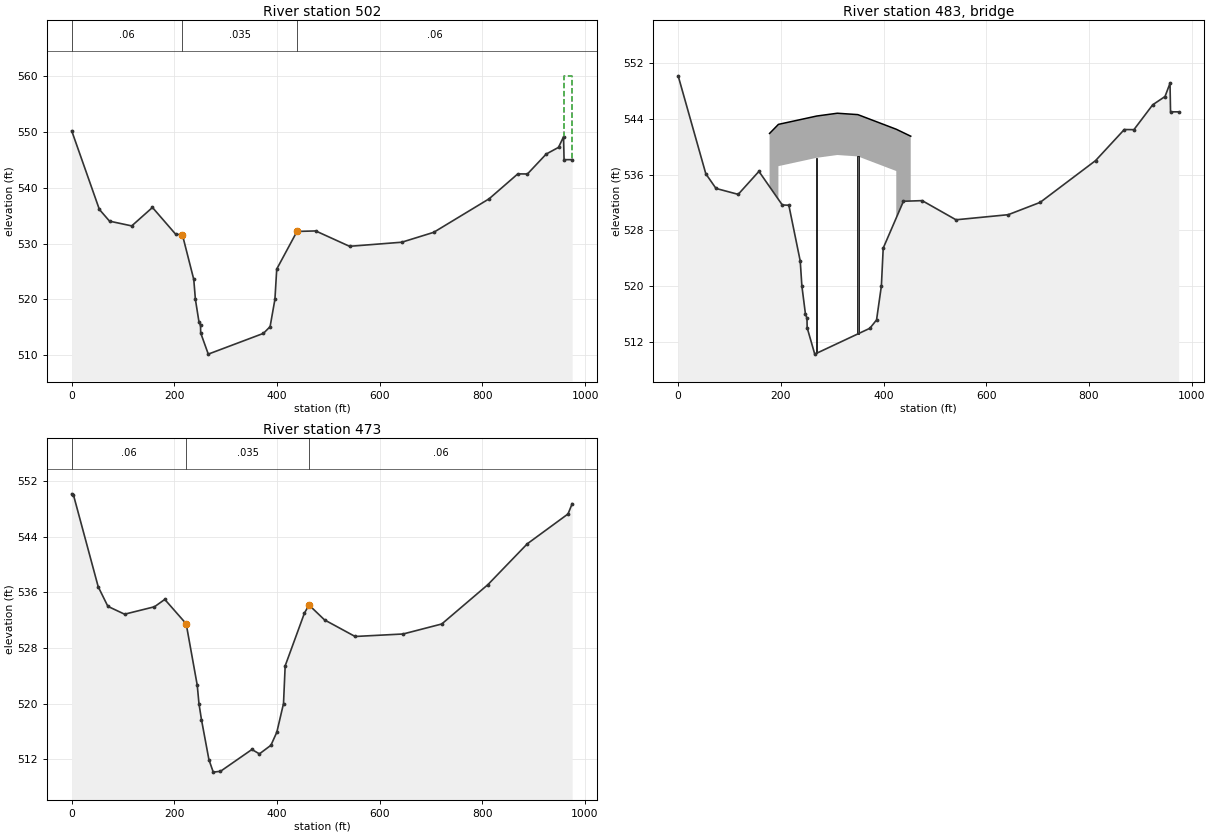
Type RM Length L Ch R = 1 ,502     ,28.3,28.3,28.3
BEGIN DESCRIPTION:
Upstream of pedestrian bridge.
Effective flow limit in LOB set at Clear Fork Levee Loop.
---------------------------------------------------------------------
RADIO SHACK RIVERFRONT CAMPUS CDC FW080602-01 IN ROB.
---------------------------------------------------------------------
END DESCRIPTION:
XS GIS Cut Line= 5
 2324917.8435708 6961507.0659417 2325008.3015784 6961446.4914756
 2325047.8769567 6961405.3006831 2325235.2542397  6961161.387275
 2325352.9610342 6960674.2343151
#Sta/Elev= 30
       0  550.17   53.89   536.1   73.71     534  116.92  533.15   157.3  536.45
  202.78  531.63  215.56  531.59  237.77  523.57  240.95     520  247.85     516
  250.89  515.35  251.25     514  266.02  510.21  373.33  513.92   386.4  515.12
   395.8     520  399.36  525.43  438.79  532.16  475.23  532.25  541.11   529.5
  642.81  530.23  705.03     532  812.99     538   868.9  542.46  887.64  542.44
  924.24  546.01  948.19   547.2  957.94   549.1  958.96     545  974.74     545
#Mann= 3 ,-1,0
       0     .06       0  215.56    .035       0  438.79     .06       0
#XS Ineff= 2 , 0
                          957.94             560
Permanent Ineff=
       F       F
Bank Sta=215.56,438.79
XS Rating Curve= 0 ,0
Exp/Cntr=0.5,0.3

Type RM Length L Ch R = 3 ,483     ,,,
BEGIN DESCRIPTION:
Pedestrian Bridge
Bridge data from TRWD May 2007 survey data, bridge plans.  Minimum low chord elev. 537.0.  Bridge width 10 feet.
END DESCRIPTION:
Node Name=ped. bridge
Bridge Culvert--1,0,-1,-1, 0
Deck Dist Width WeirC Skew NumUp NumDn MinLoCord MaxHiCord MaxSubmerge Is_Ogee
14,10,2.6,0, 9, 9, , , 0.95, 0, 0,0,,
     178  195.25  195.25     270     310     350   424.8   424.8     453
   541.9   543.2   543.2   544.4   544.8   544.6   542.5   542.5   541.5
     450     450   537.2   538.4   538.8   538.6   536.5     450     450
     174  206.25  206.25     281     321     361   435.8   435.8   456.7
   541.9   543.2   543.2   544.4   544.8   544.6   542.5   542.2   541.5
     450     450   537.2   538.4   538.8   538.6   536.5     450     450
Pier Skew, UpSta & Num, DnSta & Num=  ,270, 2 ,281, 2 , 0 , 0 , 0 ,,
     2.5     2.5
     500     540
     2.5     2.5
     500     540
Pier Skew, UpSta & Num, DnSta & Num=  ,350, 2 ,361, 2 , 0 , 0 , 0 ,,
     2.5     2.5
     500     540
     2.5     2.5
     500     540
BR Coef=-1 , 0 , 0 ,, 0 ,,,0.8,-1,,0,
WSPro=,,,, 1 ,,,, 0 ,,,, 0 ,,,,-1 ,-1 ,-1 , 0 , 0 , 0 , 0 , 0
BC Design=,, 0 ,, 0 ,,,,,,
BC Use User HTab Curves=0
BC User HTab FreeFlow(D)= 0

Type RM Length L Ch R = 1 ,473     ,0,0,0
BEGIN DESCRIPTION:
Cross-section located 473.31 feet upstream of the West Fork/Clear Fork confluence.
Effective flow limit in LOB set at Clear Fork Levee Loop.
Downstream of pedestrian bridge.
---------------------------------------------------------------------
RADIO SHACK RIVERFRONT CAMPUS CDC FW080602-01 IN ROB.
---------------------------------------------------------------------
END DESCRIPTION:
XS GIS Cut Line= 5
 2324929.0239065 6961521.7620492 2325020.9806544 6961468.4689383
 2325069.5193062 6961426.8827511 2325259.4840261  6961172.694526
 2325373.1319969 6960698.5736453
#Sta/Elev= 30
       0  550.21    3.25   550.1   51.68  536.82    70.5     534  103.08  532.87
  161.27  533.94  181.36     535  223.05  531.49  244.62  522.64  247.95     520
  252.82  517.69  267.37  511.92  275.79  510.12  289.92  510.24   351.1  513.38
  365.74  512.75  388.18  513.99  399.69  515.88  412.69     520  415.92  525.43
  453.52  533.04  462.38  534.19  492.61  532.05  552.17  529.66  645.76  530.02
  720.99  531.46  810.78  537.12  887.77  543.02  967.01  547.31  975.08  548.79
#Mann= 3 ,-1,0
       0     .06       0  223.05    .035       0  462.38     .06       0
Bank Sta=223.05,462.38
XS Rating Curve= 0 ,0
Exp/Cntr=0.5,0.3

River Reach=West Fork       ,wf4
Reach XY= 30
     2301931.855     6972568.564     2303381.874     6972834.438
       2304681.2     6971884.839     2305119.554     6971074.936
     2304979.806      6970227.72      2303843.55     6968887.397
     2300817.483     6967949.907     2300066.566        6967480.
     2299969.403     6966866.595      2301131.74     6965707.713
      2301143.92     6964945.639     2301925.229     6964073.481
 2304733.9708734  6962615.605765 2305211.6495284 6961841.7033737
 2305304.3288763 6960324.8493094 2306712.0795456 6958307.4171447
 2307872.7224067 6958506.4960362 2308857.7073536  6960522.006842
 2311273.9782877 6961475.7637758 2312608.9777605 6962649.4182334
 2313194.7250432 6964189.5666192 2312542.6866651 6966233.6403483
 2313591.8942099 6967166.0339127 2314595.6063456 6967022.8839238
 2315881.4524252 6965824.2387071 2316124.5933228 6963965.7006292
 2316809.9642509 6963246.4184489 2318919.6091978 6962770.3800985
 2323405.8064508 6963558.9277793  2325608.947074   6961458.87796

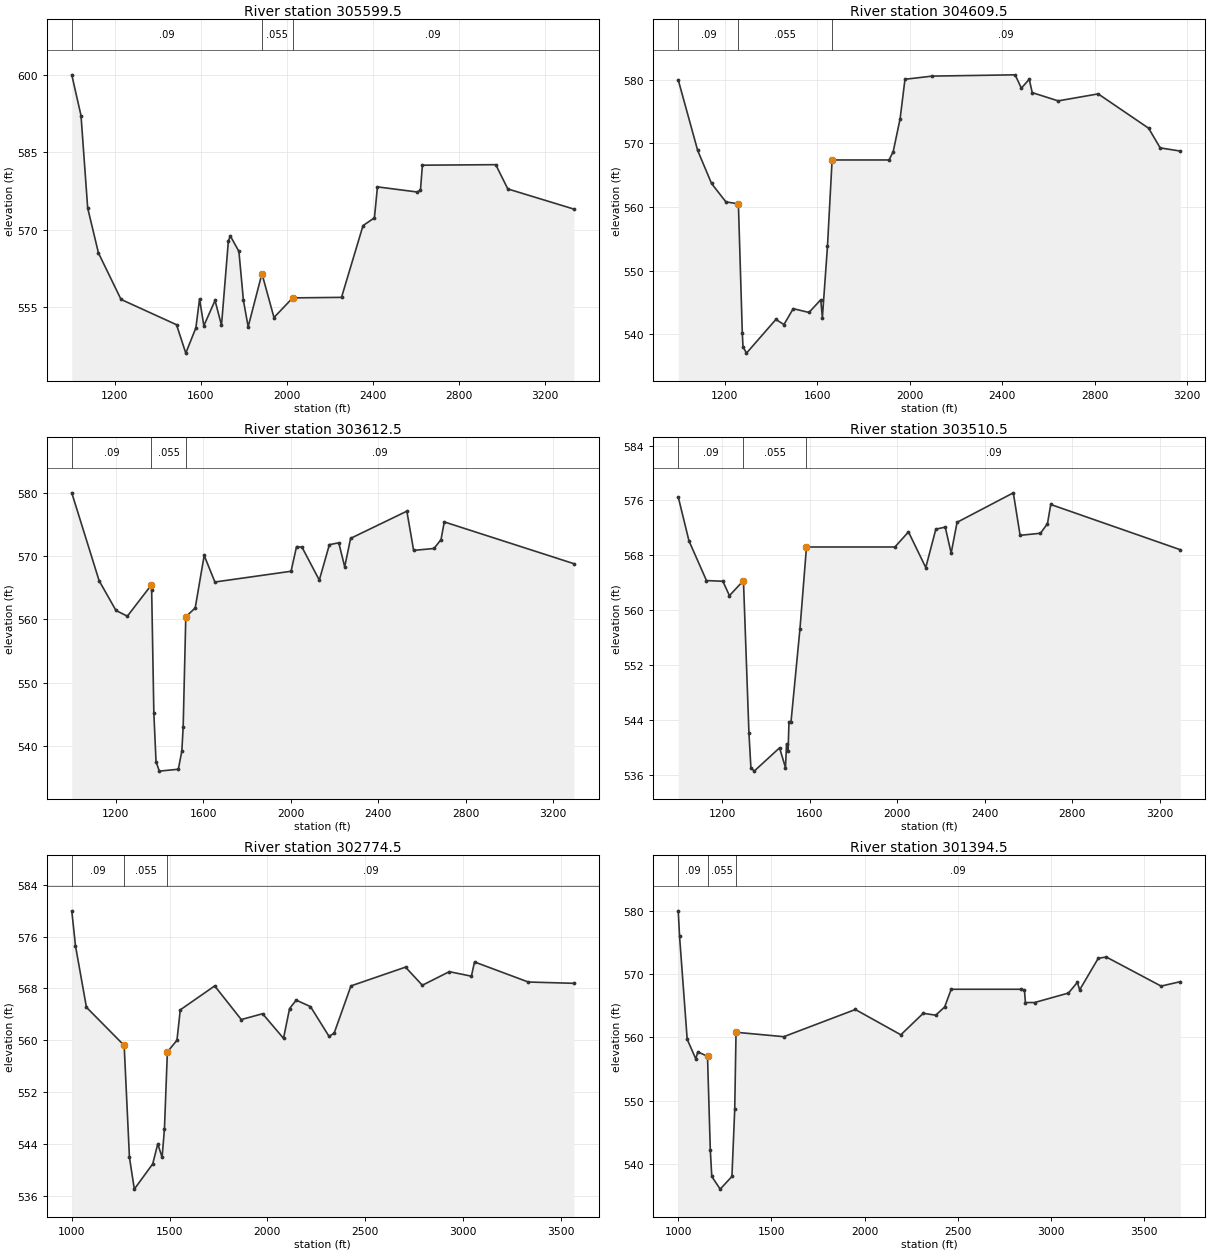
Type RM Length L Ch R = 1 ,305599.5,900,990,600
BEGIN DESCRIPTION:
424 feet downstream of Lake Worth Spillway.  Fish
hatchery ponds removed from conveyance in ROB.
Lake Worth: spillway crest elev. 594.3, top of dam elev. 606.3,
sta 3060+24 river mile 57.96
Channel data from 1975 USACE field survey.
END DESCRIPTION:
XS GIS Cut Line= 4
     2302130.541     6972749.547      2302051.83     6972311.915
     2302108.502     6971971.885     2301985.713     6971150.144
#Sta/Elev= 30
    1000     600    1043   592.1    1074   574.2    1124   565.5    1229   556.5
    1487   551.6    1530   546.1    1577     551    1594   556.6    1614   551.4
    1666   556.3    1696   551.5    1728   567.8    1737   568.8    1777   565.8
    1798   556.3    1820   551.2    1884   561.5    1940     553    2027   556.8
    2254   556.9    2354   570.8    2407   572.3    2421   578.3    2607   577.3
    2621   577.7    2630   582.5    2971   582.6    3027   577.9    3334     574
#Mann= 3 ,0,0
    1000     .09       0    1884    .055       0    2027     .09       0
Bank Sta=1884,2027
XS Rating Curve= 0 ,0
Exp/Cntr=0.3,0.1

Type RM Length L Ch R = 1 ,304609.5,1100,997,720
BEGIN DESCRIPTION:
Fish hatchery ponds removed from conveyance removed in
ROB.
Channel data from 1975 USACE field survey.
END DESCRIPTION:
XS GIS Cut Line= 3
      2303319.57     6973163.447      2303157.07     6972644.864
     2302670.734     6971092.828
#Sta/Elev= 30
    1000     580    1084   568.9    1144   563.7    1206   560.8    1260   560.5
    1277   540.1    1280     538    1295     537    1422   542.3    1457   541.5
    1497     544    1565   543.4    1616   545.4    1623   542.6    1645   553.8
    1665   567.4    1911   567.4    1929   568.7    1959   573.9    1980   580.1
    2098   580.6    2456   580.8    2483   578.7    2517   580.1    2530     578
    2642   576.7    2815   577.8    3033   572.4    3083   569.3    3170   568.8
#Mann= 3 ,0,0
    1000     .09       0    1260    .055       0    1665     .09       0
#XS Ineff= 2 , 0
                            2702
Permanent Ineff=
       F       F
Bank Sta=1260,1665
XS Rating Curve= 0 ,0
Exp/Cntr=0.3,0.1

Type RM Length L Ch R = 1 ,303612.5,102,102,102
BEGIN DESCRIPTION:
Channel data from 1975 USACE field survey.
END DESCRIPTION:
XS GIS Cut Line= 6
     2304346.193     6972656.786      2304329.86     6972634.336
     2304087.261     6972300.856     2304086.173      6972299.36
     2303930.184     6972084.937     2302682.613     6971104.311
#Sta/Elev= 30
    1000     580    1125   566.1    1202   561.4    1254   560.5    1363   565.4
    1365   564.7    1375   545.2    1385   537.5    1400     536    1487   536.3
    1503   539.2    1509     543    1521   560.4    1564   561.8    1605   570.1
    1654   565.9    2002   567.6    2027   571.5    2052   571.4    2131   566.2
    2177   571.8    2220   572.1    2247   568.3    2274   572.8    2531   577.1
    2562   570.9    2655   571.2    2687   572.6    2702   575.4    3294   568.8
#Mann= 3 ,0,0
    1000     .09       0    1363    .055       0    1521     .09       0
#XS Ineff= 2 , 0
                            2198
Permanent Ineff=
       F       F
Bank Sta=1363,1521
XS Rating Curve= 0 ,0
Exp/Cntr=0.3,0.1

Type RM Length L Ch R = 1 ,303510.5,770,736,640
BEGIN DESCRIPTION:
Fish hatchery pond in ROB removed from conveyance.
Channel data from 1975 USACE field survey.
END DESCRIPTION:
XS GIS Cut Line= 6
     2304419.002     6972585.952     2304001.906     6972012.607
     2303878.534     6971927.404     2303877.646     6971926.792
     2303865.897     6971918.677     2302697.705     6971111.909
#Sta/Elev= 30
    1000   576.5    1049   570.1    1129   564.3    1204   564.2    1234   562.1
    1298   564.3    1323   542.1    1332     537    1347   536.5    1463   539.9
    1490     537    1495   540.5    1502   539.5    1506   543.7    1515   543.6
    1556   557.2    1586   569.2    1990   569.2    2052   571.4    2131   566.2
    2177   571.8    2220   572.1    2247   568.3    2274   572.8    2531   577.1
    2562   570.9    2655   571.2    2687   572.6    2702   575.4    3294   568.8
#Mann= 3 ,0,0
    1000     .09       0    1298    .055       0    1586     .09       0
#XS Ineff= 2 , 0
                            2198
Permanent Ineff=
       F       F
Bank Sta=1298,1586
XS Rating Curve= 0 ,0
Exp/Cntr=0.3,0.1

Type RM Length L Ch R = 1 ,302774.5,1580,1380,800
BEGIN DESCRIPTION:
Channel data from 1975 USACE field survey.
END DESCRIPTION:
XS GIS Cut Line= 4
     2305024.641     6971993.963      2304735.08     6971782.824
     2304271.835     6971445.042     2302673.085     6971094.992
#Sta/Elev= 30
    1000     580    1019   574.6    1075   565.1    1268   559.2    1295   541.9
    1320     537    1414   540.9    1440     544    1462   541.9    1474   546.3
    1489   558.2    1538     560    1555   564.7    1731   568.4    1867   563.2
    1976   564.1    2083   560.3    2114   564.9    2148   566.2    2221   565.2
    2316   560.6    2342   561.1    2428   568.4    2707   571.3    2793   568.5
    2931   570.6    3044   569.9    3060   572.1    3335     569    3568   568.8
#Mann= 3 ,0,0
    1000     .09       0    1268    .055       0    1489     .09       0
#XS Ineff= 2 , 0
                            3060
Permanent Ineff=
       F       F
Bank Sta=1268,1489
XS Rating Curve= 0 ,0
Exp/Cntr=0.3,0.1

Type RM Length L Ch R = 1 ,301394.5,950,864,1000
BEGIN DESCRIPTION:
Camp Carter area in ROB - conveyance removed from ponds
in ROB.
Channel data from 1975 USACE field survey.
END DESCRIPTION:
XS GIS Cut Line= 3
     2305295.294     6970463.488     2305065.749     6970518.726
     2302676.613      6971093.64
#Sta/Elev= 30
    1000     580    1007     576    1048   559.7    1094   556.6    1105   557.7
    1157     557    1172   542.2    1180     538    1225     536    1288     538
    1303   548.6    1310   560.8    1566   560.1    1950   564.4    2194   560.4
    2314   563.8    2381   563.5    2429   564.8    2464   567.6    2838   567.6
    2857   567.5    2862   565.5    2911   565.5    3093     567    3141   568.7
    3153   567.5    3253   572.5    3296   572.7    3590   568.1    3693   568.8
#Mann= 3 ,0,0
    1000     .09       0    1157    .055       0    1310     .09       0
#XS Ineff= 2 , 0
                            3296
Permanent Ineff=
       F       F
Bank Sta=1157,1310
XS Rating Curve= 0 ,0
Exp/Cntr=0.3,0.1