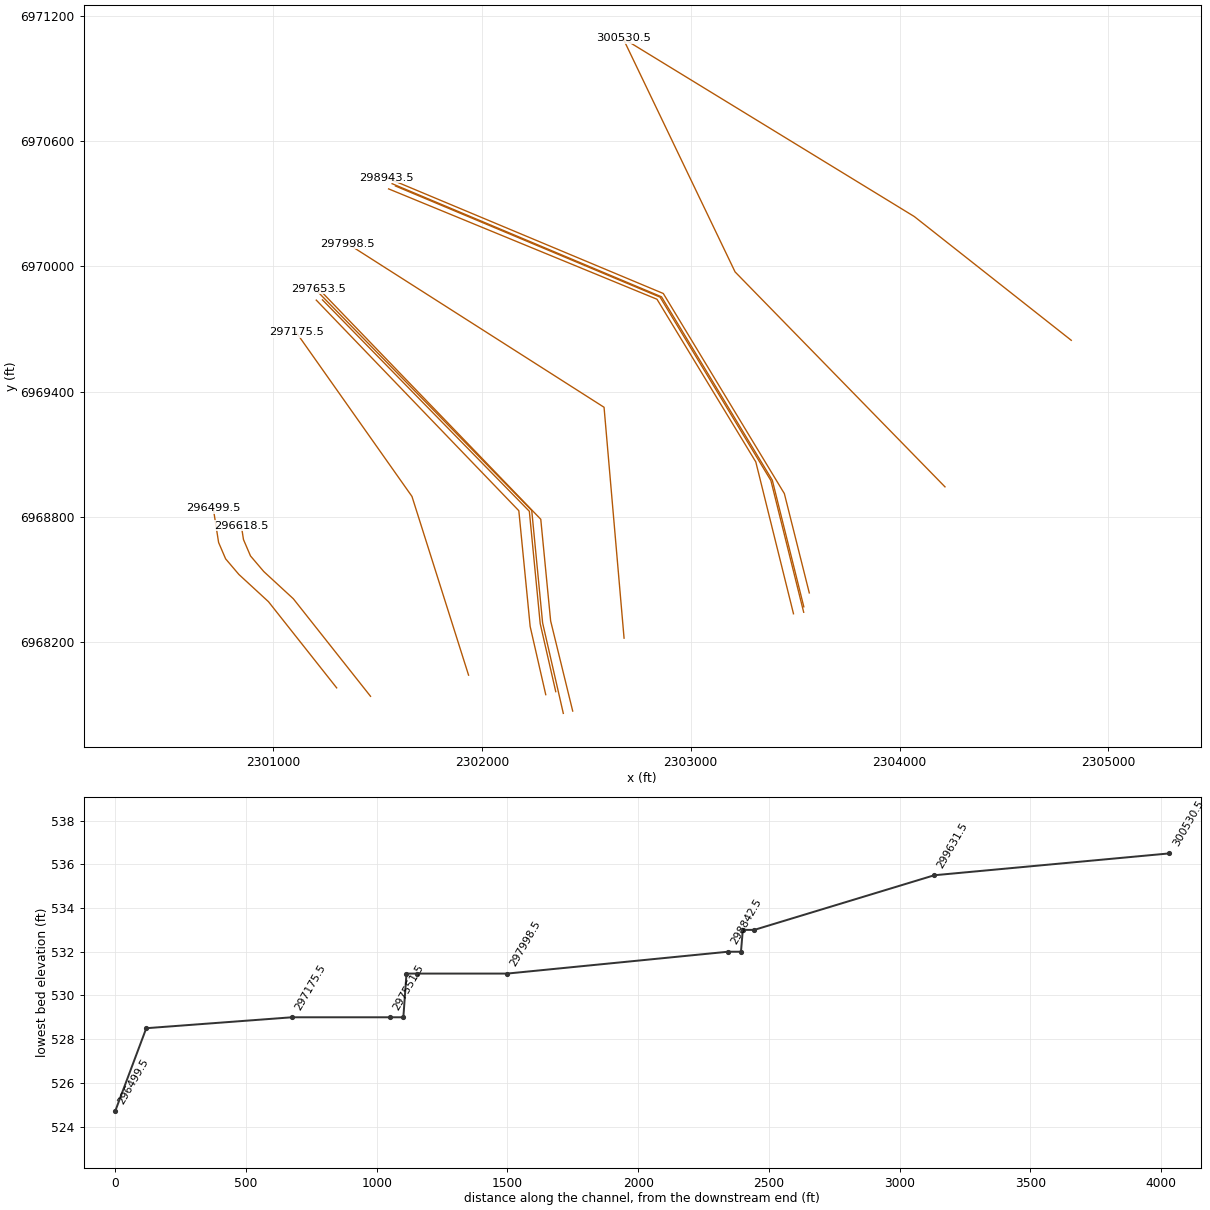
HEC-RAS study CDC_Consolidated_Model.prj: Upper Trinity CDC Consolidated Model

--- CDC_Consolidated_Model.g11 (geometry) --- (continued)

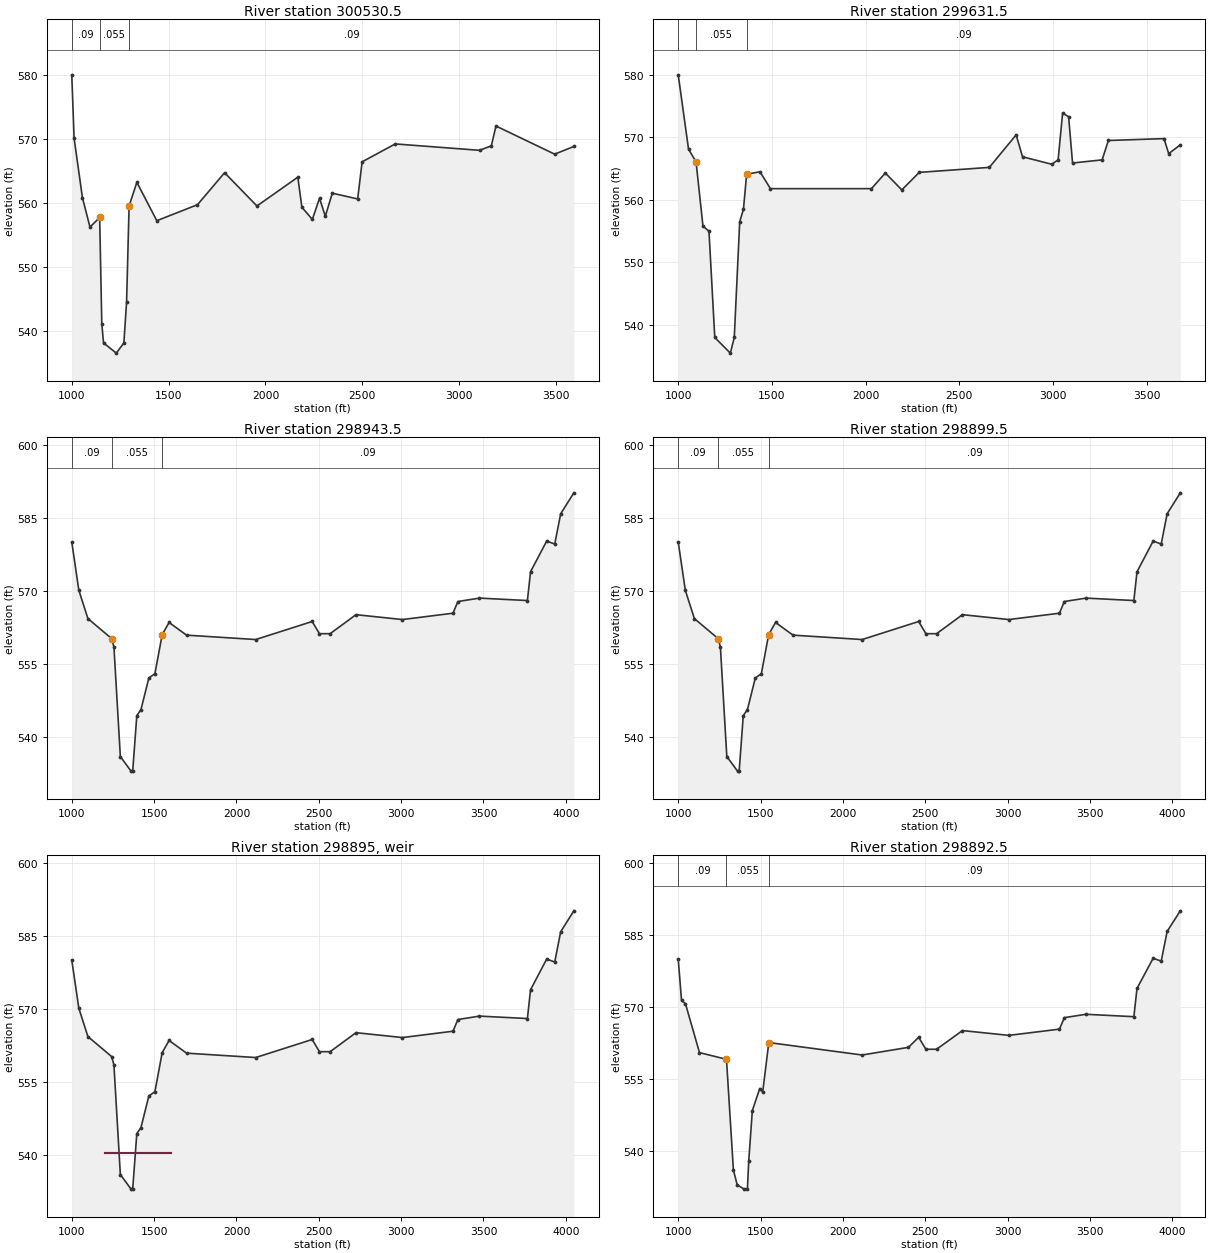
Type RM Length L Ch R = 1 ,300530.5,910,899,850
BEGIN DESCRIPTION:
Camp Carter area in ROB - conveyance removed from ponds
in ROB.
Channel data from 1975 USACE field survey.
END DESCRIPTION:
XS GIS Cut Line= 4
     2304822.302     6969645.464     2304656.012     6969776.577
     2304070.644     6970238.117     2302676.012     6971091.389
#Sta/Elev= 30
    1000     580    1012   570.1    1055   560.8    1094   556.2    1144   557.7
    1155   541.1    1164   538.1    1230   536.5    1269   538.1    1283   544.5
    1296   559.5    1336   563.2    1439   557.2    1649   559.7    1789   564.7
    1956   559.5    2167     564    2188   559.3    2242   557.4    2279   560.7
    2309   557.9    2345   561.5    2476   560.6    2499   566.4    2670   569.2
    3105   568.2    3166   568.9    3190     572    3493   567.6    3592   568.8
#Mann= 3 ,0,0
    1000     .09       0    1144    .055       0    1296     .09       0
#XS Ineff= 2 , 0
                            3190
Permanent Ineff=
       F       F
Bank Sta=1144,1296
XS Rating Curve= 0 ,0
Exp/Cntr=0.3,0.1

Type RM Length L Ch R = 1 ,299631.5,560,688,780
BEGIN DESCRIPTION:
Camp Carter area in ROB - conveyance removed from ponds
in ROB.
Channel data from 1975 USACE field survey.
END DESCRIPTION:
XS GIS Cut Line= 4
     2304217.732     6968943.697     2304051.233     6969114.188
     2303212.619      6969972.91     2302676.012     6971091.389
#Sta/Elev= 30
    1000     580    1055   568.1    1095   566.1    1132   555.8    1164     555
    1195     538    1278   535.5    1299     538    1328   556.5    1348   558.5
    1365   564.1    1436   564.5    1492   561.8    2031   561.8    2105   564.3
    2193   561.6    2286   564.4    2660   565.2    2803   570.4    2837   566.9
    2993   565.7    3027   566.4    3051   573.9    3083   573.3    3104   565.9
    3262   566.4    3295   569.5    3592   569.8    3617   567.4    3679   568.8
#Mann= 3 ,0,0
    1000     .09       0    1095    .055       0    1365     .09       0
#XS Ineff= 2 , 0
                            3346
Permanent Ineff=
       F       F
Bank Sta=1095,1365
XS Rating Curve= 0 ,0
Exp/Cntr=0.3,0.1

Type RM Length L Ch R = 1 ,298943.5,44,44,44
BEGIN DESCRIPTION:
Camp Carter area in ROB - conveyance removed from ponds
in ROB.
Channel data from 1975 USACE field survey.
END DESCRIPTION:
XS GIS Cut Line= 6
     2303567.857      6968435.92     2303448.517     6968911.441
      2303376.55     6969030.402     2303364.375     6969050.529
      2302868.87     6969869.589     2301541.644     6970424.909
#Sta/Elev= 30
    1000     580    1043   570.1    1098   564.3    1242   560.2    1256   558.5
    1295     536    1360     533    1370     533    1395   544.4    1420   545.6
    1468   552.1    1505     553    1549     561    1591   563.5    1697   560.9
    2117     560    2460   563.7    2504   561.2    2569   561.2    2726   565.1
    3008   564.1    3315   565.4    3345   567.8    3476   568.5    3767     568
    3786   573.9    3884   580.2    3933   579.6    3969   585.8    4049   590.1
#Mann= 3 ,0,0
    1000     .09       0    1242    .055       0    1549     .09       0
Bank Sta=1242,1549
XS Rating Curve= 0 ,0
Exp/Cntr=0.3,0.1

Type RM Length L Ch R = 1 ,298899.5,7,7,7
BEGIN DESCRIPTION:
One-foot upstream of channel dam.
END DESCRIPTION:
XS GIS Cut Line= 6
     2303541.772     6968369.241     2303517.616      6968466.28
     2303446.112     6968753.514     2303390.849     6968975.509
      2302860.31     6969853.644      2301570.19     6970395.445
#Sta/Elev= 30
    1000     580    1043   570.1    1098   564.3    1242   560.2    1256   558.5
    1295     536    1360     533    1370     533    1395   544.4    1420   545.6
    1468   552.1    1505     553    1549     561    1591   563.5    1697   560.9
    2117     560    2460   563.7    2504   561.2    2569   561.2    2726   565.1
    3008   564.1    3315   565.4    3345   567.8    3476   568.5    3767     568
    3786   573.9    3884   580.2    3933   579.6    3969   585.8    4049   590.1
#Mann= 3 ,0,0
    1000     .09       0    1242    .055       0    1549     .09       0
Bank Sta=1242,1549
XS Rating Curve= 0 ,0
Exp/Cntr=0.3,0.1

Type RM Length L Ch R = 5 ,298895  ,,,
BEGIN DESCRIPTION:
channel dam
crest elevation 540.5
END DESCRIPTION:
Node Name=channel dam
IW Pilot Flow=0
#Inline Weir SE= 2
    1200   540.5    1600   540.5
IW Dist,WD,Coef,Skew,MaxSub,Min_El,Is_Ogee,SpillHt,DesHd
2,5,3,0,0.95,, 0 ,,,2,2,
Inline Weir Flap Gates= 0
IW Outlet Rating Curve= 0 ,False,,

Type RM Length L Ch R = 1 ,298892.5,50,50,50
BEGIN DESCRIPTION:
Duplication of cross-section 298842.58.  One-foot downstream of channel dam.
END DESCRIPTION:
XS GIS Cut Line= 5
     2303541.083     6968343.313     2303439.143     6968752.815
     2303384.093     6968973.953     2302853.554     6969852.087
     2301586.591     6970384.164
#Sta/Elev= 30
    1000     580    1020   571.4    1044   570.7    1129   560.5    1293   559.1
    1335     536    1358   532.9    1400     532    1420     532    1428   537.8
    1450   548.4    1495     553    1513   552.3    1550   562.6    2117     560
    2398   561.6    2460   563.7    2504   561.2    2569   561.2    2726   565.1
    3008   564.1    3315   565.4    3345   567.8    3476   568.5    3767     568
    3786   573.9    3884   580.2    3933   579.6    3969   585.8    4049   590.1
#Mann= 3 ,0,0
    1000     .09       0    1293    .055       0    1550     .09       0
Bank Sta=1293,1550
XS Rating Curve= 0 ,0
Exp/Cntr=0.3,0.1

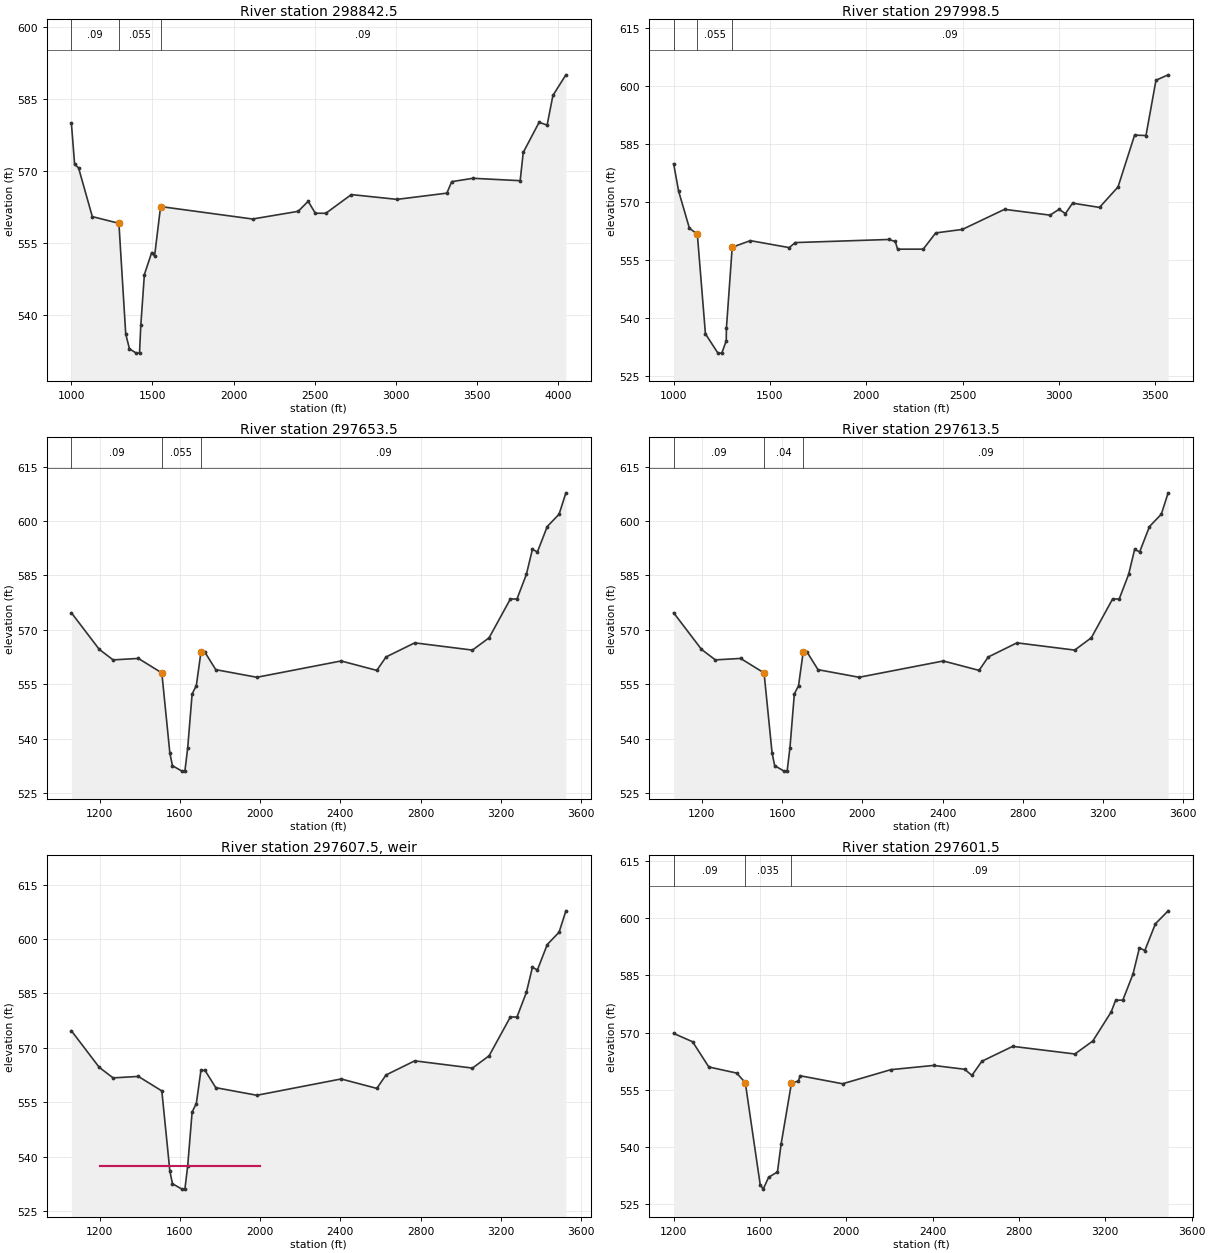
Type RM Length L Ch R = 1 ,298842.5,820,844,770
BEGIN DESCRIPTION:
51 feet downstream of channel dam.  Camp Carter area in
ROB - conveyance removed from ponds in ROB.
Channel data from 1975 USACE field survey.
END DESCRIPTION:
XS GIS Cut Line= 6
     2303492.279     6968336.068     2303492.279     6968336.069
     2303390.608     6968745.637     2303311.771     6969063.219
     2302838.729     6969842.041     2301553.591     6970370.509
#Sta/Elev= 30
    1000     580    1020   571.4    1044   570.7    1129   560.5    1293   559.1
    1335     536    1358   532.9    1400     532    1420     532    1428   537.8
    1450   548.4    1495     553    1513   552.3    1550   562.6    2117     560
    2398   561.6    2460   563.7    2504   561.2    2569   561.2    2726   565.1
    3008   564.1    3315   565.4    3345   567.8    3476   568.5    3767     568
    3786   573.9    3884   580.2    3933   579.6    3969   585.8    4049   590.1
#Mann= 3 ,0,0
    1000     .09       0    1293    .055       0    1550     .09       0
Bank Sta=1293,1550
XS Rating Curve= 0 ,0
Exp/Cntr=0.3,0.1

Type RM Length L Ch R = 1 ,297998.5,345,345,345
BEGIN DESCRIPTION:
Camp Carter area in ROB.  Conveyance removed below
elev. 559.2 in pond in ROB.
Channel data from 1975 USACE field survey.
END DESCRIPTION:
XS GIS Cut Line= 4
     2302680.992     6968219.227     2302663.012      6968426.67
     2302585.166     6969324.825      2301357.51     6970107.859
#Sta/Elev= 30
    1000     580    1026   572.9    1082   563.3    1123   561.8    1165     536
    1230     531    1250     531    1273   534.2    1274   537.5    1304   558.4
    1398   560.1    1600   558.3    1631   559.6    2115   560.4    2150   559.9
    2162   557.9    2295   557.9    2360   562.1    2498     563    2717   568.2
    2953   566.7    3000   568.2    3033   567.1    3070   569.8    3210   568.7
    3306     574    3392   587.4    3451   587.3    3503   601.6    3566     603
#Mann= 3 ,0,0
    1000     .09       0    1123    .055       0    1304     .09       0
Bank Sta=1123,1304
XS Rating Curve= 0 ,0
Exp/Cntr=0.3,0.1

Type RM Length L Ch R = 1 ,297653.5,40,40,40
BEGIN DESCRIPTION:
41 feet upstream of channel dam.  Effective flow limit
set at sta 1059 in LOB at Anahuac Street.
Channel data from 1975 USACE field survey.
END DESCRIPTION:
XS GIS Cut Line= 6
     2302435.067     6967870.107     2302329.395     6968301.809
     2302319.294     6968405.873     2302282.154     6968788.533
      2302170.46      6968904.18     2301217.949     6969892.715
#Sta/Elev= 30
    1059   574.7    1198   564.6    1267   561.7    1393   562.1    1510   558.1
    1550     536    1563   532.5    1610     531    1625     531    1639   537.4
    1661   552.3    1682   554.6    1705   563.8    1725   563.8    1779     559
    1984   556.9    2404   561.4    2582   558.8    2628   562.5    2771   566.4
    3059   564.4    3142   567.8    3248   578.5    3281   578.5    3328   585.3
    3358   592.2    3383   591.5    3432   598.5    3491   601.9    3525   607.8
#Mann= 3 ,0,0
    1059     .09       0    1510    .055       0    1705     .09       0
Bank Sta=1510,1705
XS Rating Curve= 0 ,0
Exp/Cntr=0.3,0.1

Type RM Length L Ch R = 1 ,297613.5,12,12,12
BEGIN DESCRIPTION:
One-foot upstream of channel dam.
END DESCRIPTION:
XS GIS Cut Line= 6
     2302390.048     6967859.061     2302365.237     6967967.576
     2302290.968     6968292.407     2302280.749     6968397.699
     2302238.872     6968830.834     2301202.719     6969889.758
#Sta/Elev= 30
    1059   574.7    1198   564.6    1267   561.7    1393   562.1    1510   558.1
    1550     536    1563   532.5    1610     531    1625     531    1639   537.4
    1661   552.3    1682   554.6    1705   563.8    1725   563.8    1779     559
    1984   556.9    2404   561.4    2582   558.8    2628   562.5    2771   566.4
    3059   564.4    3142   567.8    3248   578.5    3281   578.5    3328   585.3
    3358   592.2    3383   591.5    3432   598.5    3491   601.9    3525   607.8
#Mann= 3 ,0,0
    1059     .09       0    1510     .04       0    1705     .09       0
Bank Sta=1510,1705
XS Rating Curve= 0 ,0
Exp/Cntr=0.3,0.1

Type RM Length L Ch R = 5 ,297607.5,,,
BEGIN DESCRIPTION:
channel dam
crest elevation 537.4
END DESCRIPTION:
Node Name=channel dam
IW Pilot Flow=0
#Inline Weir SE= 2
    1200   537.4    2000   537.4
IW Dist,WD,Coef,Skew,MaxSub,Min_El,Is_Ogee,SpillHt,DesHd
1,10,3,0,0.95,, 0 ,,,2,2,
Inline Weir Flap Gates= 0
IW Outlet Rating Curve= 0 ,False,,

Type RM Length L Ch R = 1 ,297601.5,50,50,50
BEGIN DESCRIPTION:
One-foot downstream of channel dam.
*********************************************************************
Fort Worth Floodway limit.
END DESCRIPTION:
XS GIS Cut Line= 6
     2302353.868     6967963.117     2302279.514     6968288.317
     2302269.331     6968393.232     2302269.295     6968393.608
     2302227.418     6968826.743     2301236.769     6969839.163
#Sta/Elev= 30
    1200   569.8    1288   567.6    1363     561    1492   559.4    1532   556.9
    1601   530.2    1615     529    1640   532.1    1681   533.5    1698   540.8
    1746   556.8    1778   557.3    1786   558.7    1983   556.6    2207   560.3
    2404   561.4    2548   560.4    2582   558.8    2628   562.5    2771   566.4
    3059   564.4    3142   567.8    3227   575.4    3248   578.5    3281   578.5
    3328   585.3    3358   592.2    3383   591.5    3432   598.5    3491   601.9
#Mann= 3 ,0,0
    1200     .09       0    1532    .035       0    1746     .09       0
Bank Sta=1532,1746
XS Rating Curve= 0 ,0
Exp/Cntr=0.3,0.1

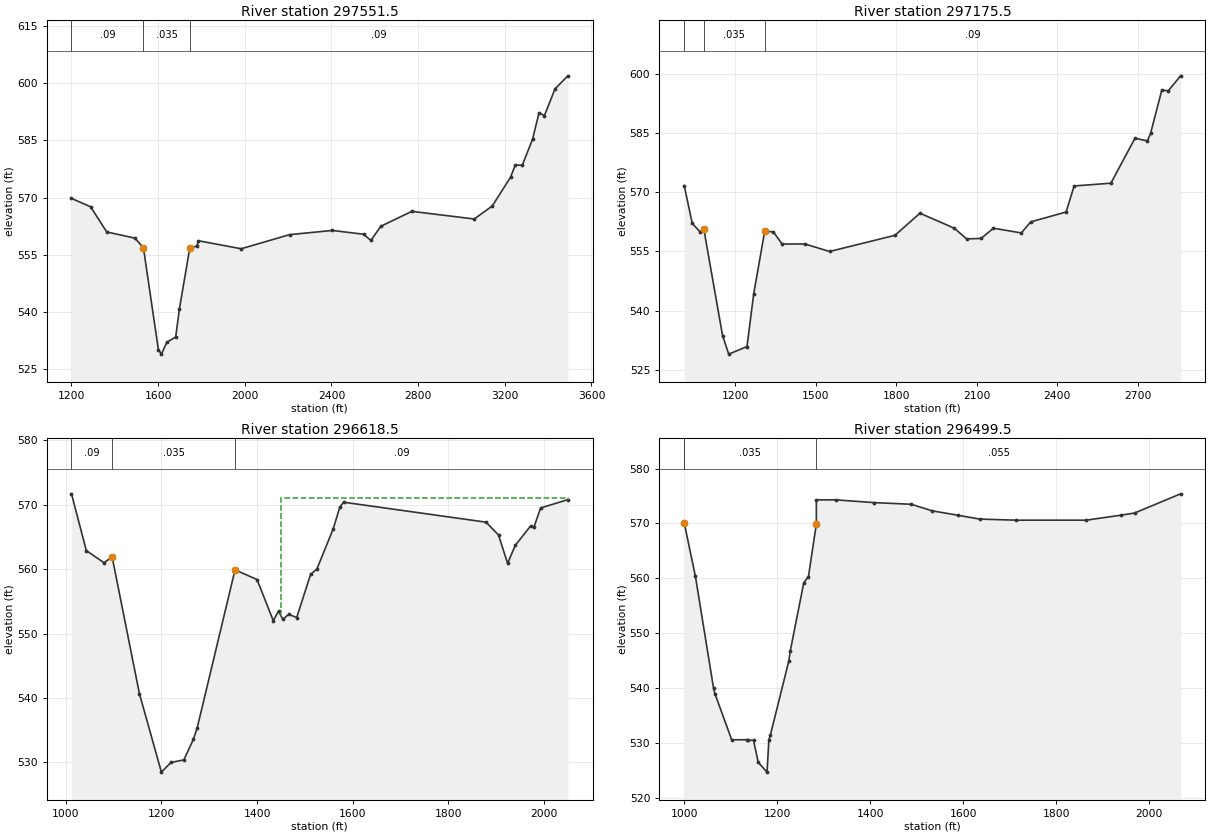
Type RM Length L Ch R = 1 ,297551.5,360,376,400
BEGIN DESCRIPTION:
51 feet downstream of channel dam.  Effective flow
limit set at sta 1200 in LOB at Anahuac Street.
Channel data from 1975 USACE field survey.
END DESCRIPTION:
XS GIS Cut Line= 5
     2302305.986     6967948.672      2302231.34     6968275.151
     2302221.284      6968378.76     2302177.049     6968829.464
     2301207.155     6969837.865
#Sta/Elev= 30
    1200   569.8    1288   567.6    1363     561    1492   559.4    1532   556.9
    1601   530.2    1615     529    1640   532.1    1681   533.5    1698   540.8
    1746   556.8    1778   557.3    1786   558.7    1983   556.6    2207   560.3
    2404   561.4    2548   560.4    2582   558.8    2628   562.5    2771   566.4
    3059   564.4    3142   567.8    3227   575.4    3248   578.5    3281   578.5
    3328   585.3    3358   592.2    3383   591.5    3432   598.5    3491   601.9
#Mann= 3 ,0,0
    1200     .09       0    1532    .035       0    1746     .09       0
Bank Sta=1532,1746
XS Rating Curve= 0 ,0
Exp/Cntr=0.3,0.1

Type RM Length L Ch R = 1 ,297175.5,520,557,600
BEGIN DESCRIPTION:
Cross-section WF363.  Effective flow limit set at Carswell Levee in LOB.
Channel data from 1975 USACE field survey.
END DESCRIPTION:
XS GIS Cut Line= 4
     2301936.412     6968042.098      2301876.71     6968230.633
     2301665.451     6968897.763     2301110.855     6969684.026
#Sta/Elev= 30
    1009   571.7    1039   562.1    1069   559.9    1082   560.7    1152   533.7
    1175     529    1243   530.9    1268   544.2    1309   560.1    1341     560
    1374   556.9    1459   556.9    1551     555    1795   559.1    1888   564.7
    2016   560.9    2062   558.2    2116   558.3    2162   560.9    2266   559.7
    2301   562.5    2433     565    2463   571.6    2600   572.3    2690   583.7
    2736     583    2748   584.9    2790   595.9    2814   595.7    2860   599.5
#Mann= 3 ,0,0
    1009     .09       0    1082    .035       0    1309     .09       0
Bank Sta=1082,1309
XS Rating Curve= 0 ,0
Exp/Cntr=0.3,0.1

Type RM Length L Ch R = 1 ,296618.5,119,119,119
BEGIN DESCRIPTION:
120 feet upstream of Meandering Road.  Effective flow
limit set at Carswell Levee in LOB.  Ineffective flow at sta 1450 due to roadway embankment.
Channel data from 1975 USACE field survey.
END DESCRIPTION:
XS GIS Cut Line= 6
     2301466.989     6967940.811     2301097.386     6968407.791
     2300955.614     6968538.369      2300892.19     6968612.986
     2300858.612     6968691.333     2300848.185     6968758.063
#Sta/Elev= 30
    1012   571.7    1043   562.9    1080     561    1097   561.9    1154   540.7
    1200   528.5    1220     530    1247   530.4    1267   533.6    1275   535.4
    1354   559.9    1400   558.4    1434     552    1445   553.5    1454   552.2
    1466     553    1483   552.5    1512   559.2    1525     560    1559   566.2
    1573   569.6    1581   570.4    1879   567.3    1905   565.3    1924   560.9
    1940   563.7    1972   566.7    1979   566.5    1993   569.5    2050   570.8
#Mann= 3 ,0,0
    1012     .09       0    1097    .035       0    1354     .09       0
#XS Ineff= 2 , 0
       0                    1450       0     571
Permanent Ineff=
       F       F
Bank Sta=1097,1354
XS Rating Curve= 0 ,0
Exp/Cntr=0.3,0.1

Type RM Length L Ch R = 1 ,296499.5,39,39,39
BEGIN DESCRIPTION:
One-foot upstream of Meandering Road.  Duplication of previous bridge cross-section without bridge piers.  Effective flow limit set at Carswell Levee in LOB.
END DESCRIPTION:
XS GIS Cut Line= 6
     2301304.799      6967981.27     2300978.253      6968393.85
     2300836.481     6968524.428     2300773.057     6968599.045
      2300739.48     6968677.392     2300713.865     6968841.321
#Sta/Elev= 29
    1000   570.1    1024   560.4    1063     540    1066     539    1102   530.6
    1135   530.6    1138   530.5    1149   530.5    1159   526.5    1178   524.7
    1182   530.6    1185   531.4    1225     545    1228   546.8    1257   559.2
    1267   560.3    1284   569.9    1284   574.3    1326   574.3    1408   573.8
    1488   573.5    1533   572.3    1588   571.5    1635   570.8    1713   570.6
    1864   570.6    1938   571.5    1968   571.9    2067   575.4
#Mann= 3 ,0,0
    1000    .055       0    1000    .035       0    1284    .055       0
Bank Sta=1000,1284
XS Rating Curve= 0 ,0
Exp/Cntr=0.5,0.3