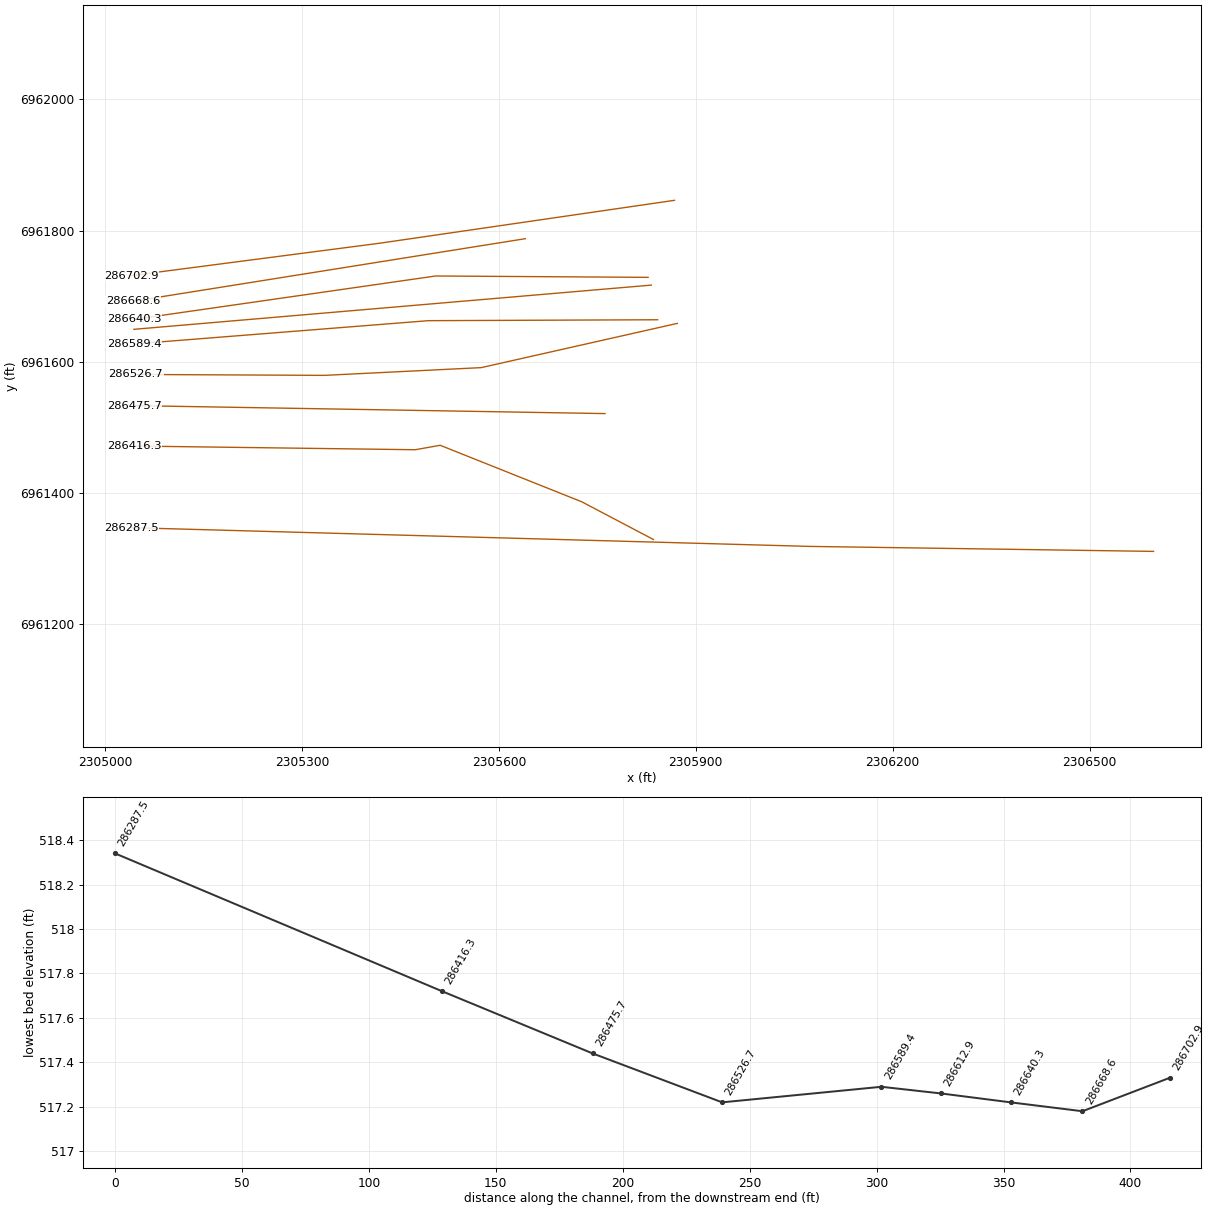
HEC-RAS study CDC_Consolidated_Model.prj: Upper Trinity CDC Consolidated Model

--- CDC_Consolidated_Model.g11 (geometry) --- (continued)

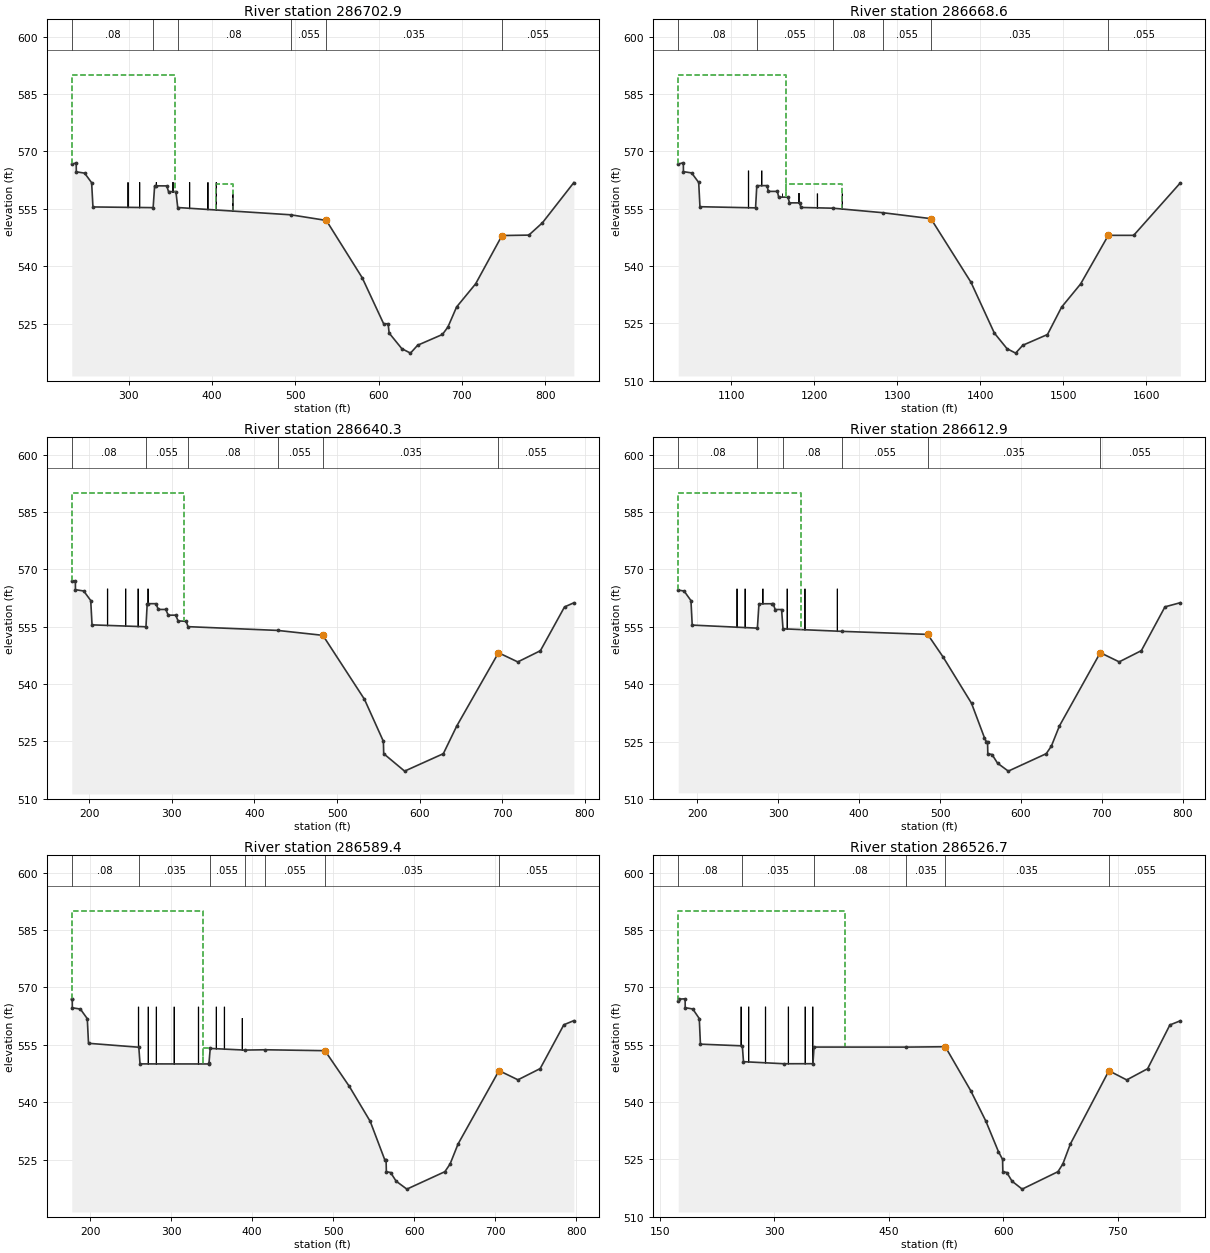
Type RM Length L Ch R = 1 ,286702.9,31,34.3,33.68
XS GIS Cut Line= 3
  2305867.6943786961846.058258012305419.083267696961780.78048025
2305040.61104545 6961731.4749247
#Sta/Elev= 30
   231.4  566.66  236.74     567  236.84  564.67  246.81  564.33  255.26  561.83
  256.84   555.5  329.12  555.32  330.92     561   332.2  561.01  345.55     561
  347.57   559.5   356.5   559.5  358.64  555.35  494.37  553.45   537.1  551.98
  580.24     537  605.94     525  611.34     525  612.53  522.58  627.79  518.49
  638.16  517.33  646.77  519.39  676.52   522.2  683.15  524.15  693.53  529.37
  716.43  535.43  748.07  548.03  780.35  548.15  796.66  551.37  834.37  561.87
#Mann= 6 ,-1,0
   231.4     .08       0  329.12    .055       0  358.64     .08       0
  494.37    .055       0   537.1    .035       0  748.07    .055       0
#XS Ineff= 2 ,-1
   231.4  355.36     590   404.1   424.6   561.5
Permanent Ineff=
       F       T
#Block Obstruct= 8 ,-1
   298.1   298.6     562   312.1   312.6     562   332.1   332.6     562
   352.1   352.6     562   372.1   372.6     562   394.1   394.6     562
   404.1   404.6     562   424.1   424.6     559
#XS Lid=6
   231.4     565  564.99   298.1     565  564.99   298.1     565     561
   404.6     565     561   404.6     565  564.99  834.37     565  564.99
Bank Sta=537.1,748.07
XS Rating Curve= 0 ,0
Exp/Cntr=0.3,0.1

Type RM Length L Ch R = 1 ,286668.6,31,28.3,25
BEGIN DESCRIPTION:
Ineffective flow set in LOB.
Effective flow limit set at White Settlement Levee in ROB.
END DESCRIPTION:
XS GIS Cut Line= 2
2305640.352914626961787.60317843 2305043.1377575  6961692.325724
#Sta/Elev= 30
 1036.26  566.65 1042.41     567 1042.51  564.67 1052.41  564.33 1060.91  561.83
 1062.42  555.49 1129.41  555.19 1130.89     561 1143.24  561.01 1144.77   559.5
 1155.66   559.5 1157.24     558 1168.48     558 1170.25   556.5 1182.34   556.5
 1184.14   555.3 1222.79   555.1 1282.38  553.93 1340.58  552.37 1388.83  535.74
 1417.04  522.43  1432.3  518.34 1442.67  517.18 1451.28  519.24 1481.03  522.05
 1498.04  529.22 1520.94  535.28 1554.28     548 1584.86     548 1641.03  561.72
#Mann= 6 ,-1,0
 1036.26     .08       0 1130.89    .055       0 1222.79     .08       0
 1282.38    .055       0 1340.58    .035       0 1554.28    .055       0
#XS Ineff= 2 ,-1
 1036.26 1165.58     590 1165.58 1233.56   561.5
Permanent Ineff=
       F       T
#Block Obstruct= 6 ,-1
 1120.06 1120.56     565 1136.06 1136.56     565 1161.06 1161.56     559
 1181.06 1181.56     559 1203.06 1203.56     559 1233.06 1233.56     559
Bank Sta=1340.58,1554.28
XS Rating Curve= 0 ,0
Exp/Cntr=0.3,0.1

Type RM Length L Ch R = 1 ,286640.3,37,27.4,22
XS GIS Cut Line= 3
  2305827.4166016961728.69714692 2305503.80548996961730.78048025
2305044.777712116961664.80825803
#Sta/Elev= 30
  178.78  566.95  183.14     567  183.24  564.67  193.24  564.33  201.74  561.83
  203.32  555.47  268.63  554.97  270.14     561  271.52  561.01  280.64  561.01
  283.62   559.5  292.65   559.5  295.61     558  304.65  558.01  307.58   556.5
  317.23   556.4  319.59     555  427.98  554.02  482.91  552.73  533.26     536
   556.2     525  556.55  521.78  581.86  517.22  628.76  521.78  645.01  529.01
  695.57  548.18  718.93  545.78  746.33  548.71  775.53  560.16  786.83  561.24
#Mann= 6 ,-1,0
  178.78     .08       0  268.63    .055       0  319.59     .08       0
  427.98    .055       0  482.91    .035       0  695.57    .055       0
#XS Ineff= 2 , 0
       0  314.94     590               0
Permanent Ineff=
       F       F
#Block Obstruct= 4 ,-1
  221.28  221.78     565  243.28  243.78     565  258.28  258.78     565
  270.28  270.78     565
Bank Sta=482.91,695.57
XS Rating Curve= 0 ,0
Exp/Cntr=0.3,0.1

Type RM Length L Ch R = 1 ,286612.9,26,23.5,23
XS GIS Cut Line= 2
  2305832.2777126961716.891591332305044.083267666961649.53048024
#Sta/Elev= 30
  176.29  564.58  183.53  564.33  192.01  561.83  193.56  555.43  274.13  554.63
  276.07     561  292.28  561.01  293.68     561   296.1   559.5  304.04   559.5
   305.8  554.46     379  553.79  484.61     553   503.7  547.08   538.8     535
  554.77     526  556.97     525   558.6     525  558.95  521.82  564.16   521.6
  570.99  519.34  584.26  517.26  631.16  521.82  637.56  523.82  647.41  529.05
  697.97  548.22  721.33  545.82  748.73  548.75  777.93   560.2  796.89  561.28
#Mann= 6 ,-1,0
  176.29     .08       0  274.13    .055       0   305.8     .08       0
     379    .055       0  484.61    .035       0  697.97    .055       0
#XS Ineff= 2 , 0
       0  328.61     590               0
Permanent Ineff=
       F       F
#Block Obstruct= 6 ,-1
  248.09  248.59     565  258.09  258.59     565  280.09  280.59     565
  310.09  310.59     565  332.09  332.59     565  372.09  372.59     565
#XS Lid=8
  167.29     565  564.99  248.09     565  564.99  248.09     568     564
   336.6     568     564   336.6     565     561   372.6     565     561
   372.6     565  564.99  796.89     565  564.99
Bank Sta=484.61,697.97
XS Rating Curve= 0 ,0
Exp/Cntr=0.3,0.1

Type RM Length L Ch R = 1 ,286589.4,72.82,62.74,55
XS GIS Cut Line= 4
  2305841.9999346961664.113813582305492.69437879 6961662.7249247
2305045.472156556961627.308258012305044.777712116961626.61381355
#Sta/Elev= 30
  177.38  566.99  177.96     567  178.06  564.67     188  564.33  196.52  561.83
  198.03  555.39   260.1  554.36   261.6  550.01  346.36  549.99  346.66  550.12
  348.22  554.05  390.62  553.62  415.99   553.7  489.78  553.46  519.92  544.11
  545.62     535  563.51     525  565.21     525  565.56  521.85  570.77  521.63
   577.6  519.37  590.87  517.29  637.77  521.85  644.17  523.85  654.02  529.08
  704.58  548.25  727.94  545.85  755.34  548.78  784.54  560.23  796.89  561.31
#Mann= 7 ,-1,0
  177.38     .08       0   260.1    .035       0  348.22    .055       0
  390.62     .08       0  415.99    .055       0  489.78    .035       0
  704.58    .055       0
#XS Ineff= 2 ,-1
  177.38  338.84     590  338.84  348.22 554.053
Permanent Ineff=
       F       T
#Block Obstruct= 8 ,-1
  258.88  259.38     565  270.88  271.38     565  280.88  281.38     565
  302.88  303.38     565  332.88  333.38     565  354.88  355.38     565
  364.88  365.38     565  386.88  387.38     562
#XS Lid=8
  177.38     565  564.99  258.88     565  564.99  258.88     568     564
  365.38     568     564  365.38     565     561  386.88     565     561
  386.88     565  564.99  796.89     565  564.99
Bank Sta=489.78,704.58
XS Rating Curve= 0 ,0
Exp/Cntr=0.3,0.1

Type RM Length L Ch R = 1 ,286526.7,56,51,44.94
XS GIS Cut Line= 4
  2305871.8610456961658.558258012305573.249934356961591.19714692
2305334.361045486961579.391591342305046.861045486961580.78048025
#Sta/Elev= 30
  173.98  566.39  175.06   566.9     183     567  183.14  564.67  193.03  564.33
  201.56  561.83  203.07  555.13     258  554.69   259.5  550.55  312.55  550.01
  350.51  550.02     352  554.37  472.36  554.36  524.03  554.46  557.27     543
  577.22     535  593.75     527  599.12     525  599.47  521.78  604.68  521.56
  611.51   519.3  624.78  517.22  671.68  521.78  678.08  523.78  687.93  529.01
  738.49  548.18  761.85  545.78  789.25  548.71  818.45  560.16  832.09  561.24
#Mann= 6 ,-1,0
  173.98     .08       0     258    .035       0     352     .08       0
  472.36    .035       0  524.03    .035       0  738.49    .055       0
#XS Ineff= 2 , 0
       0  392.46     590               0
Permanent Ineff=
       F       F
#Block Obstruct= 6 ,-1
  255.48  255.98     565  265.48  265.98     565  287.48  287.98     565
  317.48  317.98     565  339.48  339.98     565  349.48  349.98     565
Bank Sta=524.03,738.49
XS Rating Curve= 0 ,0
Exp/Cntr=0.3,0.1

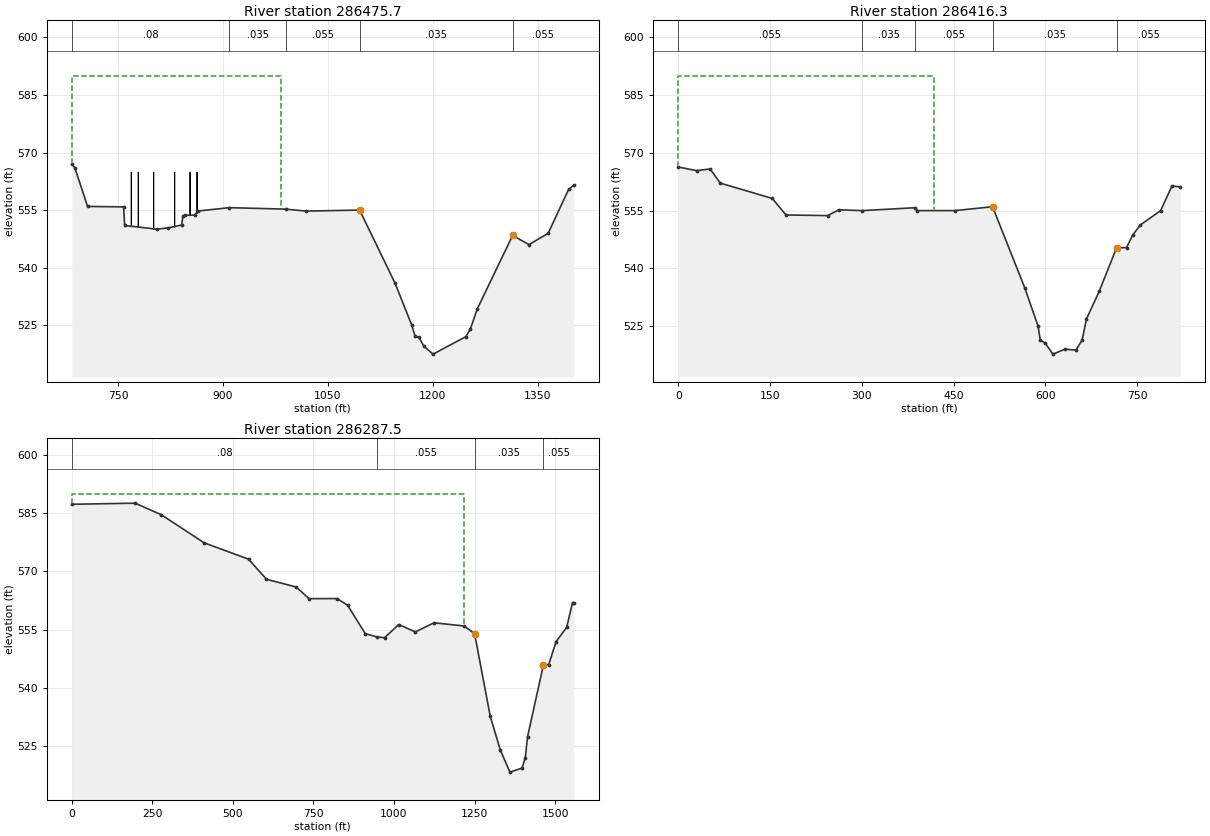
Type RM Length L Ch R = 1 ,286475.7,60,59.36,60
BEGIN DESCRIPTION:
Ineffective flow set in LOB.
Effective flow limit set at White Settlement Levee in ROB.
END DESCRIPTION:
XS GIS Cut Line= 2
2305761.856655786961521.16142448 2305044.2967177 6961533.3233898
#Sta/Elev= 30
  683.75  566.98  688.03  566.07  706.34  555.95  757.84  555.83  759.34  550.98
  805.45  550.02  821.79  550.36  841.04  551.12  842.54  553.47  844.95  553.66
  859.23  553.68  864.29  554.75  909.07  555.63  989.88  555.24 1018.79  554.73
  1095.2     555 1145.71     536 1169.73     525 1174.56  522.08 1180.12  521.78
 1186.95  519.52 1200.22  517.44 1247.12     522 1253.52     524 1263.37  529.23
 1313.93   548.4 1337.29     546 1364.69  548.93 1393.89  560.38 1401.41  561.46
#Mann= 5 ,-1,0
  683.75     .08       0  909.07    .035       0  989.88    .055       0
  1095.2    .035       0 1313.93    .055       0
#XS Ineff= 2 , 0
       0  982.41     590               0
Permanent Ineff=
       F       F
#Block Obstruct= 6 ,-1
  767.85  768.35     565  777.85  778.35     565  799.85  800.35     565
  829.85  830.35     565  851.85  852.35     565  861.85  862.35     565
Bank Sta=1095.2,1313.93
XS Rating Curve= 0 ,0
Exp/Cntr=0.3,0.1

Type RM Length L Ch R = 1 ,286416.3,129.78,128.8,126.88
XS GIS Cut Line= 5
  2305835.5536526961329.32894817 2305726.48411256961386.75425363
2305510.663128826961472.881174682305472.642295456961466.11034134
2305044.777712116961471.75270247
#Sta/Elev= 30
       0  566.32   29.94  565.38   52.04  565.81   68.72  562.13  153.68  558.16
  176.15  553.86   244.3   553.7  262.52   555.2  300.78  554.99  387.49  555.75
  390.68  554.99  452.51     555  513.86     556  566.31     535  588.23     525
   591.8  521.38  599.92  520.56  612.59  517.72  632.15  519.01  650.23  518.76
  660.28  521.38  667.35  526.83  688.32  534.09  716.73  545.38  732.89  545.38
  742.92  548.64  755.56  551.28  788.67     555  806.98  561.38  820.77  561.18
#Mann= 5 ,-1,0
       0    .055       0  300.78    .035       0  387.49    .055       0
  513.86    .035       0  716.73    .055       0
#XS Ineff= 2 , 0
       0     418     590               0
Permanent Ineff=
       F       F
Bank Sta=513.86,716.73
XS Rating Curve= 0 ,0
Exp/Cntr=0.3,0.1

Type RM Length L Ch R = 1 ,286287.5,143.69,145.35,146.57
BEGIN DESCRIPTION:
Upstream of White Settlement Road.
Ineffective flow set in LOB.
Effective flow limit set at White Settlement Levee in ROB.
------------------------------------------------------
CDC FW121615-01 Crystal Springs
Located in LOB.
Cross-section 286287.5 - 286754.9
-------------------------------------------------------
END DESCRIPTION:
XS GIS Cut Line= 3
 2306597.3789175 6961311.2435467 2306074.0756047 6961318.8419955
 2305039.7221956 6961347.3910476
#Sta/Elev= 30
       0  587.31  196.81  587.59  277.82  584.62  410.83  577.38   548.7  573.17
  604.23     568  696.66     566  736.34     563   822.8  563.03  855.78  561.34
   910.8     554  947.48  553.13  970.51  552.96 1014.88  556.35 1066.11  554.44
 1123.96  556.79 1217.08  555.98 1250.11     554 1298.72  532.69 1330.08     524
 1359.69  518.34 1397.33  519.38 1407.38     522 1414.45  527.45 1463.83     546
 1479.99     546 1502.66   551.9 1535.77  555.62 1554.08     562  1558.1   561.8
#Mann= 4 ,-1,0
       0     .08       0  947.48    .055       0 1250.11    .035       0
 1463.83    .055       0
#XS Ineff= 1 ,-1
       0 1216.62     590
Permanent Ineff=
       F
Bank Sta=1250.11,1463.83
XS Rating Curve= 0 ,0
Exp/Cntr=0.5,0.3