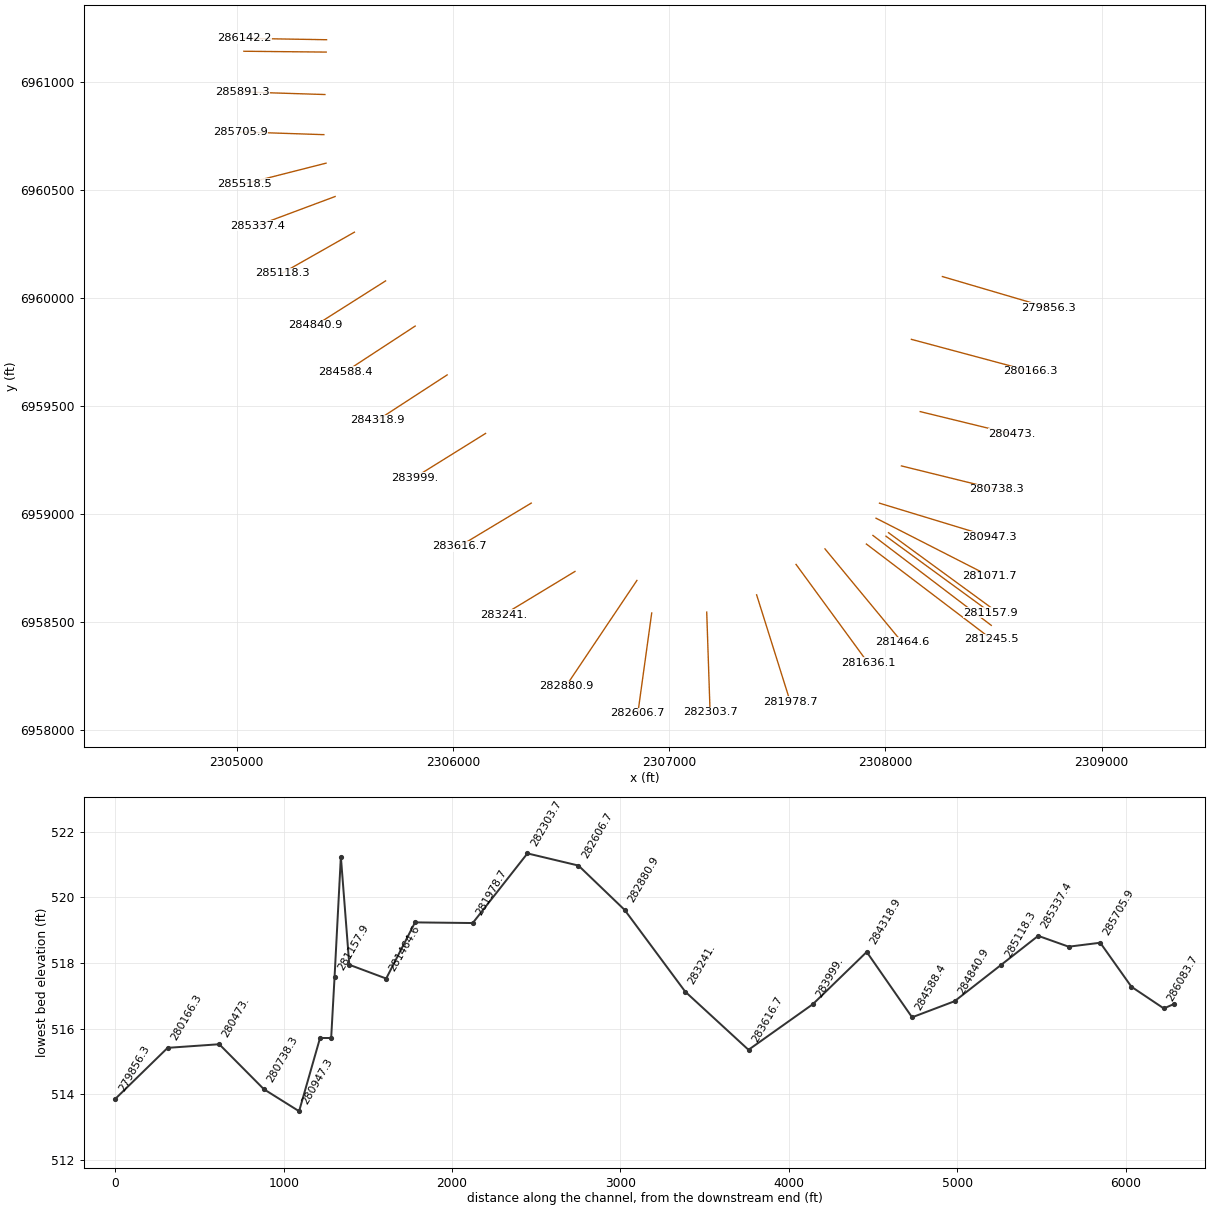
HEC-RAS study CDC_Consolidated_Model.prj: Upper Trinity CDC Consolidated Model

--- CDC_Consolidated_Model.g11 (geometry) --- (continued)

Type RM Length L Ch R = 3 ,286214.2,,,
BEGIN DESCRIPTION:
White Settlement Road - upper crossing
Double bridges - total bridge width set at 70 feet.
Bridge data from USACE 1975 survey.
Note:  Internal bridge cross-sections modified to represent geometry under bridge.
END DESCRIPTION:
Node Name=White Settlement
Bridge Culvert--1,0,-1,-1, 0
Deck Dist Width WeirC Skew NumUp NumDn MinLoCord MaxHiCord MaxSubmerge Is_Ogee
38.3,70,2.6,0, 6, 2, , , 0.95, 0, 0,0,,
  721.88 1236.88 1236.88 1501.88 1501.88  1558.1
     564     564     568     568     564     564
     460     450  563.46  563.46     450     450
  352.22  617.22
     568     568
  563.46  563.46
Pier Skew, UpSta & Num, DnSta & Num=  ,1295.38, 2 ,410.72, 2 , 0 , 0 , 0 ,,
       3       3
     500     567
       3       3
     500     567
Pier Skew, UpSta & Num, DnSta & Num=  ,1369.88, 2 ,485.22, 2 , 0 , 0 , 0 ,,
       3       3
     500     567
       3       3
     500     567
Pier Skew, UpSta & Num, DnSta & Num=  ,1443.88, 2 ,559.22, 2 , 0 , 0 , 0 ,,
       3       3
     500     567
       3       3
     500     567
BR Coef=-1 , 0 , 0 ,, 0 ,,,0.8,-1,,0,
WSPro=,,,, 1 ,,,, 0 ,,,, 0 ,,,,-1 ,-1 ,-1 , 0 , 0 , 0 , 0 , 0
BR U #Sta/Elev= 468
       0  587.31   36.76  587.37   65.73  587.67  101.41  587.97  126.29  587.34
  157.96  586.84  177.77  587.39  183.22  587.46  186.92  587.49   191.3  587.54
  196.44  587.59  196.81  587.59  200.85  587.33  201.08  587.31  204.33   587.1
  205.83  587.01  208.35  586.85   210.1  586.75   212.4   586.6  216.37  586.36
  219.11  586.21  219.41   586.2   221.7  586.07  224.55  585.92  226.59   585.8
  227.55  585.75   229.2  585.65  230.69  585.57  232.21  585.48  234.37  585.37
  239.36  585.62  239.57  585.62  244.07  585.81  277.82  584.62  290.33     584
  311.15  582.71  322.27     582  330.26     582  339.79  581.57  344.14  581.32
  347.13  581.22  357.76  580.56  359.02  580.48  366.76     580  372.33  579.63
  378.32  579.27  379.11  579.22  395.91     578  410.83  577.38  423.47  577.02
  450.74  576.38  460.62     576  462.06  575.94  462.32  575.92  477.65  575.26
  480.58  575.05  483.27  574.85  488.24  574.63  491.04   574.4  494.84  574.11
  495.28  574.09  496.32     574  499.07  573.92   501.8  573.83  503.59  573.79
  511.83  573.57  516.93  573.46  521.96  573.37  524.59   573.3  524.73  573.29
  532.07  573.25  540.79  573.28  541.91  573.27  544.41  573.29  548.55  573.17
   548.7  573.17  549.81  573.08  555.73   572.8  557.47  572.61  558.36  572.53
  561.72  572.25  563.51  572.06  566.08  571.74  567.67  571.52  569.74  571.27
  570.66  571.15   573.2  570.84  574.93  570.61  577.95  570.19  579.58     570
  583.99  569.52  588.26  569.06  589.44  568.93  590.35  568.81  593.18  568.54
  593.87   568.5  604.23     568  611.61     568  614.25  567.93  615.86  567.91
  616.94  567.92  617.76  567.95  619.63  567.98  620.97  567.98   622.6  567.95
  624.33  567.93   626.9  567.89  628.74  567.84  630.65  567.82  632.55  567.76
  633.26  567.75  635.54  567.68  637.54   567.6  638.69  567.59  642.38  567.45
  642.99  567.42  644.19  567.39   645.6  567.37  648.08  567.28  660.16     566
  696.66     566  697.86  565.88  707.73  564.84  715.14     564  716.27   563.9
  716.76  563.89  722.95  563.49  724.77  563.47  729.66   563.2  732.76  563.17
  736.34     563  760.71  562.81  762.76  562.89  768.61  562.83  770.21  562.93
  772.65  563.07  775.48  563.22  780.39  563.14  781.89  563.25  786.18  563.17
  787.05  563.21  788.87  563.21  791.49  563.16   794.7  563.13  796.35  563.06
  797.02  563.02  798.08     563  798.85  562.95  799.75  562.93  800.47  562.89
  801.16  562.87  802.22   562.8  802.82  562.78     804  562.72  805.48  562.61
  807.78  562.45  809.68   562.3  811.22  562.19  813.58  562.62  813.83  562.57
  814.31   562.6  815.98  562.79  816.63  562.83  817.11  562.88  820.01  562.97
  821.32  563.03   822.8  563.03  827.74  562.44  831.38     562  833.43  561.82
  834.62  561.78  836.84  561.63   837.3  561.63  838.72  561.55   839.3  561.55
  842.84  561.49  849.31  561.57  851.68  561.58  852.97  561.56  855.52  561.35
  855.78  561.34  862.52  560.26  864.21     560  865.49  559.77  867.38  559.42
  868.26  559.27  872.81  558.67  873.31  558.59  874.79  558.46  876.31  558.36
  877.39   558.3  879.98     558  881.48   557.8   886.1  557.13  894.13     556
  899.89  555.37   910.8     554  919.02  553.58  924.57  553.34  927.29  553.32
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BR U #Mann= 3
       0    .055 1251.69    .035 1465.07    .055
BR U Banks=1251.69,1465.07
BR D #Sta/Elev= 57
  352.22     568  352.22  559.12  367.03  553.73  368.79   553.2  368.82  553.19
  372.29  551.86  411.54  534.96  416.78  532.72  417.51   532.5  420.35  531.73
  426.55  530.08  427.35  529.88  428.32  529.64  429.49  529.34  430.96  528.97
  432.84   528.5  435.33  527.87  438.79     527  443.93  525.71  452.37  523.58
  462.17  521.12  466.05     520  475.03  517.45  477.78  517.41  481.94  517.35
  490.73  517.67  491.17  517.89  491.32  517.98  499.59  518.42  505.71  518.68
  508.45  518.57  512.31  518.41  513.78   519.4  516.69  521.36  518.47  522.56
  519.68  523.36  520.55  523.94  521.21  524.38  526.02  527.48  544.18  531.86
     546  532.29  547.39  532.61  548.13  532.79  548.31  532.83  550.47  533.36
  552.01  534.42  552.85  534.89  555.34  536.22  570.67  544.48  578.84  547.85
  580.41  548.43   592.3  548.58  592.94  548.61  596.55  550.18  610.64  556.67
  617.22  559.12  617.22     568
BR D #Mann= 3
  352.22    .055  367.03    .035  580.41    .055
BR D Banks=367.03,580.41
BC Design=,, 0 ,, 0 ,,,,,,
BC Use User HTab Curves=0
BC User HTab FreeFlow(D)= 0

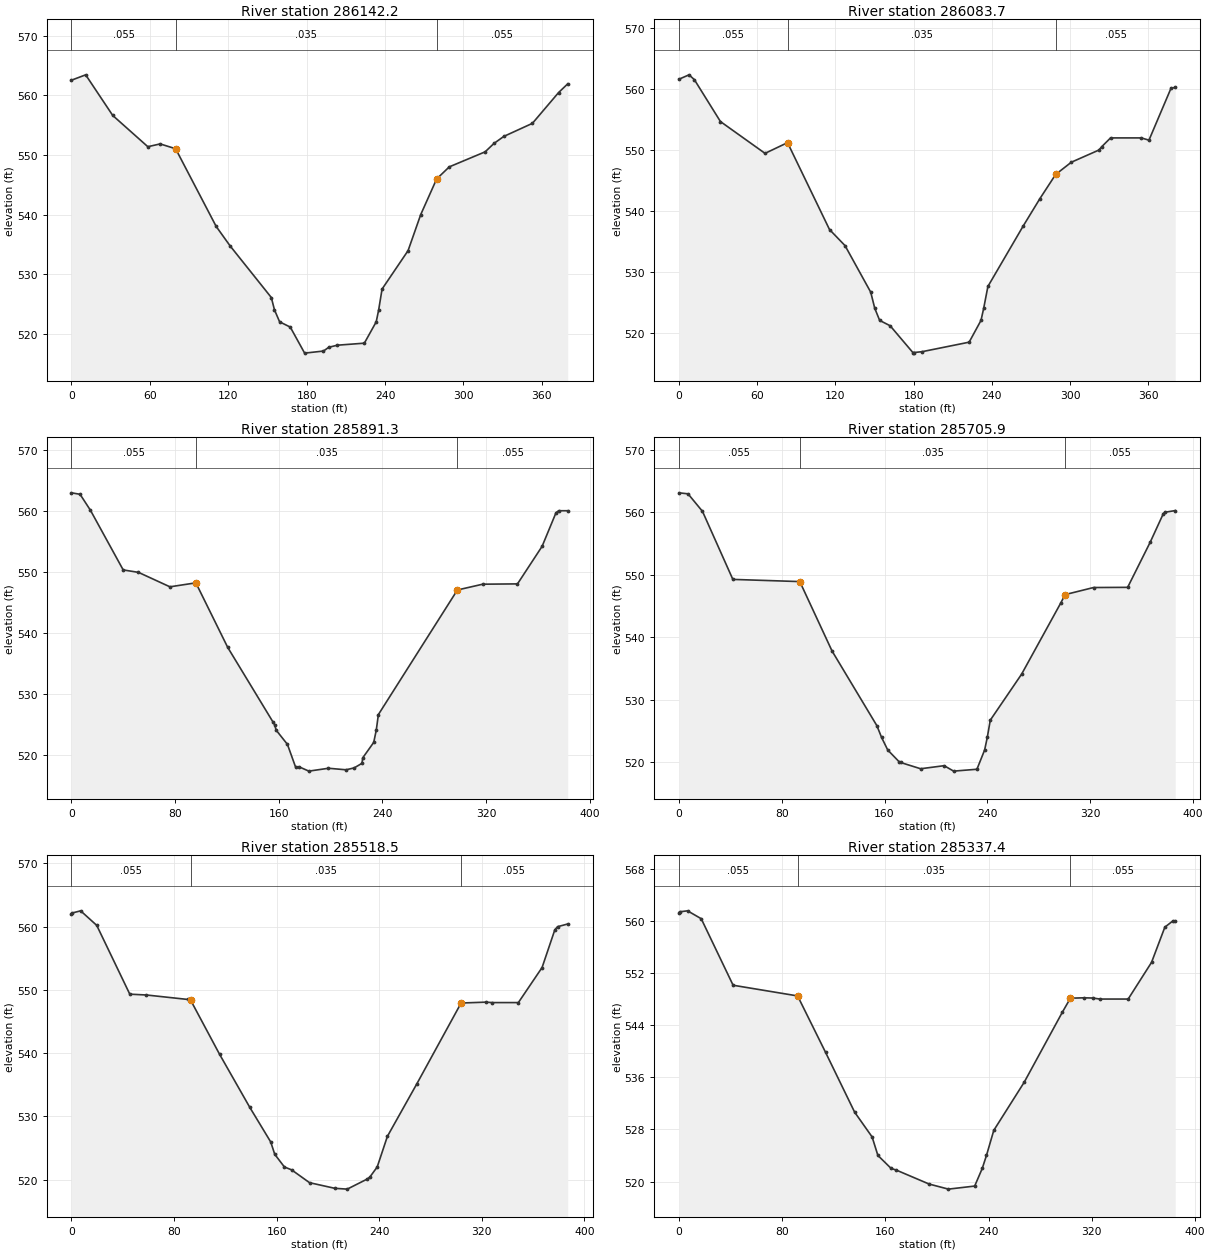
Type RM Length L Ch R = 1 ,286142.2,57.51,58.51,59.34
BEGIN DESCRIPTION:
Downstream of White Settlement Road.
Effective flow limit set at Sump 6W Levee in LOB.
Effective flow limit set at White Settlement Levee in ROB.
END DESCRIPTION:
XS GIS Cut Line= 2
 2305415.6669644  6961193.717467 2305035.8728663 6961200.1241573
#Sta/Elev= 30
       0  562.54   10.86  563.44   31.59  556.62   58.45  551.38   67.88  551.85
   79.71  551.04  110.77     538  121.45  534.73  152.96  526.08  155.39     524
  159.32     522  167.46  521.12  178.46  516.75   192.9   517.1  196.93  517.73
   203.5  518.08  224.17  518.42  233.26     522  235.13     524  237.74   527.5
  257.65  533.95  267.34     540  279.51  545.97  289.18     548  316.62  550.52
  323.45  551.94  330.94  553.11  352.81   555.3  372.87  560.47  379.85  561.93
#Mann= 3 ,-1,0
       0    .055       0   79.71    .035       0  279.51    .055       0
Bank Sta=79.71,279.51
XS Rating Curve= 0 ,0
Exp/Cntr=0.5,0.3

Type RM Length L Ch R = 1 ,286083.7,195.57,192.35,190.16
BEGIN DESCRIPTION:
Effective flow limit set at Sump 6W Levee in LOB.
Effective flow limit set at White Settlement Levee in ROB.
END DESCRIPTION:
XS GIS Cut Line= 2
 2305413.9656005 6961136.5255053 2305033.4524026 6961140.3688713
#Sta/Elev= 30
       0  561.65    7.71  562.37   11.82  561.57   31.79  554.69   65.98  549.46
   83.24  551.22  115.42  536.94  127.34  534.29  147.03  526.64  150.11     524
  153.88     522  161.92  521.12  179.72  516.62  179.85  516.71  186.47  516.86
  222.49  518.42  231.59     522  233.66     524  236.88  527.58  263.89   537.5
   276.7     542  288.83  545.99  300.83     548  321.96     550  324.14  550.55
  330.93     552   354.5     552  360.38  551.63  377.22  560.13  380.53  560.32
#Mann= 3 ,-1,0
       0    .055       0   83.24    .035       0  288.83    .055       0
Bank Sta=83.24,288.83
XS Rating Curve= 0 ,0
Exp/Cntr=0.3,0.1

Type RM Length L Ch R = 1 ,285891.3,185.55,185.37,185.59
BEGIN DESCRIPTION:
Effective flow limit set at Sump 6W Levee in LOB.
Effective flow limit set at White Settlement Levee in ROB.
END DESCRIPTION:
XS GIS Cut Line= 2
 2305408.1258154 6960940.2263032 2305025.2447867  6960952.304509
#Sta/Elev= 30
       0  562.94    6.62   562.7   14.66  560.07   39.92  550.29   51.72  549.89
   75.99  547.52   96.02  548.17   120.6  537.58  155.66   525.3  156.84  524.87
     158     524   166.7  521.67  172.98  517.95  175.56     518  183.23  517.28
  198.39  517.75  211.94   517.5  218.21  517.81  224.24  518.56  224.82  519.46
  233.32     522  235.27     524  236.91  526.56   297.9     547  317.45  547.95
  344.29     548  363.28  554.16     374  559.67  376.06     560  383.07     560
#Mann= 3 ,-1,0
       0    .055       0   96.02    .035       0   297.9    .055       0
Bank Sta=96.02,297.9
XS Rating Curve= 0 ,0
Exp/Cntr=0.3,0.1

Type RM Length L Ch R = 1 ,285705.9,147.36,187.45,228.11
BEGIN DESCRIPTION:
Effective flow limit set at Sump 6W Levee in LOB.
Effective flow limit set at White Settlement Levee in ROB.
END DESCRIPTION:
XS GIS Cut Line= 3
 2305403.2588309 6960754.8727929 2305395.6264171 6960754.9330744
 2305017.1778277 6960767.4644932
#Sta/Elev= 27
       0  563.11    7.04  562.95   18.29  560.15   41.94  549.27   94.05  548.92
  119.13  537.83  154.06  525.88  157.72     524  162.49     522  171.59  520.07
  172.53     520  188.12     519  206.41  519.49  213.79  518.62  231.93  518.92
  237.92     522  239.98     524  242.33  526.77  266.73  534.13  297.11  545.47
  300.61  546.84  322.67  547.97  349.25     548  366.81  555.22  376.95  559.75
   378.1     560  386.29  560.27
#Mann= 3 ,-1,0
       0    .055       0   94.05    .035       0  300.61    .055       0
Bank Sta=94.05,300.61
XS Rating Curve= 0 ,0
Exp/Cntr=0.3,0.1

Type RM Length L Ch R = 1 ,285518.5,166.19,181.09,197.41
BEGIN DESCRIPTION:
Effective flow limit set at Sump 6W Levee in LOB.
Effective flow limit set at White Settlement Levee in ROB.
END DESCRIPTION:
XS GIS Cut Line= 2
  2305413.428123 6960622.8788975 2305038.3259986 6960527.5138473
#Sta/Elev= 30
       0  561.98     .79  562.18    7.15  562.51    19.7  560.21   45.48  549.33
   58.45   549.2   90.53   548.5   92.96  548.37  115.51  539.82  139.04  531.44
  155.39  525.96  158.55     524  166.08     522  171.67  521.55  185.66  519.52
  205.35  518.63  215.06   518.5  230.72   520.1   232.7  520.41  238.44     522
   246.4  526.85   269.4  535.17  303.87  547.93  323.34  548.07  327.94     548
  348.54     548  367.02  553.54  376.98  559.51   379.1     560  387.04  560.43
#Mann= 3 ,-1,0
       0    .055       0   92.96    .035       0  303.87    .055       0
Bank Sta=92.96,303.87
XS Rating Curve= 0 ,0
Exp/Cntr=0.3,0.1

Type RM Length L Ch R = 1 ,285337.4,196.53,219.11,242.71
BEGIN DESCRIPTION:
Effective flow limit set at Sump 6W Levee in LOB.
Effective flow limit set at White Settlement Levee in ROB.
END DESCRIPTION:
XS GIS Cut Line= 2
 2305455.2715112 6960468.5733336 2305094.9699822 6960333.9967979
#Sta/Elev= 30
       0  561.25     .51  561.39    6.64  561.54   17.24  560.33   41.95  550.12
   91.94  548.48  113.61  539.82  136.14  530.64  149.68  526.84  154.16     524
  164.46     522  168.21  521.77  193.86  519.61  208.82  518.83  229.17   519.3
  235.03     522  238.31     524  243.98  527.85  267.54  535.23  297.17     546
  302.97     548  303.04  548.13  313.61  548.19   320.6  548.16  326.25     548
  348.13     548  366.25  553.63  376.55  559.03  382.84     560  384.61     560
#Mann= 3 ,-1,0
       0    .055       0   91.94    .035       0  303.04    .055       0
Bank Sta=91.94,303.04
XS Rating Curve= 0 ,0
Exp/Cntr=0.3,0.1

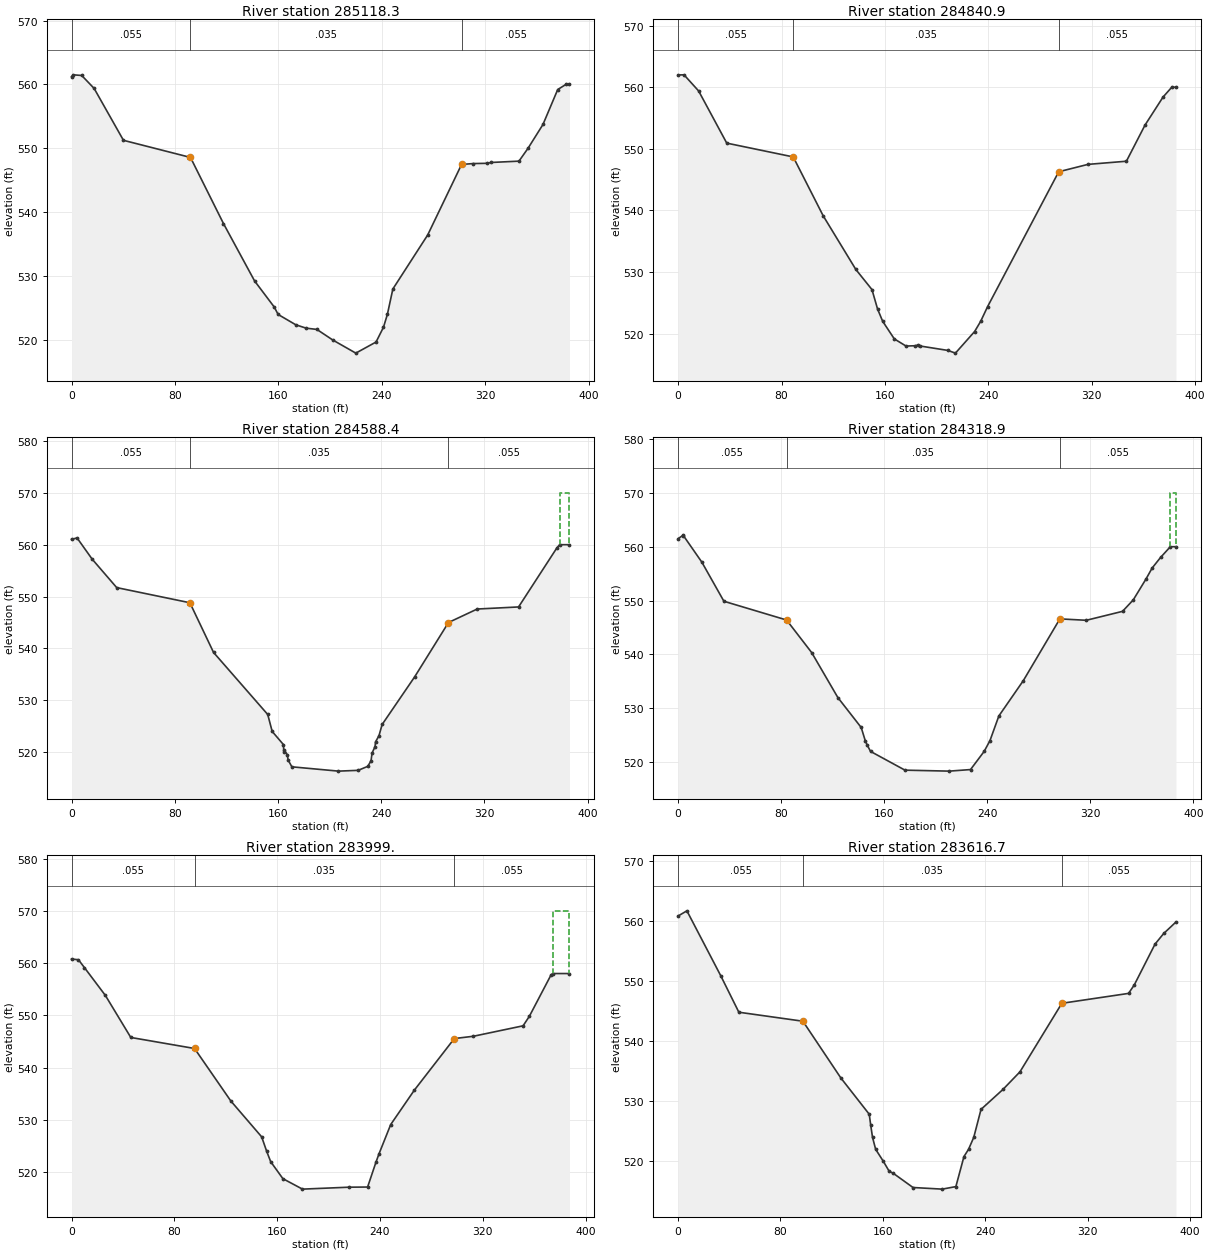
Type RM Length L Ch R = 1 ,285118.3,270.2,277.37,284.36
BEGIN DESCRIPTION:
Effective flow limit set at Sump 6W Levee in LOB.
Effective flow limit set at White Settlement Levee in ROB.
END DESCRIPTION:
XS GIS Cut Line= 3
 2305544.5801518 6960303.6826002 2305542.4985608 6960302.5144358
 2305209.6689251 6960113.5773532
#Sta/Elev= 30
       0  561.23    1.26  561.51    7.86  561.41   17.46  559.38   40.14  551.26
   91.99  548.58   117.5  538.23  141.56  529.25  156.82  525.15  159.79     524
  173.49  522.38  181.43  521.86  189.76  521.66  202.08     520  219.87  517.95
  235.52  519.69  241.26     522  244.26     524  248.52  527.99  275.45  536.44
  301.67  547.48  310.54  547.62  321.57  547.66   324.3  547.79  346.06     548
  353.03     550  364.63  553.74  376.04  559.21  382.33     560   385.1     560
#Mann= 3 ,-1,0
       0    .055       0   91.99    .035       0  301.67    .055       0
Bank Sta=91.99,301.67
XS Rating Curve= 0 ,0
Exp/Cntr=0.3,0.1

Type RM Length L Ch R = 1 ,284840.9,250.48,252.49,254.65
BEGIN DESCRIPTION:
Effective flow limit set at Sump 6W Levee in LOB.
Effective flow limit set at White Settlement Levee in ROB.
END DESCRIPTION:
XS GIS Cut Line= 2
 2305688.8433388 6960078.4510077 2305363.5097382 6959872.1706178
#Sta/Elev= 27
       0  562.01    4.59  562.03   15.88  559.41   37.64  550.94   89.07   548.7
  112.27  539.13  137.53  530.42  149.99  527.16  154.33     524   158.3     522
  167.28  519.15  176.33  517.99  183.61  518.04  185.65  518.16  187.13     518
   208.7  517.28  214.57  516.84  229.43  520.35  234.09     522  239.48   524.4
  294.48  546.29  317.15  547.49  346.85     548  361.26  553.87   375.2  558.42
  381.89     560  385.22  560.03
#Mann= 3 ,-1,0
       0    .055       0   89.07    .035       0  294.48    .055       0
Bank Sta=89.07,294.48
XS Rating Curve= 0 ,0
Exp/Cntr=0.3,0.1

Type RM Length L Ch R = 1 ,284588.4,269.89,269.49,269.04
BEGIN DESCRIPTION:
Effective flow limit set at Sump 6W Levee in LOB.
Effective flow limit set at White Settlement Levee in ROB.
END DESCRIPTION:
XS GIS Cut Line= 2
 2305825.6482153 6959869.5698282 2305502.8236208 6959658.2754447
#Sta/Elev= 30
       0  561.02    4.25  561.31   15.95  557.22   34.98  551.73    91.7  548.81
  110.04  539.23  152.02  527.27  155.48     524  164.14  521.48  164.56     520
  164.61  520.47  167.13  519.53  167.84  518.49  170.72  517.18  206.83  516.35
  222.05   516.5  229.55  517.27  232.09  518.36  232.87  519.84  235.17  521.06
  235.58     522  238.21  523.16  240.68  525.34  265.85  534.51  292.09     545
  314.37   547.6  346.41     548  376.16  559.41  378.26     560  385.83     560
#Mann= 3 ,-1,0
       0    .055       0    91.7    .035       0  292.09    .055       0
#XS Ineff= 2 , 0
       0                  378.26       0     570
Permanent Ineff=
       F       T
Bank Sta=91.7,292.09
XS Rating Curve= 0 ,0
Exp/Cntr=0.3,0.1

Type RM Length L Ch R = 1 ,284318.9,322.89,319.89,316.86
BEGIN DESCRIPTION:
Upstream of Sump 6W outfall (left bank).
Upstream of Sump 5W outfall (right bank).
Effective flow limit set at Sump 6W Levee in LOB.
Effective flow limit set at White Settlement Levee in ROB.
END DESCRIPTION:
XS GIS Cut Line= 2
 2305973.5737942 6959643.7091044 2305649.5895914 6959432.9387161
#Sta/Elev= 28
       0  561.49    3.88  562.13     4.1  562.06   18.43  557.13   35.56  549.87
   84.21  546.39  103.68  540.35  124.01     532  142.14  526.44  145.28     524
  146.82  523.16   149.4     522  176.13  518.52  210.56  518.34  227.01  518.63
  237.58     522   242.1     524     249  528.58     268  535.14  296.37   546.6
  316.88  546.34  345.01     548  353.35  550.13  363.22     554  368.03  556.05
  374.52     558  382.14     560  386.51     560
#Mann= 3 ,-1,0
       0    .055       0   84.21    .035       0  296.37    .055       0
#XS Ineff= 2 , 0
       0                  382.14       0     570
Permanent Ineff=
       F       T
Bank Sta=84.21,296.37
XS Rating Curve= 0 ,0
Exp/Cntr=0.3,0.1

Type RM Length L Ch R = 1 ,283999. ,384.43,382.31,380.1
BEGIN DESCRIPTION:
Downstream of Sump 6W outfall (left bank).
Downstream of Sump 5W outfall (right bank).
Effective flow limit set at Sump 6W Levee in LOB.
Effective flow limit set at White Settlement Levee in ROB.
END DESCRIPTION:
XS GIS Cut Line= 2
  2306150.970667 6959372.9098947 2305822.0181031 6959168.2011014
#Sta/Elev= 25
       0  560.78    5.38  560.64    9.98  559.15   26.32  553.81   46.11  545.77
   95.71  543.66  123.96  533.61  147.95  526.75  151.82     524  154.97     522
  164.46  518.75  179.71  516.75  215.91  517.12  230.38  517.15  237.02     522
  239.33  523.55  248.37  529.11   266.7  535.67  297.86  545.56   312.7     546
  351.38     548  356.24  549.81   373.2  557.77  374.95     558  387.45     558
#Mann= 3 ,-1,0
       0    .055       0   95.71    .035       0  297.86    .055       0
#XS Ineff= 2 , 0
       0                  374.95       0     570
Permanent Ineff=
       F       T
Bank Sta=95.71,297.86
XS Rating Curve= 0 ,0
Exp/Cntr=0.3,0.1

Type RM Length L Ch R = 1 ,283616.7,375.47,375.76,376.5
BEGIN DESCRIPTION:
Effective flow limit set at Sump 6W Levee in LOB.
Effective flow limit set at White Settlement Levee in ROB.
END DESCRIPTION:
XS GIS Cut Line= 2
 2306362.4578217 6959050.8802381 2306029.0793004 6958850.3943897
#Sta/Elev= 28
       0  560.91    6.87  561.77   33.28  550.96   47.47  544.86   97.51  543.36
  127.12  533.91  149.34  527.85  150.51     526  151.91     524  154.35     522
  160.35     520  164.89  518.35  168.12     518  183.55  515.63  206.37  515.36
  217.03  515.78  223.35  520.79  226.94     522  231.02     524  236.69  528.66
   253.9     532  267.11  534.92  299.85  546.35  351.96     548  356.45  549.42
  372.65  556.22  379.46     558  389.02  559.91
#Mann= 3 ,-1,0
       0    .055       0   97.51    .035       0  299.85    .055       0
Bank Sta=97.51,299.85
XS Rating Curve= 0 ,0
Exp/Cntr=0.3,0.1

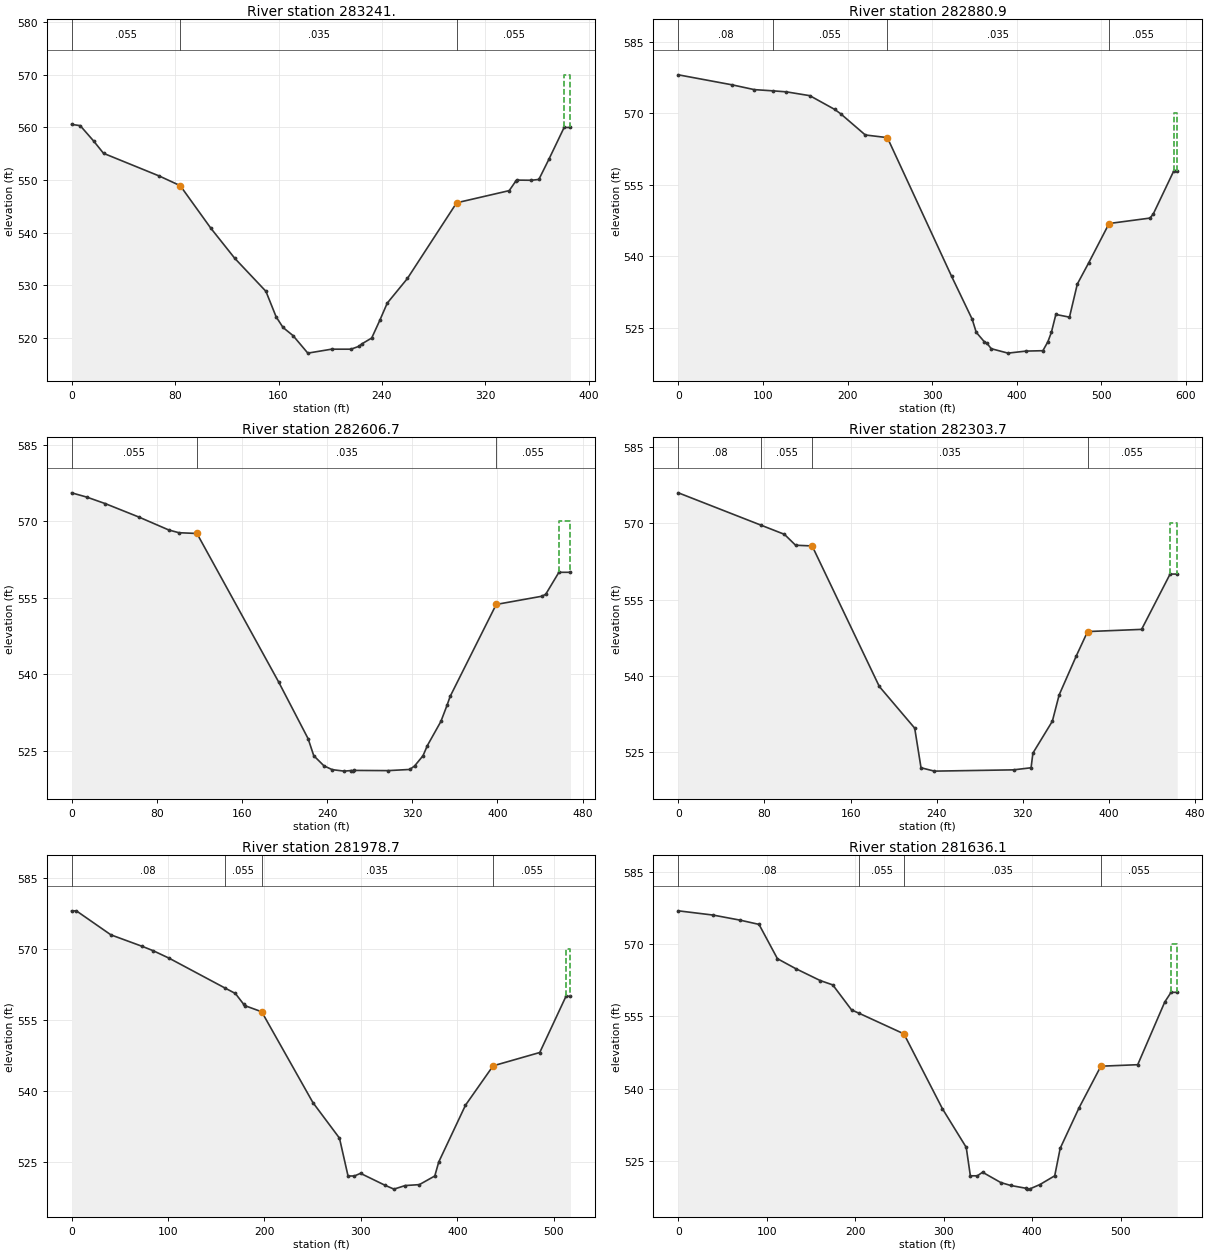
Type RM Length L Ch R = 1 ,283241. ,296.05,360.03,424.37
BEGIN DESCRIPTION:
Effective flow limit set at Sump 6W Levee in LOB.
Effective flow limit set at White Settlement Levee in ROB.
END DESCRIPTION:
XS GIS Cut Line= 2
 2306564.5685478 6958734.7641302 2306234.6390349 6958534.9105244
#Sta/Elev= 30
       0  560.58    6.64  560.35   17.16  557.39   24.67  555.09   67.87  550.77
   84.01  548.94  107.66  540.86   126.1  535.16  150.26  528.87   158.2     524
   163.5     522  171.22  520.46  182.66  517.13  201.04  517.88  216.05  517.88
  222.24  518.43  224.25  518.86  232.05     520   238.3  523.35  244.05  526.62
  259.66  531.31  297.73  545.69  338.38     548  343.45   549.8  344.32     550
   355.5  549.97   361.3  550.12  369.15     554  380.85     560  385.74     560
#Mann= 3 ,-1,0
       0    .055       0   84.01    .035       0  297.73    .055       0
#XS Ineff= 2 , 0
       0                  380.85       0     570
Permanent Ineff=
       F       T
Bank Sta=84.01,297.73
XS Rating Curve= 0 ,0
Exp/Cntr=0.3,0.1

Type RM Length L Ch R = 1 ,282880.9,199.74,274.29,346.94
BEGIN DESCRIPTION:
Effective flow limit set at White Settlement Levee in ROB.
END DESCRIPTION:
XS GIS Cut Line= 2
 2306851.0607782 6958693.2397802 2306522.5198136 6958203.5215514
#Sta/Elev= 30
       0  578.11   63.73     576   89.78     575  112.22  574.74   127.8  574.53
  155.41  573.73  184.84  570.84  191.93  569.92     221  565.47  247.11  564.91
  323.01  535.77  347.37  526.74  352.14     524  361.74     522  364.71  521.71
  369.91  520.55  389.62  519.62  411.17  520.05  430.93  520.13  436.82     522
     441     524  446.27  527.75  462.37  527.18  471.65  534.14  485.26  538.65
  509.18  546.86  557.39     548  561.31  548.82  585.91     558  589.71     558
#Mann= 4 ,-1,0
       0     .08       0  112.22    .055       0  247.11    .035       0
  509.18    .055       0
#XS Ineff= 2 , 0
       0                  585.91       0     570
Permanent Ineff=
       F       T
Bank Sta=247.11,509.18
XS Rating Curve= 0 ,0
Exp/Cntr=0.3,0.1

Type RM Length L Ch R = 1 ,282606.7,274.46,302.98,329.07
BEGIN DESCRIPTION:
Effective flow limit set at White Settlement Levee in ROB.
END DESCRIPTION:
XS GIS Cut Line= 2
 2306919.4247788 6958542.6715388 2306855.2633699 6958078.4167278
#Sta/Elev= 29
       0   575.6   14.29  574.76   31.78  573.47   62.91  570.87   91.38   568.3
  100.83  567.77  117.75  567.62  194.41  538.51  222.22  527.33   227.5     524
  237.13     522  244.86  521.26  256.07  520.97  262.96  521.09  264.22  521.04
  265.15  521.11  297.37  521.07  317.76   521.3  322.31     522  330.16     524
  334.27     526  346.96  530.73  352.75  533.91   355.6  535.62  398.92  553.69
  441.79   555.3  445.44  555.69  457.83     560  468.67     560
#Mann= 3 ,-1,0
       0    .055       0  117.75    .035       0  398.92    .055       0
#XS Ineff= 2 , 0
       0                  457.82       0     570
Permanent Ineff=
       F       T
Bank Sta=117.75,398.92
XS Rating Curve= 0 ,0
Exp/Cntr=0.3,0.1

Type RM Length L Ch R = 1 ,282303.7,289.1,325.04,362.61
BEGIN DESCRIPTION:
Effective flow limit set at White Settlement Levee in ROB.
END DESCRIPTION:
XS GIS Cut Line= 2
 2307173.8283321 6958546.6056511 2307189.3897706  6958083.490225
#Sta/Elev= 19
       0  575.94   76.83  569.59   98.51   567.8   108.9  565.66  124.29  565.52
  186.67  537.95  219.55  529.77  225.42     522  237.78  521.34  311.34  521.59
  327.66     522  329.34  524.87  347.41  531.13  353.71  536.28  369.77     544
  380.16  548.72  430.32  549.15  456.79     560  463.38     560
#Mann= 4 ,-1,0
       0     .08       0   76.83    .055       0  124.29    .035       0
  380.16    .055       0
#XS Ineff= 2 , 0
       0                  456.79       0     570
Permanent Ineff=
       F       T
Bank Sta=124.29,380.16
XS Rating Curve= 0 ,0
Exp/Cntr=0.3,0.1

Type RM Length L Ch R = 1 ,281978.7,302.35,342.54,387.21
BEGIN DESCRIPTION:
Effective flow limit set at White Settlement Levee in ROB.
END DESCRIPTION:
XS GIS Cut Line= 2
 2307404.6274707  6958626.598404 2307559.8065327 6958133.0780339
#Sta/Elev= 27
       0  578.07    5.04  578.05   40.75  572.99   73.34  570.55   84.68  569.63
  101.26  568.04  158.77  561.78  169.84  560.59  178.57  558.28  179.99     558
  197.16  556.72  250.23  537.53   277.8     530  286.68     522  293.29     522
  299.61  522.56     325  520.04  334.28  519.22  346.02  519.98  360.63  520.17
  376.65     522   380.7  524.94  408.48  536.97  437.13  545.29   485.5  548.11
  512.71     560  517.34     560
#Mann= 4 ,-1,0
       0     .08       0  158.77    .055       0  197.16    .035       0
  437.13    .055       0
#XS Ineff= 2 , 0
       0                  512.71       0     570
Permanent Ineff=
       F       T
Bank Sta=197.16,437.13
XS Rating Curve= 0 ,0
Exp/Cntr=0.3,0.1

Type RM Length L Ch R = 1 ,281636.1,164.08,171.49,178.5
BEGIN DESCRIPTION:
Effective flow limit set at White Settlement Levee in ROB.
END DESCRIPTION:
XS GIS Cut Line= 2
 2307587.0099465  6958767.245739 2307919.8193587   6958312.00839
#Sta/Elev= 30
       0  576.88   39.31     576   69.83  574.95   91.18  574.07     112  566.97
  132.45  564.93  160.49  562.43  174.55  561.54  195.84  556.35  204.36  555.66
  254.98   551.4  298.59  535.87  325.44  527.89   330.1     522  338.08     522
  343.89  522.74  364.53   520.6  375.68     520   392.9  519.42  394.18  519.24
  397.13  519.27  408.75  520.19  425.47     522  431.65  527.69  452.76     536
  477.63   544.7  519.29  545.01  549.88     558  556.98     560  563.92     560
#Mann= 4 ,-1,0
       0     .08       0  204.36    .055       0  254.98    .035       0
  477.63    .055       0
#XS Ineff= 2 , 0
       0                  556.98       0     570
Permanent Ineff=
       F       T
Bank Sta=254.98,477.63
XS Rating Curve= 0 ,0
Exp/Cntr=0.3,0.1

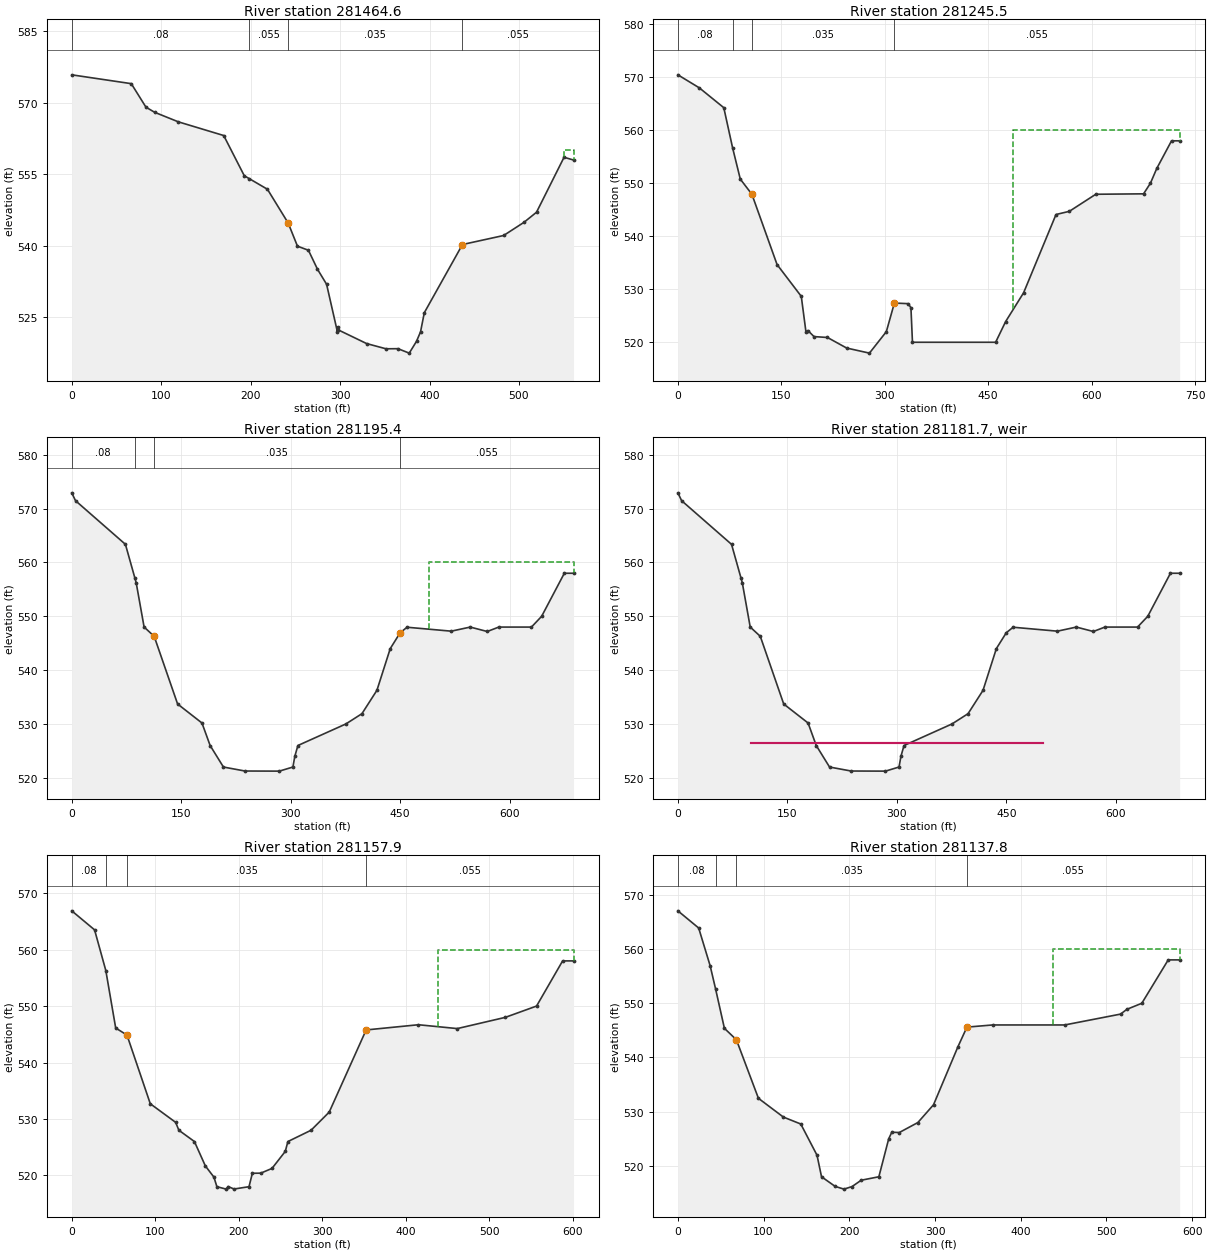
Type RM Length L Ch R = 1 ,281464.6,183.64,219.15,243.27
BEGIN DESCRIPTION:
Effective flow limit set at White Settlement Levee in ROB.
END DESCRIPTION:
XS GIS Cut Line= 2
 2307720.6320901 6958839.1961639 2308077.8895985 6958406.6984172
#Sta/Elev= 30
       0  575.85   66.55     574   82.97  569.07   92.67     568  119.13     566
  169.89  563.13  192.87  554.71  198.58  554.08  218.78  551.87     242  544.78
  252.35  539.94  264.59  539.09  274.73  535.11  284.91  531.96     297     522
  297.23  523.03  297.64  522.43   329.7  519.53  351.31  518.44  364.69  518.46
  377.32  517.53  385.44     520  389.96     522  394.16     526  436.82  540.29
  482.84  542.18  505.44  544.92   519.6  547.05  550.39  558.57  560.97     558
#Mann= 4 ,-1,0
       0     .08       0  198.58    .055       0     242    .035       0
  436.82    .055       0
#XS Ineff= 2 , 0
       0                  550.39       0     560
Permanent Ineff=
       F       T
Bank Sta=242,436.82
XS Rating Curve= 0 ,0
Exp/Cntr=0.3,0.1

Type RM Length L Ch R = 1 ,281245.5,50.31,50.03,50.01
BEGIN DESCRIPTION:
Ineffective flow in ROB.
White Settlement Levee in ROB.
END DESCRIPTION:
XS GIS Cut Line= 2
 2307912.1709994 6958861.5224814 2308491.4697189 6958421.3166125
#Sta/Elev= 30
       0  570.45   31.14  567.99   66.59  564.25   79.38  556.67   90.52  550.78
  107.34  547.92  143.83  534.66  178.96  528.66  185.69     522  188.58  522.21
   197.4  521.07  216.96   520.9  244.73  518.91  277.79  517.95  302.31     522
  313.96   527.4  334.05  527.28  337.97   526.5  340.19     520  460.78     520
  475.32  523.91  501.36  529.34  548.34   544.1  567.66   544.7  605.99  547.92
   675.3     548  685.24     550  694.48   552.8  715.85     558  727.58     558
#Mann= 4 ,-1,0
       0     .08       0   79.38    .055       0  107.34    .035       0
  313.96    .055       0
#XS Ineff= 1 ,-1
  486.62  727.58     560
Permanent Ineff=
       F
Bank Sta=107.34,313.96
XS Rating Curve= 0 ,0
Exp/Cntr=0.3,0.1

Type RM Length L Ch R = 1 ,281195.4,34.83,37.49,39.21
BEGIN DESCRIPTION:
Upstream of Tucker Dam.
Dowsntream of Sump 7W and Sump 8W outfall channel.
Ineffective flow in ROB.
White Settlement Levee in ROB.
END DESCRIPTION:
XS GIS Cut Line= 2
 2307942.4224525 6958901.3326335 2308489.7185742 6958485.4453527
#Sta/Elev= 30
       0  572.94    5.15  571.48   73.53  563.37   86.34  557.18   88.25  556.25
   99.11  548.01  112.92  546.28     145  533.71  178.39  530.18  189.56     526
  207.79     522  237.29  521.26  284.38  521.24  302.97     522  305.61     524
  309.82     526  375.48     530  397.53  531.91  418.05  536.25  436.31     544
  449.92  546.95   459.3  547.97  519.91  547.24  545.88     548  569.21  547.18
  585.01     548  629.75     548  643.72     550  674.81     558  687.38     558
#Mann= 4 ,-1,0
       0     .08       0   86.34    .055       0  112.92    .035       0
  449.92    .055       0
#XS Ineff= 2 ,-1
  489.22  687.38     560  112.92  449.92   526.5
Permanent Ineff=
       F       T
Bank Sta=112.92,449.92
XS Rating Curve= 0 ,0
Exp/Cntr=0.5,0.3

Type RM Length L Ch R = 5 ,281181.7,,,
BEGIN DESCRIPTION:
Tucker Dam
Constructed by TRWD.  Top of dam road surface elevation suveyed by TRWD May 2007.
END DESCRIPTION:
Node Name=Tucker Dam
IW Pilot Flow=0
#Inline Weir SE= 2
     100   526.5     500   526.5
IW Dist,WD,Coef,Skew,MaxSub,Min_El,Is_Ogee,SpillHt,DesHd
8,11.4,3,0,0.95,, 0 ,,,2,2,
Inline Weir Flap Gates= 0
IW Outlet Rating Curve= 0 ,False,,

Type RM Length L Ch R = 1 ,281157.9,20.17,20.1,20.05
BEGIN DESCRIPTION:
Downstream of Tucker Dam.
Ineffective flow in ROB.
White Settlement Levee in ROB.
END DESCRIPTION:
XS GIS Cut Line= 2
 2308002.8986532 6958897.6706305 2308488.1401067 6958543.2515374
#Sta/Elev= 30
       0  566.87   27.32   563.5    40.8  556.29   52.63  546.11   66.14  544.86
   94.07  532.69  124.42   529.4  128.28     528   146.9     526     160  521.68
  170.28  519.69  173.82     518  185.01  517.57  187.22  518.03  194.35  517.59
  212.27     518   216.3  520.38  226.38   520.4   239.8  521.24  255.69  524.25
  258.86     526  286.57     528  308.31  531.21  352.56  545.77  415.19  546.69
  461.69  546.01  519.27     548  556.64     550  587.86     558  600.89     558
#Mann= 4 ,-1,0
       0     .08       0    40.8    .055       0   66.14    .035       0
  352.56    .055       0
#XS Ineff= 1 ,-1
  438.68  600.89     560
Permanent Ineff=
       F
Bank Sta=66.14,352.56
XS Rating Curve= 0 ,0
Exp/Cntr=0.5,0.3

Type RM Length L Ch R = 1 ,281137.8,43.86,66.1,79.84
BEGIN DESCRIPTION:
Ineffective flow in ROB.
White Settlement Levee in ROB.
END DESCRIPTION:
XS GIS Cut Line= 2
 2308014.6950269 6958913.8212719 2308487.4500458 6958568.5223138
#Sta/Elev= 30
       0  567.05   24.28  563.88   37.66  556.92   43.97  552.67    54.3  545.38
   68.29  543.27      94  532.47  123.09  529.01  143.41  527.73  162.36  521.97
  167.62     518  183.55  516.22   193.8  515.72  203.23  516.19  213.88  517.36
  234.52     518     246     525  249.58  526.21  258.36  526.16  280.01     528
   298.3  531.28  326.83     542  337.26   545.6  367.26     546  451.35     546
  516.47     548  523.86  548.88  541.32     550  572.12     558  585.43     558
#Mann= 4 ,-1,0
       0     .08       0   43.97    .055       0   68.29    .035       0
  337.26    .055       0
#XS Ineff= 1 ,-1
  438.16  585.43     560
Permanent Ineff=
       F
Bank Sta=68.29,337.26
XS Rating Curve= 0 ,0
Exp/Cntr=0.3,0.1

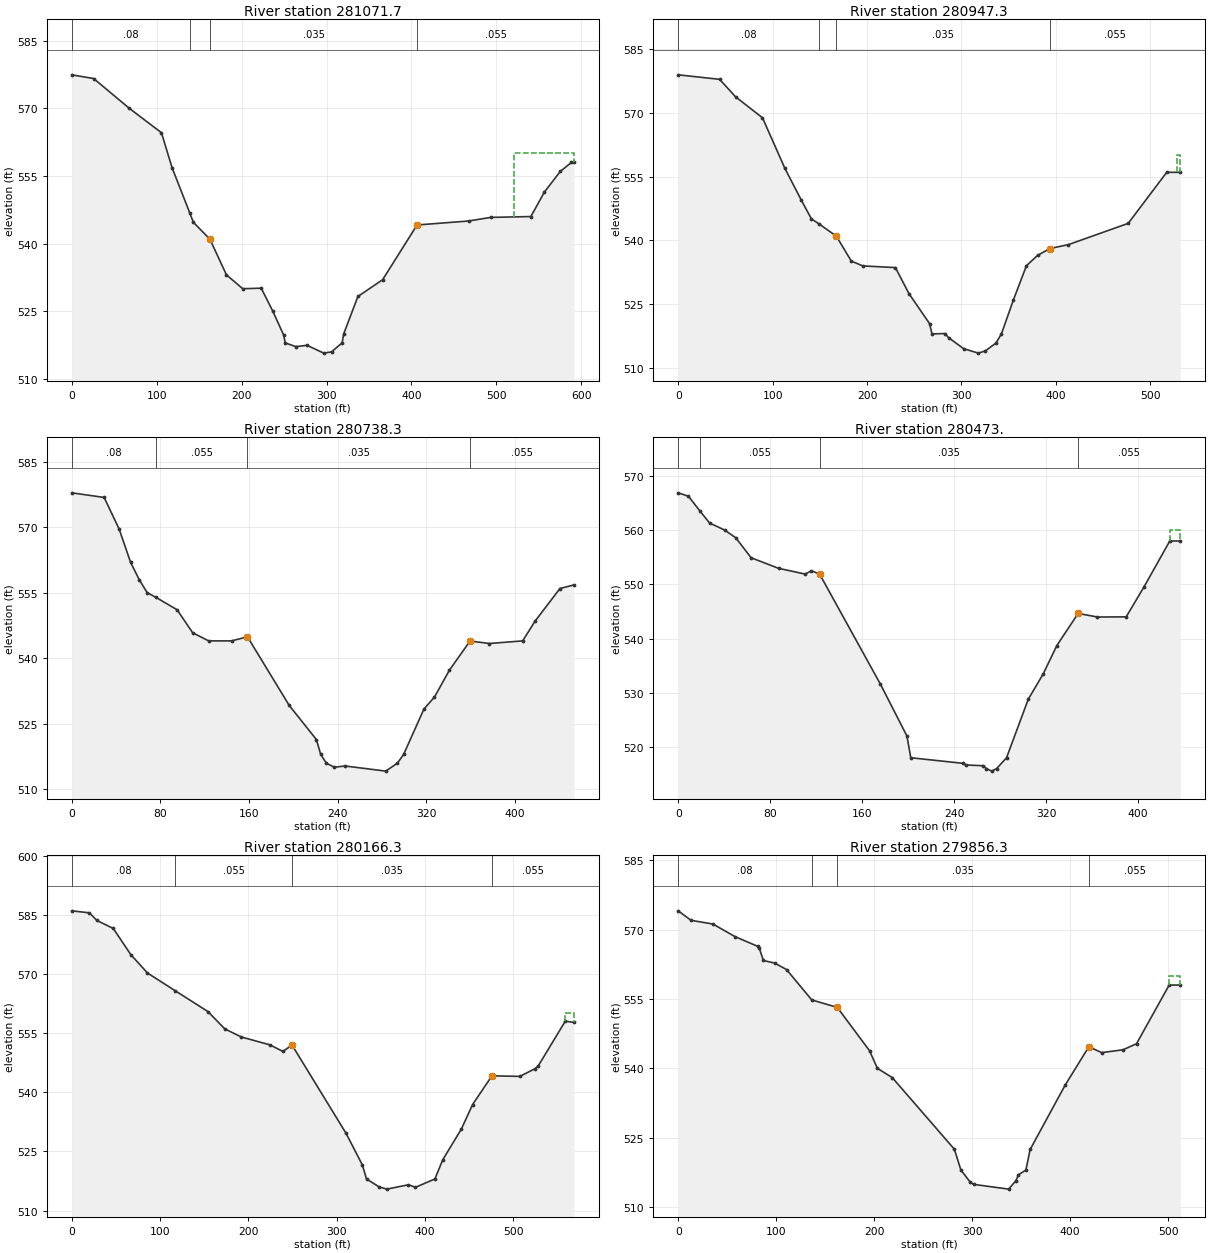
Type RM Length L Ch R = 1 ,281071.7,107.46,124.41,141.87
BEGIN DESCRIPTION:
Ineffective flow in ROB.
White Settlement Levee in ROB.
END DESCRIPTION:
XS GIS Cut Line= 2
 2307956.8233752 6958980.9902732 2308483.5235821 6958712.3127124
#Sta/Elev= 30
       0  577.42   25.74   576.6   67.73     570  105.64  564.58  118.09  556.85
  138.77  546.89   143.2  544.72  162.71  540.97  182.13  533.08  201.33     530
  223.11  530.12  236.85  524.98  249.75  519.64   251.3     518  263.86  517.16
  277.12  517.45  296.72  515.72  305.95     516  318.36     518  320.24  519.99
  336.97  528.28  366.09     532  406.63  544.13  467.28  545.01  493.24  545.81
  540.68     546  556.63  551.44   575.3     556  588.49     558  591.27     558
#Mann= 4 ,-1,0
       0     .08       0  138.77    .055       0  162.71    .035       0
  406.63    .055       0
#XS Ineff= 1 ,-1
  520.44  591.27     560
Permanent Ineff=
       F
Bank Sta=162.71,406.63
XS Rating Curve= 0 ,0
Exp/Cntr=0.3,0.1

Type RM Length L Ch R = 1 ,280947.3,202.53,209.05,215.9
BEGIN DESCRIPTION:
Ineffective flow in ROB.
White Settlement Levee in ROB.
END DESCRIPTION:
XS GIS Cut Line= 2
 2307972.8526758 6959050.4508783 2308481.5887408 6958895.6736928
#Sta/Elev= 30
       0  578.92   43.83  577.86   60.69  573.76   89.24  568.82  113.02   556.9
  130.52  549.38  141.08  545.05  149.26  543.85  167.51  540.98  183.26  535.14
  195.37     534  230.06   533.6  244.33  527.49  266.13  520.45   268.8     518
  282.52   518.1  286.35  517.12  302.28  514.54  317.79  513.49  325.14     514
  336.42  515.83  342.27     518  354.99     526  368.79  534.04  380.57  536.47
  393.67  538.08  413.25     539  476.58     544  517.35     556  531.76     556
#Mann= 4 ,-1,0
       0     .08       0  149.26    .055       0  167.51    .035       0
  393.67    .055       0
#XS Ineff= 1 ,-1
  527.77  531.76     560
Permanent Ineff=
       F
Bank Sta=167.51,393.67
XS Rating Curve= 0 ,0
Exp/Cntr=0.3,0.1

Type RM Length L Ch R = 1 ,280738.3,265.16,265.27,265.68
BEGIN DESCRIPTION:
Effective flow limit set at White Settlement Levee in ROB.
END DESCRIPTION:
XS GIS Cut Line= 2
 2308074.3721415 6959222.7666054 2308514.2928077 6959114.3990333
#Sta/Elev= 30
       0  577.92   29.22  576.86   42.79   569.6   53.07     562   60.93     558
   68.04  555.05   75.89  553.98   95.05  551.13  109.07  545.87  123.52     544
  144.21     544  158.53  544.94  196.26   529.2  220.72   521.4  224.64     518
  229.69     516  236.92  515.05  246.57  515.34  283.38  514.16  293.89     516
  299.48     518  317.78  528.38   327.3  531.13  340.78  537.29   359.4  543.97
  376.87   543.4  406.88     544   418.1  548.53  440.54     556  453.07  556.81
#Mann= 4 ,-1,0
       0     .08       0   75.89    .055       0  158.53    .035       0
   359.4    .055       0
Bank Sta=158.53,359.4
XS Rating Curve= 0 ,0
Exp/Cntr=0.3,0.1

Type RM Length L Ch R = 1 ,280473. ,310.52,306.71,304.05
BEGIN DESCRIPTION:
Effective flow limit set at White Settlement Levee in ROB.
END DESCRIPTION:
XS GIS Cut Line= 2
 2308161.1978331 6959473.8934386  2308585.569506 6959370.3881841
#Sta/Elev= 30
       0  566.89    8.87  566.26   19.13  563.47   27.21  561.33   40.53     560
   50.03   558.6   63.41  554.91   87.26  552.96  110.49  551.89  115.85  552.52
  123.03  551.88  175.93  531.57  198.98  522.01   202.3     518  247.67  516.97
  250.68  516.66  265.42  516.53  268.07     516  272.85  515.53  276.98     516
  285.64     518  304.55  528.81  317.61   533.5  329.34  538.69  347.94  544.64
  364.66  543.97  389.72     544  405.22  549.53  427.66     558  436.81     558
#Mann= 4 ,-1,0
       0     .08       0   19.13    .055       0  123.03    .035       0
  347.94    .055       0
#XS Ineff= 2 , 0
       0                  427.66       0     560
Permanent Ineff=
       F       T
Bank Sta=123.03,347.94
XS Rating Curve= 0 ,0
Exp/Cntr=0.3,0.1

Type RM Length L Ch R = 1 ,280166.3,316.19,310.01,306.93
BEGIN DESCRIPTION:
Effective flow limit set at White Settlement Levee in ROB.
END DESCRIPTION:
XS GIS Cut Line= 2
 2308120.4006204 6959808.1059186 2308669.6157675 6959660.9947231
#Sta/Elev= 30
       0  585.98   19.98  585.47   28.48  583.53   47.01  581.51   66.84  574.88
   85.71  570.22   116.9  565.75   154.2  560.44  173.23  556.06  191.89     554
  224.37     552  239.13  550.33  249.39  551.96  310.63  529.57  329.09  521.54
  333.77     518  347.95     516  356.86  515.42  381.33  516.53  389.24  515.88
  411.26     518  420.07  522.85  441.31   530.7  453.86  536.84   475.8  544.15
  507.44     544  524.96     546  528.43  546.73  558.89     558  568.58   557.7
#Mann= 4 ,-1,0
       0     .08       0   116.9    .055       0  249.39    .035       0
   475.8    .055       0
#XS Ineff= 2 , 0
       0                  558.89       0     560
Permanent Ineff=
       F       T
Bank Sta=249.39,475.8
XS Rating Curve= 0 ,0
Exp/Cntr=0.3,0.1

Type RM Length L Ch R = 1 ,279856.3,273.38,261.3,253.19
BEGIN DESCRIPTION:
Effective flow limit set at White Settlement Levee in ROB.
END DESCRIPTION:
XS GIS Cut Line= 2
 2308263.6514673 6960098.4885734 2308755.3941169 6959953.9852975
#Sta/Elev= 30
       0  574.05   13.04     572   35.27   571.2   58.07  568.47   81.12  566.37
   82.56   566.1   86.92  563.31   98.53  562.75  110.61  561.34  136.33  554.78
  162.34  553.17  195.31  543.79  203.27     540  218.54  537.98  281.89   522.5
  288.56     518     298   515.4  301.55   514.9  337.29  513.87  344.81  515.71
  347.23  516.95  354.89     518  359.24  522.45  395.03  536.38  419.17  544.66
  432.25  543.39  454.04     544  467.83  545.31  501.17     558  512.54     558
#Mann= 4 ,-1,0
       0     .08       0  136.33    .055       0  162.34    .035       0
  419.17    .055       0
#XS Ineff= 2 , 0
       0                  501.17       0     560
Permanent Ineff=
       F       T
Bank Sta=162.34,419.17
XS Rating Curve= 0 ,0
Exp/Cntr=0.3,0.1