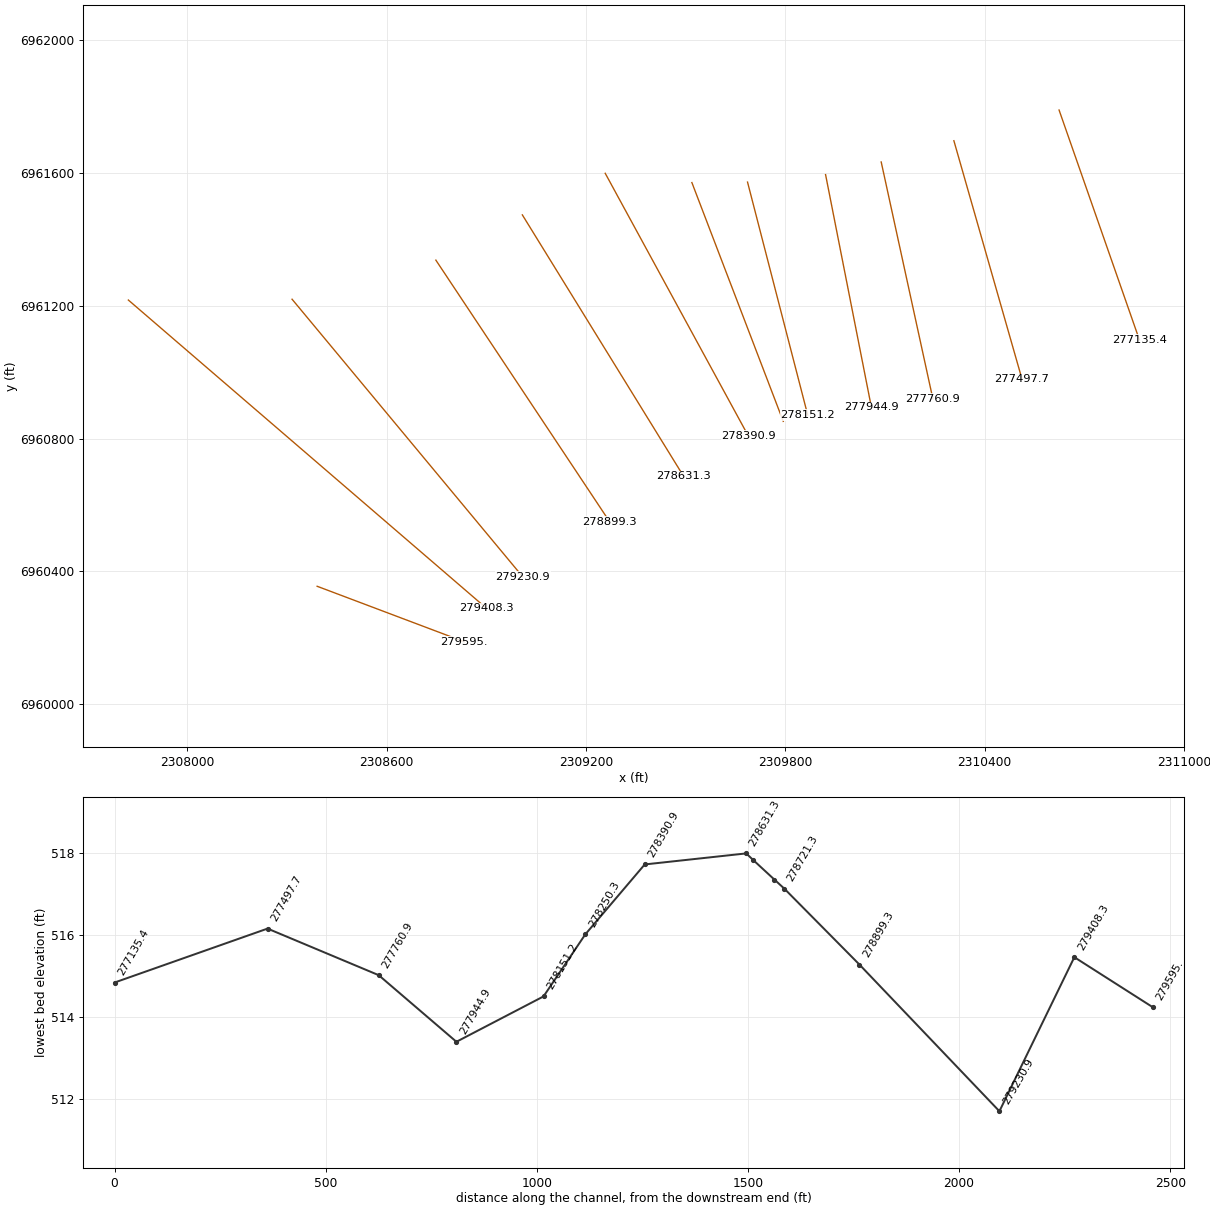
HEC-RAS study CDC_Consolidated_Model.prj: Upper Trinity CDC Consolidated Model

--- CDC_Consolidated_Model.g11 (geometry) --- (continued)

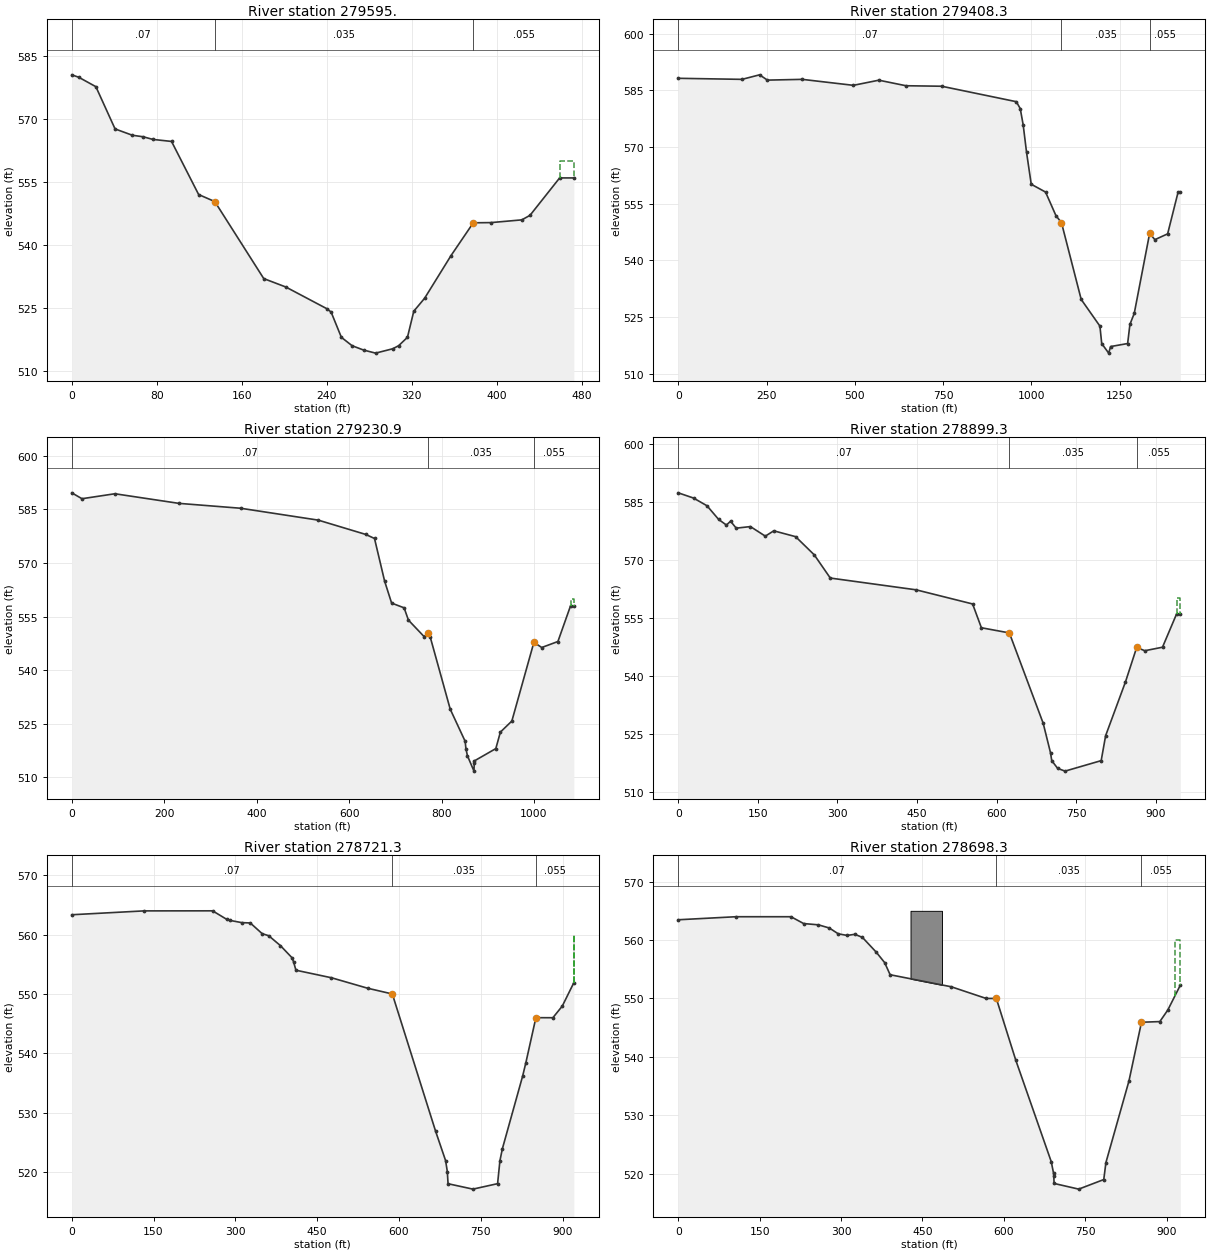
Type RM Length L Ch R = 1 ,279595. ,241.54,186.65,144.65
BEGIN DESCRIPTION:
Effective flow limit set at White Settlement Levee in ROB.
END DESCRIPTION:
XS GIS Cut Line= 2
 2308390.9522222 6960355.5088616 2308833.1243047 6960188.7014363
#Sta/Elev= 30
       0  580.58    6.58     580    22.7  577.75   40.76  567.68   56.98  566.18
   67.17  565.81   76.44  565.18   93.92   564.7  119.41  552.04  134.63  550.36
  180.71     532  201.43     530  240.17  524.81  244.11  524.02  253.77     518
  263.84     516  274.69  514.96  285.98  514.23  302.11  515.27  307.67     516
  315.97     518  321.94  524.23  332.09   527.3  356.99  537.49  377.93   545.3
   394.6  545.35  423.62     546  431.32  547.08  459.22     556  472.59     556
#Mann= 3 ,-1,0
       0     .07       0  134.63    .035       0  377.93    .055       0
#XS Ineff= 2 , 0
       0                  459.22       0     560
Permanent Ineff=
       F       T
Bank Sta=134.63,377.93
XS Rating Curve= 0 ,0
Exp/Cntr=0.3,0.1

Type RM Length L Ch R = 1 ,279408.3,204.55,177.44,155.76
BEGIN DESCRIPTION:
Effective flow limit set at White Settlement Levee in ROB.
END DESCRIPTION:
XS GIS Cut Line= 2
  2307822.636919  6961217.162946 2308900.0188632 6960289.7962092
#Sta/Elev= 30
       0  588.22  180.48  587.94  230.32  589.14  252.47  587.74  351.04  587.94
  495.84  586.36  567.95  587.72  644.88  586.25  745.79  586.12  957.13  582.03
  968.31  580.21  976.69  575.87  986.23  568.58  999.46  560.17 1040.03   558.1
  1069.4  551.86 1085.08     550 1140.89  529.68 1193.93  522.61 1198.98     518
 1218.69  515.46  1224.2   517.2  1272.4     518 1278.85  523.06 1291.12  525.98
 1334.69  547.17  1349.5   545.5 1385.65  547.04 1415.02     558 1421.53     558
#Mann= 3 ,-1,0
       0     .07       0 1085.08    .035       0 1334.69    .055       0
Bank Sta=1085.08,1334.69
XS Rating Curve= 0 ,0
Exp/Cntr=0.3,0.1

Type RM Length L Ch R = 1 ,279230.9,346.67,331.54,316.04
BEGIN DESCRIPTION:
Effective flow limit set at White Settlement Levee in ROB.
END DESCRIPTION:
XS GIS Cut Line= 2
 2308315.4489492 6961219.6497841 2309009.7432223  6960384.142956
#Sta/Elev= 30
       0  589.65    22.1     588   93.29  589.39  231.64   586.7  365.28  585.33
  533.35     582  635.96     578  655.02  576.86   676.9  564.91  692.05  558.76
  719.12  557.43  728.38     554  762.38  549.37  770.08   550.3  775.68  549.21
  818.87  529.04   851.2  520.03   852.8     518  856.08     516  870.26  511.69
   870.8     514  871.16  514.56  917.49     518  927.39  522.62   952.2  525.72
   999.9  547.77 1016.85  546.32 1051.87     548 1079.22     558 1086.33     558
#Mann= 3 ,-1,0
       0     .07       0  770.08    .035       0   999.9    .055       0
#XS Ineff= 2 , 0
       0                 1079.22       0     560
Permanent Ineff=
       F       T
Bank Sta=770.08,999.9
XS Rating Curve= 0 ,0
Exp/Cntr=0.3,0.1

Type RM Length L Ch R = 1 ,278899.3,180.53,178.08,175.88
BEGIN DESCRIPTION:
Effective flow limit set at White Settlement Levee in ROB.
END DESCRIPTION:
XS GIS Cut Line= 2
 2308748.3409239 6961337.2925376 2309271.8808253 6960549.2199786
#Sta/Elev= 30
       0  587.35   28.77     586   54.21     584   76.21  580.45   90.83     579
   98.58     580  109.27   578.2  136.04  578.61   164.1  576.13  180.01  577.51
  221.16     576  256.37  571.28  286.53  565.28  448.35  562.23   554.7  558.57
  571.27  552.41  623.98  551.07  687.73  527.67   701.5  520.05  703.84     518
  714.92     516  728.88  515.28  797.02     518  805.38  524.46  842.81   538.4
  863.88   547.3  879.26  546.46  912.56  547.37  939.16     556  946.12     556
#Mann= 3 ,-1,0
       0     .07       0  623.98    .035       0  863.88    .055       0
#XS Ineff= 2 , 0
       0                  939.16       0     560
Permanent Ineff=
       F       T
Bank Sta=623.98,863.88
XS Rating Curve= 0 ,0
Exp/Cntr=0.3,0.1

Type RM Length L Ch R = 1 ,278721.3,24.85,23.31,22.05
#Sta/Elev= 30
       0  563.34  132.59  563.99  258.26     564  284.06  562.57  289.53   562.4
  311.96  562.01  327.34  561.96  349.24  560.15  361.19  559.81   382.8  558.13
  404.11  556.08   406.8   555.4  411.11     554  476.28  552.73  542.54  550.97
  587.88     550  667.14  526.92  685.59  521.94  688.77  520.09  690.08  518.05
  735.69  517.14  780.94  518.06  785.21  521.92  789.71  523.94   826.9  536.18
  832.72   538.4  851.19  546.01  882.34     546  899.59  547.96  920.79   551.9
#Mann= 3 ,-1,0
       0     .07       0  587.88    .035       0  851.19    .055       0
#XS Ineff= 2 , 0
       0                  920.39       0     560
Permanent Ineff=
       F       F
Bank Sta=587.88,851.19
XS Rating Curve= 0 ,0
Exp/Cntr=0.3,0.1

Type RM Length L Ch R = 1 ,278698.3,50.51,50.37,50.36
BEGIN DESCRIPTION:
Structure in LOB.
END DESCRIPTION:
#Sta/Elev= 30
       0  563.47  106.35  563.99  207.74  563.99  231.12  562.82  258.36   562.6
  278.38  562.06  294.93  561.06  311.21  560.79  325.51  560.98   339.4  560.45
  364.71  557.94  380.33  556.14  390.45  554.06  503.09     552   567.4     550
  585.16     550  586.16  549.99  622.02  539.42  687.33  522.06  691.63  520.06
  691.99  519.58   692.6  518.33  737.94  517.36  784.12     519  788.07  521.91
  830.51  535.87  853.62  545.93  887.41  546.04  902.19  548.03  925.15  552.27
#Mann= 3 ,-1,0
       0     .07       0  585.16    .035       0  853.62    .055       0
#XS Ineff= 2 , 0
       0                  914.91       0     560
Permanent Ineff=
       F       F
#Block Obstruct= 1 ,-1
     428     486     565
Bank Sta=585.16,853.62
XS Rating Curve= 0 ,0
Exp/Cntr=0.3,0.1

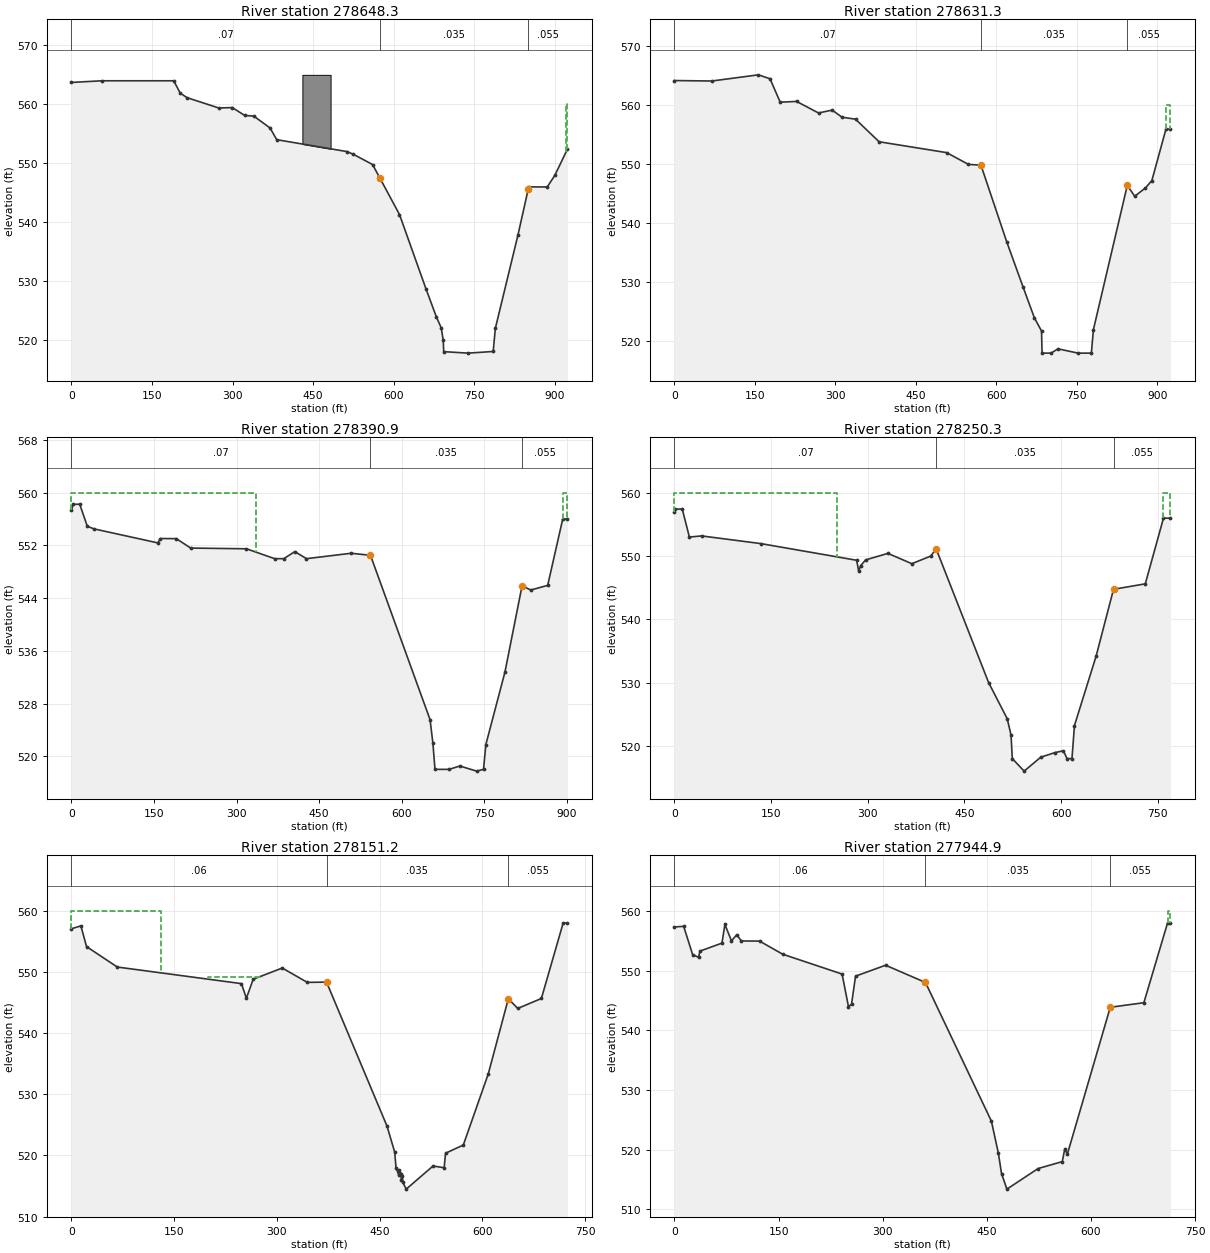
Type RM Length L Ch R = 1 ,278648.3,18.12,16.3,14.9
BEGIN DESCRIPTION:
Structure in LOB.
END DESCRIPTION:
#Sta/Elev= 30
       0  563.71   56.71  563.99   190.4  563.99  202.29  561.92  214.77  561.14
  274.22  559.38  299.41  559.45  322.38  558.12  339.48     558  369.65  555.99
  382.07  554.01  512.36     552  524.17  551.56  560.42   549.8   573.9  547.53
  610.56  541.33  659.78  528.75  679.28  523.96  688.17  522.14     692  520.04
  692.86  518.09  738.28  517.84  784.96  518.12  788.95  522.03     831  537.83
   850.2  545.64   851.6  546.01  885.56     546  899.78  547.98  923.09   552.4
#Mann= 3 ,-1,0
       0     .07       0   573.9    .035       0   850.2    .055       0
#XS Ineff= 2 , 0
       0                  920.58       0     560
Permanent Ineff=
       F       F
#Block Obstruct= 1 ,-1
   429.8   482.3     565
Bank Sta=573.9,850.2
XS Rating Curve= 0 ,0
Exp/Cntr=0.3,0.1

Type RM Length L Ch R = 1 ,278631.3,250.68,240.39,232.69
BEGIN DESCRIPTION:
Effective flow limit set at White Settlement Levee in ROB.
END DESCRIPTION:
XS GIS Cut Line= 2
 2309008.6337837 6961473.5931238 2309493.9108876 6960686.9744505
#Sta/Elev= 30
       0  564.22   69.51  564.14  156.34  565.19  178.04  564.52     197  560.55
   227.5  560.68  268.42  558.72   293.7  559.21  312.35     558  337.35  557.67
  381.31  553.84  507.12     552  547.88     550  571.08  549.88  618.99  536.92
   649.7  529.19  670.64     524  684.02  521.75     685     518  701.93     518
   714.6  518.73  752.05     518  776.87     518  780.75     522  843.87  546.45
  857.69   544.6  877.55     546  889.59  547.25  915.96     556  924.26     556
#Mann= 3 ,-1,0
       0     .07       0  571.08    .035       0  843.87    .055       0
#XS Ineff= 2 , 0
       0                  915.96       0     560
Permanent Ineff=
       F       T
Bank Sta=571.08,843.87
XS Rating Curve= 0 ,0
Exp/Cntr=0.3,0.1

Type RM Length L Ch R = 1 ,278390.9,166.53,140.62,122.21
BEGIN DESCRIPTION:
Effective flow limit set at Brookside Levee in LOB.
Effective flow limit set at White Settlement Levee in ROB.
END DESCRIPTION:
XS GIS Cut Line= 2
  2309258.144036 6961598.7313939 2309689.1438203 6960807.6631691
#Sta/Elev= 30
       0  557.39    3.33  558.26   15.01  558.27   28.74  554.93   40.59  554.53
  156.64   552.4  161.72  553.06  190.53  553.04  216.56  551.61  317.87   551.5
  369.08     550  385.62     550  405.69  551.07  426.88     550  508.11  550.82
  543.16  550.51  651.37  525.55  656.49  522.01  660.33     518  685.98     518
  705.44  518.51   735.9  517.73  748.47     518  752.71  521.76  787.36  532.76
  818.49  545.88  834.28  545.24  865.02  545.94  892.31     556  900.86     556
#Mann= 3 ,-1,0
       0     .07       0  543.16    .035       0  818.49    .055       0
#XS Ineff= 2 ,-1
       0  335.04     560  892.31  900.86     560
Permanent Ineff=
       F       T
Bank Sta=543.16,818.49
XS Rating Curve= 0 ,0
Exp/Cntr=0.3,0.1

Type RM Length L Ch R = 1 ,278250.3,120.22,99.06,82.87
BEGIN DESCRIPTION:
Effective flow limit set at Brookside Levee in LOB.
Effective flow limit set atWhite Settlement Levee in ROB.
END DESCRIPTION:
XS GIS Cut Line= 2
 2309519.0454148 6961570.8132881 2309794.1082756 6960851.9975438
#Sta/Elev= 30
       0  557.03      .8  557.41   12.02  557.45   23.12  553.01   42.08  553.19
  133.79  551.98  282.76  549.34  285.84  547.59  288.74  548.47   296.6   549.4
  331.24  550.43  368.36   548.8  397.52     550  406.12  551.13  487.53     530
  516.31  524.31  522.24  521.74  524.25     518   542.6  516.02  568.37  518.22
  590.15  518.94  603.56  519.24  609.13     518  616.83     518  620.72  523.23
  654.29  534.18  681.29  544.75  730.62  545.62  758.85     556  769.65     556
#Mann= 3 ,-1,0
       0     .07       0  406.12    .035       0  681.29    .055       0
#XS Ineff= 2 ,-1
       0  252.42     560  758.85  769.65     560
Permanent Ineff=
       F       T
Bank Sta=406.12,681.29
XS Rating Curve= 0 ,0
Exp/Cntr=0.3,0.1

Type RM Length L Ch R = 1 ,278151.2,215.07,206.29,196.39
BEGIN DESCRIPTION:
Effective flow limit set at Brookside Levee in LOB.
Effective flow limit set at White Settlement Levee in ROB.
White Settlement Road in LOB - drainage ditch to the west non-effective up to elevation 549.14.
END DESCRIPTION:
XS GIS Cut Line= 2
 2309686.5618282 6961572.2049477 2309867.7214325 6960871.1959653
#Sta/Elev= 30
       0  557.07   13.77  557.54      22  554.15    66.9  550.81  248.12   548.1
  255.36  545.71  265.35  548.82  307.77  550.65  344.34   548.3  372.37  548.35
  460.69   524.8  471.88  520.55  473.86     518  477.78  516.79  478.49  517.67
  481.46  517.01  481.59     516  483.15  516.57  483.78  515.59  488.71   514.5
  527.87  518.28  544.11     518  546.12  520.37  572.07  521.71  608.51  533.34
  637.81  545.62  651.55  544.04  686.05  545.67  717.82     558  724.04     558
#Mann= 3 ,-1,0
       0     .06       0  372.37    .035       0  637.81    .055       0
#XS Ineff= 2 ,-1
       0   130.2     560     200     280  549.14
Permanent Ineff=
       F       F
Bank Sta=372.37,637.81
XS Rating Curve= 0 ,0
Exp/Cntr=0.3,0.1

Type RM Length L Ch R = 1 ,277944.9,178.66,184.04,185.56
BEGIN DESCRIPTION:
Effective flow limit set at Brookside Levee in LOB.
Effective flow limit set at White Settlement Levee in ROB.
White Settlement Road in LOB - drainage ditch to the west non-effective up to elevation 550.
END DESCRIPTION:
XS GIS Cut Line= 2
 2309921.4986101 6961594.7631869 2310059.5551376 6960893.7612049
#Sta/Elev= 30
       0   557.3   13.24   557.4   26.13  552.67    34.6  552.22   36.81  553.26
   68.36  554.59   72.63  557.72   82.11  554.96   89.65  555.99   96.45  554.95
  122.61  554.93  155.93  552.73  241.45  549.41  250.64  543.95  255.03  544.36
  260.84  549.06   304.1  550.89  361.58     548  456.56  524.77  466.66  519.36
  471.12     516  478.86  513.39  523.87  516.84  558.67     518  562.14  520.07
  566.02  519.26  627.81  543.85  676.18  544.61   710.4     558  714.47     558
#Mann= 3 ,-1,0
       0     .06       0  361.58    .035       0  627.81    .055       0
#XS Ineff= 2 ,-1
     200     300     550   710.4  714.42     560
Permanent Ineff=
       F       T
Bank Sta=361.58,627.81
XS Rating Curve= 0 ,0
Exp/Cntr=0.3,0.1

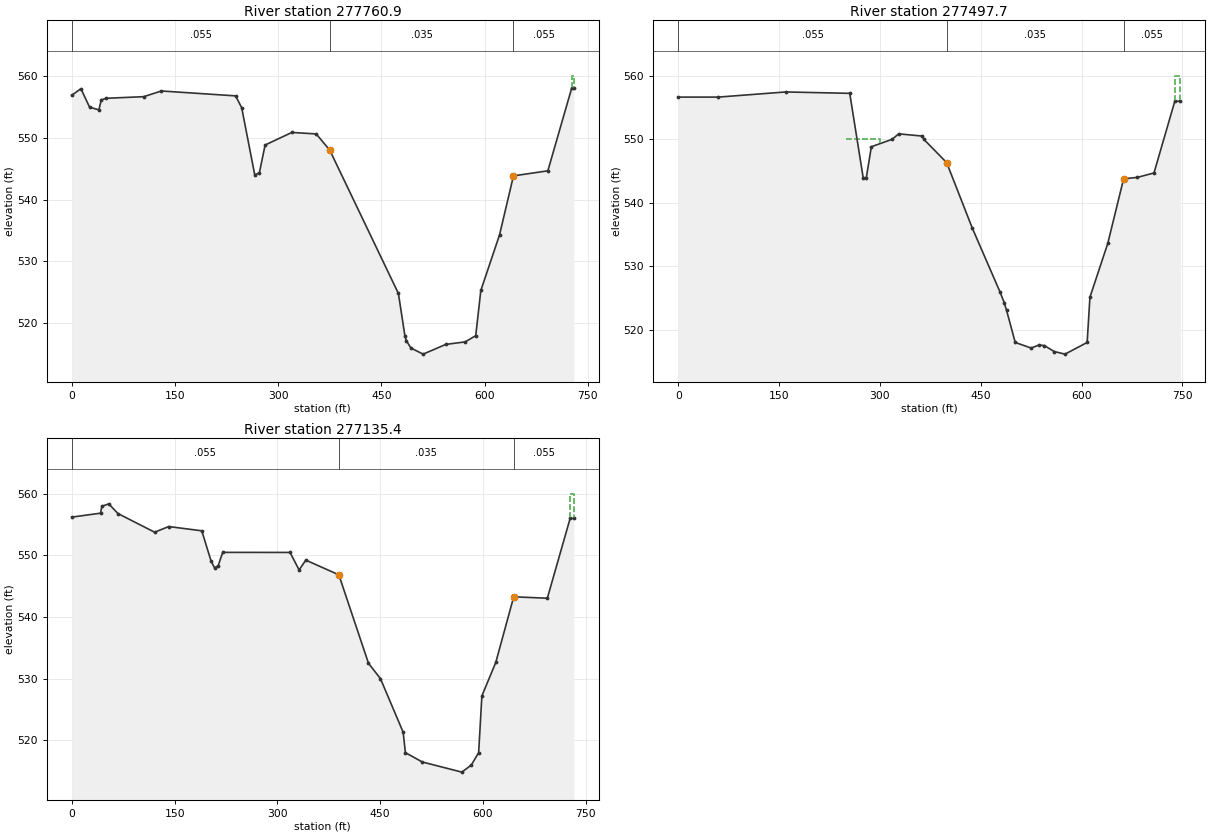
Type RM Length L Ch R = 1 ,277760.9,249.46,263.24,271.07
BEGIN DESCRIPTION:
Effective flow limit set at Brookside Levee in LOB.
Effective flow limit set at White Settlement Levee in ROB.
White Settlement Road in LOB - drainage ditch to the west non-effective up to elevation 550.
END DESCRIPTION:
XS GIS Cut Line= 2
 2310088.9489083 6961632.8330838 2310244.4551757 6960919.9069054
#Sta/Elev= 30
       0  556.86    13.3  557.92   25.89  554.93   39.39   554.5   42.91  556.11
   50.23  556.37  104.47  556.63  130.27  557.55  238.11  556.76  246.98  554.84
     266  543.95   272.7  544.35  280.99  548.82  319.89  550.85  355.22  550.61
  374.88     548  474.72  524.82  484.13     518  486.13  517.21  492.92     516
  510.67  515.02  543.55  516.59   571.8     517  587.08     518  594.51  525.31
  621.64  534.27  641.94  543.83  691.93  544.65  726.53     558  729.69     558
#Mann= 3 ,-1,0
       0    .055       0  374.88    .035       0  641.94    .055       0
#XS Ineff= 2 ,-1
     250     350     550  726.53  729.69     560
Permanent Ineff=
       F       T
Bank Sta=374.88,641.94
XS Rating Curve= 0 ,0
Exp/Cntr=0.3,0.1

Type RM Length L Ch R = 1 ,277497.7,362.7,362.28,369.29
BEGIN DESCRIPTION:
Effective flow limit set at Brookside Levee in LOB.
Effective flow limit set at White Settlement Levee in ROB.
White Settlement Road in LOB - drainage ditch to the west non-effective up to elevation 550.
END DESCRIPTION:
XS GIS Cut Line= 2
  2310307.774718 6961696.7235501 2310512.9850792 6960978.4870266
#Sta/Elev= 30
       0  556.65   59.62  556.65  159.96  557.46  255.17  557.24  275.16  543.95
   279.8  543.95  287.32  548.83  318.25     550  327.99  550.86  363.13  550.51
  365.39     550   399.4  546.32  437.47  536.02  478.54     526  484.93  524.29
  488.47  523.07  501.38     518  525.05  517.12   536.7   517.6  544.81   517.5
  559.39  516.57  575.45  516.16  608.39     518  612.51  525.12  639.06   533.6
  662.63  543.78  683.03     544  707.82   544.7   738.8     556  746.98     556
#Mann= 3 ,-1,0
       0    .055       0   399.4    .035       0  662.63    .055       0
#XS Ineff= 2 ,-1
     250     300     550   738.8  746.98     560
Permanent Ineff=
       F       T
Bank Sta=399.4,662.63
XS Rating Curve= 0 ,0
Exp/Cntr=0.3,0.1

Type RM Length L Ch R = 1 ,277135.4,357.37,382.01,395.6
BEGIN DESCRIPTION:
Effective flow limit set at Brookside Levee in LOB.
Effective flow limit set at White Settlement Levee in ROB.
White Settlement Road in LOB - drainage ditch to the west non-effective up to elevation 550.
END DESCRIPTION:
XS GIS Cut Line= 2
 2310624.4098947 6961789.1712356 2310866.1313902 6961097.6937282
#Sta/Elev= 30
       0  556.22   41.97  556.86   43.93  557.98   53.96  558.37    67.4   556.8
  120.91  553.77  141.43  554.69  189.68     554  203.24  549.09  208.32     548
  213.53  548.31   220.2   550.5  318.48  550.49  331.65  547.65  341.48  549.24
  389.63  546.86  432.87  532.51   450.4     530  483.51  521.31  486.75     518
  511.54  516.48  569.18  514.84  582.98     516  593.61     518  598.35  527.21
  618.65  532.65  644.78  543.29  693.83  543.06  727.06     556  732.51     556
#Mann= 3 ,-1,0
       0    .055       0  389.63    .035       0  644.78    .055       0
#XS Ineff= 2 ,-1
     150     250     550  727.06  732.51     560
Permanent Ineff=
       F       T
Bank Sta=389.63,644.78
XS Rating Curve= 0 ,0
Exp/Cntr=0.3,0.1