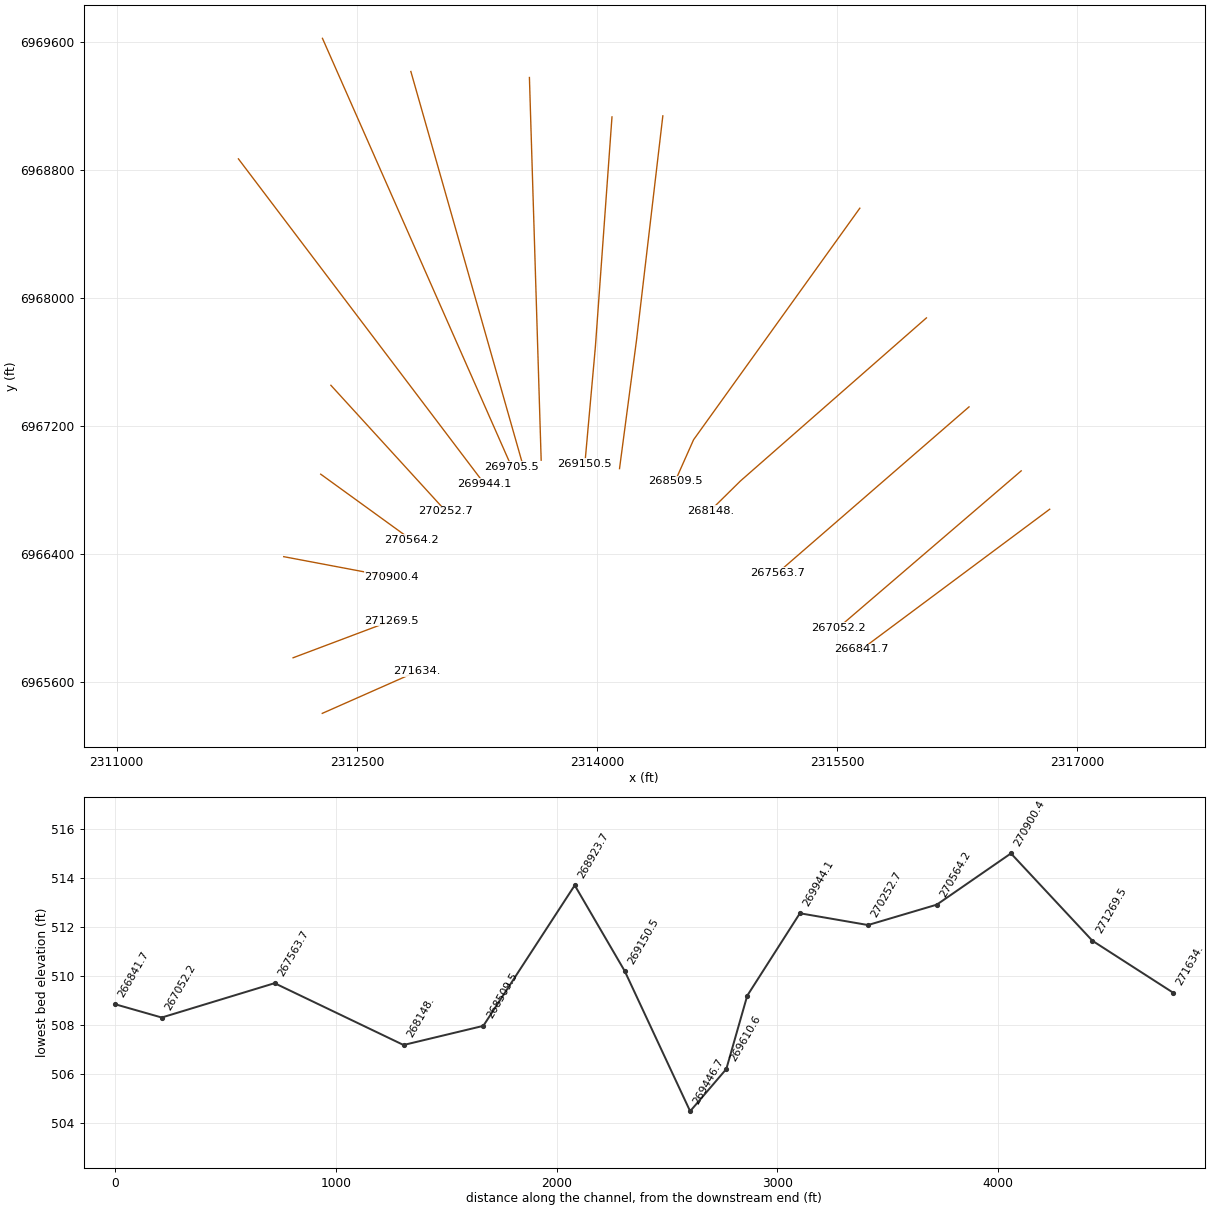
HEC-RAS study CDC_Consolidated_Model.prj: Upper Trinity CDC Consolidated Model

--- CDC_Consolidated_Model.g11 (geometry) --- (continued)

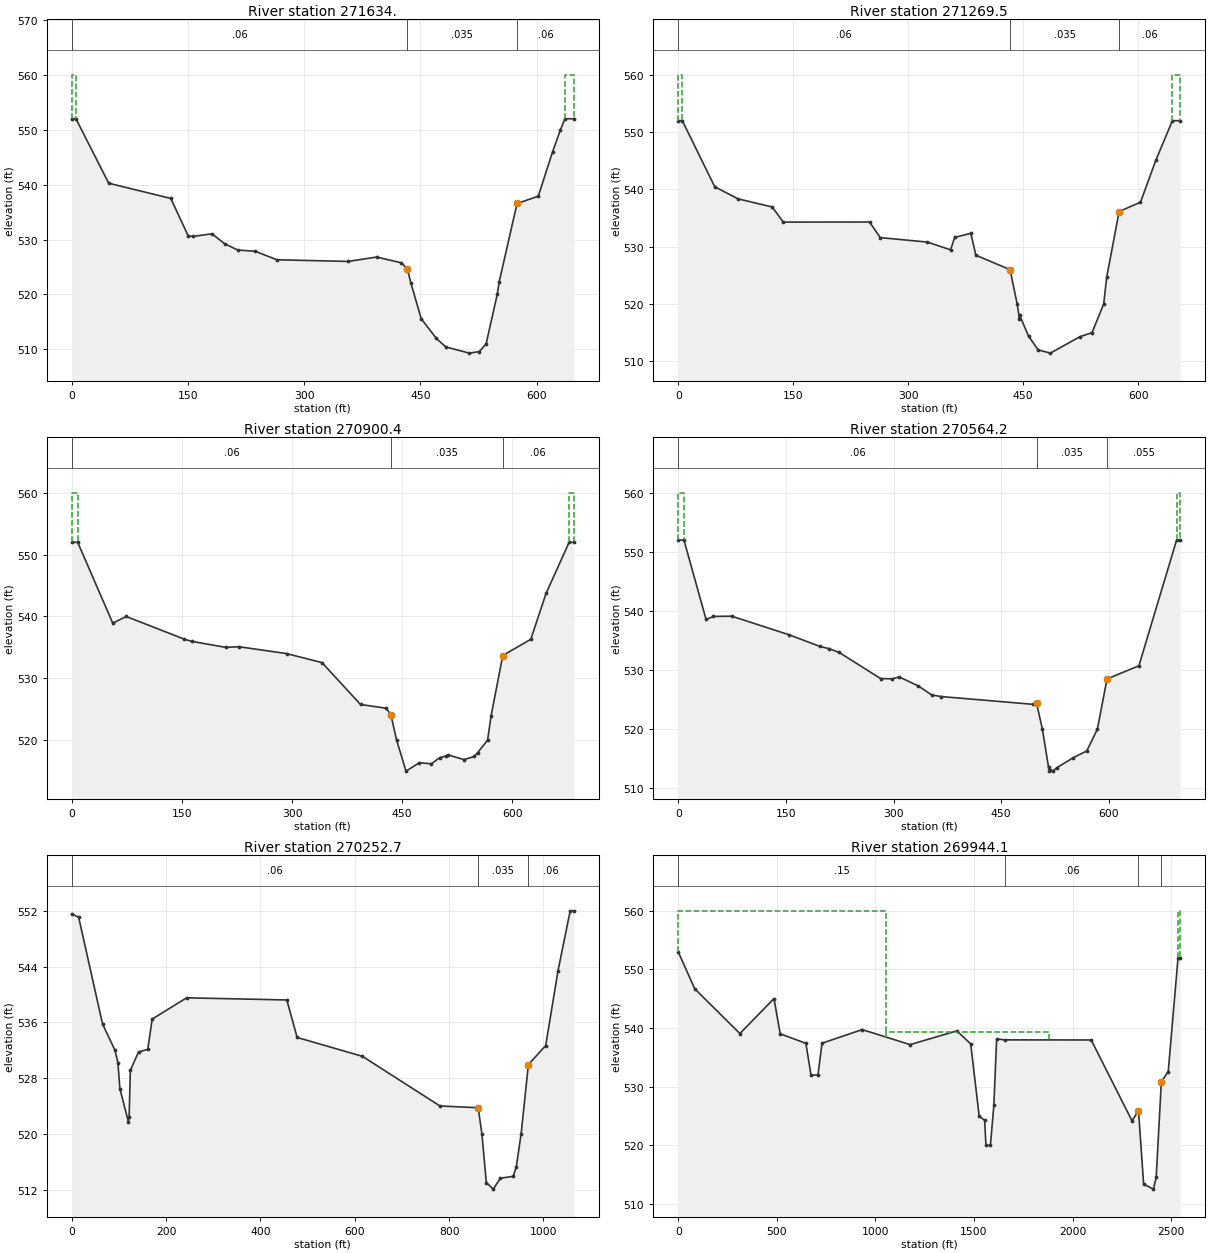
Type RM Length L Ch R = 1 ,271634. ,381.05,364.56,359.59
BEGIN DESCRIPTION:
Effective flow limit set at Brookside Levee in LOB.
Effective flow limit set at Crestwood Levee in ROB.
END DESCRIPTION:
XS GIS Cut Line= 2
   2312283.88736  6965406.855927 2312876.4745819 6965669.0041602
#Sta/Elev= 30
       0     552    5.39     552   47.68  540.26  127.81  537.49  150.19  530.69
  156.74  530.57  180.92  531.06  197.26  529.24  214.19   528.1     237  527.86
  264.71  526.32  356.73  526.02  393.52  526.82  425.53  525.76  433.05  524.68
  437.83  522.01  450.98  515.59  470.57     512  482.66  510.45  513.12  509.32
  526.02   509.6  534.72     511  549.09     520  551.64  522.31  574.67  536.57
  602.07  537.89  620.59     546  630.74     550  636.57     552  647.98     552
#Mann= 3 ,-1,0
       0     .06       0  433.05    .035       0  574.67     .06       0
#XS Ineff= 2 , 0
       0    5.39     560  636.57       0     560
Permanent Ineff=
       T       T
Bank Sta=433.05,574.67
XS Rating Curve= 0 ,0
Exp/Cntr=0.3,0.1

Type RM Length L Ch R = 1 ,271269.5,521.42,369.04,312.01
BEGIN DESCRIPTION:
Effective flow limit set at Brookside Levee in LOB.
Effective flow limit set at Crestwood Levee in ROB.
Rockwood Park in LOB.
END DESCRIPTION:
XS GIS Cut Line= 2
 2312101.6905253 6965754.0570576 2312714.7858973 6965984.8985877
#Sta/Elev= 30
       0     552    5.32     552   47.65  540.46   77.95  538.36  122.49  536.94
  137.12   534.3  249.64  534.31  263.69  531.59  325.17  530.81  355.38  529.45
  360.68  531.63  381.82  532.34   388.3  528.52  432.93     526  432.93  526.01
  442.26     520  445.25  517.46   445.6     518  457.03  514.41  469.61     512
   485.6  511.43  523.83  514.28  539.92  515.01  555.15     520  559.03  524.63
  575.25  536.14  603.15  537.77  623.34  545.14   644.8     552  655.11     552
#Mann= 3 ,-1,0
       0     .06       0  432.93    .035       0  575.25     .06       0
#XS Ineff= 2 , 0
       0    5.29     560   644.8       0     560
Permanent Ineff=
       T       T
Bank Sta=432.93,575.25
XS Rating Curve= 0 ,0
Exp/Cntr=0.3,0.1

Type RM Length L Ch R = 1 ,270900.4,469.47,336.27,297.89
BEGIN DESCRIPTION:
Effective flow limit set at Brookside Levee in LOB.
Effective flow limit set at Crestwood Levee in ROB.
Rockwood Park in LOB.
END DESCRIPTION:
XS GIS Cut Line= 2
 2312043.2985083 6966385.4362578   2312715.19633 6966258.6629983
#Sta/Elev= 30
       0     552    8.05     552   55.84  538.92   74.18     540  153.49  536.32
  163.27  535.98  209.99     535  227.61  535.11  292.55     534  340.82  532.54
  393.23  525.77  428.12  525.16  434.56  524.13  442.39     520  455.18  514.99
  473.54  516.36  489.63  516.17  501.04  517.17  509.81  517.43  511.92  517.63
  534.12  516.86  548.19  517.36  552.74  517.98  566.29     520  571.04  523.92
  586.96  533.69  625.13  536.31  645.87  543.72  677.33     552  683.75     552
#Mann= 3 ,-1,0
       0     .06       0  434.56    .035       0  586.96     .06       0
#XS Ineff= 2 , 0
       0    8.05     560  677.33       0     560
Permanent Ineff=
       T       T
Bank Sta=434.56,586.96
XS Rating Curve= 0 ,0
Exp/Cntr=0.3,0.1

Type RM Length L Ch R = 1 ,270564.2,374.6,311.43,295.86
BEGIN DESCRIPTION:
Effective flow limit set at Brookside Levee in LOB.
Effective flow limit set at Crestwood Levee in ROB.
Rockwood Park in LOB.
END DESCRIPTION:
XS GIS Cut Line= 2
  2312274.094017 6966900.5838098  2312840.779646 6966490.1505126
#Sta/Elev= 30
       0     552    7.98     552   38.79  538.57    49.1  539.08   74.62  539.12
  153.91     536  197.54     534  210.42  533.62  224.24  532.99  281.98  528.57
   298.1  528.52  308.16  528.83  334.51  527.32  353.23  525.79  366.79  525.52
  493.98  524.21  499.34  524.42   507.5     520  516.07  513.57  517.11  512.99
  518.74  513.07   521.9   512.9  528.13  513.51  549.94  515.14  569.32  516.31
  584.13     520  597.55   528.5  642.02  530.73  694.52     552  699.71     552
#Mann= 3 ,-1,0
       0     .06       0  499.34    .035       0  597.55    .055       0
#XS Ineff= 2 , 0
       0    7.93     560  694.52       0     560
Permanent Ineff=
       T       T
Bank Sta=499.34,597.55
XS Rating Curve= 0 ,0
Exp/Cntr=0.3,0.1

Type RM Length L Ch R = 1 ,270252.7,344.56,308.65,302.41
BEGIN DESCRIPTION:
Effective flow limit set at Crestwood Levee in ROB.
Rockwood Park in LOB.
Old West Fork river channel in LOB - Sump 12W outfall.
END DESCRIPTION:
XS GIS Cut Line= 2
 2312337.6313505  6967455.732081  2313055.406364 6966669.6056416
#Sta/Elev= 30
       0  551.56   14.54  551.09   65.25  535.77   91.53     532   97.86   530.2
  102.01  526.49  120.07  521.74   121.6   522.4  124.17  529.11  141.56  531.75
  161.11  532.12  170.51  536.47   243.5  539.52  455.96  539.21  477.84  533.83
  616.38  531.12  780.64     524  861.74  523.75  869.59     520  878.93  513.02
  893.69  512.07  908.72  513.64  935.82   513.9  942.46  515.25  952.74     520
  968.14  529.94 1004.85  532.67 1030.92  543.39 1056.77     552 1064.52     552
#Mann= 3 ,-1,0
       0     .06       0  861.74    .035       0  968.14     .06       0
#XS Ineff= 2 , 0
       0   243.5  539.52               0
Permanent Ineff=
       F       F
Bank Sta=861.74,968.14
XS Rating Curve= 0 ,0
Exp/Cntr=0.3,0.1

Type RM Length L Ch R = 1 ,269944.1,329.52,238.62,219.17
BEGIN DESCRIPTION:
Ineffective flow in LOB.
Effective flow limit set at Crestwood Levee in ROB.
Rockwood Park in LOB.
Old West Fork river channel in LOB - Sump 12W outfall.
END DESCRIPTION:
XS GIS Cut Line= 2
 2311760.2316922 6968869.5783104 2313297.2647568 6966839.1455683
#Sta/Elev= 30
       0     553   83.59  546.71  312.69  539.08  485.72  545.04  517.18  539.03
  647.46  537.41  673.35     532  708.66     532  729.33  537.43  932.96  539.75
 1176.13  537.19 1412.77  539.53 1483.38  537.33 1526.36  525.01 1554.13  524.28
 1560.87     520 1583.28     520 1600.95  526.85 1615.07  538.16 1655.79     538
  2094.6  537.98 2301.71  524.19 2334.51  525.93 2360.52   513.4 2410.21  512.55
 2424.27  514.55 2450.41  530.87 2485.32  532.59 2535.09     552 2546.59     552
#Mann= 4 ,-1,0
       0     .15       0 1655.79     .06       0 2334.51    .035       0
 2450.41     .06       0
#XS Ineff= 3 ,-1
       0 1052.67     560 2535.09 2546.59     560 1052.67 1878.98  539.31
Permanent Ineff=
       F       T       F
Bank Sta=2334.51,2450.41
XS Rating Curve= 0 ,0
Exp/Cntr=0.3,0.1

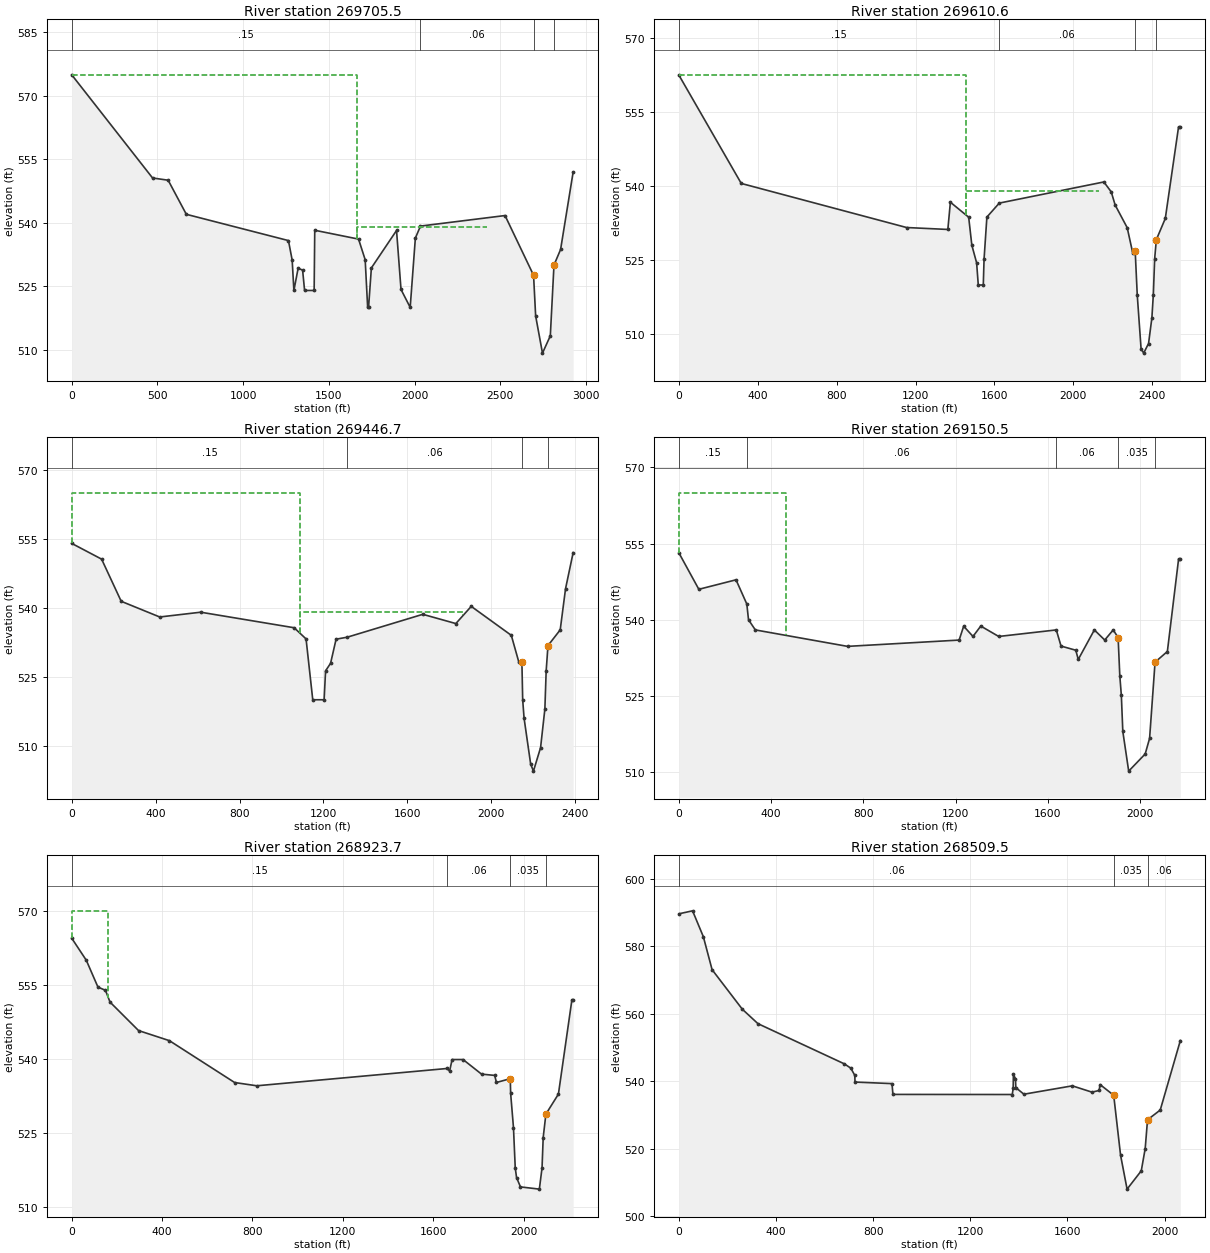
Type RM Length L Ch R = 1 ,269705.5,150.52,94.89,84.69
BEGIN DESCRIPTION:
Ineffective flow in LOB.
Effective flow limit set at Crestwood Levee in ROB.
Rockwood Park in LOB.
Old West Fork river channel in LOB - Sump 12W outfall.
END DESCRIPTION:
XS GIS Cut Line= 2
 2312284.9958912 6969622.2601929  2313466.466848 6966945.7924605
#Sta/Elev= 30
       0  574.97  471.53  550.59  562.53  550.06  668.66     542 1264.45  535.79
 1286.11   531.2 1296.24     524 1320.99  529.26 1347.11  528.81 1358.63     524
 1414.43     524 1417.92  538.23 1673.52  536.14 1712.13  531.27 1726.63     520
 1731.91     520 1748.36  529.33 1895.14  538.18 1921.24  524.24 1974.78     520
 2004.99  536.38 2034.78  539.22 2528.23  541.71 2694.67  527.59 2706.79  517.98
 2746.69  509.19 2792.41  513.28 2813.81     530 2852.36  533.69 2925.64     552
#Mann= 4 ,-1,0
       0     .15       0 2034.78     .06       0 2694.67    .035       0
 2813.81     .06       0
#XS Ineff= 2 ,-1
       0 1665.82 574.893 1665.82  2424.3     539
Permanent Ineff=
       F       F
Bank Sta=2694.67,2813.81
XS Rating Curve= 0 ,0
Exp/Cntr=0.3,0.1

Type RM Length L Ch R = 1 ,269610.6,278.74,163.85,144.53
BEGIN DESCRIPTION:
Ineffective flow in LOB.
Effective flow limit set at Crestwood Levee in ROB.
Rockwood Park in LOB.
Old West Fork river channel in LOB - Sump 12W outfall.
END DESCRIPTION:
XS GIS Cut Line= 2
 2312837.0971602 6969415.2222008   2313533.07037 6966969.8893684
#Sta/Elev= 30
       0   562.5  316.05  540.57  1154.4  531.64 1363.56  531.25 1376.39  536.77
 1469.18  533.73 1485.22  528.05 1509.43   524.5 1517.87     520 1543.31     520
 1547.12   525.2 1561.54  533.76 1624.37  536.59 2154.61  540.87 2192.08  538.86
 2211.87   536.2 2272.95  531.61 2300.67  526.56  2313.6  526.79  2323.9     518
 2343.26  507.12 2356.51   506.2 2381.24  508.15 2398.06  513.31 2405.48     518
 2412.24  525.32 2420.83  529.19 2466.15  533.47 2533.31     552 2542.45     552
#Mann= 4 ,-1,0
       0     .15       0 1624.37     .06       0  2313.6    .035       0
 2420.83     .06       0
#XS Ineff= 2 ,-1
       0  1453.6 562.569  1453.6 2131.91     539
Permanent Ineff=
       F       F
Bank Sta=2313.6,2420.83
XS Rating Curve= 0 ,0
Exp/Cntr=0.3,0.1

Type RM Length L Ch R = 1 ,269446.7,360.06,296.23,285.87
BEGIN DESCRIPTION:
Ineffective flow in LOB.
Effective flow limit set at Crestwood Levee in ROB.
Rockwood Park in LOB.
Old West Fork river channel in LOB - Sump 12W outfall.
END DESCRIPTION:
XS GIS Cut Line= 2
 2313577.4148564 6969377.5789413 2313650.8252601 6966988.0147794
#Sta/Elev= 30
       0     554  142.43  550.58  235.84  541.41  419.51     538  614.82  539.04
 1060.47  535.66 1117.23  533.23 1149.19     520  1203.3     520 1210.31   526.3
 1234.07  527.92  1260.4  533.17 1313.92  533.61 1673.82  538.58  1831.4  536.57
  1904.8  540.31 2095.85  534.01 2131.38  528.24 2146.33  528.27 2150.08     520
 2156.69     516 2188.16     506 2201.38  504.48 2235.35  509.58  2255.9     518
 2262.04  526.27 2270.68  531.78 2329.01   535.2 2354.45  544.16 2390.69     552
#Mann= 4 ,-1,0
       0     .15       0 1313.92     .06       0 2146.33    .035       0
 2270.68     .06       0
#XS Ineff= 2 ,-1
       0 1086.44     565 1086.44 1866.04     539
Permanent Ineff=
       F       F
Bank Sta=2146.33,2270.68
XS Rating Curve= 0 ,0
Exp/Cntr=0.3,0.1

Type RM Length L Ch R = 1 ,269150.5,250.63,226.75,222.45
BEGIN DESCRIPTION:
Downstream of old West Fork channel - Sump 12W outfall.
Ineffective flow in LOB.
Effective flow limit set at Crestwood Levee in ROB.
Rockwood Park in LOB.
END DESCRIPTION:
XS GIS Cut Line= 3
 2314093.0585315 6969131.5963874 2313989.3920079 6967696.5975794
 2313923.5900351 6966963.8842953
#Sta/Elev= 30
       0  553.16    86.3     546  247.57  547.87  294.41   543.1  301.73     540
  331.32     538  731.24  534.76 1215.12     536 1234.76  538.73 1275.18  536.72
 1308.96  538.76 1386.82  536.71 1636.45     538 1657.01  534.82 1720.96     534
  1731.7  532.19 1801.49     538 1846.49  536.01 1883.22     538 1904.55   536.5
 1911.83  528.99 1918.51  525.13 1924.93     518 1950.39  510.19 2021.96  513.57
 2041.06  516.65 2064.76  531.65 2118.13  533.75 2166.91     552  2174.4     552
#Mann= 5 ,-1,0
       0     .15       0  294.41     .06       0 1636.45     .06       0
 1904.55    .035       0 2064.76     .06       0
#XS Ineff= 2 ,-1
       0  465.04     565  465.04 1904.55   536.5
Permanent Ineff=
       F       F
Bank Sta=1904.55,2064.76
XS Rating Curve= 0 ,0
Exp/Cntr=0.3,0.1

Type RM Length L Ch R = 1 ,268923.7,673.79,414.3,388.89
BEGIN DESCRIPTION:
Ineffective flow in LOB.
Effective flow limit set at Crestwood Levee in ROB.
Rockwood Park in LOB.
END DESCRIPTION:
XS GIS Cut Line= 3
 2314410.5678546 6969138.1062693 2314246.3454031 6967738.2347142
 2314140.1031099 6966935.2286812
#Sta/Elev= 30
       0  564.46   64.42     560  116.13  554.56  149.17  553.92   169.6  551.53
  295.82  545.77  432.33  543.73  721.02  535.26  819.13   534.6  1661.5   538.1
 1672.76  537.58 1683.57  539.91 1732.18  539.91 1813.93  536.96 1872.08   536.7
 1879.94  535.27 1938.14     536  1941.1  536.02 1942.79  533.06 1955.31  526.14
 1963.12     518 1968.98  516.02 1986.31  514.14 2069.86  513.69 2081.77     518
 2086.86  524.13 2098.85  528.87 2154.23  532.91 2213.97     552 2219.47     552
#Mann= 4 ,-1,0
       0     .15       0  1661.5     .06       0 1938.14    .035       0
 2098.85     .06       0
#XS Ineff= 1 ,-1
       0  161.86     570
Permanent Ineff=
       F
Bank Sta=1938.14,2098.85
XS Rating Curve= 0 ,0
Exp/Cntr=0.3,0.1

Type RM Length L Ch R = 1 ,268509.5,514.72,361.42,330.71
BEGIN DESCRIPTION:
Effective flow limit set at Crestwood Levee in ROB.
Rockwood Park in LOB.
END DESCRIPTION:
XS GIS Cut Line= 3
 2315640.7218795 6968561.5741459 2314602.5787744 6967115.7154663
  2314486.829767 6966855.3252486
#Sta/Elev= 30
       0  589.56   56.17  590.44  100.56  582.77  136.55     573  261.03  561.28
  325.38     557  681.71  545.07  707.95   543.8   724.3  541.66  725.07  539.69
  877.46  539.23  881.25  536.03 1372.78     536 1376.55  537.85 1377.35  542.02
 1385.88  540.67 1387.44  538.04 1420.69  536.09 1619.99  538.57 1700.96   536.7
 1730.51   537.2 1734.32  538.95 1790.47  535.78 1818.79     518 1845.56  507.96
    1904  513.38  1920.2     520 1929.78  528.51 1982.13   531.4 2064.92     552
#Mann= 3 ,-1,0
       0     .06       0 1790.47    .035       0 1929.78     .06       0
Bank Sta=1790.47,1929.78
XS Rating Curve= 0 ,0
Exp/Cntr=0.3,0.1

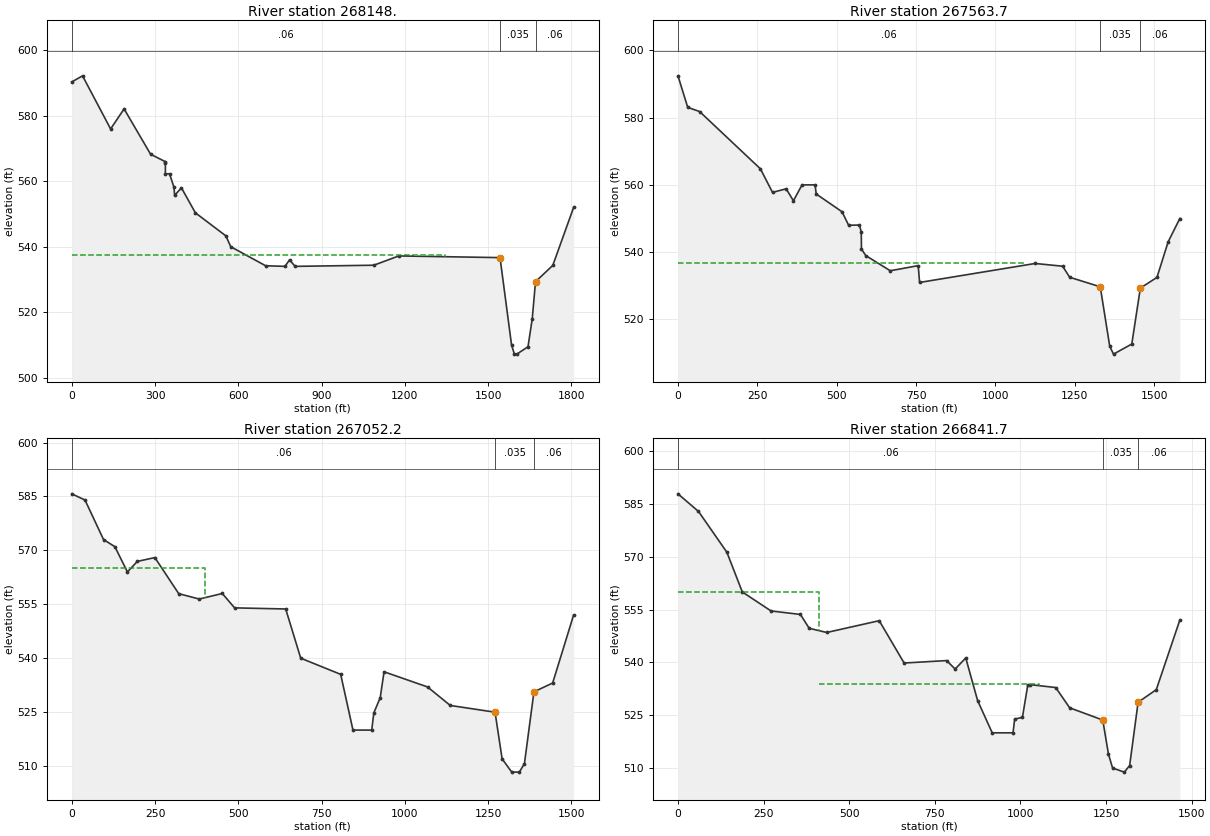
Type RM Length L Ch R = 1 ,268148. ,589.13,584.37,578.78
BEGIN DESCRIPTION:
Rockwood Park in LOB.
Effective flow limit set at Crestwood Levee in ROB.
END DESCRIPTION:
XS GIS Cut Line= 3
  2316056.660756  6967876.541183  2314895.577905 6966858.5131669
 2314707.7108512 6966673.3810775
#Sta/Elev= 30
       0  590.36   38.82  592.23  139.95     576  188.54  582.12  284.05  568.27
  336.95     566  337.27  565.64  337.38  562.29  352.29  562.29  368.32  558.15
   370.6   555.7  395.11     558   445.3  550.37  555.24  543.32  572.89     540
  698.39  534.19  768.12     534  784.69     536  804.49     534 1088.17  534.35
  1178.2  537.19 1542.89  536.67 1584.52  509.91 1594.66   507.2 1603.55  507.18
 1643.72  509.45 1658.96     518 1670.75  529.32 1733.05   534.3 1807.94     552
#Mann= 3 ,-1,0
       0     .06       0 1542.89    .035       0 1670.75     .06       0
#XS Ineff= 2 , 0
       0 1345.36  537.41               0
Permanent Ineff=
       F       F
Bank Sta=1542.89,1670.75
XS Rating Curve= 0 ,0
Exp/Cntr=0.3,0.1

Type RM Length L Ch R = 1 ,267563.7,511.85,511.43,510.56
BEGIN DESCRIPTION:
Rockwood Park in LOB.
Effective flow limit set at Crestwood Levee in ROB.
END DESCRIPTION:
XS GIS Cut Line= 2
 2316322.6662265 6967320.8747503 2315128.6425903 6966285.2088901
#Sta/Elev= 30
       0  592.41   30.73  583.04   68.13   581.8  259.64  564.77   297.8  557.77
  340.78  558.83  363.67  555.27  390.76     560  431.93     560  435.36   557.3
  516.88     552  537.49     548  571.47  548.07  577.27     546  577.93  540.94
  591.34     539  668.75  534.48  756.71     536  761.01     531 1124.88  536.64
 1211.53  535.83 1233.78  532.54 1330.04  529.71 1359.94     512 1371.83   509.7
 1429.34   512.7 1456.36  529.33 1508.63   532.5 1543.81  543.05  1580.6     550
#Mann= 3 ,-1,0
       0     .06       0 1330.04    .035       0 1456.36     .06       0
#XS Ineff= 2 , 0
       0 1091.35  536.77               0
Permanent Ineff=
       F       F
Bank Sta=1330.04,1456.36
XS Rating Curve= 0 ,0
Exp/Cntr=0.3,0.1

Type RM Length L Ch R = 1 ,267052.2,243.99,210.56,203.95
BEGIN DESCRIPTION:
Downstream of Sump 13W outfall.
Ineffective flow in LOB to model all flows: Set at sta 399.88 to represent ineffective flow for the more frequent flood flows (up to 50-year).  For 100-year and rarer events the entire floodplain is effective since flow overtops low point in University Drive roadway in LOB.
Rockwood Park in LOB.
Effective flow limit set at Crestwood Levee in ROB.
END DESCRIPTION:
XS GIS Cut Line= 2
 2316648.3405147 6966921.1841322 2315504.8576535 6965940.2267663
#Sta/Elev= 30
       0  585.73   39.81     584   95.44     573  129.36  571.03  167.06     564
  196.75  566.92  249.44     568  321.13  557.95  382.68  556.46  451.93     558
  488.88     554  642.28  553.69   687.4     540  807.34   535.5  844.22     520
  900.56     520  906.85  524.77  926.04  529.02  937.53  536.22 1068.08     532
 1136.33  526.85 1270.79  524.97 1291.97     512 1320.94   508.3 1343.82  508.33
 1358.99  510.66 1387.51  530.63 1387.51  530.64 1443.73  533.09 1506.59     552
#Mann= 3 ,-1,0
       0     .06       0 1270.79    .035       0 1387.51     .06       0
#XS Ineff= 2 ,-1
       0  399.88     565  399.88  937.42  536.14
Permanent Ineff=
       F       F
Bank Sta=1270.79,1387.51
XS Rating Curve= 0 ,0
Exp/Cntr=0.3,0.1

Type RM Length L Ch R = 1 ,266841.7,417.55,396.52,380.5
BEGIN DESCRIPTION:
Ineffective flow in LOB to model all flows: Set at sta 410.76 to represent ineffective flow for the more frequent flood flows (up to 50-year).  For 100-year and rarer events the entire floodplain is effective since flow overtops low point in University Drive roadway in LOB.
Rockwood Park in LOB.
Effective flow limit set at Crestwood Levee in ROB.
END DESCRIPTION:
XS GIS Cut Line= 2
 2316826.3452583 6966681.6518269  2315651.002271 6965806.3262907
#Sta/Elev= 30
       0  587.86   59.93  582.86  142.86  571.27  187.84     560  271.86   554.6
  357.61  553.61  383.12  549.68  434.52  548.49   587.7  551.84  660.41  539.82
  784.53  540.51  809.45  538.11  840.42  541.26  874.99  529.17  917.65     520
  978.48     520  983.19   523.9  1005.9  524.39 1021.51  533.56 1028.41  533.68
 1103.07  532.86 1143.85   527.1  1240.5  523.63    1257     514 1269.16     510
 1303.53  508.84    1319  510.72 1343.71  528.68 1396.84  532.26 1465.48     552
#Mann= 3 ,-1,0
       0     .06       0  1240.5    .035       0 1343.71     .06       0
#XS Ineff= 2 ,-1
       0  410.76     560  410.76 1052.87  533.73
Permanent Ineff=
       F       F
Bank Sta=1240.5,1343.71
XS Rating Curve= 0 ,0
Exp/Cntr=0.3,0.1