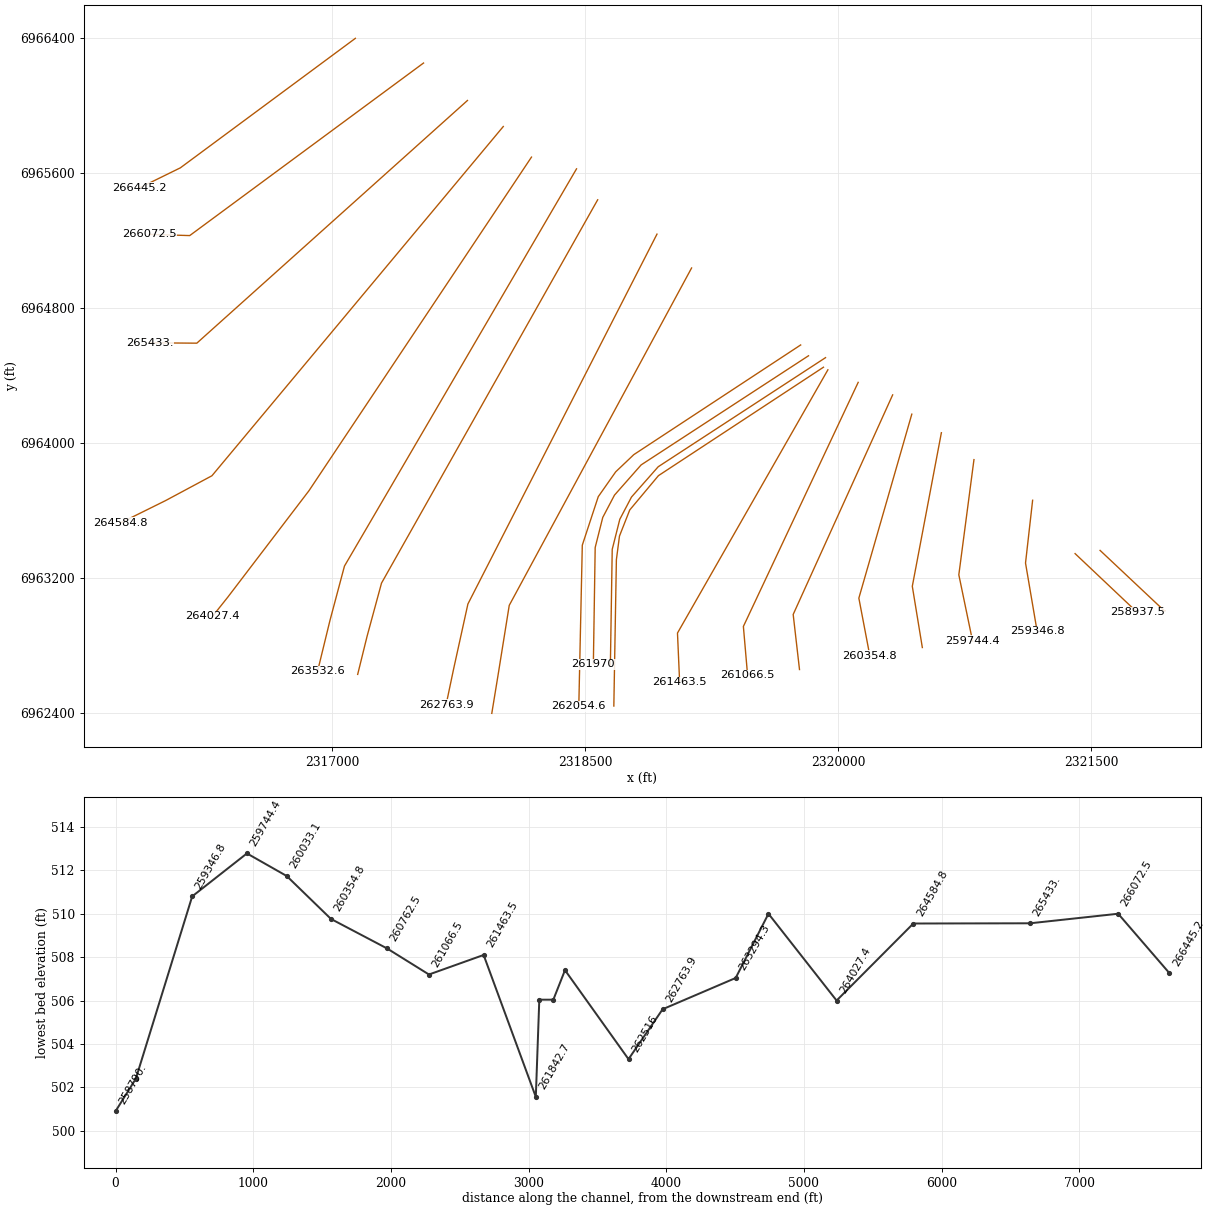
HEC-RAS study CDC_Consolidated_Model.prj: Upper Trinity CDC Consolidated Model

--- CDC_Consolidated_Model.g11 (geometry) --- (continued)

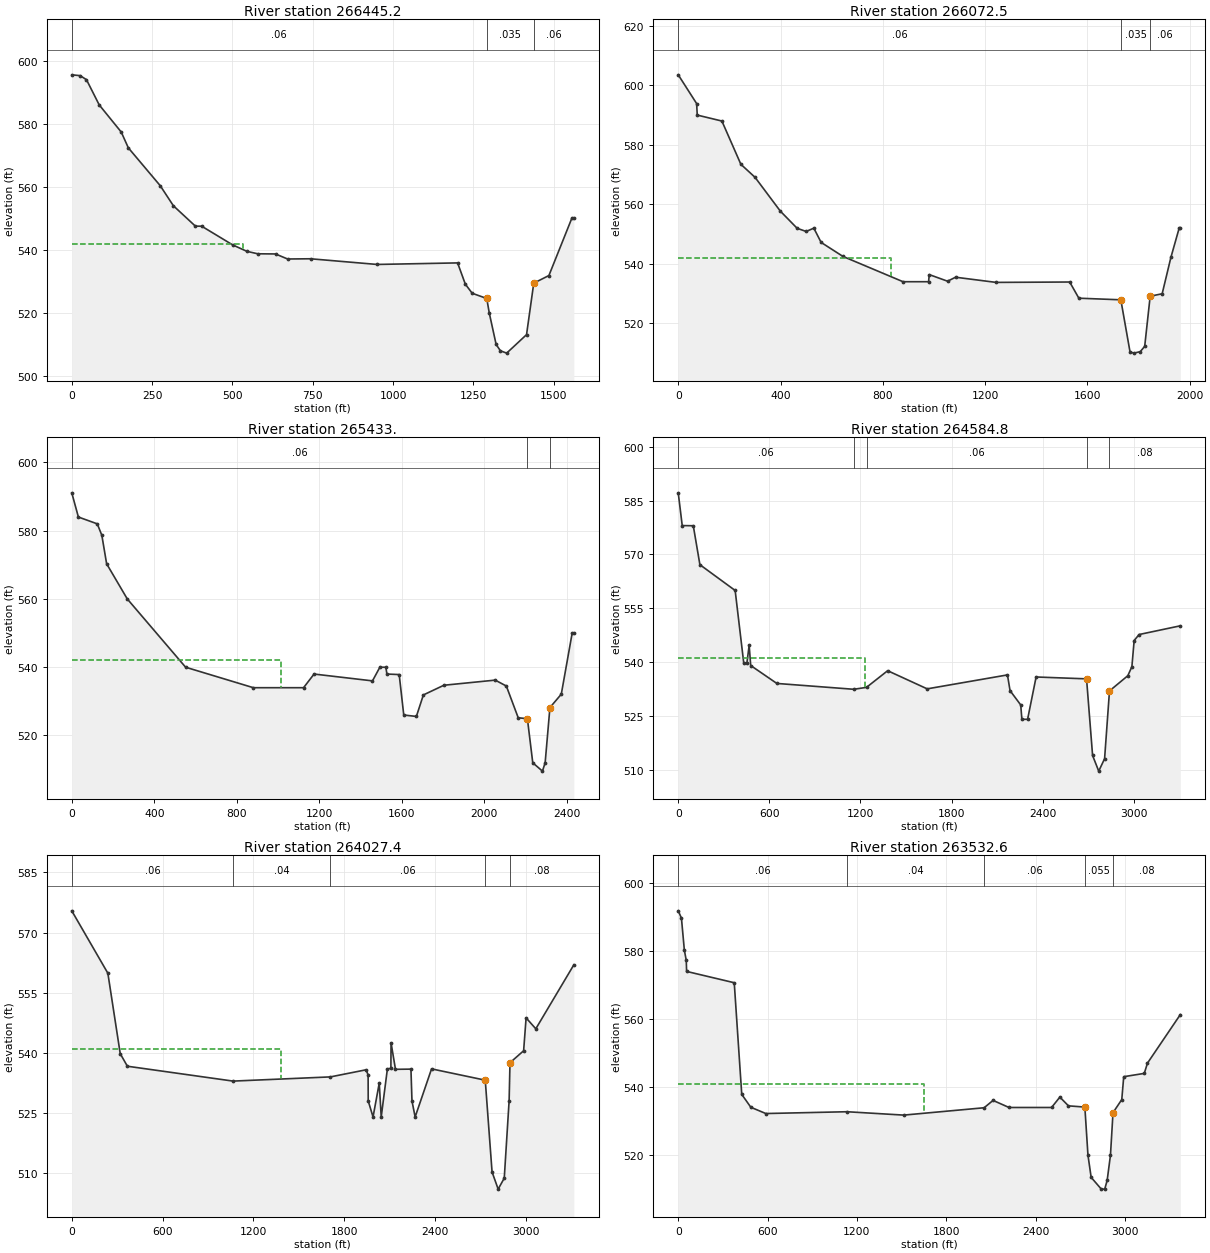
Type RM Length L Ch R = 1 ,266445.2,416.4,372.62,336.78
BEGIN DESCRIPTION:
Ineffective flow in LOB to model all flows: Set at sta 533.94 to represent ineffective flow for the more frequent flood flows (up to 50-year).  For 100-year and rarer events the entire floodplain is effective since flow overtops low point in University Drive roadway in LOB.
Rockwood Park in LOB.
Effective flow limit set at Crestwood Levee in ROB.
END DESCRIPTION:
XS GIS Cut Line= 3
 2317137.9577558 6966399.2763682 2316100.1676539 6965631.3444367
 2315856.1388684 6965511.6675395
#Sta/Elev= 30
       0  595.54   26.07  595.28   45.78     594   85.43     586     154  577.39
  176.03  572.38   275.3  560.38  316.35     554  384.78  547.54  404.45  547.52
  500.95  541.58  545.09  539.55     579  538.77  634.17  538.72  671.84  537.12
  743.14  537.19  950.34  535.39 1200.97  535.88 1225.07  529.13 1246.42  526.25
 1291.76  524.59 1299.53     520 1320.92     510 1334.28     508 1353.74  507.26
 1415.56  513.12 1438.03  529.46 1485.18  531.87 1556.34     550 1562.81     550
#Mann= 3 ,-1,0
       0     .06       0 1291.76    .035       0 1438.03     .06       0
#XS Ineff= 1 ,-1
       0  533.94     542
Permanent Ineff=
       F
Bank Sta=1291.76,1438.03
XS Rating Curve= 0 ,0
Exp/Cntr=0.3,0.1

Type RM Length L Ch R = 1 ,266072.5,609.18,639.55,640.84
BEGIN DESCRIPTION:
Ineffective flow in LOB to model all flows: Set at sta 830.4 to represent ineffective flow for the more frequent flood flows (up to 50-year).  For 100-year and rarer events the entire floodplain is effective since flow overtops low point in University Drive roadway in LOB.
Rockwood Park in LOB.
Effective flow limit set at Crestwood Levee in ROB.
END DESCRIPTION:
XS GIS Cut Line= 3
 2317542.0909248 6966252.8277505 2316155.6656411 6965229.6093041
  2315915.214983 6965236.7465023
#Sta/Elev= 30
       0  603.53   72.03  593.86   74.35     590  170.73     588  244.98  573.46
  300.43  569.08  399.43  557.71  465.26  551.94  500.53  550.89  530.33     552
  558.84  547.21  644.03  542.51  879.17     534   979.1     534  981.84  536.39
 1053.36  534.17 1084.68  535.51 1243.38  533.77 1531.04   533.9 1566.86  528.46
 1731.06  527.92 1767.03   510.4 1782.35     510  1807.1   510.5 1824.39  512.28
 1845.82  529.13  1892.7  529.95 1926.92  542.19 1959.11  551.98 1963.68     552
#Mann= 3 ,-1,0
       0     .06       0 1731.06    .035       0 1845.82     .06       0
#XS Ineff= 1 ,-1
       0   830.4     542
Permanent Ineff=
       F
Bank Sta=1731.06,1845.82
XS Rating Curve= 0 ,0
Exp/Cntr=0.3,0.1

Type RM Length L Ch R = 1 ,265433. ,738.25,848.21,899.16
BEGIN DESCRIPTION:
Ineffective flow in LOB to model all flows: Set at sta 1012.75 to represent ineffective flow for the more frequent flood flows (up to 50-year).  For 100-year and rarer events the entire floodplain is effective since flow overtops low point in University Drive roadway in LOB.
Rockwood Park in LOB.
Effective flow limit set at Crestwood Levee in ROB.
END DESCRIPTION:
XS GIS Cut Line= 3
 2317802.7220092 6966030.8085778 2316197.7384879 6964591.5846211
 2315919.6571451  6964593.621876
#Sta/Elev= 30
       0  591.09   32.06     584  123.66     582  145.74  578.65  169.01   570.3
   269.1     560  551.88     540  880.32     534 1123.62     534 1174.49     538
 1457.77     536 1493.51     540 1522.53     540 1527.67     538  1587.2  537.85
 1609.34     526 1670.48  525.58 1704.45  531.88 1803.81  534.72 2052.77  536.22
 2106.65  534.49 2164.22  525.19 2208.68  524.92 2234.73     512 2281.68  509.56
 2294.73     512 2317.89  528.18 2372.98   532.1  2425.8     550 2433.86     550
#Mann= 3 ,-1,0
       0     .06       0 2208.68    .035       0 2317.89     .06       0
#XS Ineff= 1 ,-1
       0 1012.75     542
Permanent Ineff=
       F
Bank Sta=2208.68,2317.89
XS Rating Curve= 0 ,0
Exp/Cntr=0.3,0.1

Type RM Length L Ch R = 1 ,264584.8,522.17,557.41,607.28
BEGIN DESCRIPTION:
Ineffective flow in LOB to model all flows: Set at sta 1232.93 to represent ineffective flow for the more frequent flood flows (up to 50-year).  For 100-year and rarer events the entire floodplain is effective since flow overtops low point in University Drive roadway in LOB.
This river reach from University Drive to the Crestwood Levee is not part of the Fort Worth Floodway project.
Rockwood Park in LOB.
END DESCRIPTION:
XS GIS Cut Line= 4
 2318015.0881068 6965876.3604126 2316287.4912669 6963805.4168273
 2316013.1316901 6963658.3635798 2315745.4483202  6963525.860079
#Sta/Elev= 30
       0  587.15   26.26  578.02   99.14  577.97   142.7  567.11  374.92  559.92
  431.54  539.68  452.42  539.76  467.13  544.62  477.31     539  649.51     534
 1156.42  532.37 1240.08  532.91 1379.32  537.55 1639.76  532.49 2168.42  536.38
 2185.44     532  2255.9     528 2263.31     524 2301.02     524 2357.13   535.8
 2689.35  535.28 2729.11  513.91 2769.52  509.55 2808.18  513.02 2840.42  531.92
 2961.08  536.15 2987.96  538.67 3002.91  545.97 3035.47  547.64 3306.89  550.07
#Mann= 5 ,-1,0
       0     .06       0 1156.42     .04       0 1240.08     .06       0
 2689.35    .055       0 2840.42     .08       0
#XS Ineff= 1 ,-1
       0 1232.93     541
Permanent Ineff=
       F
Bank Sta=2689.35,2840.42
XS Rating Curve= 0 ,0
Exp/Cntr=0.3,0.1

Type RM Length L Ch R = 1 ,264027.4,414.29,494.79,543.87
BEGIN DESCRIPTION:
Ineffective flow in LOB to model all flows: Set at sta 1379.81 to represent ineffective flow for the more frequent flood flows (up to 50-year).  For 100-year and rarer events the entire floodplain is effective since flow overtops low point in University Drive roadway in LOB.
This river reach from University Drive to the Crestwood Levee is not part of the Fort Worth Floodway project.
Rockwood Park in LOB.
END DESCRIPTION:
XS GIS Cut Line= 4
 2318182.2983161 6965694.9539783 2316862.8792089 6963716.7576711
 2316382.6680833 6963087.0465179  2316291.695544 6962972.7335062
#Sta/Elev= 30
       0  575.43  238.38  559.86  320.09  539.79  367.33  536.66 1065.38  532.95
 1708.33     534 1943.69  535.77 1957.19  534.49 1957.85     528 1989.71     524
 2030.68  532.45 2043.66     524 2084.45     536 2107.56  536.13 2108.63  542.49
 2137.85  535.89 2240.02  535.94 2246.79     528 2267.72     524 2376.11     536
 2730.75  533.18  2775.7  510.29 2815.97     506 2856.32  508.74 2888.43  528.08
 2894.13  537.53 2984.18  540.52 3000.54  548.72 3064.65     546 3315.85  561.96
#Mann= 5 ,-1,0
       0     .06       0 1065.38     .04       0 1708.33     .06       0
 2730.75    .055       0 2894.13     .08       0
#XS Ineff= 1 ,-1
       0 1379.81     541
Permanent Ineff=
       F
Bank Sta=2730.75,2894.13
XS Rating Curve= 0 ,0
Exp/Cntr=0.3,0.1

Type RM Length L Ch R = 1 ,263532.6,242.54,238.26,238.82
BEGIN DESCRIPTION:
Ineffective flow in LOB to model all flows: Set at sta 1647.7 to represent ineffective flow for the more frequent flood flows (up to 50-year).  For 100-year and rarer events the entire floodplain is effective since flow overtops low point in University Drive roadway in LOB.
This river reach from University Drive to the Crestwood Levee is not part of the Fort Worth Floodway project.
Rockwood Park in LOB.
END DESCRIPTION:
XS GIS Cut Line= 4
  2318449.473377  6965625.382533 2317073.2828524 6963269.6855465
 2316986.8707047 6962945.6029488 2316913.6191071 6962645.2603666
#Sta/Elev= 30
       0  591.81   21.51  589.66   41.03  580.27   53.98  577.24   56.17     574
  376.25  570.67  426.62  537.85  487.74  534.06  588.52  532.22 1133.93  532.75
  1515.1  531.76 2054.69  533.92 2114.93  536.08  2222.1     534 2507.88     534
 2563.56  537.05 2621.49  534.48 2731.51  534.12 2752.35     520 2773.85  513.46
 2842.11     510 2865.11     510 2881.44  512.58 2903.61     520 2920.63  532.47
 2979.57  536.33 2992.65  543.05  3130.7  544.02 3152.18  547.04 3372.78   561.3
#Mann= 5 ,-1,0
       0     .06       0 1133.93     .04       0 2054.69     .06       0
 2731.51    .055       0 2920.63     .08       0
#XS Ineff= 1 ,-1
       0  1647.7     541
Permanent Ineff=
       F
Bank Sta=2731.51,2920.63
XS Rating Curve= 0 ,0
Exp/Cntr=0.3,0.1

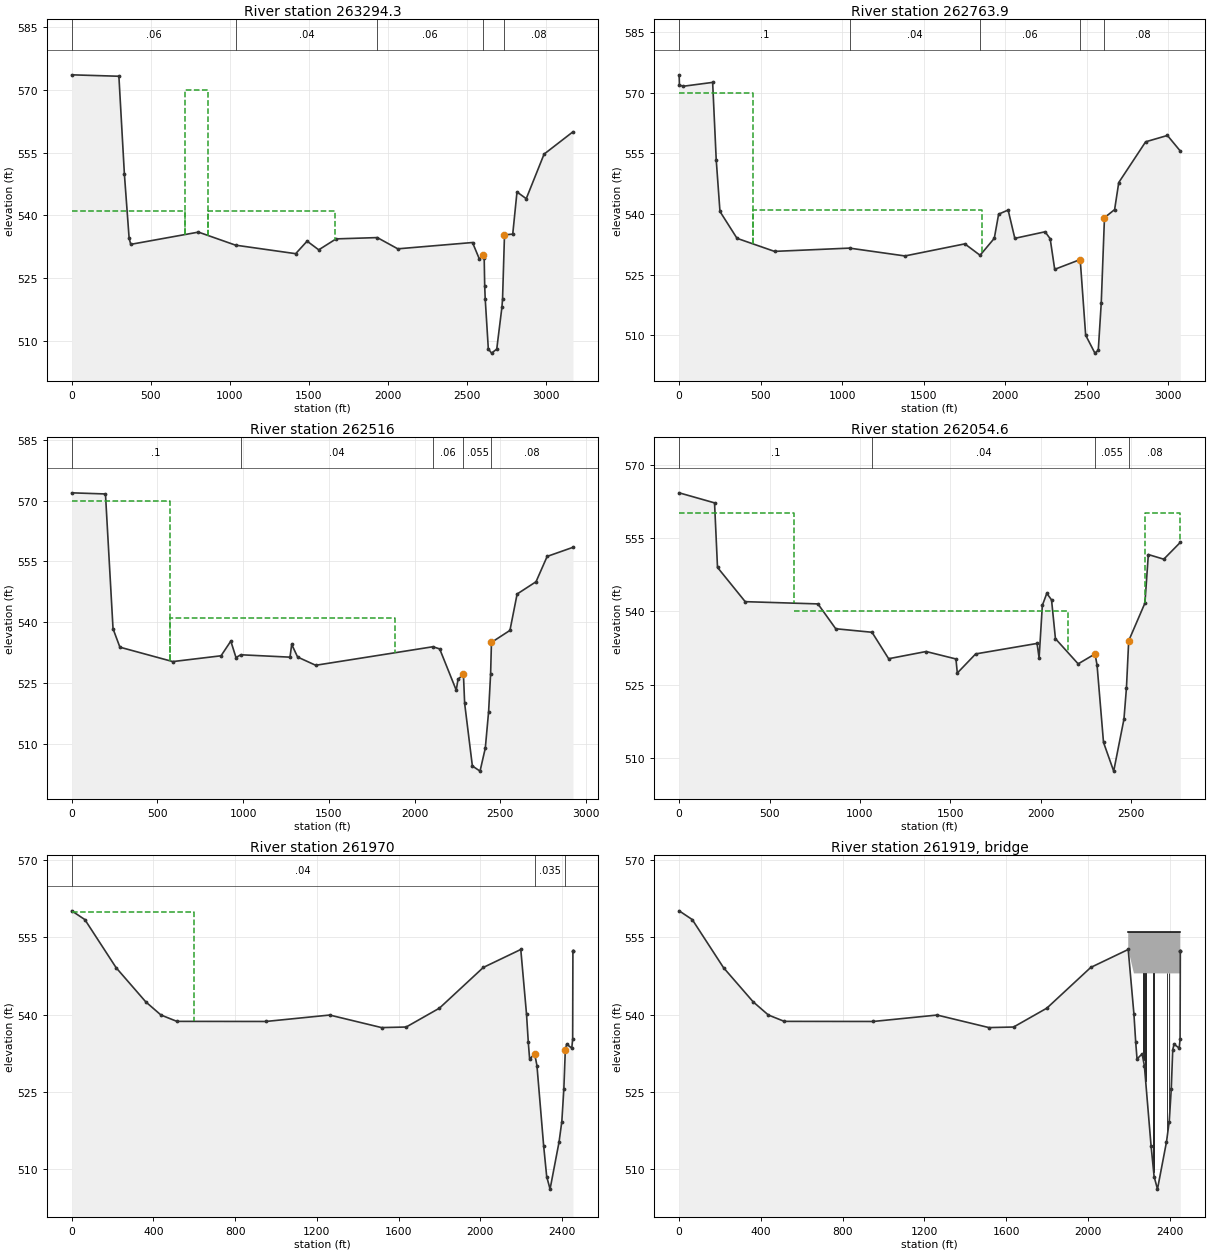
Type RM Length L Ch R = 1 ,263294.3,506.87,530.43,537.94
BEGIN DESCRIPTION:
Ineffective flow in LOB to model all flows: Set at sta 1662.61 to represent ineffective flow for the more frequent flood flows (up to 50-year).  For 100-year and rarer events the entire floodplain is effective since flow overtops low point in University Drive roadway in LOB.
This river reach from University Drive to the Crestwood Levee is not part of the Fort Worth Floodway project.
Rockwood Park in LOB.
END DESCRIPTION:
XS GIS Cut Line= 4
 2318574.8643108 6965441.8108915 2317293.0546276 6963168.8370851
 2317207.7969028  6962854.962541  2317151.656302 6962627.3730998
#Sta/Elev= 30
       0  573.64  298.23   573.3  333.04  549.86  362.92  534.54  373.19  533.07
  801.31     536 1035.68  532.88 1416.05  530.84 1488.33  533.84 1561.82  531.76
 1671.54  534.38 1932.23  534.69 2061.63     532 2534.08  533.51 2578.31  529.49
 2599.42  530.51 2608.03   529.7 2611.28     523 2614.53     520 2634.19  508.01
 2654.81  507.04 2687.37     508 2720.03     518 2724.09     520  2736.4  535.32
 2788.54  535.53 2815.37  545.61 2873.87     544 2986.66  554.66 3169.15     560
#Mann= 5 ,-1,0
       0     .06       0 1035.68     .04       0 1932.23     .06       0
 2599.42    .055       0  2736.4     .08       0
#XS Ineff= 3 ,-1
  714.77   863.6     570       0  714.77     541   863.6 1662.61     541
Permanent Ineff=
       F       F       F
Bank Sta=2599.42,2736.4
XS Rating Curve= 0 ,0
Exp/Cntr=0.3,0.1

Type RM Length L Ch R = 1 ,262763.9,233.98,247.95,257.33
BEGIN DESCRIPTION:
Ineffective flow in LOB to model all flows: Set at sta 1859.29 to represent ineffective flow for the more frequent flood flows (up to 50-year).  Set at sta 454.57 for 100-year and rarer events since flow overtops low point in University Drive roadway in LOB. This river reach from University Drive to the Crestwood Levee is not part of the Fort Worth Floodway project.  Rockwood Park in LOB.
CDC FW 100115-01 Rockwood Golf Course Renovation
Cross-section 262763.9 - 269446.7  Project in LOB.
END DESCRIPTION:
XS GIS Cut Line= 4
 2318926.5612735 6965238.2849117  2317805.327725 6963044.9678375
 2317720.6848713 6962660.2769382 2317675.8884682 6962447.1253665
#Sta/Elev= 30
       0  574.45    1.77     572   22.69  571.61  205.52  572.58  227.48  553.44
  250.48  540.64  355.09     534  585.16  530.77 1045.19  531.58 1385.33  529.64
 1752.66  532.63 1846.23  529.81 1933.43     534  1960.1  539.98 2018.36     541
 2059.47     534 2245.03  535.62 2276.33   533.9  2304.1  526.33 2460.54  528.75
 2494.07  510.03  2550.8   505.6 2571.44  506.31 2589.67     518 2609.44  539.11
  2671.7  541.11 2697.06  547.81 2862.01  557.88 2995.64  559.45 3074.99  555.58
#Mann= 5 ,-1,0
       0      .1       0 1045.19     .04       0 1846.23     .06       0
 2460.54    .055       0 2609.44     .08       0
#XS Ineff= 2 ,-1
  454.57 1859.29     541       0  454.57     570
Permanent Ineff=
       F       F
Bank Sta=2460.54,2609.44
XS Rating Curve= 0 ,0
Exp/Cntr=0.3,0.1

Type RM Length L Ch R = 1 ,262516  ,298.64,461.35,465.94
BEGIN DESCRIPTION:
Ineffective flow in LOB to model all flows: Set at sta 1885.77 to represent ineffective flow for the more frequent flood flows (up to 50-year).  Set at sta 572.27 for 100-year and rarer events since flow overtops low point in University Drive roadway in LOB.
This river reach from University Drive to the Crestwood Levee is not part of the Fort Worth Floodway project.
Rockwood Park in LOB.
END DESCRIPTION:
XS GIS Cut Line= 4
 2319131.7808389 6965037.5137309 2318050.4568745 6963036.8046873
    2317983.0601 6962616.6527183 2317946.9481199 6962396.2156429
#Sta/Elev= 30
       0  571.92  196.75  571.64   240.9  538.41  280.98  533.86  589.47  530.31
   870.9  531.74  927.82  535.36  958.11   531.3  985.68  531.99 1273.07   531.4
 1282.89  534.55 1317.39  531.43 1422.87   529.4 2106.69  533.97    2146  533.43
 2242.46  523.27 2253.04  525.95 2284.47  527.19 2291.55     520  2336.6  504.57
 2381.32   503.3 2412.09  508.99 2431.35     518 2443.04  527.33 2447.89  535.04
 2555.72     538 2597.59  546.97 2707.94     550  2772.7  556.24 2923.12  558.48
#Mann= 5 ,-1,0
       0      .1       0  985.68     .04       0 2106.69     .06       0
 2284.47    .055       0 2447.89     .08       0
#XS Ineff= 2 ,-1
  572.27 1885.77     541       0  572.27     570
Permanent Ineff=
       F       F
Bank Sta=2284.47,2447.89
XS Rating Curve= 0 ,0
Exp/Cntr=0.3,0.1

Type RM Length L Ch R = 1 ,262054.6,84.6,84.6,84.6
BEGIN DESCRIPTION:
Ineffective flow in LOB to model all flows: Set at sta 2152.68 to represent ineffective flow for the more frequent flood flows (up to 50-year).  Set at sta 634.61 for 100-year and rarer events since flow overtops low point in University Drive roadway in LOB.
This river reach from University Drive to the Crestwood Levee is not part of the Fort Worth Floodway project.
Rockwood Park in LOB.
END DESCRIPTION:
XS GIS Cut Line= 6
 2319778.5573565 6964580.9039087 2318789.2381059 6963930.6821422
  2318681.554113 6963828.4035188 2318578.2907623 6963681.1874465
 2318483.6789066 6963393.6835242  2318462.924445  6962438.869655
#Sta/Elev= 30
       0  564.22  195.85  562.17  212.22  548.99  365.45     542  767.87  541.54
  866.14  536.47 1066.91  535.75 1158.91  530.35  1366.1  531.82 1531.19   530.3
 1538.81  527.43  1640.3  531.33 1980.08  533.47 1991.27   530.5  2009.2  541.24
 2033.84   543.7  2060.1  542.36 2081.64  534.44 2207.36   529.3 2300.63  531.33
 2311.84  529.05 2347.51  513.28 2403.86   507.4  2460.6     518 2474.41  524.36
 2486.88  534.01 2576.59   541.7 2595.53  551.62 2680.86  550.67 2772.64  554.11
#Mann= 4 ,-1,0
       0      .1       0 1066.91     .04       0 2300.63    .055       0
 2486.88     .08       0
#XS Ineff= 3 ,-1
  634.61 2152.68     540 2576.58 2772.64     560       0  634.61     560
Permanent Ineff=
       F       F       F
Bank Sta=2300.63,2486.88
XS Rating Curve= 0 ,0
Exp/Cntr=0.3,0.1

Type RM Length L Ch R = 1 ,261970  ,102,102,102
BEGIN DESCRIPTION:
Upstream of University Drive.
Copy of cross-section 261868.
END DESCRIPTION:
XS GIS Cut Line= 6
 2319825.0098304 6964516.8145688 2318832.5389601 6963869.6806404
 2318674.4705352 6963690.3974108 2318604.9860767 6963558.1622598
 2318560.0832411 6963379.9219647 2318549.2245947 6962687.6727682
#Sta/Elev= 30
       0  560.17   64.17  558.47  217.43   549.1  362.45  542.46  436.52  539.91
  514.42  538.67     950  538.65 1262.33   539.9 1516.29  537.46 1636.81  537.57
 1799.49  541.24 2014.34  549.16 2197.63  552.65 2225.71  540.07 2234.34  534.63
 2240.86  531.35 2265.73  532.35 2276.73  530.06 2309.54  514.46 2324.42  508.49
 2340.88  506.04 2385.01  515.23 2398.44  519.19 2408.34  525.48 2415.61  533.18
 2422.08  534.23 2447.13  533.47  2451.5  535.21 2452.73  552.45 2452.86  552.45
#Mann= 3 ,0,0
       0     .04       0 2265.73    .035       0 2415.61     .04       0
#XS Ineff= 1 ,-1
       0     600     560
Permanent Ineff=
       F
Bank Sta=2265.73,2415.61
XS Rating Curve= 0 ,0
Exp/Cntr=0.5,0.3

Type RM Length L Ch R = 3 ,261919  ,,,
BEGIN DESCRIPTION:
University Drive
Data from TXDOT bridge plans for upstream bridge, USACE 1975 survey for downstream bridge.
Double bridges - a composite of both bridges represented.  Total bridge width set at 100 feet.
END DESCRIPTION:
Node Name=University Drive
Bridge Culvert--1,0,-1,-1, 0
Deck Dist Width WeirC Skew NumUp NumDn MinLoCord MaxHiCord MaxSubmerge Is_Ogee
1,100,2.6,0, 2, 2, , , 0.95, 0, 0,0,,
 2197.63 2452.73
     556     556
     548     548
 2197.63 2452.73
     556     556
     548     548
Pier Skew, UpSta & Num, DnSta & Num=  ,2271.43, 2 ,2271.43, 2 , 0 , 0 , 0 ,,
     2.5     2.5
     480     551
     2.5     2.5
     480     551
Pier Skew, UpSta & Num, DnSta & Num=  ,2282.93, 2 ,2282.93, 2 , 0 , 0 , 0 ,,
       3       3
     480     551
       3       3
     480     551
Pier Skew, UpSta & Num, DnSta & Num=  ,2322.33, 2 ,2322.33, 2 , 0 , 0 , 0 ,,
     2.5     2.5
     480     551
     2.5     2.5
     480     551
Pier Skew, UpSta & Num, DnSta & Num=  ,2387.93, 2 ,2387.93, 2 , 0 , 0 , 0 ,,
       3       3
     480     551
       3       3
     480     551
Pier Skew, UpSta & Num, DnSta & Num=  ,2397.83, 2 ,2397.83, 2 , 0 , 0 , 0 ,,
     2.5     2.5
     480     551
     2.5     2.5
     480     551
BR Coef=-1 , 0 , 0 ,, 0 ,,,0.8,-1,,0,
WSPro=,,,, 1 ,,,, 0 ,,,, 0 ,,,,-1 ,-1 ,-1 , 0 , 0 , 0 , 0 , 0
BC Design=,, 0 ,, 0 ,,,,,,
BC Use User HTab Curves=0
BC User HTab FreeFlow(D)= 0

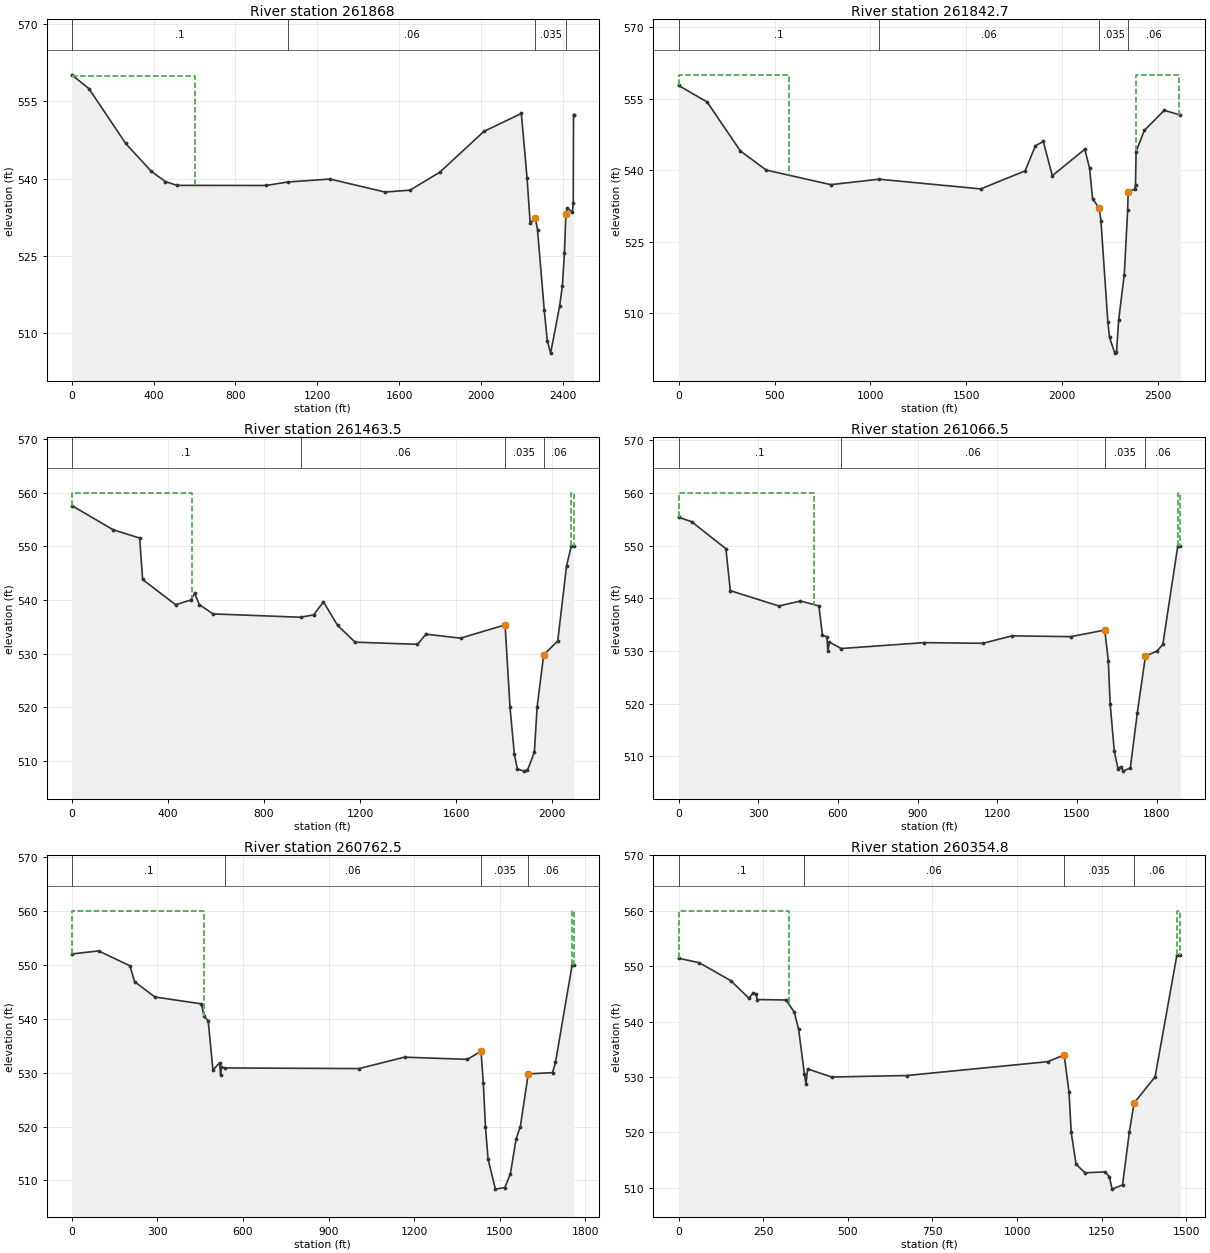
Type RM Length L Ch R = 1 ,261868  ,25.3,25.3,25.3
BEGIN DESCRIPTION:
Downstream of University Drive.
Cross-section generated from points along centerline of west roadway.
END DESCRIPTION:
XS GIS Cut Line= 6
 2319926.0649996 6964505.7006505 2318933.5941293 6963858.5667221
 2318775.5257044 6963679.2834925 2318706.0412459 6963547.0483415
 2318661.1384103 6963368.8080464  2318650.053097   6962676.73014
#Sta/Elev= 30
       0  560.17   84.37  557.47  263.42  546.83  389.12  541.39  457.44  539.41
  514.42  538.67     950  538.65 1054.73  539.32 1262.33   539.9 1531.38  537.37
 1653.68  537.74 1799.49  541.24 2014.34  549.16 2197.63  552.65 2225.71  540.07
 2240.86  531.35 2265.73  532.35 2276.73  530.06 2309.54  514.46 2324.42  508.49
 2340.88  506.04 2385.01  515.23 2398.44  519.19 2408.34  525.48 2415.61  533.18
 2422.08  534.23 2447.13  533.47  2451.5  535.21 2452.73  552.45 2452.86  552.45
#Mann= 4 ,-1,0
       0      .1       0 1054.73     .06       0 2265.73    .035       0
 2415.61     .06       0
#XS Ineff= 1 ,-1
       0     600     560
Permanent Ineff=
       F
Bank Sta=2265.73,2415.61
XS Rating Curve= 0 ,0
Exp/Cntr=0.5,0.3

Type RM Length L Ch R = 1 ,261842.7,564.03,379.14,385.2
BEGIN DESCRIPTION:
Ineffective flow in LOB, ROB.
Effective flow in ROB set at Clear Fork Levee Loop.
END DESCRIPTION:
XS GIS Cut Line= 6
 2319913.9009579 6964449.0371878   2318935.15858 6963805.8916899
 2318764.9158879 6963602.3423753 2318704.1966166  6963447.882413
 2318685.8287832 6963307.7366459 2318670.6845186 6962439.7799703
#Sta/Elev= 30
       0  557.77  149.32  554.28  322.52     544  456.64     540  793.18  536.94
 1045.23  538.08 1574.19  536.05 1805.43  539.82 1859.72  545.12  1900.3     546
 1947.51  538.82 2116.62  544.37 2141.42  540.42 2157.32     534 2191.33     532
 2200.74  529.37    2237     508 2245.48  504.87 2272.83  501.56 2281.76  501.77
 2293.07   508.5 2322.14     518 2340.16   531.7 2342.53  535.48  2376.5     536
 2380.89  536.94 2383.85  543.88 2426.93  548.33 2530.52  552.54 2614.39  551.56
#Mann= 4 ,-1,0
       0      .1       0 1045.23     .06       0 2191.33    .035       0
 2342.53     .06       0
#XS Ineff= 2 ,-1
 2384.27 2607.59     560       0  574.12     560
Permanent Ineff=
       F       F
Bank Sta=2191.33,2342.53
XS Rating Curve= 0 ,0
Exp/Cntr=0.3,0.1

Type RM Length L Ch R = 1 ,261463.5,338.43,397.03,400.82
BEGIN DESCRIPTION:
Ineffective flow in LOB.
Effective flow in ROB set at Clear Fork Levee Loop.
END DESCRIPTION:
XS GIS Cut Line= 3
 2319940.0365467 6964433.5532725 2319048.1211568 6962872.5953292
 2319060.8615515  6962581.488389
#Sta/Elev= 30
       0  557.63  171.97  553.12  282.91  551.56  295.02  543.84  432.28  539.14
  495.45     540  511.64  541.26  531.29  539.15   588.2  537.42  952.46   536.8
 1007.23  537.24 1047.92  539.67 1107.02  535.27 1179.75  532.15 1439.42  531.75
 1474.96  533.64 1618.55   532.9 1804.15  535.37 1824.63     520 1842.72  511.29
 1855.08  508.53 1881.78   508.1 1897.12  508.24 1926.06   511.6 1937.51     520
 1964.79  529.78 2023.35  532.36 2060.09  546.37 2079.24     550 2089.19     550
#Mann= 4 ,-1,0
       0      .1       0  952.46     .06       0 1804.15    .035       0
 1964.79     .06       0
#XS Ineff= 3 ,-1
       0  500.89     560  500.89 1804.15  535.37 2079.24 2089.19     560
Permanent Ineff=
       F       F       T
Bank Sta=1804.15,1964.79
XS Rating Curve= 0 ,0
Exp/Cntr=0.3,0.1

Type RM Length L Ch R = 1 ,261066.5,269.54,304.03,306.52
BEGIN DESCRIPTION:
Ineffective flow in LOB.
Effective flow in ROB set at Clear Fork Levee Loop.
END DESCRIPTION:
XS GIS Cut Line= 3
 2320119.6997441 6964359.2097375 2319438.9025603 6962911.6605835
 2319463.7749603 6962623.2845891
#Sta/Elev= 30
       0  555.36    48.8  554.54  178.32  549.39  194.88  541.44  377.77  538.53
  458.65  539.48  528.39  538.54  541.75  533.02   558.3  532.67   562.3  529.93
  567.94  531.67  612.26  530.46  924.44  531.58 1145.36  531.45 1255.98  532.87
 1476.88  532.71  1604.6  533.97 1617.95  528.15 1624.89     520 1640.62  510.94
 1654.41  507.69 1665.88  508.05 1673.45   507.2 1700.87   507.8 1727.24  518.29
 1757.83  529.03 1801.99     530 1823.37  531.27 1879.73     550  1889.1     550
#Mann= 4 ,-1,0
       0      .1       0  612.26     .06       0  1604.6    .035       0
 1757.83     .06       0
#XS Ineff= 3 ,-1
       0   508.8     560   508.8  1604.6  533.97 1879.73  1889.1     560
Permanent Ineff=
       F       F       T
Bank Sta=1604.6,1757.83
XS Rating Curve= 0 ,0
Exp/Cntr=0.3,0.1

Type RM Length L Ch R = 1 ,260762.5,322.8,407.67,416.27
BEGIN DESCRIPTION:
Upstream of Sump 14W outfall.
Ineffective flow in LOB.
Effective flow in ROB set at Clear Fork Levee Loop.
END DESCRIPTION:
XS GIS Cut Line= 3
 2320324.1442064  6964284.866332 2319734.2228521  6962982.857814
 2319771.6847486 6962656.2413197
#Sta/Elev= 30
       0     552   94.12  552.57  204.02   549.8  219.85  546.88  291.01  544.03
  454.52  542.75  463.69  540.42  478.03  539.62   494.7  530.47  518.08  531.83
  521.45  529.61   523.9  530.99  538.53  530.87 1006.09  530.75 1166.02  532.87
 1385.67  532.46 1434.11  533.94    1442  528.11 1449.48     520 1458.62     514
 1484.34   508.4 1517.45   508.7 1536.74  511.21 1556.65  517.64 1571.74     520
 1599.48  529.77 1684.54     530 1694.93  531.89  1753.3     550 1758.18     550
#Mann= 4 ,-1,0
       0      .1       0  538.53     .06       0 1434.11    .035       0
 1599.48     .06       0
#XS Ineff= 3 ,-1
       0  464.15     560  464.15 1434.11  533.94  1753.3 1758.18     560
Permanent Ineff=
       F       F       T
Bank Sta=1434.11,1599.48
XS Rating Curve= 0 ,0
Exp/Cntr=0.3,0.1

Type RM Length L Ch R = 1 ,260354.8,287.75,321.73,317.81
BEGIN DESCRIPTION:
Ineffective flow in LOB.
Effective flow in ROB set at Clear Fork Levee Loop.
END DESCRIPTION:
XS GIS Cut Line= 3
 2320437.6515204 6964170.5596725 2320123.6780629 6963079.6691012
 2320188.5957775 6962738.9808341
#Sta/Elev= 30
       0  551.45   61.28  550.63  154.15   547.4   208.1  544.21  220.88  545.22
  227.57  545.01  232.74  543.99  317.98   543.9  341.92  541.69  354.63  538.63
  371.54  530.63  376.44  528.74  381.04  531.46  452.16     530  674.06  530.27
 1090.43  532.77 1138.96  533.97 1153.32  527.23 1159.76     520 1174.04  514.25
 1200.59  512.71 1259.89  512.87 1272.52     512 1280.42  509.76 1311.36  510.52
 1331.27     520  1345.2  525.28 1407.49  530.05 1471.84     552 1481.99     552
#Mann= 4 ,-1,0
       0      .1       0  371.54     .06       0 1138.96    .035       0
  1345.2     .06       0
#XS Ineff= 3 ,-1
       0  326.74     560  326.74 1138.96  533.97 1471.84 1481.99     560
Permanent Ineff=
       F       F       T
Bank Sta=1138.96,1345.2
XS Rating Curve= 0 ,0
Exp/Cntr=0.3,0.1

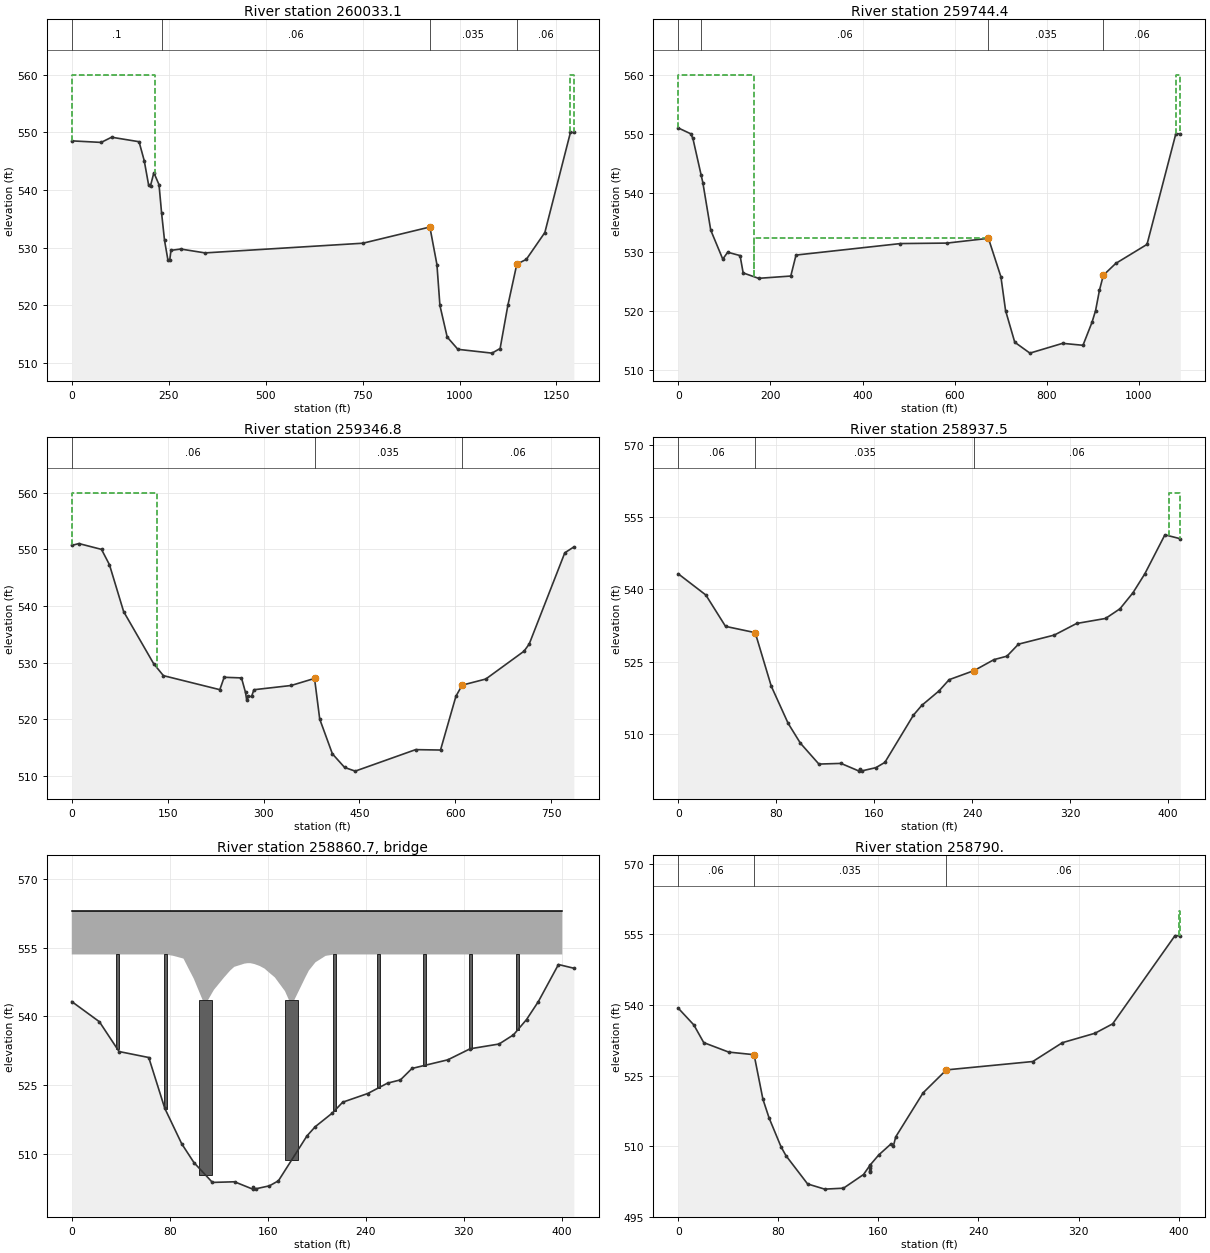
Type RM Length L Ch R = 1 ,260033.1,262.38,288.74,295.16
BEGIN DESCRIPTION:
Ineffective flow in LOB.
Effective flow in ROB set at Clear Fork Levee Loop.
END DESCRIPTION:
XS GIS Cut Line= 3
 2320613.0313618 6964060.5174419 2320440.6541865 6963149.8090074
  2320500.110269 6962786.6850086
#Sta/Elev= 30
       0  548.55   75.75  548.28  102.74  549.18  173.51   548.4  186.86  545.12
  198.28  540.85  203.14  540.79  211.74  543.03  225.02  540.95  231.65  536.04
   239.2   531.3  248.02  527.87  252.63  527.86  255.93  529.56  281.03  529.79
  343.72  529.12  750.83   530.8  923.54  533.61  941.72   527.1  949.45     520
  968.21  514.53  995.79   512.4 1083.73  511.74 1104.68  512.54  1124.6     520
 1147.79  527.17 1172.29     528 1220.04  532.65    1286     550 1294.84     550
#Mann= 4 ,-1,0
       0      .1       0  231.65     .06       0  923.54    .035       0
 1147.79     .06       0
#XS Ineff= 3 ,-1
       0  213.53     560  213.53  923.54  533.61    1286 1294.84     560
Permanent Ineff=
       F       F       T
Bank Sta=923.54,1147.79
XS Rating Curve= 0 ,0
Exp/Cntr=0.3,0.1

Type RM Length L Ch R = 1 ,259744.4,389,397.51,391.45
BEGIN DESCRIPTION:
Ineffective flow in LOB.
Effective flow in ROB set at Clear Fork Levee Loop.
END DESCRIPTION:
XS GIS Cut Line= 3
  2320806.283432 6963901.0039467 2320716.5096516  6963218.050371
 2320797.9280292 6962825.5200266
#Sta/Elev= 30
       0  550.99   27.02     550   31.78  549.22   49.69     543   53.45   541.7
   70.54  533.65   96.66  528.73  107.34   529.9  134.19  529.33  140.91  526.39
  174.34  525.47  244.29  525.86  255.63  529.42  482.36  531.37  583.28  531.45
  673.25  532.26  700.36  525.72  710.45     520  730.38  514.63  763.27  512.78
  834.21  514.44  878.47  514.11  897.99     518  905.82     520  914.21  523.45
   922.7     526  949.59     528 1017.44  531.23    1080     550 1089.71     550
#Mann= 4 ,-1,0
       0      .1       0   49.69     .06       0  673.25    .035       0
   922.7     .06       0
#XS Ineff= 3 ,-1
       0  164.16     560  164.16  673.25  532.25    1080 1089.71     560
Permanent Ineff=
       F       F       T
Bank Sta=673.25,922.7
XS Rating Curve= 0 ,0
Exp/Cntr=0.3,0.1

Type RM Length L Ch R = 1 ,259346.8,320.01,409.36,515.53
BEGIN DESCRIPTION:
Ineffective flow in LOB.
Effective flow in ROB set at Clear Fork Levee Loop.
END DESCRIPTION:
XS GIS Cut Line= 3
 2321154.1322321 6963660.0436832 2321112.0364395  6963287.725656
 2321180.8620797 6962882.9181122
#Sta/Elev= 30
       0   550.7   11.15  551.03   46.51     550   58.91   547.3   81.14     539
  128.04   529.8  143.32  527.68  231.57   525.2  238.35  527.39  265.47  527.28
  271.76  524.71  273.65  523.32  276.42     524  281.26     524  284.89  525.19
   343.2  525.94  379.72  527.19  387.83     520  407.63  513.86  426.76  511.45
  443.34   510.8  537.87   514.6  576.76  514.53   600.9  524.05  610.65     526
  647.58  527.08  707.36     532  715.45  533.26  771.18   549.4  785.31  550.43
#Mann= 3 ,0,0
       0     .06       0  379.72    .035       0  610.65     .06       0
#XS Ineff= 2 ,-1
       0  133.44     560  133.44  379.72  527.19
Permanent Ineff=
       F       F
Bank Sta=379.72,610.65
XS Rating Curve= 0 ,0
Exp/Cntr=0.3,0.1

Type RM Length L Ch R = 1 ,258937.5,144.07,147.49,141.82
BEGIN DESCRIPTION:
Upstream of Henderson Street.
At Sump 15W outfall.
Cross-section skewed.
END DESCRIPTION:
XS GIS Cut Line= 2
 2321405.9893139 6963343.5993329 2321774.1922547 6962995.5554282
#Sta/Elev= 30
       0  543.24   22.55  538.85   38.62  532.36   62.85  531.06   75.93     520
   89.75  512.28   99.75  508.18  114.84  503.86  132.87     504  147.74   502.4
  148.14   502.9  150.06  502.46  161.39  503.12   168.7  504.21  192.05     514
   198.8     516  212.84  518.99  221.18  521.33  241.64  523.22  257.79  525.48
  268.34  526.19  277.78  528.68  307.03  530.56  325.22  532.96  348.87     534
  360.63     536  371.28  539.33  380.93  543.24  397.33  551.31   409.9   550.5
#Mann= 3 ,-1,0
       0     .06       0   62.85    .035       0  241.64     .06       0
#XS Ineff= 2 , 0
       0                  400.42       0     560
Permanent Ineff=
       F       T
Bank Sta=62.85,241.64
XS Rating Curve= 0 ,0
Skew Angle= 36
Exp/Cntr=0.5,0.3

Type RM Length L Ch R = 3 ,258860.7,,,
BEGIN DESCRIPTION:
Henderson Street/Jacksboro Highway
Data from USACE survey, USACE 1975 survey, bridge plans.
Note:  Internal bridge cross-sections modified to represent geometry under bridge.
Bridge skewed.
END DESCRIPTION:
Node Name=Henderson Street
Bridge Culvert--1,0,-1,-1, 0
Deck Dist Width WeirC Skew NumUp NumDn MinLoCord MaxHiCord MaxSubmerge Is_Ogee
43.3,67,2.6,34, 29, 29, , , 0.95, 0, 0,0,,
       0  76.271  82.904  91.194  96.168  99.485 106.946 111.091 116.065 124.356
  129.33 132.646 140.936 143.423 145.911 149.227 153.372 157.517 159.175 165.808
 174.098 177.414 181.559 190.679  193.58 198.969 207.259 214.721 400.425
     563     563     563     563     563     563     563     563     563     563
     563     563     563     563     563     563     563     563     563     563
     563     563     563     563     563     563     563     563     563
   553.5   553.5   553.2   552.6     550   548.3   543.5   543.5   545.8   548.5
     550   550.8   551.5   551.6   551.6   551.4     551   550.4     550   548.5
   545.5   543.5   543.5   548.5     550   551.8   553.2   553.5   553.5
       0  76.271  82.904  91.194  96.168  99.485 106.946 111.091 116.065 124.356
  129.33 132.646 140.936 143.423 145.911 149.227 153.372 157.517 159.175 165.808
 174.098 177.414 181.559 190.679  193.58 198.969 207.259 214.721 400.425
     563     563     563     563     563     563     563     563     563     563
     563     563     563     563     563     563     563     563     563     563
     563     563     563     563     563     563     563     563     563
   553.5   553.5   553.2   552.6     550   548.3   543.5   543.5   545.8   548.5
     550   550.8   551.5   551.6   551.6   551.4     551   550.4     550   548.5
   545.5   543.5   543.5   548.5     550   551.8   553.2   553.5   553.5
Pier Skew, UpSta & Num, DnSta & Num=  ,37.307, 2 ,37.307, 2 , 0 , 0 , 0 ,,
     2.5     2.5
     450     556
     2.5     2.5
     450     556
Pier Skew, UpSta & Num, DnSta & Num=  ,76.271, 2 ,76.271, 2 , 0 , 0 , 0 ,,
     2.5     2.5
     450     556
     2.5     2.5
     450     556
Pier Skew, UpSta & Num, DnSta & Num=  ,109.018, 4 ,109.018, 4 , 0 , 0 , 0 ,,
      11      11       7       5
     450     514     514   543.5
      11      11       7       5
     450     514     514   543.5
Pier Skew, UpSta & Num, DnSta & Num=  ,179.487, 4 ,179.487, 4 , 0 , 0 , 0 ,,
      11      11       7       5
     450     514     514   543.5
      11      11       7       5
     450     514     514   543.5
Pier Skew, UpSta & Num, DnSta & Num=  ,214.721, 2 ,214.721, 2 , 0 , 0 , 0 ,,
     2.5     2.5
     450     556
     2.5     2.5
     450     556
Pier Skew, UpSta & Num, DnSta & Num=  ,250.369, 2 ,250.369, 2 , 0 , 0 , 0 ,,
     2.5     2.5
     450     556
     2.5     2.5
     450     556
Pier Skew, UpSta & Num, DnSta & Num=  ,287.676, 2 ,287.676, 2 , 0 , 0 , 0 ,,
     2.5     2.5
     450     556
     2.5     2.5
     450     556
Pier Skew, UpSta & Num, DnSta & Num=  ,325.812, 2 ,325.812, 2 , 0 , 0 , 0 ,,
     2.5     2.5
     450     556
     2.5     2.5
     450     556
Pier Skew, UpSta & Num, DnSta & Num=  ,363.947, 2 ,363.947, 2 , 0 , 0 , 0 ,,
     2.5     2.5
     450     556
     2.5     2.5
     450     556
BR Coef=-1 , 0 , 0 ,, 0 ,,,0.8,-1,,0,
WSPro=,,,, 1 ,,,, 0 ,,,, 0 ,,,,-1 ,-1 ,-1 , 0 , 0 , 0 , 0 , 0
BR U #Sta/Elev= 270
       0  556.55    .166  556.54   1.567  556.57   9.982  550.87  20.403  543.81
  25.269  540.27  26.836  539.15  32.258  535.73  37.199  532.13  37.373     532
  42.629  531.73  45.365  531.63  48.789  531.47   54.65  531.28  55.819  531.24
  59.475  531.12  63.363  529.07  63.554  528.96  63.761  528.83  63.993  528.69
  64.259  528.53  70.452  525.18  70.966  524.85  71.546  524.49  72.193  524.08
   72.93  523.62  73.776  523.09  79.297  520.07  80.151  519.49  81.105  518.85
  82.182  518.13  83.393  517.31  84.777  516.39  86.361  515.32  87.687  514.57
  88.906  513.68    90.1   512.8  90.307  512.72  90.332  512.71  92.065     512
  92.255  511.92  93.839  511.28  94.204  511.13  95.638  510.54  96.185  510.32
  97.462  509.79  98.191   509.5   99.31  509.04 100.222  508.66 101.184  508.27
 102.278  507.82 103.074  507.49 104.368  506.97 104.998  506.71 106.473   506.1
 106.938  505.91 108.621  505.22 108.911   505.1 110.784  504.33   110.9  504.28
 112.194  503.75 112.873  503.69 112.882  503.68  112.89  503.68 112.907  503.68
 114.739  503.51 114.764  503.51  114.83  503.51 114.871  503.51 116.571  503.35
 116.728  503.32 116.762  503.32 116.886  503.31 118.478  503.16 118.677  503.15
 118.751  503.14 118.867  503.14 118.925  503.15 120.409  503.02 120.467  503.02
 120.617  502.98 120.766  502.97 120.915  503.01 122.275   502.9 122.449  502.95
 122.631  502.88 122.805   502.8 122.996  502.78  124.24  502.67 124.439   502.7
 124.662  502.68 124.886  502.67 126.005  502.57 126.113  502.52 126.354   502.5
 126.478  502.49 126.851  502.47 127.846  502.38 128.119  502.41 128.526  502.33
 128.675  502.27 128.932  502.25 129.811  502.18 130.159  502.32 130.457  502.25
 130.789  502.22 131.112  502.26 131.867   502.2 132.173  502.19 132.563  502.16
  132.92  502.14 133.558  502.09 133.931  502.07 134.304  502.05 134.644  502.03
 134.893  502.01 135.415  501.97 136.012  502.02 139.917  501.82  140.24  501.72
 140.472   501.7 140.696  501.77 140.928  501.76 141.185  501.74 141.426  501.73
 141.691  501.71 141.956  501.79 142.089  501.87 142.379  501.77  142.52  501.76
  142.81  501.84 143.108  501.83 143.432  501.81 143.656  501.73 143.664   501.7
  144.07  501.78 144.112  501.79 144.667   501.8 145.189   502.1 145.645  502.19
 146.209   502.3 146.441  502.34  146.69   502.4 147.196   502.5 147.693  502.69
 148.149  502.69 148.597  502.87 149.036  502.95 149.517  503.07 149.948  503.15
 150.387  503.39 150.802  503.47 151.183  503.55 151.863   503.7 152.278  503.78
 152.477  503.82 153.024  503.93 153.389  504.13 154.276  504.34 154.798   504.5
 155.304  504.54 155.453  504.56 155.768  504.68  155.95  504.72 157.061  504.97
 157.268  505.01 157.476   505.1 157.758  505.16 158.031  505.21 158.288  505.26
 159.615  505.56  159.83  505.65  160.22  505.76 160.319  505.78 160.543  505.86
 162.093  506.21 162.292  506.35 162.458  506.41 162.665  506.41 162.922  506.46
 164.697  506.84 164.912   506.9 165.028  506.92 165.111  506.94 165.244  506.96
  165.36  506.98 167.341  507.41 167.432  507.42 167.515  507.46 167.557  507.46
 167.598  507.47 167.681  507.48 169.895  507.96 169.936  507.97 169.969  507.98
 170.002  507.99 170.036  507.99 170.069     508 171.702  508.35 172.465   508.7
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BR U #Mann= 3
       0    .035  59.475    .035 222.464    .035
BR U Banks=59.475,222.464
BR D #Sta/Elev= 270
       0  556.55    .166  556.54   1.567  556.57   9.982  550.87  20.403  543.81
  25.269  540.27  26.836  539.15  32.258  535.73  37.199  532.13  37.373     532
  42.629  531.73  45.365  531.63  48.789  531.47   54.65  531.28  55.819  531.24
  59.475  531.12  63.363  529.07  63.554  528.96  63.761  528.83  63.993  528.69
  64.259  528.53  70.452  525.18  70.966  524.85  71.546  524.49  72.193  524.08
   72.93  523.62  73.776  523.09  79.297  520.07  80.151  519.49  81.105  518.85
  82.182  518.13  83.393  517.31  84.777  516.39  86.361  515.32  87.687  514.57
  88.906  513.68    90.1   512.8  90.307  512.72  90.332  512.71  92.065     512
  92.255  511.92  93.839  511.28  94.204  511.13  95.638  510.54  96.185  510.32
  97.462  509.79  98.191   509.5   99.31  509.04 100.222  508.66 101.184  508.27
 102.278  507.82 103.074  507.49 104.368  506.97 104.998  506.71 106.473   506.1
 106.938  505.91 108.621  505.22 108.911   505.1 110.784  504.33   110.9  504.28
 112.194  503.75 112.873  503.69 112.882  503.68  112.89  503.68 112.907  503.68
 114.739  503.51 114.764  503.51  114.83  503.51 114.871  503.51 116.571  503.35
 116.728  503.32 116.762  503.32 116.886  503.31 118.478  503.16 118.677  503.15
 118.751  503.14 118.867  503.14 118.925  503.15 120.409  503.02 120.467  503.02
 120.617  502.98 120.766  502.97 120.915  503.01 122.275   502.9 122.449  502.95
 122.631  502.88 122.805   502.8 122.996  502.78  124.24  502.67 124.439   502.7
 124.662  502.68 124.886  502.67 126.005  502.57 126.113  502.52 126.354   502.5
 126.478  502.49 126.851  502.47 127.846  502.38 128.119  502.41 128.526  502.33
 128.675  502.27 128.932  502.25 129.811  502.18 130.159  502.32 130.457  502.25
 130.789  502.22 131.112  502.26 131.867   502.2 132.173  502.19 132.563  502.16
  132.92  502.14 133.558  502.09 133.931  502.07 134.304  502.05 134.644  502.03
 134.893  502.01 135.415  501.97 136.012  502.02 139.917  501.82  140.24  501.72
 140.472   501.7 140.696  501.77 140.928  501.76 141.185  501.74 141.426  501.73
 141.691  501.71 141.956  501.79 142.089  501.87 142.379  501.77  142.52  501.76
  142.81  501.84 143.108  501.83 143.432  501.81 143.656  501.73 143.664   501.7
  144.07  501.78 144.112  501.79 144.667   501.8 145.189   502.1 145.645  502.19
 146.209   502.3 146.441  502.34  146.69   502.4 147.196   502.5 147.693  502.69
 148.149  502.69 148.597  502.87 149.036  502.95 149.517  503.07 149.948  503.15
 150.387  503.39 150.802  503.47 151.183  503.55 151.863   503.7 152.278  503.78
 152.477  503.82 153.024  503.93 153.389  504.13 154.276  504.34 154.798   504.5
 155.304  504.54 155.453  504.56 155.768  504.68  155.95  504.72 157.061  504.97
 157.268  505.01 157.476   505.1 157.758  505.16 158.031  505.21 158.288  505.26
 159.615  505.56  159.83  505.65  160.22  505.76 160.319  505.78 160.543  505.86
 162.093  506.21 162.292  506.35 162.458  506.41 162.665  506.41 162.922  506.46
 164.697  506.84 164.912   506.9 165.028  506.92 165.111  506.94 165.244  506.96
  165.36  506.98 167.341  507.41 167.432  507.42 167.515  507.46 167.557  507.46
 167.598  507.47 167.681  507.48 169.895  507.96 169.936  507.97 169.969  507.98
 170.002  507.99 170.036  507.99 170.069     508 171.702  508.35 172.465   508.7
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BR D #Mann= 3
       0    .035  59.475    .035 222.464    .035
BR D Banks=59.475,222.464
BC Design=,, 0 ,, 0 ,,,,,,
BC Use User HTab Curves=0
BC User HTab FreeFlow(D)= 0

Type RM Length L Ch R = 1 ,258790. ,301.08,221.91,132.49
BEGIN DESCRIPTION:
Downstream of Henderson Street.
Cross-section skewed.
END DESCRIPTION:
XS GIS Cut Line= 2
 2321554.2004844 6963362.6972852 2321935.8802911  6963003.735172
#Sta/Elev= 30
       0  539.33   12.47  535.77    20.4  532.01   40.35     530   60.64  529.45
   67.69     520   72.65     516   82.21  509.87   86.14     508  103.43     502
  117.07   500.9   132.1   501.1  148.12     504  153.14  505.91  153.15   504.8
  153.24  504.54  153.26  505.29  153.37     506  160.29  508.16  169.84  510.44
  171.99  510.04  173.87     512  195.79  521.36  214.35  526.22  283.44     528
  307.09     532  333.14     534  347.29     536  397.15  554.74  401.38  554.67
#Mann= 3 ,-1,0
       0     .06       0   60.64    .035       0  214.35     .06       0
#XS Ineff= 2 , 0
       0                  400.42       0     560
Permanent Ineff=
       F       T
Bank Sta=60.64,214.35
XS Rating Curve= 0 ,0
Skew Angle= 40
Exp/Cntr=0.5,0.3