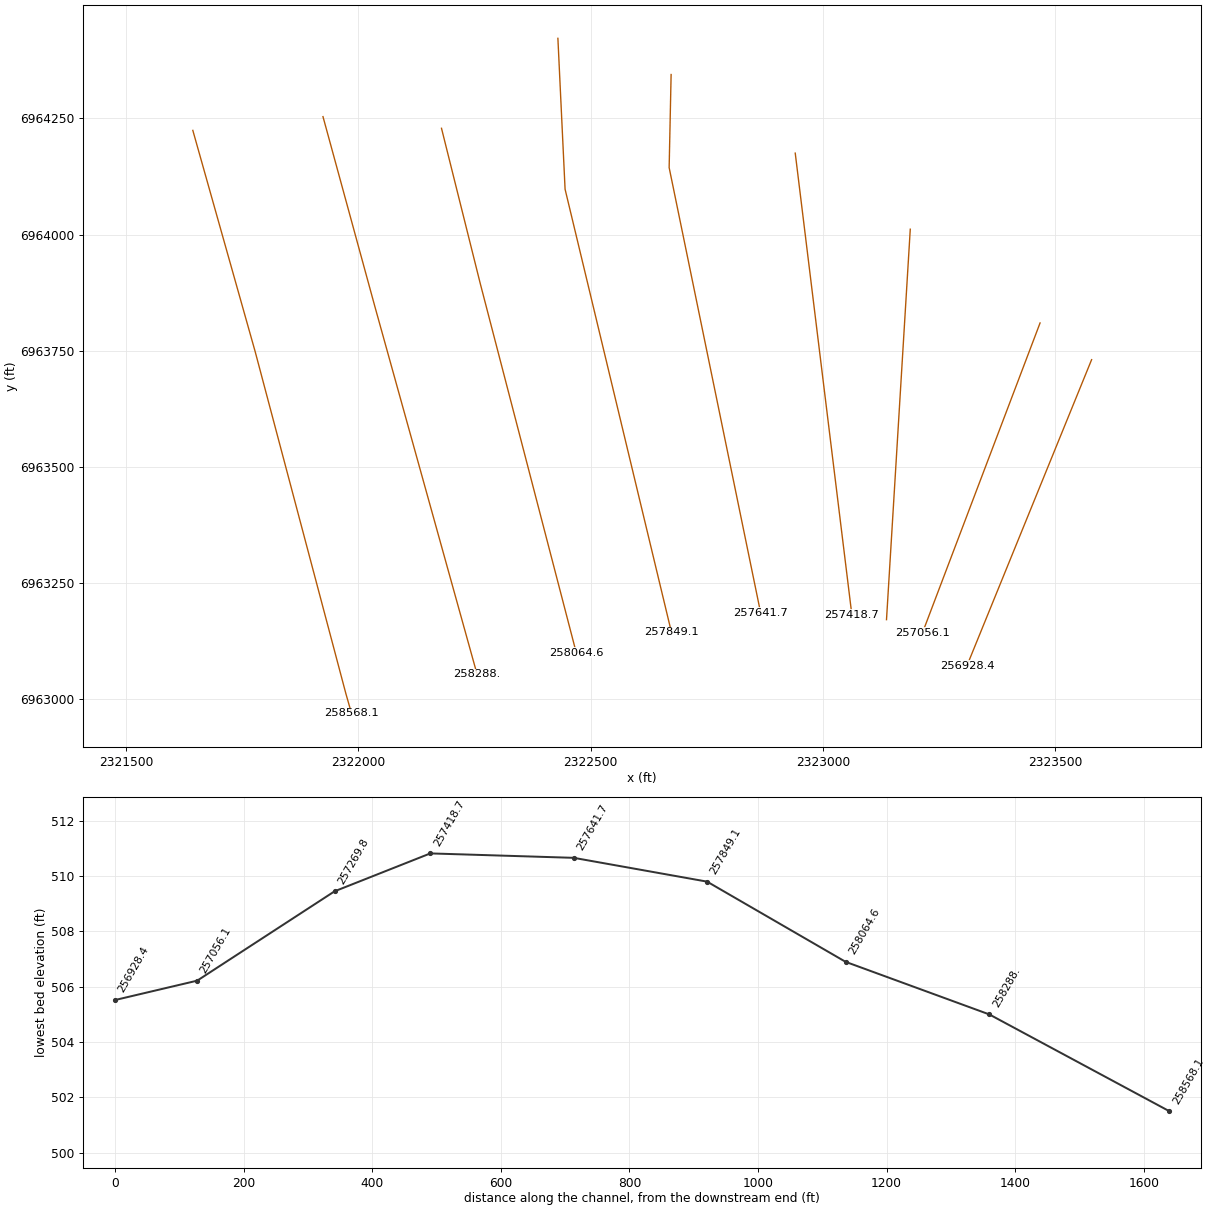
HEC-RAS study CDC_Consolidated_Model.prj: Upper Trinity CDC Consolidated Model

--- CDC_Consolidated_Model.g11 (geometry) --- (continued)

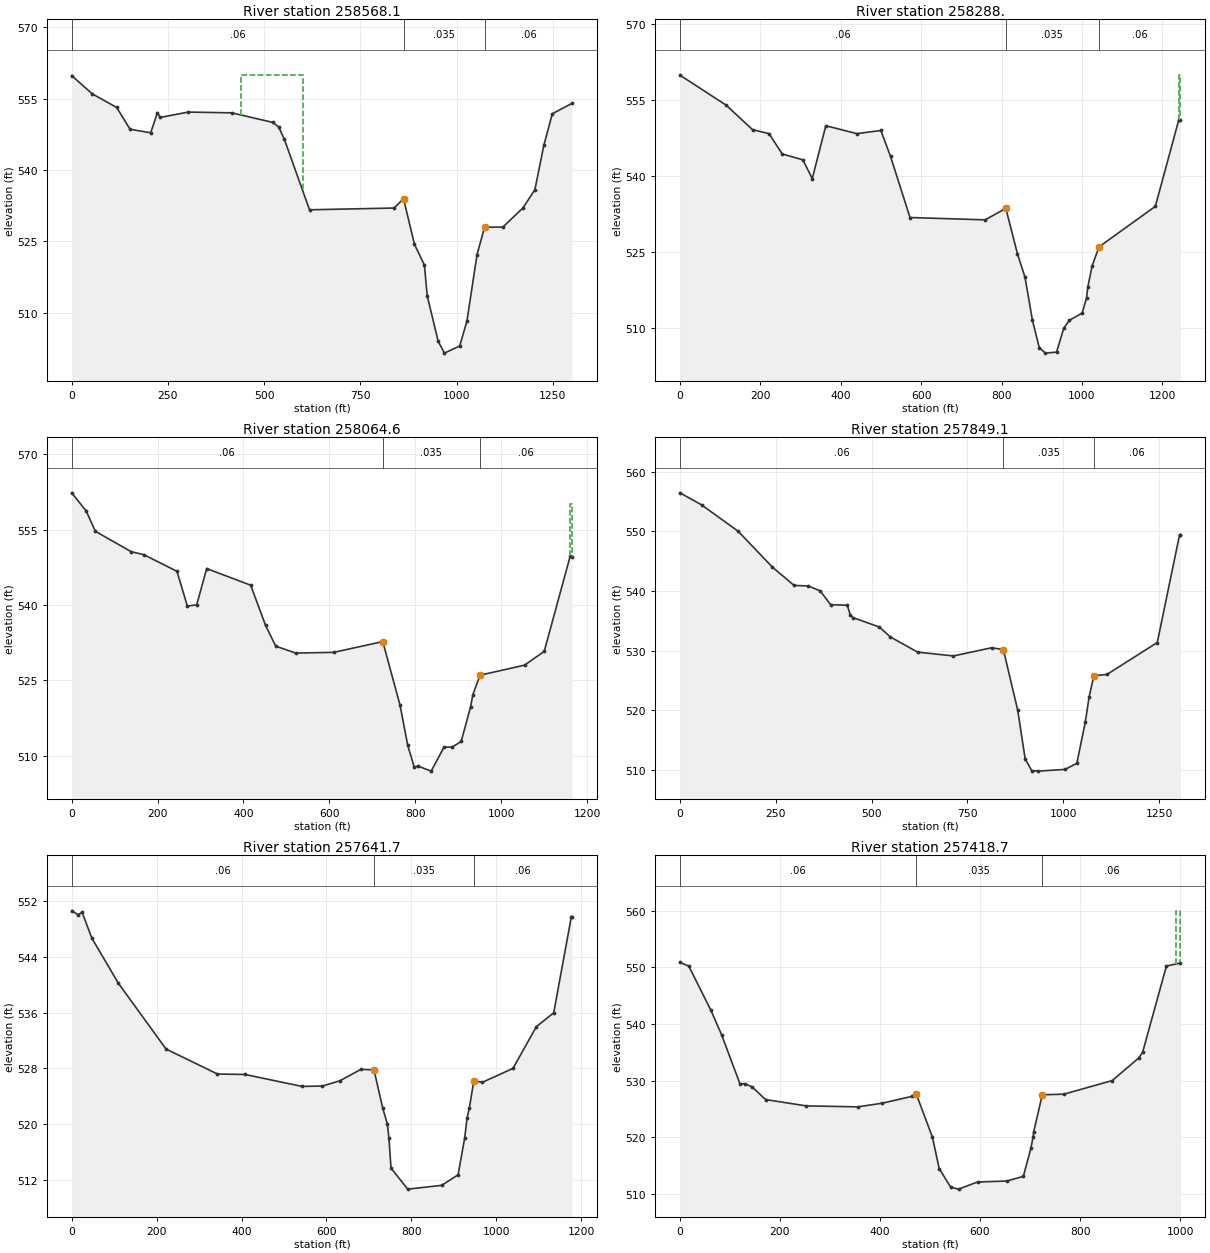
Type RM Length L Ch R = 1 ,258568.1,278.42,280.08,281.91
BEGIN DESCRIPTION:
Effective flow in ROB set at Clear Fork Levee Loop.
Ineffective flow in LOB due to Henderson Street.
Oakwood Cemetery in LOB.
END DESCRIPTION:
XS GIS Cut Line= 4
 2321643.8179219 6964224.2531043 2321777.9794876 6963748.1522685
 2321973.1695103 6963012.1898772 2321985.3248505 6962969.6643359
#Sta/Elev= 30
       0  559.84    53.4     556  116.95  553.14  151.71  548.55  205.25  547.82
  222.83  552.06  229.61  551.04  303.08  552.17  416.16  552.01  522.73  549.99
   537.9  549.02   552.5  546.46  617.94  531.63  837.73     532  862.16  533.97
  890.54  524.39  916.41     520  923.81  513.52  952.21     504  968.46   501.5
 1008.18  503.01 1027.02  508.27 1053.21  522.23 1072.79  527.97 1120.33     528
 1172.31     532 1203.48  535.85 1226.71  545.17  1248.8  551.82 1300.28  554.02
#Mann= 3 ,0,0
       0     .06       0  862.16    .035       0 1072.79     .06       0
#XS Ineff= 1 ,-1
     440     600     560
Permanent Ineff=
       F
Bank Sta=862.16,1072.79
XS Rating Curve= 0 ,0
Exp/Cntr=0.3,0.1

Type RM Length L Ch R = 1 ,258288. ,226.43,223.43,221.07
BEGIN DESCRIPTION:
Effective flow in ROB set at Clear Fork Levee Loop.
Oakwood Cemetery in LOB.
END DESCRIPTION:
XS GIS Cut Line= 3
 2321923.9103327  6964253.856499 2322035.6885404 6963844.7919156
 2322255.4714645 6963054.0792867
#Sta/Elev= 30
       0  559.94  114.98     554   180.6  549.16  221.49  548.38  254.43  544.36
  305.83   543.2  329.05  539.49  362.86  549.94  439.94  548.38  499.74     549
  523.72  543.89  572.28   531.8  759.25  531.34  810.58  533.61  839.44  524.63
  858.27     520  876.77  511.49   893.7  506.08  909.17     505  936.78   505.2
  954.87  509.96  968.87   511.5 1000.35  512.91  1011.3   515.9  1014.3     518
 1025.21  522.25 1042.36     526 1182.42     534 1240.89  551.14 1244.75  551.07
#Mann= 3 ,0,0
       0     .06       0  810.58    .035       0 1042.36     .06       0
#XS Ineff= 2 , 0
       0                 1240.89       0     560
Permanent Ineff=
       F       T
Bank Sta=810.58,1042.36
XS Rating Curve= 0 ,0
Exp/Cntr=0.3,0.1

Type RM Length L Ch R = 1 ,258064.6,219.42,215.49,212.82
BEGIN DESCRIPTION:
Effective flow in ROB set at Clear Fork Levee Loop.
Oakwood Cemetery in LOB.
END DESCRIPTION:
XS GIS Cut Line= 3
 2322178.9536475 6964228.8076622 2322262.4556903 6963894.3159428
 2322468.9936702 6963100.1270816
#Sta/Elev= 30
       0  562.31   33.66  558.71   55.09  554.66  138.56  550.59  167.91     550
   245.2  546.68  269.31  539.77  291.09     540  314.31  547.23  416.71  543.92
  451.53   535.9  475.15  531.78  522.05   530.4  610.11  530.55   724.4  532.69
  764.68     520  782.55  512.02   797.9  507.63  805.84  507.92  837.04   506.9
  867.02  511.67  886.07   511.7  906.96   512.8  928.75  519.66  934.25  522.15
  950.93     526 1054.43     528 1100.31  530.73  1160.6  549.64 1165.36  549.63
#Mann= 3 ,0,0
       0     .06       0   724.4    .035       0  950.93     .06       0
#XS Ineff= 2 , 0
       0                  1160.6       0     560
Permanent Ineff=
       F       T
Bank Sta=724.4,950.93
XS Rating Curve= 0 ,0
Exp/Cntr=0.3,0.1

Type RM Length L Ch R = 1 ,257849.1,214.57,207.35,201.99
BEGIN DESCRIPTION:
Effective flow in ROB set at Clear Fork Levee Loop.
Oakwood Cemetery in LOB.
END DESCRIPTION:
XS GIS Cut Line= 3
  2322429.442923 6964422.3671031 2322444.9119299 6964097.6241314
 2322673.7871168 6963144.2925385
#Sta/Elev= 30
       0  556.43   56.32  554.42  151.75     550  240.97     544  297.87  540.91
  334.59  540.83  365.89     540   393.1  537.69  436.59   537.6  444.26     536
  450.67  535.54  520.09  533.95  548.98  532.28  619.98  529.74  713.54   529.1
  812.82  530.47  843.71  530.17  881.17     520  900.52  511.87  917.65  509.89
  933.89   509.8 1004.77  510.09  1035.4  511.11 1057.41     518 1067.23  522.16
 1079.78  525.79 1113.97     526 1245.24  531.35 1303.48  549.42 1305.53  549.43
#Mann= 3 ,0,0
       0     .06       0  843.71    .035       0 1079.78     .06       0
Bank Sta=843.71,1079.78
XS Rating Curve= 0 ,0
Exp/Cntr=0.3,0.1

Type RM Length L Ch R = 1 ,257641.7,239.25,223.03,207.58
BEGIN DESCRIPTION:
Effective flow in ROB set at Clear Fork Levee Loop.
END DESCRIPTION:
XS GIS Cut Line= 3
 2322673.1006857 6964344.4880913 2322668.8676291 6964144.1627343
 2322865.8317424 6963185.7086412
#Sta/Elev= 30
       0  550.62   15.45  550.05   24.59  550.41   47.52  546.69   109.9  540.23
  222.33  530.77  343.31  527.19  408.61  527.12  542.17  525.41  590.78  525.46
  631.36  526.21  681.46  527.86  712.07  527.78  732.74  522.26  743.62     520
  747.27     518  752.22  513.67   791.6  510.66   871.4   511.2  910.12  512.71
   925.7     518  931.41  520.89   936.7  522.31  947.22   526.2  967.59     526
  1039.5     528 1094.71     534 1135.42  535.97 1176.96  549.76 1178.85  549.75
#Mann= 3 ,0,0
       0     .06       0  712.07    .035       0  947.22     .06       0
#XS Ineff= 2 , 0
       0  712.07  527.78               0
Permanent Ineff=
       F       F
Bank Sta=712.07,947.22
XS Rating Curve= 0 ,0
Exp/Cntr=0.3,0.1

Type RM Length L Ch R = 1 ,257418.7,184.72,148.92,110.54
BEGIN DESCRIPTION:
Effective flow in LOB set at North Main Levee.
Effective flow in ROB set at Clear Fork Levee Loop.
END DESCRIPTION:
XS GIS Cut Line= 2
  2322940.201205 6964175.3792096 2323062.0031217 6963182.2689667
#Sta/Elev= 30
       0  550.88   17.73  550.23   61.92  542.42   83.23  538.11  120.45  529.33
  129.08  529.47  144.54  528.87  171.17  526.65  252.48  525.53  355.41  525.36
  404.25     526  464.25  527.22  472.35  527.65  504.83     520  518.29  514.46
  541.28  511.17  556.93  510.82  594.95  512.08  653.25  512.25  686.53  513.07
  701.52     518  706.03     520   707.1  520.88  724.41  527.49  767.64   527.6
  864.13     530  917.33     534  925.04  535.01   972.6  550.24 1000.55  550.78
#Mann= 3 ,0,0
       0     .06       0  472.35    .035       0  724.41     .06       0
#XS Ineff= 2 , 0
       0  472.35  527.65  991.84       0     560
Permanent Ineff=
       F       T
Bank Sta=472.35,724.41
XS Rating Curve= 0 ,0
Exp/Cntr=0.3,0.1

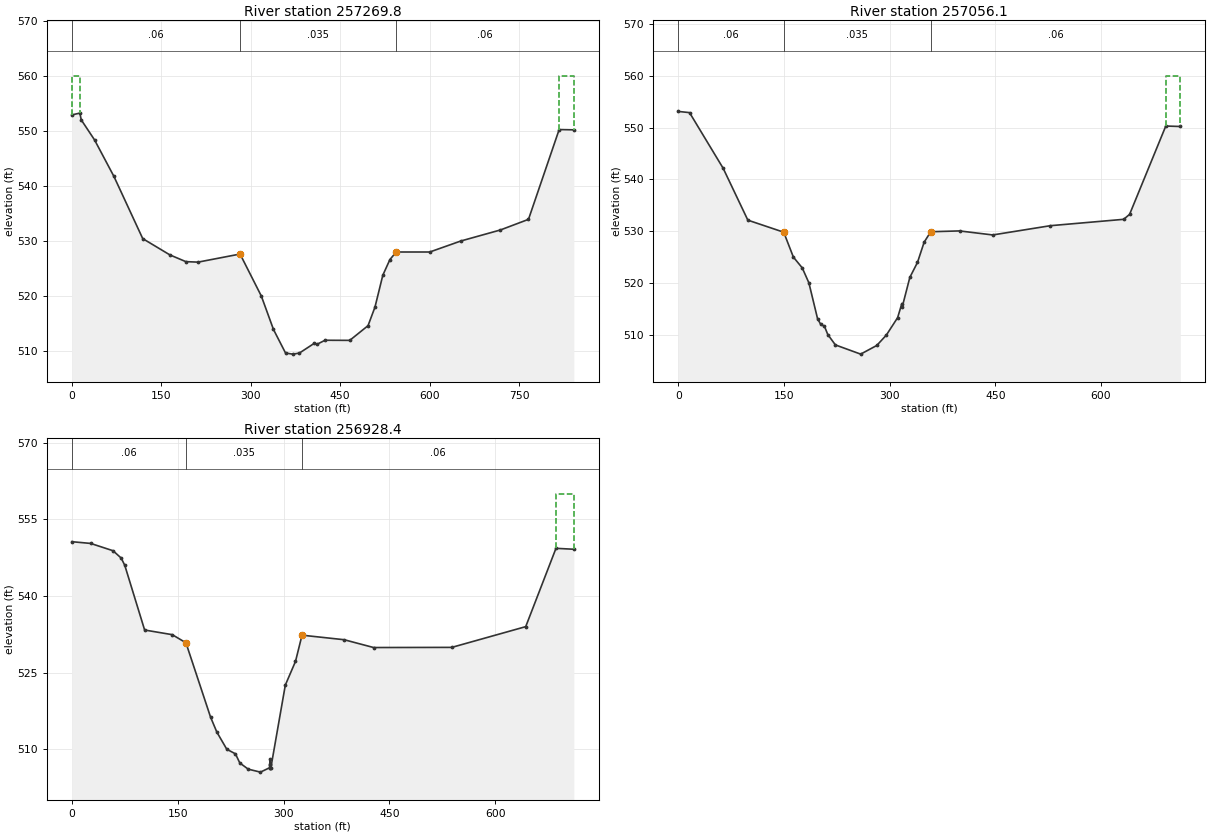
Type RM Length L Ch R = 1 ,257269.8,268.01,213.66,144.96
BEGIN DESCRIPTION:
Effective flow in LOB set at North Main Levee.
Effective flow in ROB set at Clear Fork Levee Loop.
END DESCRIPTION:
XS GIS Cut Line= 2
 2323187.7692267 6964011.6090637 2323136.6185069 6963171.3536102
#Sta/Elev= 30
       0   552.9   13.55  553.23   15.89     552   38.14  548.37   70.68  541.73
  118.99  530.43  164.57  527.47  191.26  526.25   211.7  526.16  282.17  527.63
  317.83     520  338.18  513.93  358.42  509.65  370.51  509.45   381.6  509.64
  406.29  511.39  410.85  511.22  424.66  511.97   466.1  511.95  496.75  514.62
   508.4     518  521.52  523.78  533.43  526.63  544.01     528  600.24     528
  652.39     530  718.62     532  765.77  533.93  817.18  550.24  841.81  550.19
#Mann= 3 ,-1,0
       0     .06       0  282.17    .035       0  544.01     .06       0
#XS Ineff= 3 ,-1
       0   13.55     560   13.55  282.17  527.63  817.18  841.81     560
Permanent Ineff=
       T       F       T
Bank Sta=282.17,544.01
XS Rating Curve= 0 ,0
Exp/Cntr=0.3,0.1

Type RM Length L Ch R = 1 ,257056.1,135.12,127.74,122.55
BEGIN DESCRIPTION:
Effective flow in LOB set at North Main Levee.
Effective flow in ROB set at Clear Fork Levee Loop.
END DESCRIPTION:
XS GIS Cut Line= 2
 2323467.0931459 6963809.8422661   2323214.26093 6963143.7015207
#Sta/Elev= 30
       0  553.12   16.04  552.89   63.77  542.13   98.79  532.11  149.71  529.78
   163.4  524.97  175.96  522.89   185.4     520  197.77  513.04  202.11     512
  207.51   511.6  212.25     510  223.03     508  258.89  506.22  281.72  507.89
  295.33   509.9  311.35  513.27  317.37     516   317.9  515.35  328.68  521.05
  339.51  523.94  348.99  527.86  358.35  529.87  399.15  530.03  446.29  529.25
  528.13  531.04  632.12  532.27  640.54  533.23  691.91   550.3  712.51  550.21
#Mann= 3 ,-1,0
       0     .06       0  149.71    .035       0  358.35     .06       0
#XS Ineff= 2 , 0
       0                  691.91       0     560
Permanent Ineff=
       F       T
Bank Sta=149.71,358.35
XS Rating Curve= 0 ,0
Exp/Cntr=0.3,0.1

Type RM Length L Ch R = 1 ,256928.4,41.75,41.65,41.02
BEGIN DESCRIPTION:
Upstream of the Fort Worth and Western Railroad.
Effective flow in LOB set at North Main Levee.
Effective flow in ROB set at Clear Fork Levee Loop.
END DESCRIPTION:
XS GIS Cut Line= 2
 2323578.0293574 6963730.8911514 2323309.8003428 6963072.3353724
#Sta/Elev= 30
       0  550.63   26.82  550.29   58.41  548.86   69.96  547.43   75.08     546
  103.19  533.34  142.29  532.43   161.7  530.84  196.51  516.31  205.49  513.35
  219.56     510  231.82   509.1  238.01  507.31  249.93   506.1  267.21  505.52
  280.18  506.38  280.58  507.08  280.63     508  280.68  506.96  281.08  506.35
   281.9  506.32  302.46  522.56  316.86  527.19  326.11  532.33  385.77  531.44
   427.5  529.91  538.26  529.94  642.93     534  685.78  549.33  711.09  549.15
#Mann= 3 ,-1,0
       0     .06       0   161.7    .035       0  326.11     .06       0
#XS Ineff= 2 , 0
       0                  685.78       0     560
Permanent Ineff=
       F       T
Bank Sta=161.7,326.11
XS Rating Curve= 0 ,0
Exp/Cntr=0.5,0.3