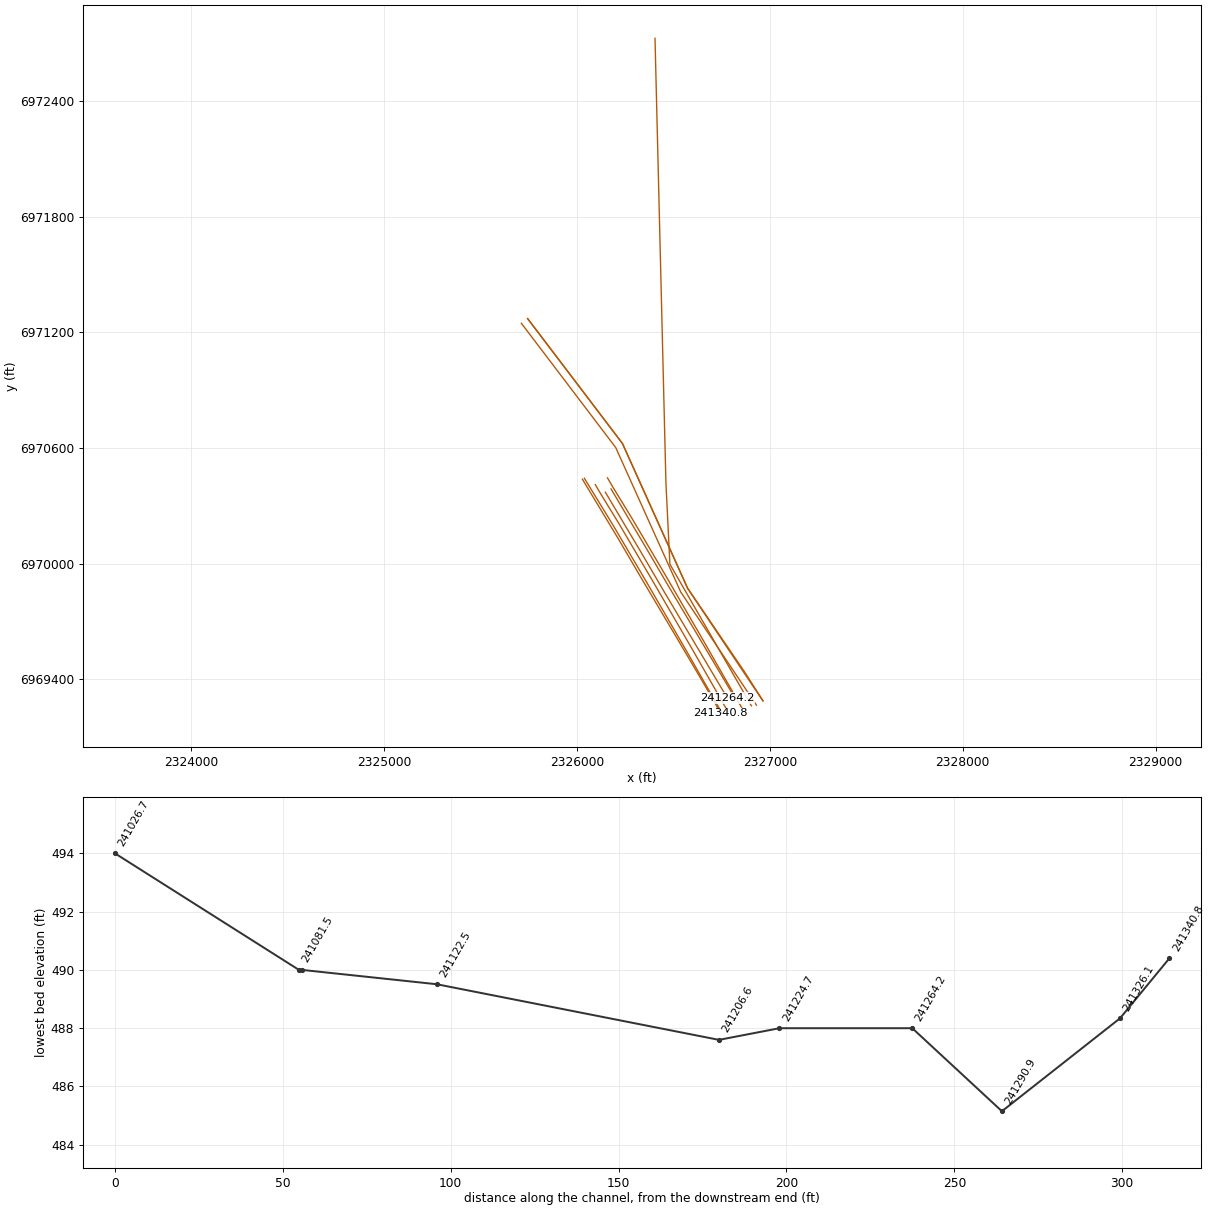
HEC-RAS study CDC_Consolidated_Model.prj: Upper Trinity CDC Consolidated Model

--- CDC_Consolidated_Model.g11 (geometry) --- (continued)

Type RM Length L Ch R = 3 ,241352.2,,,
BEGIN DESCRIPTION:
Burlington Northern Railroad
Two bridges: West Fork channel bridge, and ROB relief bridge.  West Fork bridge: data from 1975 USACE field survey, Fort Worth Floodway as-built plans, low chord elev. 533.1, total bridge length 640 feet.
Relief bridge: Structure designed by EA Inc. in 1995. Minimum low chord elev. 534.24, bridge length 353 feet.
Note: Internal bridge cross-sections modified to represent channel geometry under bridges.
END DESCRIPTION:
Node Name=BNSF Railroad
Bridge Culvert--1,0,-1,-1, 0
Deck Dist Width WeirC Skew NumUp NumDn MinLoCord MaxHiCord MaxSubmerge Is_Ogee
3.5,16,2.6,0, 13, 13, , , 0.95, 0, 0,0,,
       0      65      65     342     342     640     640  643.92  793.75  793.75
 1166.83 1166.83  1399.5
     542     542     542     542     542     542     542     542     541     541
     540     540  537.04
   533.2   533.2  535.09  535.09     533     533     533                  535.23
  534.34
       0      65      65     342     342     640     640  643.92  793.75  793.75
 1166.83 1166.83 1410.23
     542     542     542     542     542     542     542     542     541     541
     540     540  537.04
   533.2   533.2  535.09  535.09     533     533     533                  535.23
  534.34
Pier Skew, UpSta & Num, DnSta & Num=  ,60, 2 ,60, 2 , 0 , 0 , 0 ,,
       9       8
     450     540
       9       8
     450     540
Pier Skew, UpSta & Num, DnSta & Num=  ,200, 2 ,200, 2 , 0 , 0 , 0 ,,
       6       6
     450     540
       6       6
     450     540
Pier Skew, UpSta & Num, DnSta & Num=  ,342, 4 ,342, 4 , 0 , 0 , 0 ,,
    13.5    13.5     8.5     8.5
     450     511     513     540
    13.5    13.5     8.5     8.5
     450     511     513     540
Pier Skew, UpSta & Num, DnSta & Num=  ,402.5, 2 ,402.5, 2 , 0 , 0 , 0 ,,
     5.5     5.5
     450     541
     5.5     5.5
     450     541
Pier Skew, UpSta & Num, DnSta & Num=  ,465, 2 ,465, 2 , 0 , 0 , 0 ,,
     5.5     5.5
     450     540
     5.5     5.5
     450     540
Pier Skew, UpSta & Num, DnSta & Num=  ,525, 2 ,525, 2 , 0 , 0 , 0 ,,
     5.5     5.5
     450     541
     5.5     5.5
     450     541
Pier Skew, UpSta & Num, DnSta & Num=  ,585, 2 ,585, 2 , 0 , 0 , 0 ,,
     5.5     5.5
     450     541
     5.5     5.5
     450     541
Pier Skew, UpSta & Num, DnSta & Num=  ,821.75, 2 ,821.75, 2 , 0 , 0 , 0 ,,
       2       2
     450     539
       2       2
     450     539
Pier Skew, UpSta & Num, DnSta & Num=  ,851.75, 2 ,851.75, 2 , 0 , 0 , 0 ,,
       2       2
     450     539
       2       2
     450     539
Pier Skew, UpSta & Num, DnSta & Num=  ,879.75, 2 ,879.75, 2 , 0 , 0 , 0 ,,
       2       2
     450     539
       2       2
     450     539
Pier Skew, UpSta & Num, DnSta & Num=  ,901.75, 2 ,901.75, 2 , 0 , 0 , 0 ,,
       2       2
     450     539
       2       2
     450     539
Pier Skew, UpSta & Num, DnSta & Num=  ,929.75, 2 ,929.75, 2 , 0 , 0 , 0 ,,
       2       2
     450     539
       2       2
     450     539
Pier Skew, UpSta & Num, DnSta & Num=  ,958.75, 2 ,958.75, 2 , 0 , 0 , 0 ,,
       2       2
     450     539
       2       2
     450     539
Pier Skew, UpSta & Num, DnSta & Num=  ,986.75, 2 ,986.75, 2 , 0 , 0 , 0 ,,
       4       4
     450     539
       4       4
     450     539
Pier Skew, UpSta & Num, DnSta & Num=  ,1014.75, 2 ,1014.75, 2 , 0 , 0 , 0 ,,
       2       2
     450     539
       2       2
     450     539
Pier Skew, UpSta & Num, DnSta & Num=  ,1036.75, 2 ,1036.75, 2 , 0 , 0 , 0 ,,
       2       2
     450     539
       2       2
     450     539
Pier Skew, UpSta & Num, DnSta & Num=  ,1056.75, 2 ,1056.75, 2 , 0 , 0 , 0 ,,
       2       2
     450     539
       2       2
     450     539
Pier Skew, UpSta & Num, DnSta & Num=  ,1078.75, 2 ,1078.75, 2 , 0 , 0 , 0 ,,
       2       2
     450     539
       2       2
     450     539
Pier Skew, UpSta & Num, DnSta & Num=  ,1103.75, 2 ,1103.75, 2 , 0 , 0 , 0 ,,
       2       2
     450     539
       2       2
     450     539
Pier Skew, UpSta & Num, DnSta & Num=  ,1131.75, 2 ,1131.75, 2 , 0 , 0 , 0 ,,
       2       2
     450     539
       2       2
     450     539
Abutment Skew #Up #Dn= , 2 , 2
 1144.42 1166.94
  521.03  534.28
 1144.42 1166.94
  522.58  534.28
BR Coef=-1 , 0 , 0 ,, 0 ,,,0.8,-1,,0,
WSPro=,,,, 1 ,,,, 0 ,,,, 0 ,,,,-1 ,-1 ,-1 , 0 , 0 , 0 , 0 , 0
BR U #Sta/Elev= 499
       0  528.43     .46  528.06     .65  527.85     1.2     526    1.32  525.46
    1.56     524    1.71  523.66     2.3  522.05    3.61  522.03    4.65     522
   29.84     522   33.14  521.88   34.74   521.8   51.77  521.74   53.98   521.5
   60.96  521.49   62.91  521.55   64.13  521.62   65.84  521.39   68.15  521.02
   69.28  520.94   71.54  520.57   75.28     520   75.45  519.97   78.68  519.28
   79.32  519.13   79.68  518.99    80.1  518.81   82.07     518   84.71  516.87
   86.83     516   91.83  513.99   94.24  513.01   96.75     512  100.45  510.56
   103.6  509.34  106.41  508.23  109.85  506.77  111.68     506  113.64  505.14
  117.88  503.33  120.11  502.36  122.23  501.38   123.3   500.9  125.41     500
  128.43  499.59  131.39  499.18   139.2     498  144.56  497.49  157.97     496
  164.59  495.42  164.86   495.4  165.13  495.32  167.15  495.14  167.38  495.19
  168.46  494.94  170.21  494.76  170.69  494.82  171.41  494.78  174.86  494.68
  176.22  494.56  185.98  494.27  186.62  494.22  188.52  494.17  190.46  494.13
  191.16  494.09  195.15     494  196.06     494  204.35  493.83  209.59  493.74
  221.48  493.52  222.65  493.42  223.86  493.48  225.24  493.46  228.66   493.4
  228.98  493.25  229.22  493.31  229.77  493.21  229.94   493.1  230.12  493.07
  230.27  492.97  230.83  492.74  231.19   492.7  233.84  492.56  234.19  492.48
  234.81  492.43   235.2  492.36  235.44  492.39  235.64  492.33  236.26  492.32
  236.47  492.24  236.61  492.26  240.65  492.15   241.1  492.07  241.17  491.25
  264.93  491.69  265.52  491.67  265.89   491.6  266.88  491.56  267.29  491.55
  267.64  491.59  268.46  491.56  268.79   491.6  269.84  491.56  270.54  491.53
  271.43   491.5  271.74  491.44  272.09  491.43  273.48  491.38  274.41  491.35
  275.28  491.28  275.54  491.23   276.5   491.2  276.75  491.15  277.62  491.12
  278.32   491.1  278.83  491.05  279.16  491.04  279.38     491  279.85  490.99
  281.59  490.94  281.99  490.96  282.76  490.94  282.94  490.93  284.09   490.9
  284.64  490.88  285.38  490.78  285.54  490.75  285.73  490.75  286.55   490.8
  286.93  490.71  287.08  490.71  287.46  490.77   287.6  490.75  289.28  490.71
  289.95  490.69  290.18  490.66  291.21  490.64  291.52  490.59  291.62  490.59
  291.99  490.52  292.07  490.48  300.73   490.4  304.09   491.9  304.47  492.16
  304.84  492.33  306.56  493.08  307.03  493.29   307.5  493.42  308.45  493.84
  308.86  494.03  309.33  494.23  309.71  494.48  310.08  494.64  310.44  494.87
  310.79  495.02  311.18   495.2  311.51  495.34  311.82  495.48  312.48  495.64
  312.77  495.77  313.31  495.95  313.63  496.09  314.13  496.37  319.71   498.8
  320.44  499.13  320.65  499.22  320.86  499.28  321.28   499.5  321.47  499.58
  322.02  499.83  322.34  499.93  322.66  500.08  322.96  500.21   323.1  500.24
  323.48  500.42  323.62  500.48  332.73   504.5  332.86  504.51  350.36   505.2
   351.9  505.23  353.06  505.27  353.73  505.29  354.43  505.32  355.18  505.37
  357.93  505.67  358.22   505.7  362.67  506.44  369.07  507.55  370.47  508.59
  374.14  511.51  376.42  513.28  376.82  513.62     384   516.4   391.3  519.06
  401.38  522.23  402.75  522.68  405.12  523.45   408.5  523.96     409  523.91
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BR U #Mann= 3
       0     .06   64.13    .035  425.03     .06
BR U Banks=64.13,425.03
BR D #Sta/Elev= 499
       0  528.43     .46  528.06     .65  527.85     1.2     526    1.32  525.46
    1.56     524    1.71  523.66     2.3  522.05    3.61  522.03    4.65     522
   29.84     522   33.14  521.88   34.74   521.8   51.77  521.74   53.98   521.5
   60.96  521.49   62.91  521.55   64.13  521.62   65.84  521.39   68.15  521.02
   69.28  520.94   71.54  520.57   75.28     520   75.45  519.97   78.68  519.28
   79.32  519.13   79.68  518.99    80.1  518.81   82.07     518   84.71  516.87
   86.83     516   91.83  513.99   94.24  513.01   96.75     512  100.45  510.56
   103.6  509.34  106.41  508.23  109.85  506.77  111.68     506  113.64  505.14
  117.88  503.33  120.11  502.36  122.23  501.38   123.3   500.9  125.41     500
  128.43  499.59  131.39  499.18   139.2     498  144.56  497.49  157.97     496
  164.59  495.42  164.86   495.4  165.13  495.32  167.15  495.14  167.38  495.19
  168.46  494.94  170.21  494.76  170.69  494.82  171.41  494.78  174.86  494.68
  176.22  494.56  185.98  494.27  186.62  494.22  188.52  494.17  190.46  494.13
  191.16  494.09  195.15     494  196.06     494  204.35  493.83  209.59  493.74
  221.48  493.52  222.65  493.42  223.86  493.48  225.24  493.46  228.66   493.4
  228.98  493.25  229.22  493.31  229.77  493.21  229.94   493.1  230.12  493.07
  230.27  492.97  230.83  492.74  231.19   492.7  233.84  492.56  234.19  492.48
  234.81  492.43   235.2  492.36  235.44  492.39  235.64  492.33  236.26  492.32
  236.47  492.24  236.61  492.26  240.65  492.15   241.1  492.07  241.17  491.25
  264.93  491.69  265.52  491.67  265.89   491.6  266.88  491.56  267.29  491.55
  267.64  491.59  268.46  491.56  268.79   491.6  269.84  491.56  270.54  491.53
  271.43   491.5  271.74  491.44  272.09  491.43  273.48  491.38  274.41  491.35
  275.28  491.28  275.54  491.23   276.5   491.2  276.75  491.15  277.62  491.12
  278.32   491.1  278.83  491.05  279.16  491.04  279.38     491  279.85  490.99
  281.59  490.94  281.99  490.96  282.76  490.94  282.94  490.93  284.09   490.9
  284.64  490.88  285.38  490.78  285.54  490.75  285.73  490.75  286.55   490.8
  286.93  490.71  287.08  490.71  287.46  490.77   287.6  490.75  289.28  490.71
  289.95  490.69  290.18  490.66  291.21  490.64  291.52  490.59  291.62  490.59
  291.99  490.52  292.07  490.48  300.73   490.4  304.09   491.9  304.47  492.16
  304.84  492.33  306.56  493.08  307.03  493.29   307.5  493.42  308.45  493.84
  308.86  494.03  309.33  494.23  309.71  494.48  310.08  494.64  310.44  494.87
  310.79  495.02  311.18   495.2  311.51  495.34  311.82  495.48  312.48  495.64
  312.77  495.77  313.31  495.95  313.63  496.09  314.13  496.37  319.71   498.8
  320.44  499.13  320.65  499.22  320.86  499.28  321.28   499.5  321.47  499.58
  322.02  499.83  322.34  499.93  322.66  500.08  322.96  500.21   323.1  500.24
  323.48  500.42  323.62  500.48  332.73   504.5  332.86  504.51  350.36   505.2
   351.9  505.23  353.06  505.27  353.73  505.29  354.43  505.32  355.18  505.37
  357.93  505.67  358.22   505.7  362.67  506.44  369.07  507.55  370.47  508.59
  374.14  511.51  376.42  513.28  376.82  513.62     384   516.4   391.3  519.06
  401.38  522.23  402.75  522.68  405.12  523.45   408.5  523.96     409  523.91
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BR D #Mann= 3
       0     .06   64.13    .035  425.03     .06
BR D Banks=,425.03
BC Design=,, 0 ,, 0 ,,13,812,812,25,2
BC Use User HTab Curves=0
BC User HTab FreeFlow(D)= 0

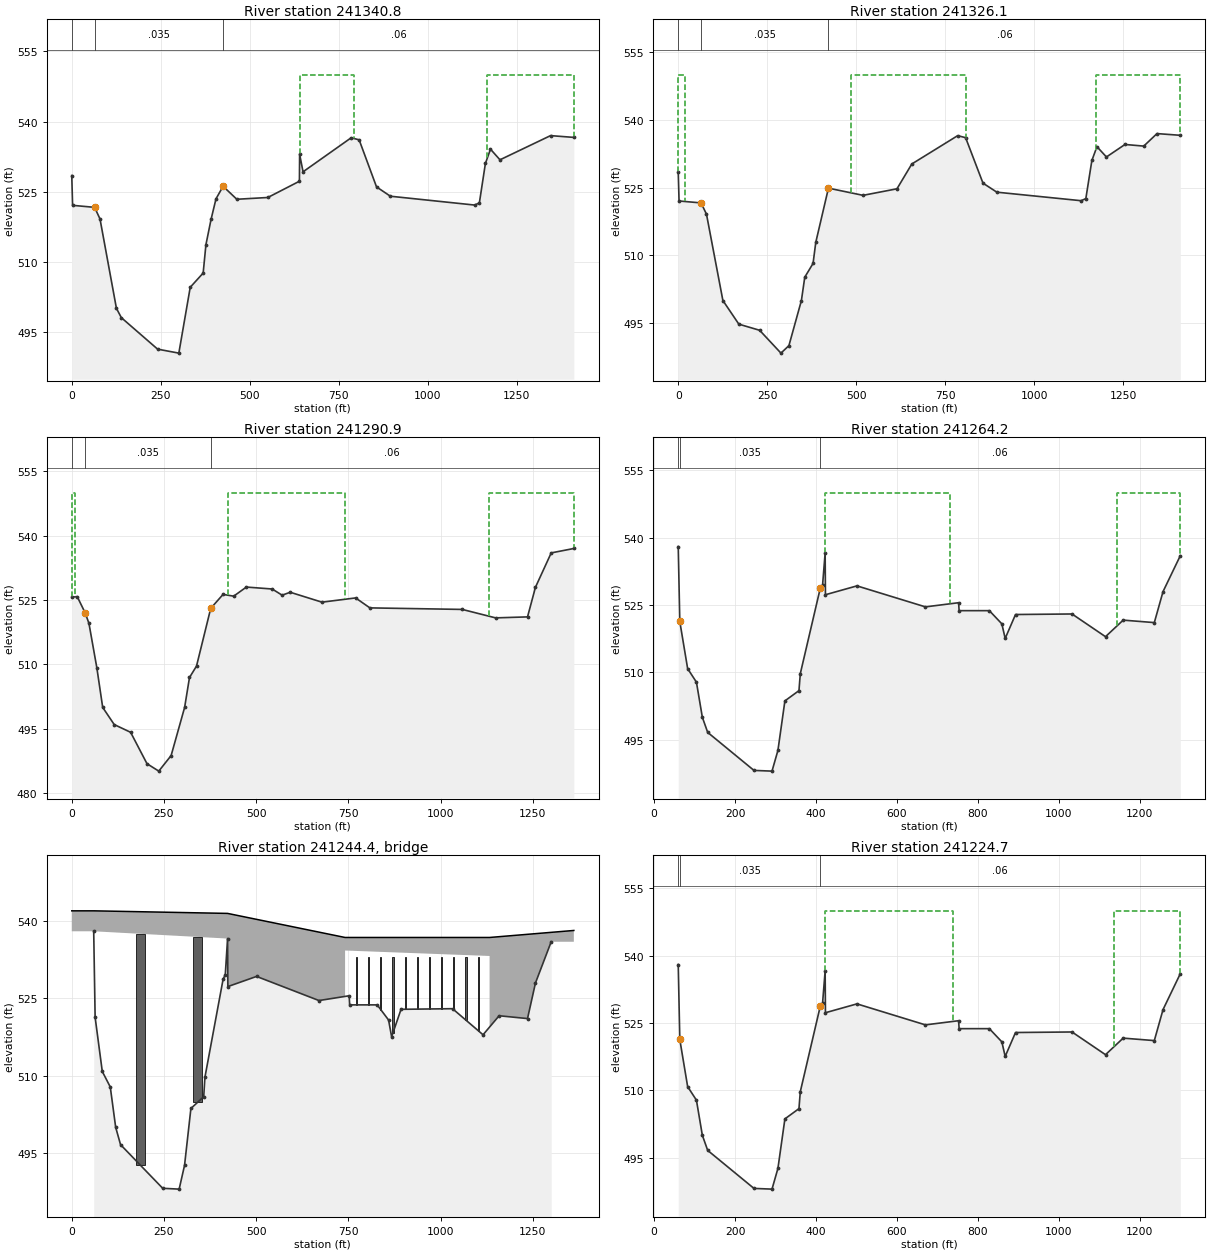
Type RM Length L Ch R = 1 ,241340.8,12.83,14.71,14.82
BEGIN DESCRIPTION:
Downstream of Burlington Northern Railroad.
Ineffective flow in LOB and ROB due to railroad bridges.
Cross-section generated from ground points along centerline of railroad.
END DESCRIPTION:
XS GIS Cut Line= 6
 2326027.9076731 6970437.9092628 2326212.7107422 6970131.3042769
 2326335.6204122 6969921.0438829 2326506.4224906 6969633.5397014
  2326657.182855 6969378.4070663 2326745.5348911 6969223.9616496
#Sta/Elev= 30
       0  528.43     2.3  522.05   64.13  521.62   79.32  519.13  125.41     500
   139.2     498  241.17  491.25  300.73   490.4  332.73   504.5  369.07  507.55
  376.82  513.62   391.3  519.06  405.12  523.45  425.03  526.13  463.61  523.35
  550.66  523.73  639.42  527.21     640     533   649.6  529.23  784.83  536.52
  807.16  536.08     856     526  894.94     524 1131.59  522.11 1144.88  522.58
 1161.81  531.02 1176.07  534.08 1202.75   531.8 1344.75  536.98 1410.23   536.6
#Mann= 3 ,0,0
       0     .06       0   64.13    .035       0  425.03     .06       0
#XS Ineff= 2 ,-1
     640  793.75     550 1166.94 1410.23     550
Permanent Ineff=
       F       F
Bank Sta=64.13,425.03
XS Rating Curve= 0 ,0
Exp/Cntr=0.5,0.3

Type RM Length L Ch R = 1 ,241326.1,33.85,35.18,35.94
BEGIN DESCRIPTION:
This cross section corresponds to cross section 241326.1 of the non-georeferenced CDC model which was the source of this model.
END DESCRIPTION:
XS GIS Cut Line= 6
 2326037.9735143 6970442.8086566 2326186.5566152 6970199.9748705
 2326360.9410991 6969903.6758148 2326559.4490666 6969561.5004747
 2326721.7830872 6969277.0296834 2326751.0789814 6969226.2498568
#Sta/Elev= 30
       0  528.43     2.3  522.05   64.13  521.62   79.32  519.13  125.41     500
  170.21  494.76  228.66   493.4   288.5  488.34  310.87     490  345.98     500
  355.38  505.16   378.7  508.22  386.35  512.89  421.89  524.89  519.19   523.3
  614.41  524.75  656.12  530.25  784.83  536.52  807.16  536.08     856     526
  894.94     524 1131.59  522.11 1144.88  522.58 1161.81  531.02 1176.07  534.08
 1202.75   531.8  1254.8  534.57 1307.56  534.21 1344.75  536.98 1410.23   536.6
#Mann= 3 ,-1,0
       0     .06       0   64.13    .035       0  421.89     .06       0
#XS Ineff= 3 ,-1
  484.53   809.5     550       0   18.67     550 1172.89 1410.23     550
Permanent Ineff=
       F       F       F
Bank Sta=64.13,421.89
XS Rating Curve= 0 ,0
Exp/Cntr=0.5,0.3

Type RM Length L Ch R = 1 ,241290.9,21.5,26.7,27.88
BEGIN DESCRIPTION:
This cross section corresponds to cross section 241290.9 of the non-georeferenced CDC model which was the source of this model.
END DESCRIPTION:
XS GIS Cut Line= 6
 2326094.5699209 6970409.9931015 2326124.3322513  6970359.576649
  2326216.645373 6970208.7066112  2326391.089231 6969912.3065678
 2326589.6307746 6969570.0734093 2326781.4263663 6969234.5356441
#Sta/Elev= 30
       0  525.71   14.81  525.81   36.49     522   46.57  519.58   67.94  509.25
   83.87     500  115.12     496  159.58   494.2  203.97  486.88  235.95  485.15
  269.43  488.78  306.03     500  319.24  506.97  338.24  509.62  376.83  523.08
  410.26  526.33  439.11  525.92  473.46  528.04  543.43  527.59  570.41  526.15
  592.34  526.83  678.47  524.52  769.67  525.51  808.42  523.19  1058.9  522.83
 1149.36  520.86 1235.87  521.09 1257.41     528 1300.09     536 1361.48  537.03
#Mann= 3 ,-1,0
       0     .06       0   36.49    .035       0  376.83     .06       0
#XS Ineff= 3 ,-1
  423.67  740.44     550       0    9.98     550  1130.1 1361.48     550
Permanent Ineff=
       F       F       F
Bank Sta=36.49,376.83
XS Rating Curve= 0 ,0
Exp/Cntr=0.5,0.3

Type RM Length L Ch R = 1 ,241264.2,37.29,39.56,40.23
BEGIN DESCRIPTION:
Upstream of Union Pacific Railroad.
Copy of cross-section 241224.7
Ineffective flow in LOB and ROB due to railroad bridges.
END DESCRIPTION:
XS GIS Cut Line= 6
 2326146.7868138 6970370.5437384 2326146.8589886 6970370.4216123
 2326330.8986218 6970060.9470981 2326451.3906802 6969855.3250079
 2326777.5349048 6969306.5119966 2326779.4097597 6969303.3571201
#Sta/Elev= 30
   59.48  538.03   63.34  521.34   82.74  510.83  104.44  507.82  119.05     500
  132.26  496.63  246.61  488.16   291.2     488  305.82  492.62  323.05  503.65
  357.78  505.93  361.09  509.71  410.52  528.78  416.24  529.56  422.48  536.62
  423.24   527.3  501.11  529.27  670.31  524.59  752.25  525.52  753.54  523.75
  828.23  523.75  859.12  520.81  867.34  517.56  892.89  522.89 1032.52  523.01
 1115.25  517.95 1158.91  521.64 1235.87  521.09 1257.41     528 1300.09     536
#Mann= 3 ,0,0
   59.48     .06       0   63.34    .035       0  410.52     .06       0
#XS Ineff= 2 ,-1
  422.48  731.35     550 1142.79 1300.09     550
Permanent Ineff=
       F       F
Bank Sta=63.34,410.52
XS Rating Curve= 0 ,0
Exp/Cntr=0.5,0.3

Type RM Length L Ch R = 3 ,241244.4,,,
BEGIN DESCRIPTION:
Union Pacific Railroad
Two bridges: West Fork channel bridge, and ROB relief bridge.  West Fork bridge: data from 1975 USACE field survey, Fort Worth Floodway as-built plans, minimum low chord elev. 536.62, bridge length 363 feet.
Relief bridge replaced with new structure (see CDC FW111317-1 UPRR Bridge).
END DESCRIPTION:
Node Name=UP RR
Bridge Culvert--1,0,-1,-1, 0
Deck Dist Width WeirC Skew NumUp NumDn MinLoCord MaxHiCord MaxSubmerge Is_Ogee
9.8,20,2.6,0, 10, 10, , , 0.95, 0, 0,0,,
       0   59.48   59.48  422.48  422.48  741.15  741.15 1132.99 1132.99 1361.48
     542     542     542   541.5   541.5  536.83  536.83  536.83  536.83  538.19
                  538.03  536.62     450     450   534.3  533.24     450     450
       0   59.48   59.48  422.48  422.48  741.15  741.15 1132.99 1132.99 1361.48
     542     542     542   541.5   541.5  536.83  536.83  536.83  536.83  538.19
                  538.03  536.62     450     450   534.3  533.24     450     450
Pier Skew, UpSta & Num, DnSta & Num=  ,186.48, 6 ,186.48, 6 , 0 , 0 , 0 ,,
      26      26      20      20      11     9.5
     450   506.4   509.2   510.2   512.5     540
      26      26      20      20      11     9.5
     450   506.4   509.2   510.2   512.5     540
Pier Skew, UpSta & Num, DnSta & Num=  ,341.48, 5 ,341.48, 5 , 0 , 0 , 0 ,,
      26      26      26    12.5      12
     450     450   505.6   507.6     540
      26      26      26    12.5      12
     450     450   505.6   507.6     540
Pier Skew, UpSta & Num, DnSta & Num=  ,772.07, 4 ,772.07, 4 , 3 , 3 , 0 ,,
    1.17    1.17       3       3
     517  530.33  530.33     533
    1.17    1.17       3       3
     517  530.33  530.33     533
Pier Skew, UpSta & Num, DnSta & Num=  ,805.07, 4 ,805.07, 4 , 3 , 3 , 0 ,,
    1.17    1.17       3       3
     517  530.33  530.33     533
    1.17    1.17       3       3
     517  530.33  530.33     533
Pier Skew, UpSta & Num, DnSta & Num=  ,838.07, 4 ,838.07, 4 , 3 , 3 , 0 ,,
    1.17    1.17       3       3
     517  530.33  530.33     533
    1.17    1.17       3       3
     517  530.33  530.33     533
Pier Skew, UpSta & Num, DnSta & Num=  ,871.07, 4 ,871.07, 4 , 3 , 3 , 0 ,,
    1.17    1.17       3       3
     517  530.33  530.33     533
    1.17    1.17       3       3
     517  530.33  530.33     533
Pier Skew, UpSta & Num, DnSta & Num=  ,904.07, 4 ,904.07, 4 , 3 , 3 , 0 ,,
    1.17    1.17       3       3
     517  530.33  530.33     533
    1.17    1.17       3       3
     517  530.33  530.33     533
Pier Skew, UpSta & Num, DnSta & Num=  ,937.07, 4 ,937.07, 4 , 3 , 3 , 0 ,,
    1.17    1.17       3       3
     517  530.33  530.33     533
    1.17    1.17       3       3
     517  530.33  530.33     533
Pier Skew, UpSta & Num, DnSta & Num=  ,970.07, 4 ,970.07, 4 , 3 , 3 , 0 ,,
    1.17    1.17       3       3
     517  530.33  530.33     533
    1.17    1.17       3       3
     517  530.33  530.33     533
Pier Skew, UpSta & Num, DnSta & Num=  ,1003.07, 4 ,1003.07, 4 , 3 , 3 , 0 ,,
    1.17    1.17       3       3
     517  530.33  530.33     533
    1.17    1.17       3       3
     517  530.33  530.33     533
Pier Skew, UpSta & Num, DnSta & Num=  ,1036.07, 4 ,1036.07, 4 , 3 , 3 , 0 ,,
    1.17    1.17       3       3
     517  530.33  530.33     533
    1.17    1.17       3       3
     517  530.33  530.33     533
Pier Skew, UpSta & Num, DnSta & Num=  ,1069.07, 4 ,1069.07, 4 , 3 , 3 , 0 ,,
    1.17    1.17       3       3
     517  530.33  530.33     533
    1.17    1.17       3       3
     517  530.33  530.33     533
Pier Skew, UpSta & Num, DnSta & Num=  ,1102.07, 4 ,1102.07, 4 , 3 , 3 , 0 ,,
    1.17    1.17       3       3
     517  530.33  530.33     533
    1.17    1.17       3       3
     517  530.33  530.33     533
BR Coef=-1 , 0 , 0 ,, 0 ,,,0.8,-1,,0,
WSPro=,,,, 1 ,,,, 0 ,,,, 0 ,,,,-1 ,-1 ,-1 , 0 , 0 , 0 , 0 , 0
BR U #Sta/Elev= 421
   59.48  538.03   63.25   521.7   63.34  521.34   64.72  520.65   79.23  513.12
      81  512.41   82.33  511.77   82.74  510.83   84.91  510.89   86.95  510.82
   87.49  510.75   88.77  510.74   89.16  510.69   90.12  510.63   91.55  510.37
    92.7  510.11   93.52  509.98    94.6  509.77   97.06  509.13   97.46  509.09
    98.8  508.81  100.02   508.6  102.09  508.15  102.58  508.08  102.92  507.98
  103.78  507.93  104.44  507.82   104.5  507.72  104.93  507.58  105.88  507.09
  107.89  506.08  109.39  505.35  110.81  504.64  113.05  503.48  114.12  502.95
  115.93     502  117.73  501.01  118.41  500.51  119.05     500  120.05  499.69
  125.35     498   126.3  497.78  127.54  497.57  132.26  496.63   136.8     496
  138.26     496   138.8  495.97  139.48  495.83  139.82  495.81  141.95  495.61
  143.35  495.56  143.77  495.46  145.49  495.46  146.83  495.39     147  495.32
  147.67  495.23  148.24   495.2     149  495.22  149.55  495.19  150.18   495.2
  151.04  494.93  152.85  494.84  153.38  494.89  154.51  494.83   154.8   494.9
  155.11  494.88  155.58  494.77  156.62   494.7  157.39  494.62  157.68  494.67
  158.47  494.58  158.86   494.6  162.18  494.38  163.53   494.3  164.38  494.21
  167.66     494  170.27  493.75  174.23  493.38  175.97  493.29   179.1  493.11
  188.87  492.57  193.76  492.31   198.7  491.89  203.54  491.64  208.32  491.37
  209.72   491.3  212.97  491.25   214.6  491.15  217.43  491.07  220.56  490.89
  222.78  490.85  225.31  490.68  226.97  490.52  228.25  490.42  232.12     490
  234.16   489.8     235  489.65  237.08  489.39  239.66     489  242.88  488.65
  243.76  488.53  245.33  488.41  246.61  488.16  247.73  488.14  248.33  488.22
  249.03  488.15  249.54  488.16  253.97  488.08   254.9  488.09  259.47  488.19
  259.85  488.18  264.39  488.19  269.68  488.13  270.73  488.06  271.12   488.1
  275.13  488.09  276.33  488.18  277.37   488.2  277.46  488.15  278.02  488.22
  278.74  488.23  281.19  488.21  281.48  488.24  283.22  488.09  287.95  488.07
   291.2     488  293.81  488.22  294.66  488.65  295.56     489  296.79   489.4
  298.61  490.12  300.58  490.73  301.23  490.83  301.78  491.05  302.38   491.3
  302.64  491.33  303.21  491.48   303.7  491.68  304.23  491.97  304.69  492.16
  305.18  492.36  305.82  492.62  323.05  503.65  338.63  503.66  347.56  504.22
  348.39  504.35  350.51  504.68  354.88  505.44  356.27  505.44  357.78  505.93
  358.73  506.92  361.09  509.71  368.81  512.52  377.43  516.02  387.21  519.77
  394.34  522.89  402.77   525.1  403.46  525.29  405.29  526.21  410.52  528.78
  411.85  529.01  416.24  529.56  422.48  536.62  423.24   527.3  423.96  527.35
  426.33  527.64  428.16  527.76  429.64  527.96   430.4  527.99  430.94  528.04
  436.07  528.22  437.26  528.29  438.14  528.32  438.71  528.29   441.4  528.35
  442.03  528.42  443.36  528.45  445.35  528.54  446.77  528.63  448.16  528.65
   448.9   528.7  449.56  528.71  451.62   528.8  453.98  528.92  456.68  529.04
   458.3  529.08  459.24  529.07  459.76   529.1  460.86   529.1  462.35  529.15
  464.72  529.21  467.51  529.27  471.07  529.31   473.3  529.31  475.56  529.29
  480.59  529.29  483.39  529.26  486.66  529.25  490.24  529.25  493.59  529.26
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BR U #Mann= 3
   59.48    .035  410.52     .06  475.56     .06
BR U Banks=63.34,410.52
BR D #Sta/Elev= 389
   59.48  538.03   63.25   521.7   63.34  521.34   64.72  520.65   79.23  513.12
      81  512.41   82.33  511.77   82.74  510.83   84.91  510.89   86.95  510.82
   87.49  510.75   88.77  510.74   89.16  510.69   90.12  510.63   91.55  510.37
    92.7  510.11   93.52  509.98    94.6  509.77   97.06  509.13   97.46  509.09
    98.8  508.81  100.02   508.6  102.09  508.15  102.58  508.08  102.92  507.98
  103.78  507.93  104.44  507.82   104.5  507.72  104.93  507.58  105.88  507.09
  107.89  506.08  109.39  505.35  110.81  504.64  113.05  503.48  114.12  502.95
  115.93     502  117.73  501.01  118.41  500.51  119.05     500  120.05  499.69
  125.35     498   126.3  497.78  127.54  497.57  132.26  496.63   136.8     496
  138.26     496   138.8  495.97  139.48  495.83  139.82  495.81  141.95  495.61
  143.35  495.56  143.77  495.46  145.49  495.46  146.83  495.39     147  495.32
  147.67  495.23  148.24   495.2     149  495.22  149.55  495.19  150.18   495.2
  151.04  494.93  152.85  494.84  153.38  494.89  154.51  494.83   154.8   494.9
  155.11  494.88  155.58  494.77  156.62   494.7  157.39  494.62  157.68  494.67
  158.47  494.58  158.86   494.6  162.18  494.38  163.53   494.3  164.38  494.21
  167.66     494  170.27  493.75  174.23  493.38  175.97  493.29   179.1  493.11
  188.87  492.57  193.76  492.31   198.7  491.89  203.54  491.64  208.32  491.37
  209.72   491.3  212.97  491.25   214.6  491.15  217.43  491.07  220.56  490.89
  222.78  490.85  225.31  490.68  226.97  490.52  228.25  490.42  232.12     490
  234.16   489.8     235  489.65  237.08  489.39  239.66     489  242.88  488.65
  243.76  488.53  245.33  488.41  246.61  488.16  247.73  488.14  248.33  488.22
  249.03  488.15  249.54  488.16  253.97  488.08   254.9  488.09  259.47  488.19
  259.85  488.18  264.39  488.19  269.68  488.13  270.73  488.06  271.12   488.1
  275.13  488.09  276.33  488.18  277.37   488.2  277.46  488.15  278.02  488.22
  278.74  488.23  281.19  488.21  281.48  488.24  283.22  488.09  287.95  488.07
   291.2     488  293.81  488.22  294.66  488.65  295.56     489  296.79   489.4
  298.61  490.12  300.58  490.73  301.23  490.83  301.78  491.05  302.38   491.3
  302.64  491.33  303.21  491.48   303.7  491.68  304.23  491.97  304.69  492.16
  305.18  492.36  305.82  492.62  323.05  503.65  338.63  503.66  347.56  504.22
  348.39  504.35  350.51  504.68  354.88  505.44  356.27  505.44  357.78  505.93
  358.73  506.92  361.09  509.71  368.81  512.52  377.43  516.02  387.21  519.77
  394.34  522.89  402.77   525.1  403.46  525.29  405.29  526.21  410.52  528.78
  411.85  529.01  416.24  529.56  422.48  536.62  423.24   527.3  423.96  527.35
  426.33  527.64  428.16  527.76  429.64  527.96   430.4  527.99  430.94  528.04
  436.07  528.22  437.26  528.29  438.14  528.32  438.71  528.29   441.4  528.35
  442.03  528.42  443.36  528.45  445.35  528.54  446.77  528.63  448.16  528.65
   448.9   528.7  449.56  528.71  451.62   528.8  453.98  528.92  456.68  529.04
   458.3  529.08  459.24  529.07  459.76   529.1  460.86   529.1  462.35  529.15
  464.72  529.21  467.51  529.27  471.07  529.31   473.3  529.31  475.56  529.29
  480.59  529.29  483.39  529.26  486.66  529.25  490.24  529.25  493.59  529.26
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BR D #Mann= 2
   59.48    .035  410.52     .06
BR D Banks=63.34,410.52
BC Design=,, 0 ,, 0 ,,,,,,
BC Use User HTab Curves=0
BC User HTab FreeFlow(D)= 0

Type RM Length L Ch R = 1 ,241224.7,14.45,18.02,17.37
BEGIN DESCRIPTION:
Downstream of Union Pacific Railroad.
Ineffective flow in LOB and ROB due to railroad bridges.
Cross-section generated from ground points along centerline of railroad.
---------------------------------------------
CDC FW111317-1 UPRR Bridge (new relief bridge)
--------------------------------------------
END DESCRIPTION:
XS GIS Cut Line= 6
 2326176.0573526 6970387.8420164 2326176.1057502  6970387.760123
 2326360.1777929 6970078.2314203  2326480.672444 6969872.6049224
 2326806.7632579 6969323.8816204 2326808.6790219 6969320.6579039
#Sta/Elev= 30
   59.48  538.03   63.34  521.34   82.74  510.83  104.44  507.82  119.05     500
  132.26  496.63  246.61  488.16   291.2     488  305.82  492.62  323.05  503.65
  357.78  505.93  361.09  509.71  410.52  528.78  416.24  529.56  422.48  536.62
  423.24   527.3  501.11  529.27  670.31  524.59  752.25  525.52  753.54  523.75
  828.23  523.75  859.12  520.81  867.34  517.56  892.89  522.89 1032.52  523.01
 1115.25  517.95 1158.91  521.64 1235.87  521.09 1257.41     528 1300.09     536
#Mann= 3 ,0,0
   59.48     .06       0   63.34    .035       0  410.52     .06       0
#XS Ineff= 2 ,-1
  422.48   737.9     550 1136.24 1300.09     550
Permanent Ineff=
       F       F
Bank Sta=63.34,410.52
XS Rating Curve= 0 ,0
Exp/Cntr=0.5,0.3

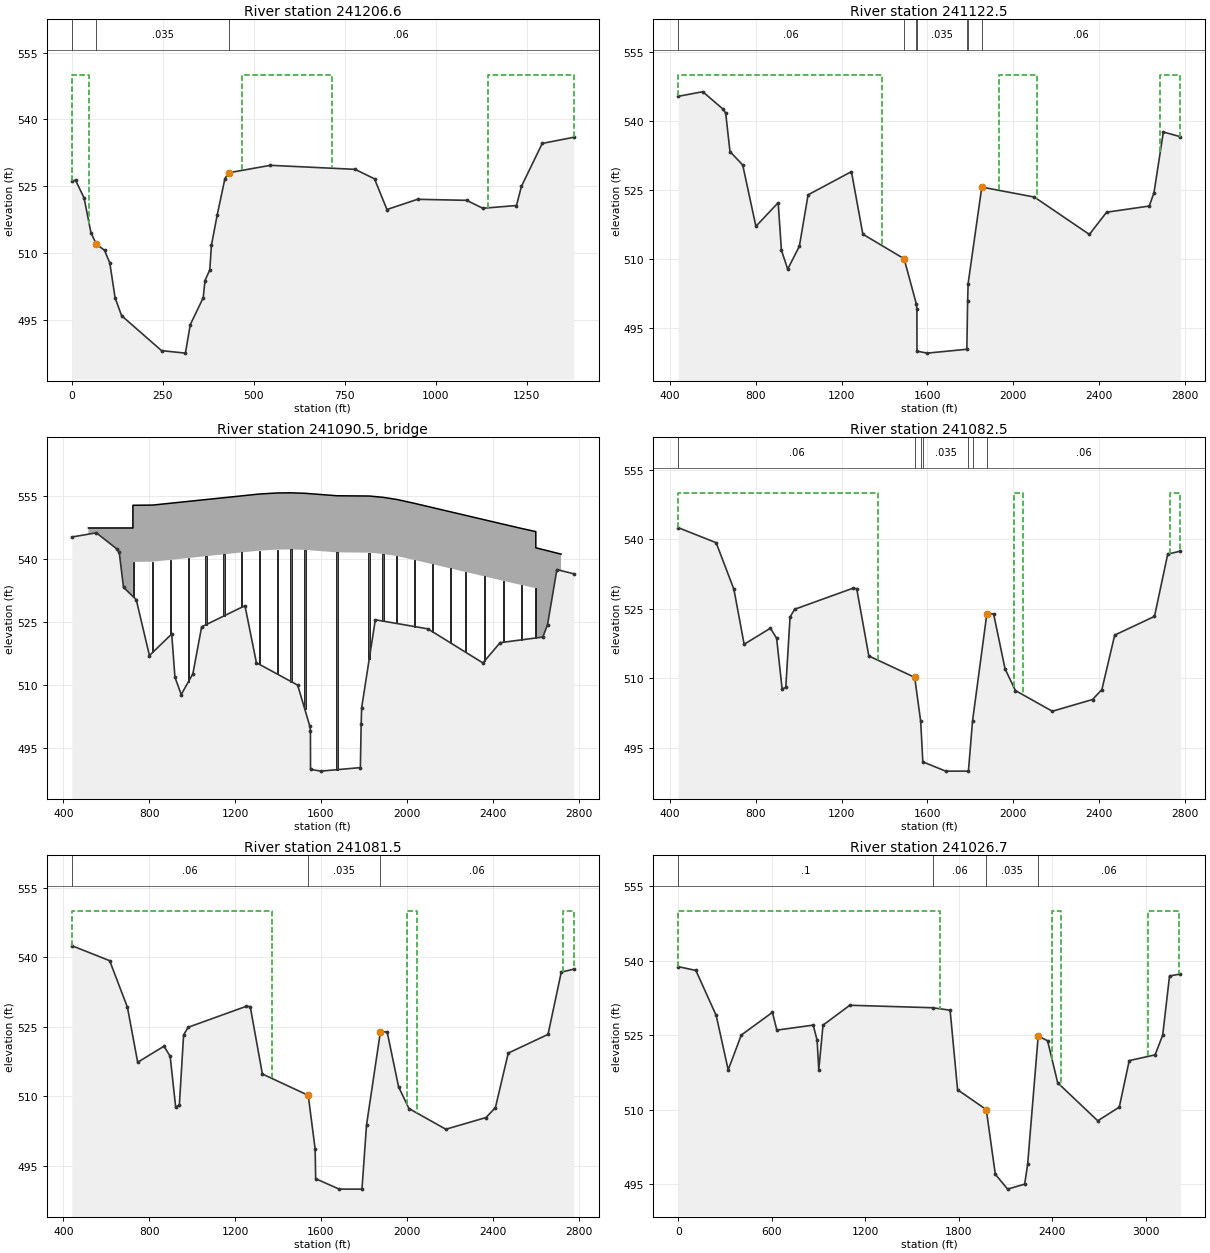
Type RM Length L Ch R = 1 ,241206.6,102.58,84.1,67
BEGIN DESCRIPTION:
This cross section corresponds to cross section 241206.6 of the non-georeferenced CDC model which was the source of this model.
END DESCRIPTION:
XS GIS Cut Line= 6
 2326157.7156192 6970445.2090265 2326188.2027534 6970393.1266012
 2326283.4687604  6970237.430674 2326458.2094885 6969940.5260811
 2326656.9190425 6969598.0033122 2326853.3091205 6969254.5012609
#Sta/Elev= 30
       0  526.19   10.44  526.37   33.73  522.41   52.81  514.56   67.29  512.07
   90.12  510.63  104.44  507.82  119.05     500   136.8     496  246.61  488.16
  312.11   487.6  325.55     494  360.96     500  365.96  503.88  379.16  506.29
  383.54  511.75  399.62  518.65  420.64  526.72  430.94  528.04  545.47  529.71
  778.08  528.81  831.56  526.68   865.7   519.8  949.68  522.09 1084.61  521.86
 1128.92  520.08 1221.45   520.7 1235.13     525 1292.27  534.62 1379.06     536
#Mann= 3 ,-1,0
       0     .06       0   67.29    .035       0  430.94     .06       0
#XS Ineff= 3 ,-1
  466.23   714.1     550       0   48.23     550 1143.35 1379.06     550
Permanent Ineff=
       F       F       F
Bank Sta=67.29,430.94
XS Rating Curve= 0 ,0
Exp/Cntr=0.3,0.1

Type RM Length L Ch R = 1 ,241122.5,40,40,40
BEGIN DESCRIPTION:
Upstream TexRail Bridge
END DESCRIPTION:
XS GIS Cut Line= 4
      2325711.44       6971246.4      2326200.48      6970602.36
      2326537.53      6969853.27      2326929.97      6969266.81
#Sta/Elev= 30
  439.17  545.33  553.51  546.33  649.01   542.5  660.27  541.66  680.17  533.33
  739.55   530.4  800.98  517.07  904.76  522.21   919.9  511.89  949.05  507.77
 1003.38  512.73 1044.15  523.92 1246.04  528.96 1299.27  515.36 1491.51  510.02
 1548.61  500.16 1551.01  499.17 1551.47  489.94 1599.08  489.51 1783.73  490.35
 1787.36   500.8 1789.63  504.62 1853.34   525.6 2098.35  523.43 2354.54  515.31
 2434.75  520.14 2633.65  521.48  2655.6   524.4 2699.17  537.57 2778.18  536.56
#Mann= 7 ,-1,0
  439.17     .06       0 1491.51     .02       0 1548.61     .03       0
 1551.47    .035       0 1783.73     .03       0 1787.36     .02       0
 1853.34     .06       0
#XS Ineff= 3 ,-1
  439.17 1387.17     550  1932.7  2108.5     550 2684.922778.178     550
Permanent Ineff=
       F       F       F
Bank Sta=1491.51,1853.34
XS Rating Curve= 0 ,0
Exp/Cntr=0.3,0.1

Type RM Length L Ch R = 3 ,241090.5,,,
BEGIN DESCRIPTION:
TexRail Bridge
CDC FW030316-01
END DESCRIPTION:
Node Name=TexRail
Bridge Culvert--1,0,-1,-1, 0
Deck Dist Width WeirC Skew NumUp NumDn MinLoCord MaxHiCord MaxSubmerge Is_Ogee
12.42,19,2.6,0, 27, 27, , , 0.98, 0, 0,0,,
  516.67     724  724.01  816.01  899.01  982.01 1065.01 1148.01 1231.01 1314.01
 1397.01 1461.01 1525.01 1675.01 1825.01 1889.01 1953.01 2036.01 2119.01 2202.01
 2272.01 2362.01 2452.01 2535.01 2601.01 2601.02 2718.61
  547.49  547.49   552.9  552.95  553.39  553.83  554.27  554.71  555.15  555.59
  555.84  555.87  555.76  555.17  555.11   554.8  554.29  553.36  552.36  551.36
  550.52  549.44  548.36  547.37  546.63  542.77  541.25
     530     530   539.4  539.45  539.89  540.33  540.77  541.21  541.65  542.09
  542.34  542.37  542.26  541.67  541.61   541.3  540.79  539.86  538.86  537.86
  537.02  535.94  534.86  533.87  533.13     515     515
  516.67     724  724.01  816.01  899.01  982.01 1065.01 1148.01 1231.01 1314.01
 1397.01 1461.01 1525.01 1675.01 1825.01 1889.01 1953.01 2036.01 2119.01 2202.01
 2272.01 2362.01 2452.01 2535.01 2601.01 2601.02 2718.61
  547.49  547.49   552.9  552.95  553.39  553.83  554.27  554.71  555.15  555.59
  555.84  555.87  555.76  555.17  555.11   554.8  554.29  553.36  552.36  551.36
  550.52  549.44  548.36  547.37  546.63  542.77  541.25
     530     520   539.4  539.45  539.89  540.33  540.77  541.21  541.65  542.09
  542.34  542.37  542.26  541.67  541.61   541.3  540.79  539.86  538.86  537.86
  537.02  535.94  534.86  533.87  533.13     515     515
Pier Skew, UpSta & Num, DnSta & Num=  ,727.01, 2 ,727.01, 2 , 0 , 0 , 0 ,,
       6       6
     500   539.4
       6       6
     500   539.4
Pier Skew, UpSta & Num, DnSta & Num=  ,816.01, 2 ,816.01, 2 , 0 , 0 , 0 ,,
       6       6
     500  539.45
       6       6
     500  539.45
Pier Skew, UpSta & Num, DnSta & Num=  ,899.01, 2 ,899.01, 2 , 0 , 0 , 0 ,,
       6       6
     500  539.89
       6       6
     500  539.89
Pier Skew, UpSta & Num, DnSta & Num=  ,982.01, 2 ,982.01, 2 , 0 , 0 , 0 ,,
       6       6
     513  540.77
       6       6
     513  540.77
Pier Skew, UpSta & Num, DnSta & Num=  ,1065.01, 2 ,1065.01, 2 , 0 , 0 , 0 ,,
       6       6
     513  540.77
       6       6
     513  540.77
Pier Skew, UpSta & Num, DnSta & Num=  ,1148.01, 2 ,1148.01, 2 , 0 , 0 , 0 ,,
       6       6
     515  541.21
       6       6
     515  541.21
Pier Skew, UpSta & Num, DnSta & Num=  ,1231.01, 2 ,1231.01, 2 , 0 , 0 , 0 ,,
       6       6
     510  541.65
       6       6
     510  541.65
Pier Skew, UpSta & Num, DnSta & Num=  ,1314.01, 2 ,1314.01, 2 , 0 , 0 , 0 ,,
       6       6
     502  542.09
       6       6
     502  542.09
Pier Skew, UpSta & Num, DnSta & Num=  ,1397.01, 2 ,1397.01, 2 , 0 , 0 , 0 ,,
       6       6
     490  542.34
       6       6
     490  542.34
Pier Skew, UpSta & Num, DnSta & Num=  ,1461.01, 2 ,1461.01, 2 , 0 , 0 , 0 ,,
       6       6
     490  542.37
       6       6
     490  542.37
Pier Skew, UpSta & Num, DnSta & Num=  ,1525.01, 2 ,1525.01, 2 , 0 , 0 , 0 ,,
       8       8
     490  542.26
       8       8
     490  542.26
Pier Skew, UpSta & Num, DnSta & Num=  ,1675.01, 2 ,1675.01, 2 , 0 , 0 , 0 ,,
       8       8
     490  541.67
       8       8
     490  541.67
Pier Skew, UpSta & Num, DnSta & Num=  ,1825.01, 2 ,1825.01, 2 , 0 , 0 , 0 ,,
       8       8
     500  541.61
       8       8
     500  541.61
Pier Skew, UpSta & Num, DnSta & Num=  ,1889.01, 2 ,1889.01, 2 , 0 , 0 , 0 ,,
       6       6
     500   541.3
       6       6
     500   541.3
Pier Skew, UpSta & Num, DnSta & Num=  ,1953.01, 2 ,1953.01, 2 , 0 , 0 , 0 ,,
       6       6
     500  540.79
       6       6
     500  540.79
Pier Skew, UpSta & Num, DnSta & Num=  ,2036.01, 2 ,2036.01, 2 , 0 , 0 , 0 ,,
       6       6
     500  539.86
       6       6
     500  539.86
Pier Skew, UpSta & Num, DnSta & Num=  ,2119.01, 2 ,2119.01, 2 , 0 , 0 , 0 ,,
       6       6
     500  538.86
       6       6
     500  538.86
Pier Skew, UpSta & Num, DnSta & Num=  ,2202.01, 2 ,2202.01, 2 , 0 , 0 , 0 ,,
       6       6
     500  537.86
       6       6
     500  537.86
Pier Skew, UpSta & Num, DnSta & Num=  ,2272.01, 2 ,2272.01, 2 , 0 , 0 , 0 ,,
       6       6
     500  537.02
       6       6
     500  537.02
Pier Skew, UpSta & Num, DnSta & Num=  ,2362.01, 2 ,2362.01, 2 , 0 , 0 , 0 ,,
       6       6
     500  535.94
       6       6
     500  535.94
Pier Skew, UpSta & Num, DnSta & Num=  ,2452.01, 2 ,2452.01, 2 , 0 , 0 , 0 ,,
       6       6
     500  534.86
       6       6
     500  534.86
Pier Skew, UpSta & Num, DnSta & Num=  ,2535.01, 2 ,2535.01, 2 , 0 , 0 , 0 ,,
       6       6
     500  533.87
       6       6
     500  533.87
Pier Skew, UpSta & Num, DnSta & Num=  ,2598.01, 2 ,2598.01, 2 , 0 , 0 , 0 ,,
       6       6
     500  533.13
       6       6
     500  533.13
Abutment Skew #Up #Dn= , 3 , 3
  730.01  732.01  788.57
  535.98  535.98  517.13
  730.01  732.01  788.57
  535.98  535.98  517.13
BR Coef=-1 , 0 , 0 ,0.9, 0 ,,,0.8,-1,1.2,0,
WSPro=,,,, 1 ,,,, 0 ,,,, 0 ,,,,-1 ,-1 ,-1 , 0 , 0 , 0 , 0 , 0
BC Design=,, 0 ,, 0 ,,,,,,
BC Use User HTab Curves=0
BC User HTab FreeFlow(D)= 0

Type RM Length L Ch R = 1 ,241082.5,1,1,1
BEGIN DESCRIPTION:
Downstream TexRail Bridge
-----------------------------------------------
CDC FW030316-01TexRail Bridge
----------------------------------------------
END DESCRIPTION:
XS GIS Cut Line= 4
       2325743.3      6971270.59      2326235.09      6970622.93
      2326572.58      6969872.86      2326963.66      6969288.38
#Sta/Elev= 30
  439.17  542.49  615.71  539.25  698.49  529.21  746.21  517.35  868.61  520.81
  897.52  518.64  923.14  507.71  940.28  508.06  960.13  523.25  981.53   524.9
 1252.39  529.42 1270.63  529.34 1327.04  514.83 1540.75  510.22 1568.71   500.7
 1578.65     492 1685.09     490 1791.09     490 1810.13  500.77 1876.82  523.88
 1908.38  523.91 1961.77  512.04 2010.13  507.37  2181.9  502.91 2369.12  505.44
  2412.8  507.58 2472.57  519.33 2657.87  523.36 2719.56  536.78 2778.18  537.43
#Mann= 7 ,-1,0
  439.17     .06       0 1540.75     .02       0 1568.71     .03       0
 1578.65    .035       0 1791.09     .03       0 1810.13     .02       0
 1876.82     .06       0
#XS Ineff= 4 ,-1
  439.16 1370.34     550 2729.792778.178     550 2002.67  2045.5     550
  2045.5 2729.79     505
Permanent Ineff=
       F       F       F       T
Bank Sta=1540.75,1876.82
XS Rating Curve= 0 ,0
Exp/Cntr=0.3,0.1

Type RM Length L Ch R = 1 ,241081.5,126.43,54.8,4.75
XS GIS Cut Line= 5
      2325744.09      6971271.19      2326235.95      6970623.44
      2326573.45      6969873.35      2326866.36      6969442.17
       2326964.5      6969288.92
#Sta/Elev= 30
  439.17  542.49  615.71  539.25  698.49  529.21  746.21  517.35  868.61  520.81
  897.52  518.64  923.14  507.71  940.28  508.06  960.13  523.25  981.53   524.9
 1252.39  529.42 1270.63  529.34 1327.04  514.83 1540.75  510.22 1573.01  498.64
 1575.36  492.25 1685.09     490 1791.09     490 1812.31   503.8 1876.82  523.88
 1908.38  523.91 1961.77  512.04 2010.13  507.37  2181.9  502.91 2369.12  505.44
  2412.8  507.58 2472.57  519.33 2657.87  523.36 2719.56  536.78 2778.18  537.43
#Mann= 3 ,0,0
  439.17     .06       0 1540.75    .035       0 1876.82     .06       0
#XS Ineff= 4 ,-1
  439.16 1370.34     550 2729.792778.178     550 2002.67  2045.5     550
  2045.5 2729.79     505
Permanent Ineff=
       F       F       F       T
Bank Sta=1540.75,1876.82
XS Rating Curve= 0 ,0
Exp/Cntr=0.3,0.1

Type RM Length L Ch R = 1 ,241026.7,234.18,212,210.43
BEGIN DESCRIPTION:
Samuels Ave North Valley Storage Site in LOB.
Samuels Ave South Valley Storage Site in ROB - proposed land use is maintained grass and water feature.
Ineffective flow in LOB.
Landfills in LOB.
Effective flow limit in ROB set at West Fork Levee Loop.
Ineffective flow in ROB due to Union Pacific Railroad bridge.
END DESCRIPTION:
XS GIS Cut Line= 6
2326404.246944526972723.905171112326412.935689586972370.01181753
2326460.891361096970416.773082212326481.512295936969997.42019941
2326900.430244586969269.33575554 2326904.00998956969263.11411573
#Sta/Elev= 30
       0  538.77  113.28     538  243.78  528.94  320.63     518  404.55     525
  604.38  529.57  632.92     526  866.04     527   891.2     524  902.04     518
  929.25     527 1101.11     531 1632.34   530.5 1744.98     530 1792.87     514
  1977.2     510    2035     497 2113.94     494 2223.34     495  2242.5  498.98
 2310.24   524.8 2370.42  523.86  2435.6  515.39 2692.75  507.75 2830.79  510.51
 2894.48  519.86 3060.58  521.02 3109.33  524.99 3153.23  536.89  3222.4  537.28
#Mann= 4 ,-1,0
       0      .1       0 1632.34     .06       0  1977.2    .035       0
 2310.24     .06       0
#XS Ineff= 3 ,-1
       0 1681.97     550    2401    2458     550 3013.89 3213.69     550
Permanent Ineff=
       F       F       F
Bank Sta=1977.2,2310.24
XS Rating Curve= 0 ,0
Exp/Cntr=0.3,0.1