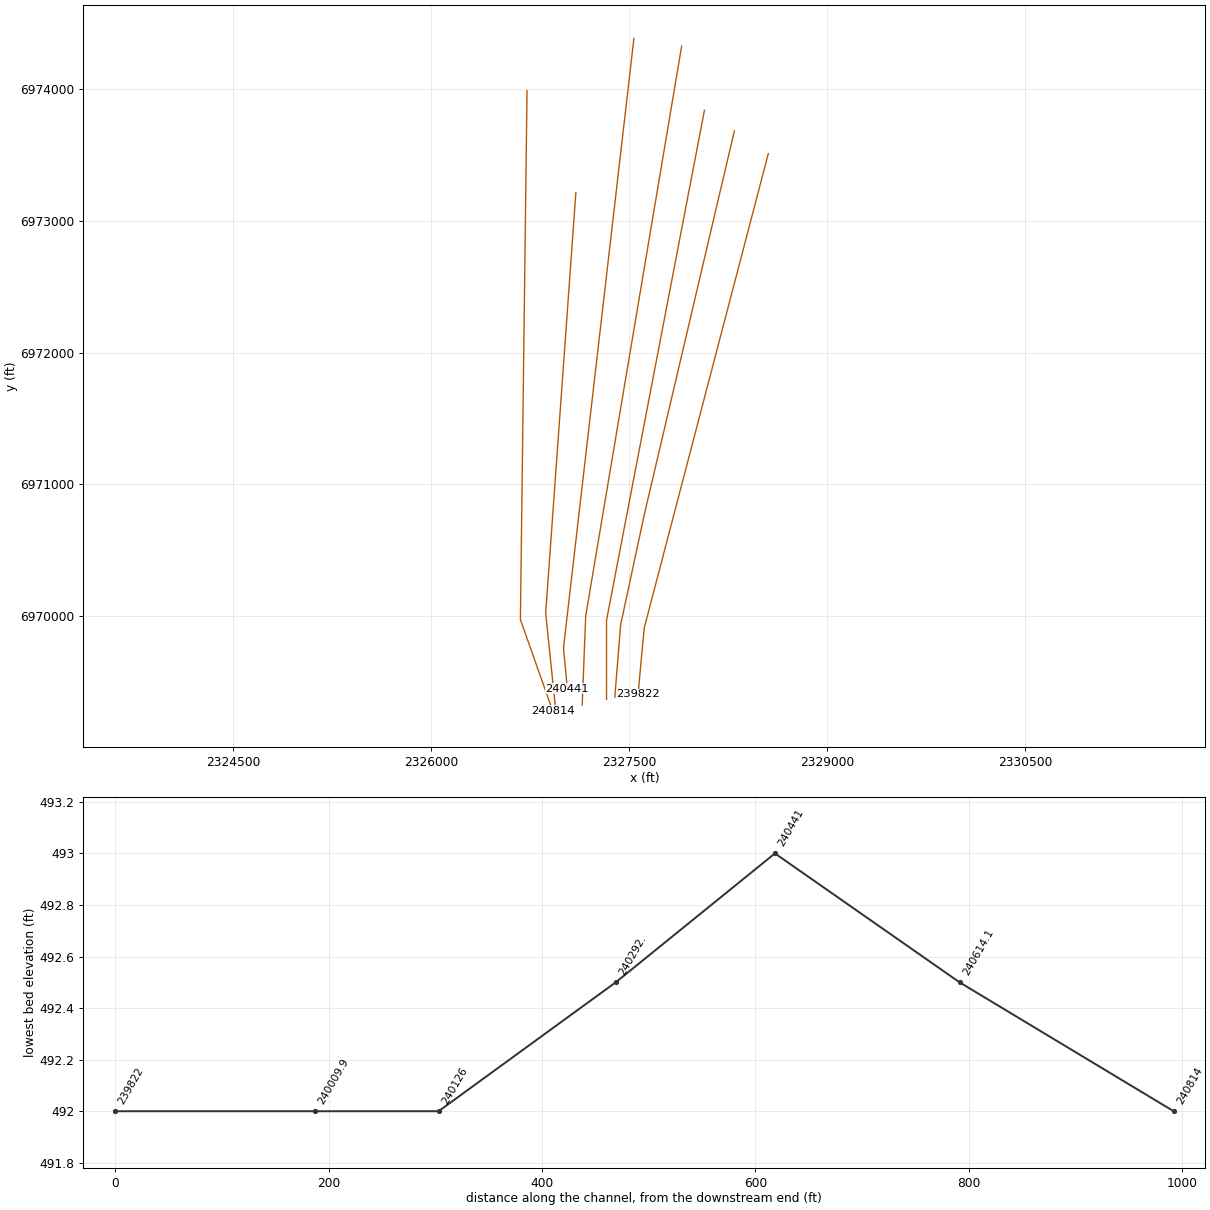
HEC-RAS study CDC_Consolidated_Model.prj: Upper Trinity CDC Consolidated Model

--- CDC_Consolidated_Model.g11 (geometry) --- (continued)

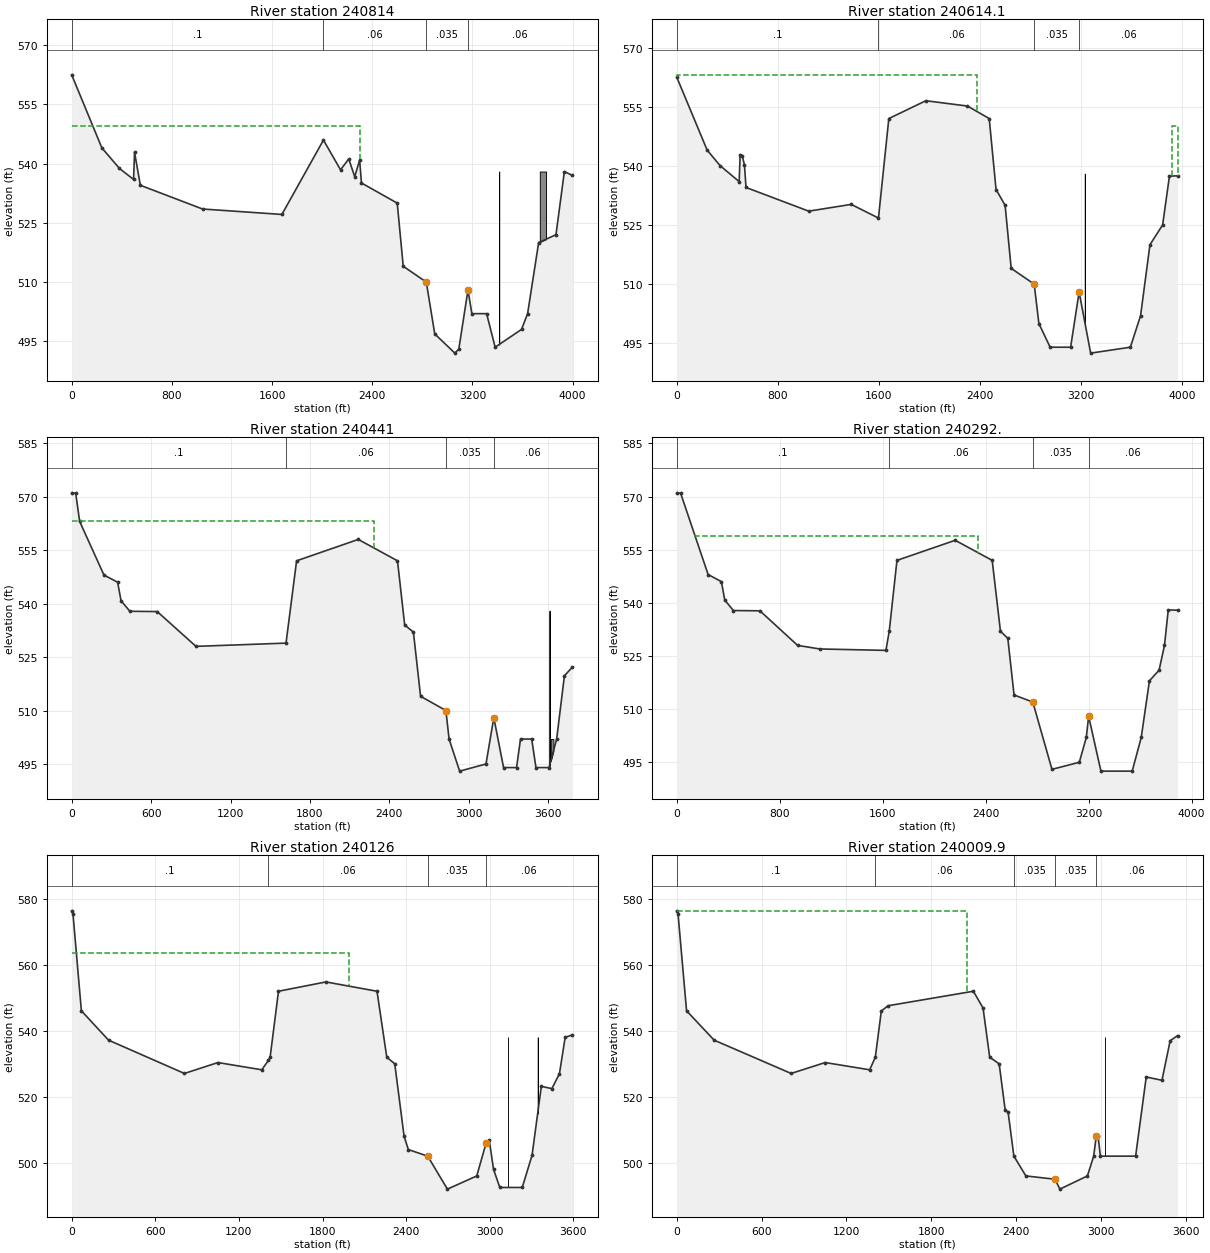
Type RM Length L Ch R = 1 ,240814  ,221.56,200.58,199.1
BEGIN DESCRIPTION:
Interpolated Section.
Samuels Ave North Valley Storage Site in LOB.
Samuels Ave South Valley Storage Site in ROB - proposed land use is maintained grass and water feature.
Wake Park in ROB.  Pylon and building represented as blocked obstructions.
END DESCRIPTION:
XS GIS Cut Line= 4
2326727.240658176973986.05868399  2326711.9599876972766.15438402
2326676.989077026969974.316056282326921.784928266969280.72778948
#Sta/Elev= 30
       0   562.5  240.59     544   381.4  538.78  494.14     536  501.79  542.88
  548.21  534.52 1044.58  528.51 1678.51  527.13 2010.37  545.98 2146.75  538.44
 2212.23  541.18 2260.19   536.7 2299.35  540.89 2313.86   535.1 2599.47     530
 2647.43     514 2831.56     510 2899.11  496.87 3059.54     492 3091.11     493
 3164.54     508  3195.6     502 3313.42     502 3381.32   493.5 3591.95     498
 3640.68     502  3728.8     520  3867.2     522  3934.2     538 3999.02     537
#Mann= 4 ,-1,0
       0      .1       0 2010.37     .06       0 2831.56    .035       0
 3164.54     .06       0
#XS Ineff= 2 , 0
         2298.97  549.55
Permanent Ineff=
       F       F
#Block Obstruct= 2 ,-1
    34123414.125     538    3738    3788     538
Bank Sta=2831.56,3164.54
XS Rating Curve= 0 ,0
Exp/Cntr=0.3,0.1

Type RM Length L Ch R = 1 ,240614.1,188.73,173,160.36
BEGIN DESCRIPTION:
Samuels Ave North Valley Storage Site in LOB.
Samuels Ave South Valley Storage Site in ROB - proposed land use is maintained grass and water feature.
Ineffective flow in LOB.
Landfills in LOB.
Effective flow limit in ROB set at West Fork Levee Loop.
Ineffective flow in ROB due to Union Pacific Railroad bridge.
Wake Park in ROB.  Pylon represented as blocked obstructions.
END DESCRIPTION:
XS GIS Cut Line= 4
     2327097.343     6973213.822     2326868.427     6970022.865
     2326944.732     6969287.557 2326947.3140925 6969262.6748392
#Sta/Elev= 30
       0   562.5  240.59     544  342.91  540.06  494.14     536  501.79  542.88
  517.19  542.62  535.69   540.3  548.21  534.52 1044.58  528.51 1380.77  530.23
 1596.45  526.76 1678.52     552 1971.65  556.52 2301.12  555.17 2473.01     552
 2527.08     534 2598.82     530 2646.89     514 2829.09     510 2866.11     500
 2955.36     494 3117.31     494 3184.55     508 3275.85   492.5 3590.24     494
 3670.96     502 3745.18     520 3845.38     525 3899.37  537.38 3963.43  537.48
#Mann= 4 ,-1,0
       0      .1       0 1596.45     .06       0 2829.09    .035       0
 3184.55     .06       0
#XS Ineff= 2 ,-1
     .18 2373.85563.0907 3921.38 3963.43     550
Permanent Ineff=
       F       F
#Block Obstruct= 1 ,-1
    32293231.125     538
Bank Sta=2829.09,3184.55
XS Rating Curve= 0 ,0
Exp/Cntr=0.3,0.1

Type RM Length L Ch R = 1 ,240441  ,162.73,149.17,138.28
BEGIN DESCRIPTION:
Interpolated Section.
Samuels Ave North Valley Storage Site in LOB.
Samuels Ave South Valley Storage Site in ROB - proposed land use is maintained grass and water feature.
Wake Park in ROB.  Pylon and dock represented as blocked obstructions.
END DESCRIPTION:
XS GIS Cut Line= 4
2327537.345486556974383.714760672327399.71974719 6973191.6329028
2327003.383631786969758.662478762327032.603267796969449.76907768
#Sta/Elev= 30
       0  571.07   30.18  570.95   60.06  563.05  243.73     548  346.92     546
  372.97  540.79  439.74  537.84  646.21  537.76  939.01     528 1619.57  528.91
 1699.43     552 2165.61     558  2461.9     552 2516.13     534 2582.07     532
 2636.31     514  2827.7     510  2851.7     502 2931.45     493  3130.6     495
 3189.76     508 3263.47     494 3361.53     494 3391.53     502 3475.91     502
 3508.27     494 3606.97     494 3664.72     502  3723.2  519.74 3784.27  522.21
#Mann= 4 ,-1,0
       0      .1       0 1619.57     .06       0  2827.7    .035       0
 3189.76     .06       0
#XS Ineff= 2 , 0
         2287.84  563.12
Permanent Ineff=
       F       F
#Block Obstruct= 2 ,-1
    36103612.125     538    3620    3640     502
Bank Sta=2827.7,3189.76
XS Rating Curve= 0 ,0
Exp/Cntr=0.3,0.1

Type RM Length L Ch R = 1 ,240292. ,173.83,166,157.96
BEGIN DESCRIPTION:
Samuels Ave North Valley Storage Site in LOB.
Samuels Ave South Valley Storage Site in ROB - proposed land use is maintained grass and water feature.
Ineffective flow in LOB.
Landfills in LOB.
Effective flow limit in ROB set at West Fork Levee Loop.
Wake Park in ROB.
END DESCRIPTION:
XS GIS Cut Line= 4
2327898.898212456974323.908299262327704.825992726973170.11630175
2327171.782617946970001.083758062327145.418089126969326.14100832
#Sta/Elev= 30
       0  571.07   30.18  570.95  243.73     548  346.92     546  372.97  540.79
  439.74  537.84  646.21  537.76  939.01     528 1110.51  526.99 1625.05  526.59
 1650.75     532 1710.75     552 2163.17  557.67 2450.56     552  2514.7     532
 2571.89     530  2620.4     514 2766.09     512 2914.84     493  3127.4     495
 3181.65     502 3199.76     508 3295.27   492.5 3538.32   492.5 3608.39     502
 3672.21     518 3747.05     521 3789.07     528 3818.27     538 3890.36  537.94
#Mann= 4 ,-1,0
       0      .1       0 1650.75     .06       0 2766.09    .035       0
 3199.76     .06       0
#XS Ineff= 1 ,-1
  130.89 2342.88558.9566
Permanent Ineff=
       F
Bank Sta=2766.09,3199.76
XS Rating Curve= 0 ,0
Exp/Cntr=0.3,0.1

Type RM Length L Ch R = 1 ,240126  ,121.59,116.11,110.49
BEGIN DESCRIPTION:
Interpolated Section.
Samuels Ave North Valley Storage Site in LOB.
Samuels Ave South Valley Storage Site in ROB - proposed land use is maintained grass and water feature.
Wake Park in ROB.  Pylon represented as blocked obstructions.
END DESCRIPTION:
XS GIS Cut Line= 4
2328071.800304736973837.603820992327900.968333246972946.83705156
2327329.778056896969968.487549682327329.778056896969368.15486994
#Sta/Elev= 30
       0  576.38    9.03  575.49   69.39  546.07  264.37  537.17  808.83  527.07
 1049.54  530.38  1364.3  528.18 1411.63  531.03 1423.97     532 1483.97     552
 1824.17  554.82 2190.95     552 2261.04     532 2318.36     530  2385.4     508
 2415.78     504 2554.77     502 2696.33     492 2906.84     496 2974.16     506
 2996.29   506.9 3027.33     498 3072.27   492.5 3233.27   492.5 3303.65  502.25
 3370.28  523.16 3445.95  522.47 3500.24     527 3541.29     538 3593.84  538.79
#Mann= 4 ,-1,0
       0      .1       0 1411.63     .06       0 2554.77    .035       0
 2974.16     .06       0
#XS Ineff= 2 , 0
         1990.41   563.6
Permanent Ineff=
       F       F
#Block Obstruct= 2 ,-1
    31293131.125     538    33443346.125     538
Bank Sta=2554.77,2974.16
XS Rating Curve= 0 ,0
Exp/Cntr=0.3,0.1

Type RM Length L Ch R = 1 ,240009.9,193.93,187,174
BEGIN DESCRIPTION:
Samuels Ave North Valley Storage Site in LOB.
Samuels Ave South Valley Storage Site in ROB - proposed land use is maintained grass and water feature.
Ineffective flow in LOB.
Landfills in LOB.
Effective flow limit in ROB set at West Fork Levee Loop.
Wake Park in ROB.  Pylon represented as blocked obstructions.
END DESCRIPTION:
XS GIS Cut Line= 5
2328298.491738596973680.994090462328103.464342316972849.56140244
2327616.592825646970773.950993112327436.623683456969934.24662904
2327392.499580936969385.25860702
#Sta/Elev= 30
       0  576.38    9.03  575.49   69.39  546.07  264.37  537.17  808.83  527.07
 1049.54  530.38  1364.3  528.18 1404.15     532 1446.55     546 1493.97   547.6
 2097.38     552 2165.75  546.92 2212.86     532 2279.77     530 2322.25     516
    2343  515.33 2383.85     502 2468.73     496  2674.9     495 2709.04     492
 2903.78     496 2948.13     502 2966.22     508 2979.22     508 2995.73     502
 3244.68     502 3319.73     526 3430.91     525 3488.88     537 3540.99  538.53
#Mann= 5 ,-1,0
       0      .1       0 1404.15     .06       0 2383.85    .035       0
  2674.9    .035       0 2966.22     .06       0
#XS Ineff= 1 ,-1
     .06 2053.48576.3792
Permanent Ineff=
       F
#Block Obstruct= 1 ,-1
    30273029.125     538
Bank Sta=2674.9,2966.22
XS Rating Curve= 0 ,0
Exp/Cntr=0.3,0.1

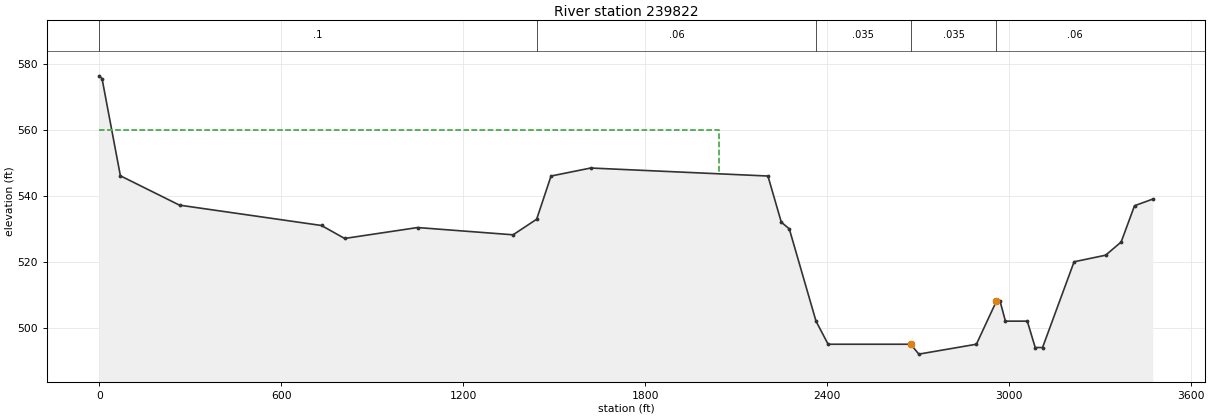
Type RM Length L Ch R = 1 ,239822  ,227.06,218.95,203.73
BEGIN DESCRIPTION:
Interpolated Section.
Samuels Ave North Valley Storage Site in LOB.
Samuels Ave South Valley Storage Site in ROB - proposed land use is maintained grass and water feature.
Wake Park in ROB.
END DESCRIPTION:
XS GIS Cut Line= 4
2328555.828313416973509.109578132328355.589255416972742.84048724
2327615.373195076969910.202872572327568.745401536969408.95415689
#Sta/Elev= 30
       0  576.38    9.03  575.49   69.39  546.07  264.37  537.17  732.62     531
  808.83  527.07 1049.54  530.38  1364.3  528.18 1442.04   532.9 1489.52     546
 1620.49  548.43  2204.7     546  2248.8     532 2275.05     530 2363.25     502
 2403.14     495  2675.5     495 2702.26     492 2892.09     495 2957.82     508
 2970.29     508 2987.83     502 3059.95     502 3086.08     494 3110.29     494
 3214.26     520 3318.38     522 3369.49     526 3413.56     537 3473.63     539
#Mann= 5 ,-1,0
       0      .1       0 1442.04     .06       0 2363.25    .035       0
  2675.5    .035       0 2957.82     .06       0
#XS Ineff= 2 , 0
         2042.22  560.06
Permanent Ineff=
       F       F
Bank Sta=2675.5,2957.82
XS Rating Curve= 0 ,0
Exp/Cntr=0.3,0.1