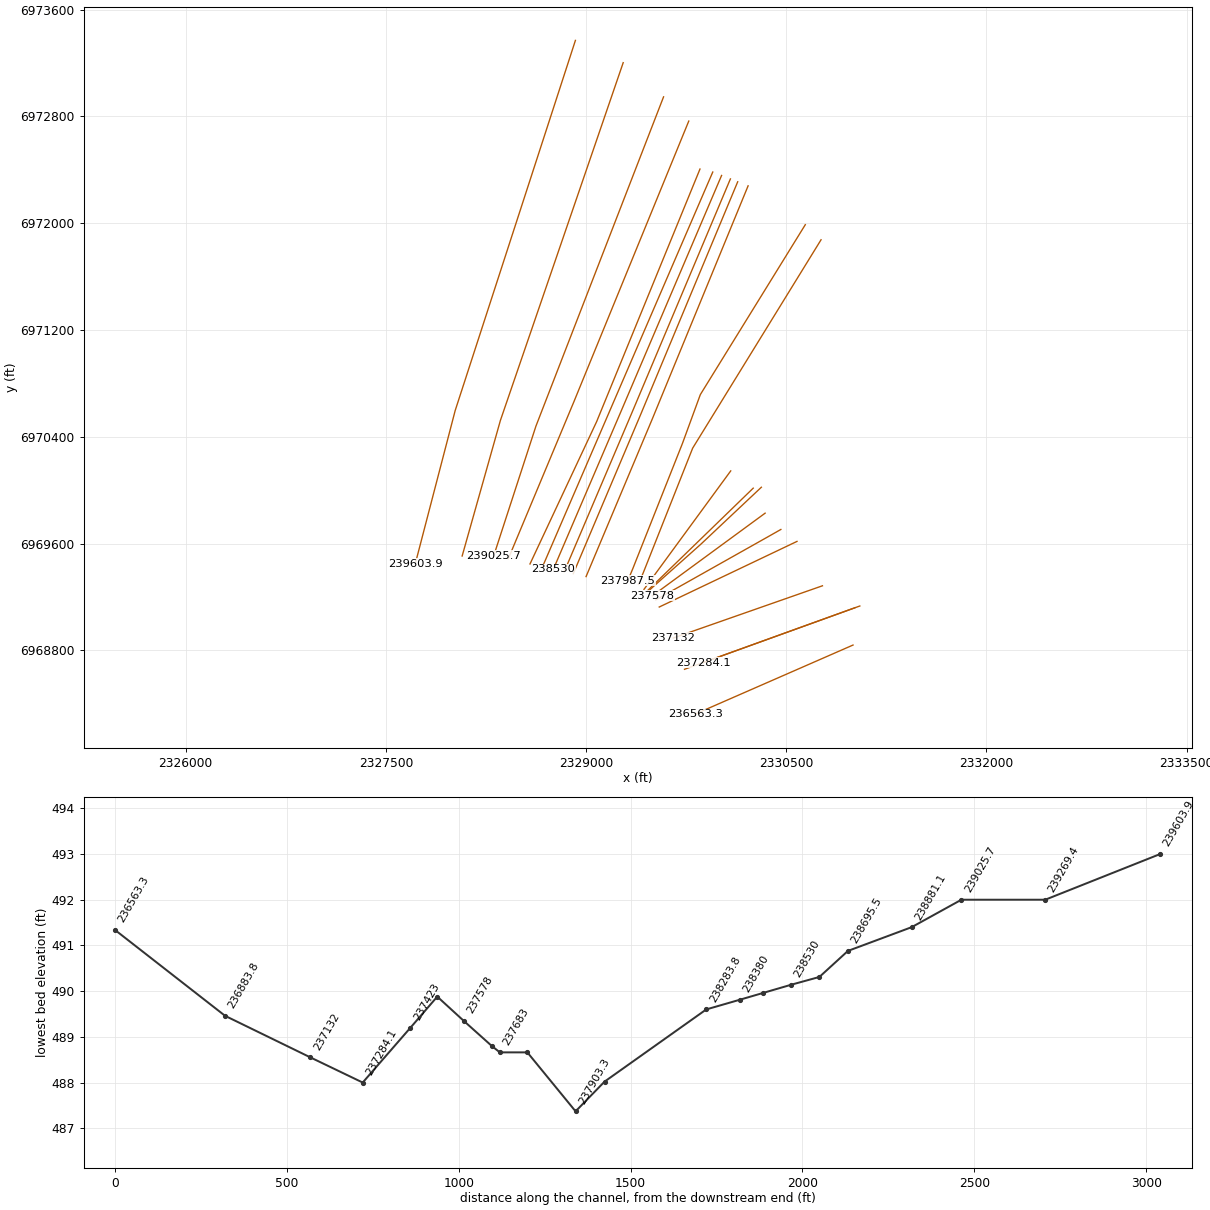
HEC-RAS study CDC_Consolidated_Model.prj: Upper Trinity CDC Consolidated Model

--- CDC_Consolidated_Model.g11 (geometry) --- (continued)

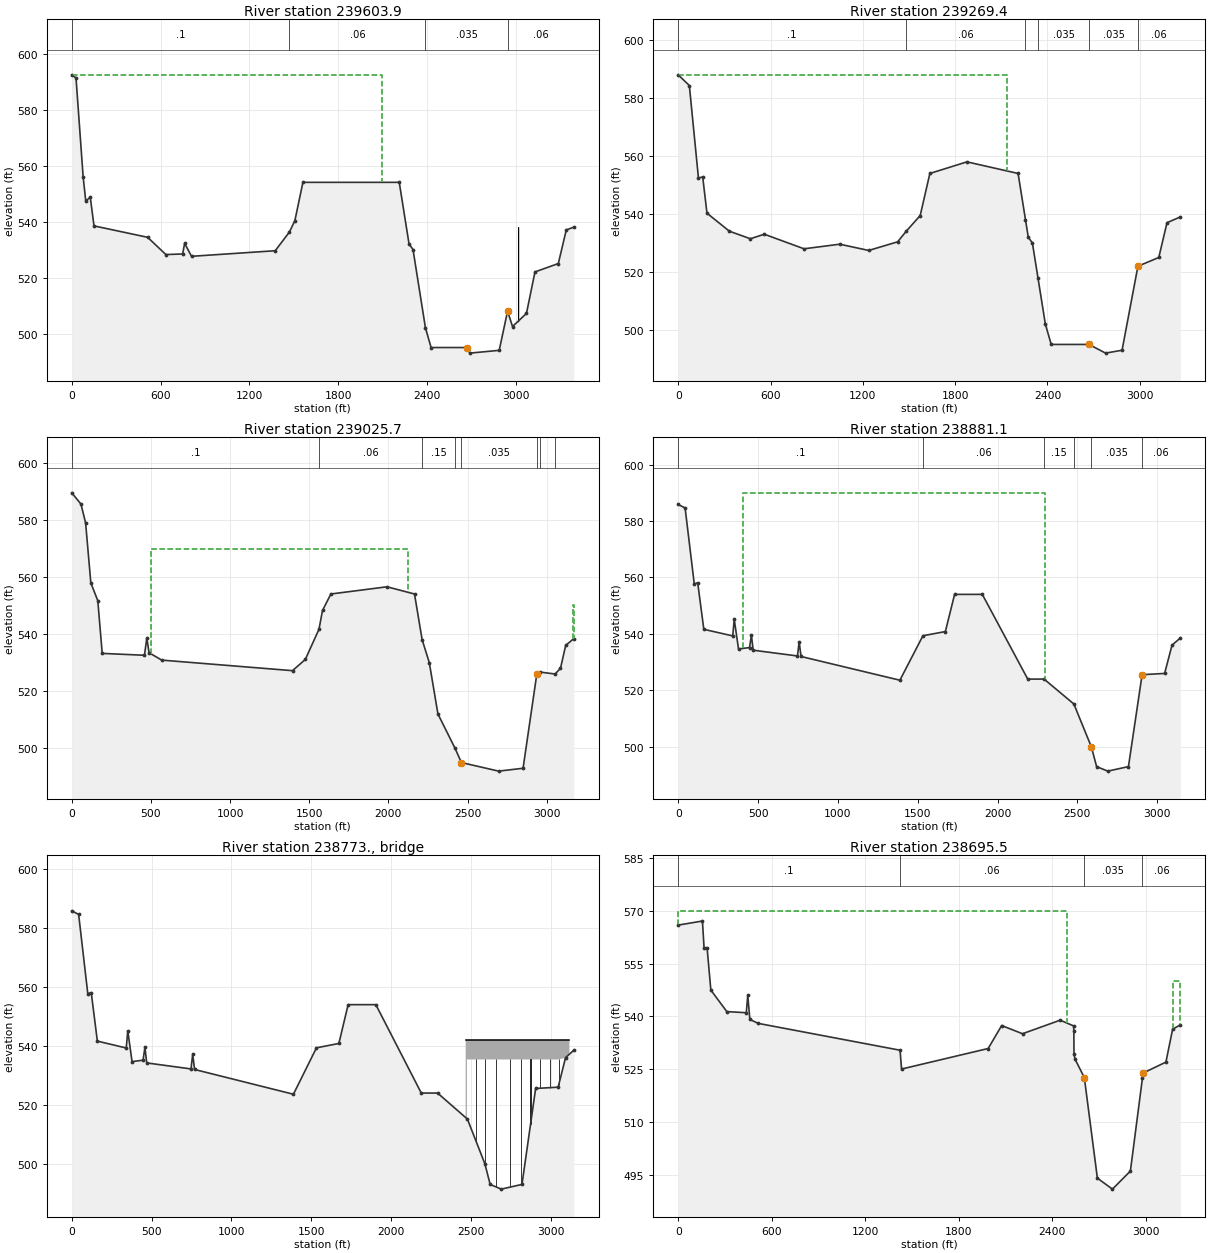
Type RM Length L Ch R = 1 ,239603.9,341.97,334.47,328.79
BEGIN DESCRIPTION:
Samuels Ave North Valley Storage Site in LOB.
Samuels Ave South Valley Storage Site in ROB - proposed land use is maintained grass and water feature.
Ineffective flow in LOB.
Landfills in LOB.
Effective flow limit in ROB set at West Fork Levee Loop.
Wake Park in ROB.  Pylon represented as blocked obstruction.
END DESCRIPTION:
XS GIS Cut Line= 4
2328920.470172366973369.383485772328700.81341262 6972693.1646544
2328019.835254676970596.756354882327720.982597466969449.52839294
#Sta/Elev= 30
       0  592.39   28.65  591.32    76.7  556.02    94.4  547.37  124.95  548.65
  150.21  538.44  512.34  534.37  635.29  528.21  748.72  528.41  762.14  532.22
  808.66  527.58 1373.96  529.57 1469.89  536.27 1506.63  540.32 1560.91     554
 2211.49     554 2277.54  532.01 2304.37     530 2388.48     502 2426.53     495
 2669.57     495 2687.91     493 2886.57     494 2943.01     508 2976.34   502.5
 3070.61  507.19 3127.92     522  3285.7     525  3339.4     537  3390.5     538
#Mann= 4 ,-1,0
       0      .1       0 1469.89     .06       0 2388.48    .035       0
 2943.01     .06       0
#XS Ineff= 1 ,-1
     -.1 2093.29592.3987
Permanent Ineff=
       F
#Block Obstruct= 1 ,-1
    30133015.125     538
Bank Sta=2669.57,2943.01
XS Rating Curve= 0 ,0
Exp/Cntr=0.3,0.1

Type RM Length L Ch R = 1 ,239269.4,258.18,243.8,233.51
BEGIN DESCRIPTION:
Samuels Ave North Valley Storage Site in LOB.
Samuels Ave South Valley Storage Site in ROB - proposed land use is maintained grass and water feature.
Ineffective flow in LOB.
Landfills in LOB.
Effective flow limit in ROB set at West Fork Levee Loop.
END DESCRIPTION:
XS GIS Cut Line= 4
2329278.449568216973202.453033612329074.892048096972609.41565199
2328358.420799916970522.073298922328071.918587436969506.49517418
#Sta/Elev= 30
       0  588.02    72.2  584.35  131.34  552.44  159.12  552.79  186.78  540.29
  332.43  534.07   468.8  531.47  559.35  533.03  817.67     528 1049.81  529.59
    1238  527.43 1426.32  530.41 1481.01     534 1572.76  539.49 1635.58     554
 1876.68     558 2209.03     554 2257.16     538 2275.21     532 2302.03     530
 2338.13     518 2386.25     502 2424.35     495 2670.08     495 2777.78     492
 2884.85     493 2988.01     522 3123.52     525 3176.88     537 3263.45     539
#Mann= 6 ,-1,0
       0      .1       0 1481.01     .06       0 2257.16     .15       0
 2338.13    .035       0 2670.08    .035       0 2988.01     .06       0
#XS Ineff= 1 ,-1
       0  2138.5588.0345
Permanent Ineff=
       F
Bank Sta=2670.08,2988.01
XS Rating Curve= 0 ,0
Exp/Cntr=0.3,0.1

Type RM Length L Ch R = 1 ,239025.7,174.33,144.59,122.1
BEGIN DESCRIPTION:
Samuels Ave North Valley Storage Site in LOB.
Samuels Ave South Valley Storage Site in ROB - proposed land use is maintained grass and water feature.
Ineffective flow in LOB.
Landfills in LOB.
Effective flow limit in ROB set at West Fork Levee Loop.
END DESCRIPTION:
XS GIS Cut Line= 4
 2329580.92686746972946.530873832329400.582541036972481.26006672
2328624.550463186970479.172845722328308.013162816969506.69403826
#Sta/Elev= 30
       0  589.41   58.29  585.45   87.55  578.82  120.48  557.86   164.4  551.66
   192.3  533.21  459.11  532.55  474.14   538.6   488.2  533.44  568.39  530.86
 1394.47  527.16 1475.58  531.11 1561.86  541.69 1583.96  548.23 1636.86     554
 1991.48  556.52 2165.13     554 2213.32     538 2258.49     530 2313.17     512
 2421.21  499.99 2461.45     495 2696.72     492 2850.97     493 2937.85     526
  2960.8  526.65 3052.99     526 3087.34     528 3120.14     536 3171.71   538.4
#Mann= 8 ,-1,0
       0      .1       0 1561.86     .06       0 2213.32     .15       0
 2421.21    .035       0 2461.45    .035       0 2937.85     .06       0
  2960.8     .15       0 3052.99     .06       0
#XS Ineff= 2 , 0
     499 2125.54   569.9 3166.49     499     550
Permanent Ineff=
       F       T
Bank Sta=2461.45,2937.85
XS Rating Curve= 0 ,0
Exp/Cntr=0.3,0.1

Type RM Length L Ch R = 1 ,238881.1,201.79,185.56,175.91
BEGIN DESCRIPTION:
**********************************************
CDC FW090808-01 Fort Worth Central City
Cross-section 238881.1 - 241026.7
**********************************************
Samuels Ave North Valley Storage Site in LOB.
Samuels Ave South Valley Storage Site in ROB - proposed land use is maintained grass and water feature.
Upstream of Northside Drive.
Ineffective flow in LOB.
Landfills in LOB.
Effective flow limit in ROB set at West Fork Levee Loop.
END DESCRIPTION:
XS GIS Cut Line= 4
2329769.724839736972765.002489042329616.311437996972390.18342847
 2328910.93898356970666.820034182328417.44207788 6969485.2073835
#Sta/Elev= 30
       0  585.84   43.07  584.61  100.43   557.7  121.94  558.11   160.3  541.63
  341.27  539.29   350.9  545.14  377.59  534.67  446.56  535.16  458.36  539.54
  469.42  534.23  746.92  532.19  757.46  537.19  769.27     532 1388.45   523.6
 1532.85  539.35 1673.24  540.83 1731.24     554 1904.74     554 2189.42     524
 2291.71     524 2478.26  515.18 2587.87     500 2620.92     493 2690.56   491.4
 2820.22     493 2905.82  525.56 3046.85     526  3093.1     536 3145.13  538.56
#Mann= 6 ,-1,0
       0      .1       0 1532.85     .06       0 2291.71     .15       0
 2478.26    .035       0 2587.87    .035       0 2905.82     .06       0
#XS Ineff= 2 , 0
     405 2296.94  589.97             405
Permanent Ineff=
       F       F
Bank Sta=2587.87,2905.82
XS Rating Curve= 0 ,0
Exp/Cntr=0.5,0.3

Type RM Length L Ch R = 3 ,238773. ,,,
BEGIN DESCRIPTION:
Northside Drive
Bridge length 632 feet.
Data from USACE 1975 survey.
Note:  Internal bridge cross-sections modified to represent geometry under bridge.
END DESCRIPTION:
Node Name=Northside Drive
Bridge Culvert--1,0,-1,-1, 0
Deck Dist Width WeirC Skew NumUp NumDn MinLoCord MaxHiCord MaxSubmerge Is_Ogee
76.6,63,2.6,0, 6, 6, , , 0.95, 0, 0,0,,
 2467.47 2475.47 2475.47 3107.47 3107.47 3117.42
     542     542     542     542     542     542
     450     450   535.4   535.4     450     450
 2541.47 2549.47 2549.47 3181.47 3181.47 3191.42
     542     542     542     542     542     542
     450     450   535.4   535.4     450     450
Pier Skew, UpSta & Num, DnSta & Num=  ,2532.47, 2 ,2591, 2 , 0 , 0 , 0 ,,
     2.5     2.5
     450     540
     2.5     2.5
     450     540
Pier Skew, UpSta & Num, DnSta & Num=  ,2588.47, 2 ,2662.47, 2 , 0 , 0 , 0 ,,
     2.5     2.5
     450     540
     2.5     2.5
     450     540
Pier Skew, UpSta & Num, DnSta & Num=  ,2658.47, 2 ,2732.47, 2 , 0 , 0 , 0 ,,
     2.5     2.5
     450     540
     2.5     2.5
     450     540
Pier Skew, UpSta & Num, DnSta & Num=  ,2744.47, 2 ,2818.47, 2 , 0 , 0 , 0 ,,
     2.5     2.5
     450     540
     2.5     2.5
     450     540
Pier Skew, UpSta & Num, DnSta & Num=  ,2813.97, 2 ,2887.97, 2 , 0 , 0 , 0 ,,
     2.5     2.5
     450     540
     2.5     2.5
     450     540
Pier Skew, UpSta & Num, DnSta & Num=  ,2874.47, 2 ,2948.47, 2 , 0 , 0 , 0 ,,
     2.5     2.5
     450     540
     2.5     2.5
     450     540
Pier Skew, UpSta & Num, DnSta & Num=  ,2934.47, 2 ,3008.47, 2 , 0 , 0 , 0 ,,
     2.5     2.5
     450     540
     2.5     2.5
     450     540
Pier Skew, UpSta & Num, DnSta & Num=  ,2994.47, 2 ,3068.47, 2 , 0 , 0 , 0 ,,
     2.5     2.5
     450     540
     2.5     2.5
     450     540
Pier Skew, UpSta & Num, DnSta & Num=  ,3050.47, 2 ,3124.47, 2 , 0 , 0 , 0 ,,
     2.5     2.5
     450     540
     2.5     2.5
     450     540
Abutment Skew #Up #Dn= , 2 , 2
  2450.1  2475.1
   535.4     522
    2534    2559
   535.4     523
BR Coef=-1 , 0 , 0 ,, 0 ,,,0.8,-1,,0,
WSPro=,,,, 1 ,,,, 0 ,,,, 0 ,,,,-1 ,-1 ,-1 , 0 , 0 , 0 , 0 , 0
BR U #Sta/Elev= 498
       0  585.84   13.86  585.34   27.19  585.07   43.07  584.61   46.84  583.45
   47.25  583.31   48.01  583.09   48.63  582.88   49.14  582.74   49.85  582.51
   50.14  582.43   51.57     582   51.83  581.93    52.8  581.64   53.86  581.33
   54.43  581.14    54.7  581.06   57.86  579.86   60.26  578.88   61.27  578.54
   62.26  578.11   62.58     578   62.72     578   63.73  577.61   66.82  576.13
   67.35  575.86   76.26  572.03   76.86   571.8   79.45  570.64   83.66     568
   83.75  567.95   96.16  560.25  100.43   557.7  107.29   558.2  121.01  558.13
  121.53  558.11  121.94  558.11  135.75  552.25  136.49  551.95  137.72  551.44
  139.72     550  141.22  548.98   142.2  548.35  142.45  548.01  143.76  546.18
  144.21  545.53  152.58  544.12  152.96     544   159.1     542   160.3  541.63
  160.42  541.64  160.71   541.6  166.61  541.78  183.31     541  207.34  541.97
  242.95  542.07  271.55  541.54  272.28  541.52   283.7  541.43  290.72  541.29
  324.31  540.03  324.48  540.02  341.27  539.29   342.4     540   350.9  545.14
  358.95  540.09  361.69  538.39  368.69     536  368.98  535.89  371.72  534.97
  377.59  534.67  402.73  534.35  411.14  534.37   422.4  534.25  446.56  535.16
  454.56  538.23  458.36  539.54  469.42  534.23  480.31  534.26  523.24  534.87
  531.41  535.09  548.14  534.08  586.72  534.13  612.52  534.44  614.62  534.75
  625.75  535.87  632.96  533.62  681.54  533.26  746.92  532.19  747.51  532.46
  757.46  537.19  766.89  532.11  769.27     532  802.59  531.83  803.09  531.88
  803.66  531.83  868.99  530.56  917.49  530.08  917.79  530.07  940.86   529.8
  964.16  529.68  972.72  529.56  986.64  529.58  996.51  529.46 1012.55  528.95
 1029.96  528.85 1039.86  528.54 1057.85  528.14  1090.7  526.98  1097.3   526.6
 1104.72     526 1119.21  524.99 1124.78  525.18 1127.88  525.18  1132.8  524.91
 1154.15   524.4 1156.65  524.23 1164.26     524  1173.3  523.96 1173.78   523.9
 1175.99  523.82 1184.64  523.77  1185.2  523.75 1212.88  523.78 1215.25  523.82
 1220.21     524 1224.66     524  1239.1  525.19 1244.68  525.47  1263.5  524.94
 1272.46  524.78  1293.1  524.95 1294.12  524.94 1308.26  525.36 1328.42  524.64
 1346.72  524.74 1352.91  524.61 1359.61  524.52 1388.45   523.6 1399.25  524.62
 1399.65  524.67 1419.99  526.66 1421.12  526.79 1425.62   527.2 1427.05  527.36
 1431.58  527.74 1433.99     528 1434.18     528 1439.53  528.61 1440.65   528.7
 1446.05  529.37 1446.47  529.41 1446.82  529.43 1452.99   530.1 1454.67  530.28
 1454.93  530.32  1456.2  530.45 1456.62  530.51 1460.77  530.92 1461.65  531.03
  1470.8     532 1470.92  532.01 1474.97  532.56 1475.56  532.63 1476.91  532.82
 1477.84  532.92  1479.2   533.1 1487.33  534.02  1489.5  534.18 1489.58  534.18
 1512.16  535.23 1513.18  535.27 1526.96   535.9 1527.64  535.94 1529.72  536.09
 1529.82  536.09 1537.45  536.64 1553.94     538 1560.35  538.43 1573.51  539.72
 1573.61  539.72 1583.18  540.65 1594.85   541.6 1599.76  541.89 1599.88   541.9
 1603.14   542.1 1603.26   542.1 1606.26  542.28 1606.65  542.29 1608.55  542.39
 1636.19  543.11  1656.6   543.1 1677.05  542.73 1688.66  542.36  1689.6  542.35
 1693.36  542.24 1693.99  542.24 1703.86  541.98 1703.93  541.97 1717.75  541.66
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BR U #Mann= 5
       0      .1 1419.99     .06 2547.75    .035 2914.25     .06 3028.71     .06
BR U Banks=2547.75,2914.25
BR D #Sta/Elev= 481
       0  565.95   17.02  565.86   17.63  565.85   40.01  565.82   58.27  565.45
   78.96  565.42   79.79  565.41   91.14  565.49  108.87     566     109     566
  109.73  566.03  118.25  566.25   126.5  567.85  127.45     568  127.67  568.05
  131.79  568.01  131.93     568     133     568  136.57  567.79  144.02  566.77
  148.22  566.78  155.39   567.1  156.77  566.05   157.1  565.81  158.73  564.58
  163.12  561.32  164.97     560  165.66  559.52  165.73  559.46  171.19  559.03
   172.4  558.97  173.35  558.96  185.03  559.54  185.11  559.53  202.07  552.31
  202.61     552  204.81  550.79  206.19     550  207.34  549.39  207.52  549.29
  209.12  547.64  209.28  547.47   218.5  546.32   225.4  544.91   225.7  544.86
  240.66     544  241.03     544  242.84  543.91  300.87  541.75  303.39   541.7
  303.74   541.7  311.85  541.35  319.09   541.2  320.06   541.2  342.25  541.62
  345.84  541.59  352.64  541.71   353.8  541.79  360.68  541.93  363.55  541.94
  367.77  541.83  374.28  541.79  393.46   542.4  395.94  542.81  396.97  542.85
  404.37  542.59  404.98  542.54  416.53  542.05  417.42     542  417.64     542
  435.63  541.03  436.74  541.03  438.71     542  442.44     544   442.7  544.15
   446.1  545.99   454.9  541.47  459.72  539.13  464.89  538.92  468.01  538.86
  475.55  538.62  513.31     538  541.08  537.82  541.29  537.86  552.97  540.37
  565.71  538.05  565.74  537.94  566.58  538.03  595.68  538.04  597.12  538.02
  611.58  537.98  616.81  538.03  618.87  537.92  621.78   537.9  630.75  537.61
  649.35  537.24  686.13  536.74   716.1     536  743.37     536  791.71  534.56
  812.01  534.09   812.2  534.08  815.34     534  815.66     534  839.13  533.43
  844.77     536  844.84  536.03  847.16  537.12  848.11  537.55  857.53  534.59
  862.63     534  880.94     534  890.41  534.92  892.72  535.21  907.55     534
  933.71  533.39  964.42  532.93 1021.18  533.16 1023.03  533.23 1027.17  533.07
 1033.25  532.93 1074.28  533.42 1092.92  533.31 1126.07  532.92 1226.79  532.82
 1260.39     532 1276.01  531.28  1281.1  531.14 1296.78  531.03 1383.99  531.21
 1413.34  531.54 1420.73  530.66  1423.5  530.37 1423.77  530.34 1424.31     530
 1427.69     528 1428.26  527.71 1431.24     526 1431.54  525.85 1433.14  525.02
 1435.12  525.48 1444.03   527.4 1444.82  527.58 1445.81  527.79 1467.84   527.1
 1478.66  526.93 1500.98  527.32 1545.37  528.32 1579.68  528.63 1652.94  528.99
 1672.15  528.87 1707.06  529.31 1854.18  530.77 1892.93  530.74 1918.99  530.97
 1932.23  530.84 1956.81  531.13 1958.23  531.16  1971.6  530.93 1976.92   531.1
 1989.07  530.86 1989.68  530.88 1994.82  531.15 2003.93  531.33 2028.97  532.47
 2032.93   532.7 2043.69  534.87 2043.78  534.88  2048.5  535.79 2054.26  535.96
 2054.64  535.98 2055.21     536  2069.1  536.13 2069.71  536.13 2070.93  536.15
  2071.8  536.15 2087.18  536.38 2087.84  536.38 2088.72   536.4 2094.76  536.47
 2095.07  536.47 2108.26  536.72 2108.66  536.72 2108.85  536.73 2109.33  536.73
 2124.03     537 2124.56     537 2124.84  537.01 2129.47  537.09 2139.12   536.8
 2139.26   536.8 2140.43  536.77 2140.72  536.77 2154.51  536.43 2154.71  536.42
 2156.87  536.39 2157.26  536.38 2157.65  536.38 2166.88  536.19  2167.2  536.18
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BR D #Mann= 6
       0      .1 1423.77     .06 2621.75    .035 2710.81    .035 2988.25     .06
 3211.01     .06
BR D Banks=2621.75,2988.25
BC Design=,, 0 ,, 0 ,,,,,,
BC Use User HTab Curves=0
BC User HTab FreeFlow(D)= 0

Type RM Length L Ch R = 1 ,238695.5,83,83,108
BEGIN DESCRIPTION:
Downstream of Northside Drive.
Ineffective flow in LOB.
Effective flow limit in ROB set at West Fork Levee Loop.
END DESCRIPTION:
XS GIS Cut Line= 3
 2329853.7412212 6972405.5962385  2329079.821977 6970514.0104244
 2328580.2118806 6969446.9087421
#Sta/Elev= 30
       0  565.95  155.39   567.1  165.73  559.46  185.11  559.53  209.28  547.47
  311.85  541.35  436.74  541.03   446.1  545.99  459.72  539.13  513.31     538
  1423.5  530.37 1433.14  525.02 1989.07  530.86 2075.65  537.39  2209.3  535.06
  2451.1  538.91  2537.3  537.28  2538.8  535.85  2539.8  529.27  2546.1  527.86
    2605  522.69 2606.03522.6022 2689.84     494 2786.52  490.88 2901.68  496.01
 2979.38  522.56 2984.75  523.91 3129.65  526.99 3172.81  536.37 3222.05  537.55
#Mann= 4 ,-1,0
       0      .1       0  1423.5     .06       0    2605    .035       0
 2979.38     .06       0
#XS Ineff= 2 , 0
       0  2497.8     570 3175.48       0     550
Permanent Ineff=
       F       T
Bank Sta=2606.03,2984.75
XS Rating Curve= 0 ,0
Exp/Cntr=0.5,0.3

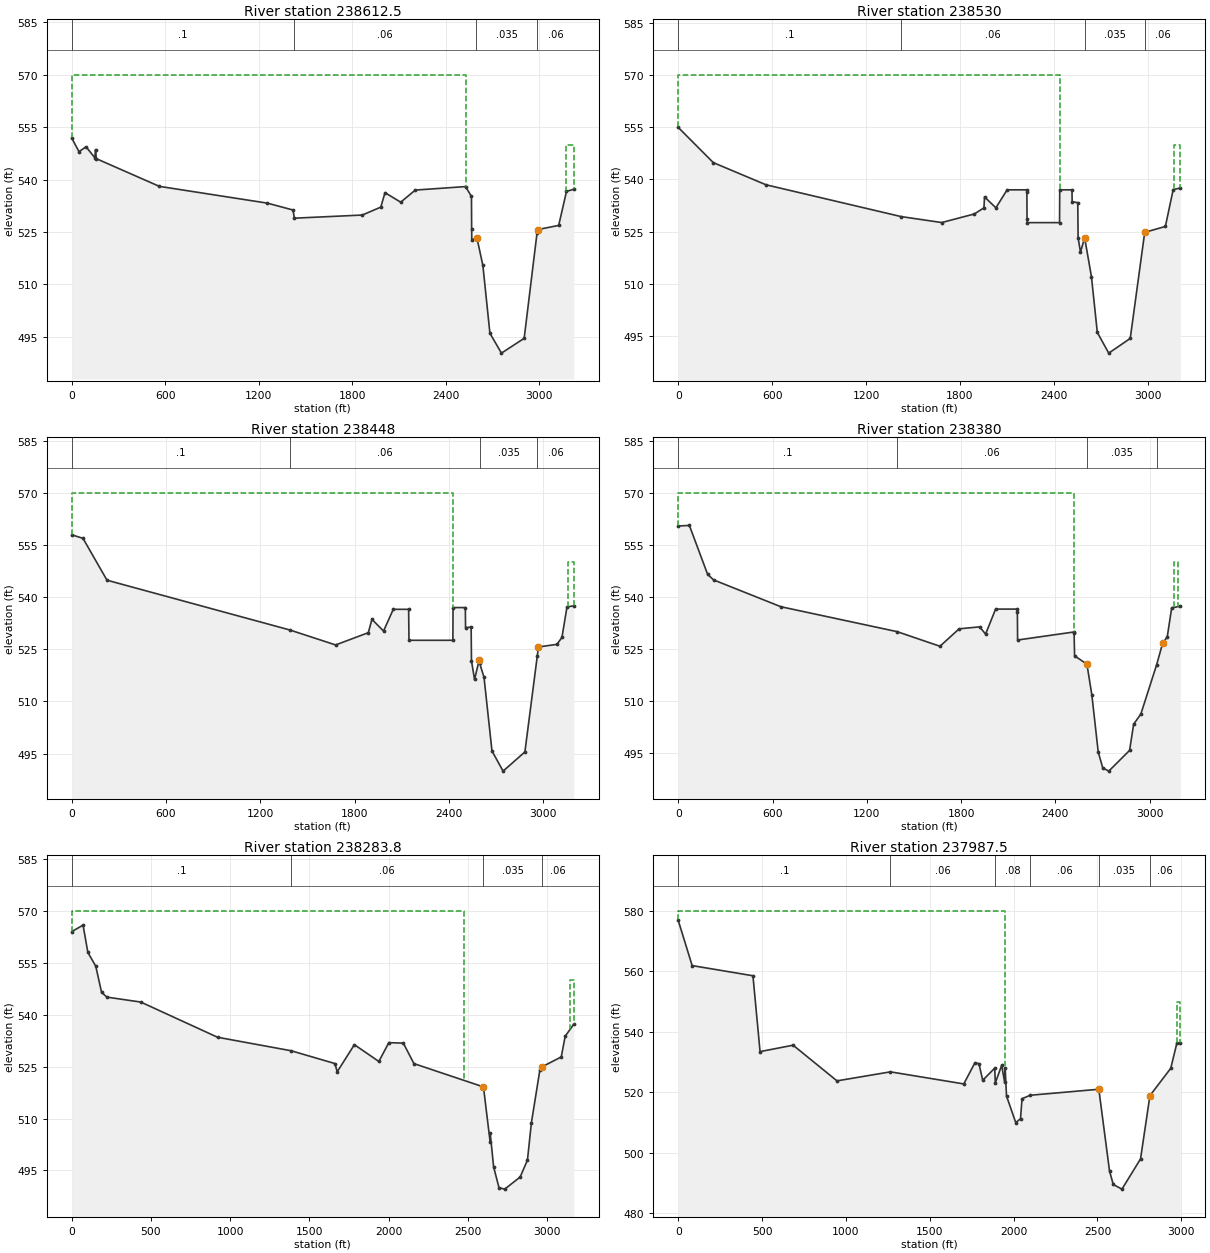
Type RM Length L Ch R = 1 ,238612.5,81.35,82,83.62
BEGIN DESCRIPTION:
Ineffective flow in LOB.
Effective flow limit in ROB set at West Fork Levee Loop.
END DESCRIPTION:
XS GIS Cut Line= 2
 2329949.4028821 6972383.1899346  2328673.554973 6969424.9456692
#Sta/Elev= 30
       0  551.88   46.36     548   91.64  549.39  148.08  546.25  152.76  548.58
  157.15     546  562.29  538.06 1255.04  533.26 1419.56  531.29 1428.48  528.95
 1864.03  529.85 1982.94  532.12 2009.99  536.26 2110.63  533.53 2204.29     537
 2526.65     538 2564.76  535.18 2565.85  525.79 2566.94  522.59  2595.3  523.38
 2599.61  523.32 2637.96  515.42 2683.09     496 2757.17  490.31 2902.93  494.55
 2985.11   524.6 2992.26  525.71 3124.46  526.88 3174.48  536.62 3221.65  537.24
#Mann= 4 ,-1,0
       0      .1       0 1428.48     .06       0  2595.3    .035       0
 2985.11     .06       0
#XS Ineff= 2 , 0
       0 2526.65     570 3174.25       0     550
Permanent Ineff=
       F       T
Bank Sta=2599.61,2992.26
XS Rating Curve= 0 ,0
Exp/Cntr=0.3,0.1

Type RM Length L Ch R = 1 ,238530  ,81.35,82,83.62
XS GIS Cut Line= 3
  2330015.475209 6972357.3917064 2329268.3403982 6970604.6002469
 2328755.0668875 6969406.8314685
#Sta/Elev= 30
       0  554.91  223.99  544.81  560.71  538.45 1424.45  529.32 1683.96  527.61
 1892.75  530.08 1953.53  531.84 1957.38  534.97 2029.93  531.84 2101.73     537
 2226.85     537 2227.94  536.34 2229.03  528.53 2230.11  527.59 2436.82  527.59
 2437.91     537 2516.24     537 2517.33   533.6 2553.23  533.31 2555.41   523.2
 2570.64  519.14 2597.09  523.25 2640.61  512.09 2678.09  496.08 2751.11  490.14
 2888.57  494.36 2981.05   524.8 3113.11  526.49 3163.09  537.08  3208.5  537.52
#Mann= 4 ,-1,0
       0      .1       0 1424.45     .06       0 2597.09    .035       0
 2981.05     .06       0
#XS Ineff= 2 , 0
       0  2437.9     570 3166.84       0     550
Permanent Ineff=
       F       T
Bank Sta=2597.09,2981.05
XS Rating Curve= 0 ,0
Exp/Cntr=0.3,0.1

Type RM Length L Ch R = 1 ,238448  ,67.46,68.25,69.34
XS GIS Cut Line= 3
  2330081.547536 6972331.5934781 2329344.9496802 6970582.7859089
 2328836.5788021 6969388.7172677
#Sta/Elev= 30
       0  557.93   71.45  556.91  224.13  544.87 1387.36  530.56  1679.2  526.25
  1887.4  529.78 1910.32  533.62 1984.19  530.24 2046.14   536.5 2143.96   536.5
 2146.13  527.59 2425.45  527.59 2426.54     537 2504.79     537 2506.17  531.24
 2541.75  531.38 2543.92  521.66 2563.48  516.32 2592.83  521.91 2595.51  521.04
 2623.66  516.95 2674.37  495.76 2745.05  489.96 2883.85  495.48 2962.74  523.08
 2969.87  525.67 3087.55  526.42 3119.64  528.41 3151.73  537.18 3195.39  537.51
#Mann= 4 ,-1,0
       0      .1       0 1387.36     .06       0 2595.51    .035       0
 2962.74     .06       0
#XS Ineff= 2 , 0
       0 2426.54     570 3159.43       0     550
Permanent Ineff=
       F       T
Bank Sta=2592.83,2969.87
XS Rating Curve= 0 ,0
Exp/Cntr=0.3,0.1

Type RM Length L Ch R = 1 ,238380  ,95.95,96.72,98.63
XS GIS Cut Line= 4
  2330136.339221 6972310.1998254 2329408.4857669 6970564.7112555
 2329408.4780367 6970564.6928354 2328904.1740483 6969373.6957354
#Sta/Elev= 30
       0  560.44   70.78  560.61  187.13   546.5  225.05  544.91  653.29  537.18
 1393.05     530 1665.82  525.79 1787.81  530.81 1918.16  531.38  1956.2  529.29
  2019.9   536.5  2157.9   536.5  2158.6  535.65    2160  527.59  2516.2  529.89
  2519.5  529.69  2522.7  523.04  2601.3  520.62 2632.62  511.74 2673.11  495.33
 2701.82  490.77 2740.26  489.81 2872.66  495.78 2898.59  503.31 2944.71 506.295
 3044.55 520.405 3083.78 526.753  3112.3 528.437 3140.83 536.877 3195.61  537.31
#Mann= 4 ,-1,0
       0      .1       0 1393.05     .06       0  2601.3    .035       0
 3044.55     .06       0
#XS Ineff= 2 ,-1
       0  2516.2     5703153.289 3182.81     550
Permanent Ineff=
       F       T
Bank Sta=2601.3,3083.78
XS Rating Curve= 0 ,0
Exp/Cntr=0.3,0.1

Type RM Length L Ch R = 1 ,238283.8,296,296,313
BEGIN DESCRIPTION:
Downstream of Sump 28 outfall.
Ineffective flow in LOB.
Effective flow limit in ROB set at West Fork Levee Loop.
CDC FW032024-1 Stonehawk Northside
Located in LOB.
Cross-sections 238283.8 - 238881.1
END DESCRIPTION:
XS GIS Cut Line= 3
 2330214.2723383 6972279.7705002 2329498.8489508 6970538.9843307
 2329000.3183467 6969352.3298144
#Sta/Elev= 30
       0     564   71.29  565.86   101.5     558  151.49     554  188.22  546.44
  221.91  545.07   435.8  543.64  919.98  533.48  1384.3  529.58 1660.95  525.88
  1675.5   523.5 1783.95  531.33 1938.32  526.48 2001.38  531.92 2093.03  531.78
 2159.74  525.86 2598.68  519.13 2640.49  503.35  2641.1  505.87 2662.86     496
 2696.84     490 2732.88   489.6 2830.29   493.1 2876.35     498  2901.1  508.71
 2954.48  523.96 2968.71  524.95 3089.71  527.79 3114.62  533.78 3169.19  537.26
#Mann= 4 ,-1,0
       0      .1       0  1384.3     .06       0 2598.68    .035       0
 2968.71     .06       0
#XS Ineff= 2 , 0
       0 2472.84     570 3144.55       0     550
Permanent Ineff=
       F       T
Bank Sta=2598.68,2968.71
XS Rating Curve= 0 ,0
Exp/Cntr=0.5,0.3

Type RM Length L Ch R = 1 ,237987.5,85.29,84.19,84.39
BEGIN DESCRIPTION:
Upstream of the Union Pacific Railroad.
Ineffective flow in LOB - limit set at Northside Drive.
Effective flow limit in ROB set at West Fork Levee Loop.
END DESCRIPTION:
XS GIS Cut Line= 5
  2330642.738226 6971988.7213785 2329856.2939152 6970715.6645669
 2329722.3982361 6970350.0201539 2329351.7015864 6969414.9695371
 2329312.6522775 6969320.3876277
#Sta/Elev= 30
       0  576.83      83   561.9  445.52  558.54  487.91  533.47  685.12  535.59
   946.7   523.8 1265.24  526.78 1702.81  522.79  1769.2  529.79 1792.98  529.49
 1815.67     524  1887.1     528 1890.76  523.15 1928.79  528.93 1946.17  523.42
 1949.57     528  1957.5  518.81 2012.65     510 2041.03   511.3 2050.05   517.9
 2098.91  519.05 2508.03  521.03  2571.9     494 2594.18  489.55 2645.84  488.02
 2756.74     498 2812.79  518.92 2937.07  527.97 2973.52   536.3 2993.95  536.28
#Mann= 6 ,-1,0
       0      .1       0 1265.24     .06       0  1887.1     .08       0
 2098.91     .06       0 2508.03    .035       0 2812.79     .06       0
#XS Ineff= 2 ,-1
       0 1949.57     580 2973.52 2993.98     550
Permanent Ineff=
       F       T
Bank Sta=2508.03,2812.79
XS Rating Curve= 0 ,0
Exp/Cntr=0.5,0.3

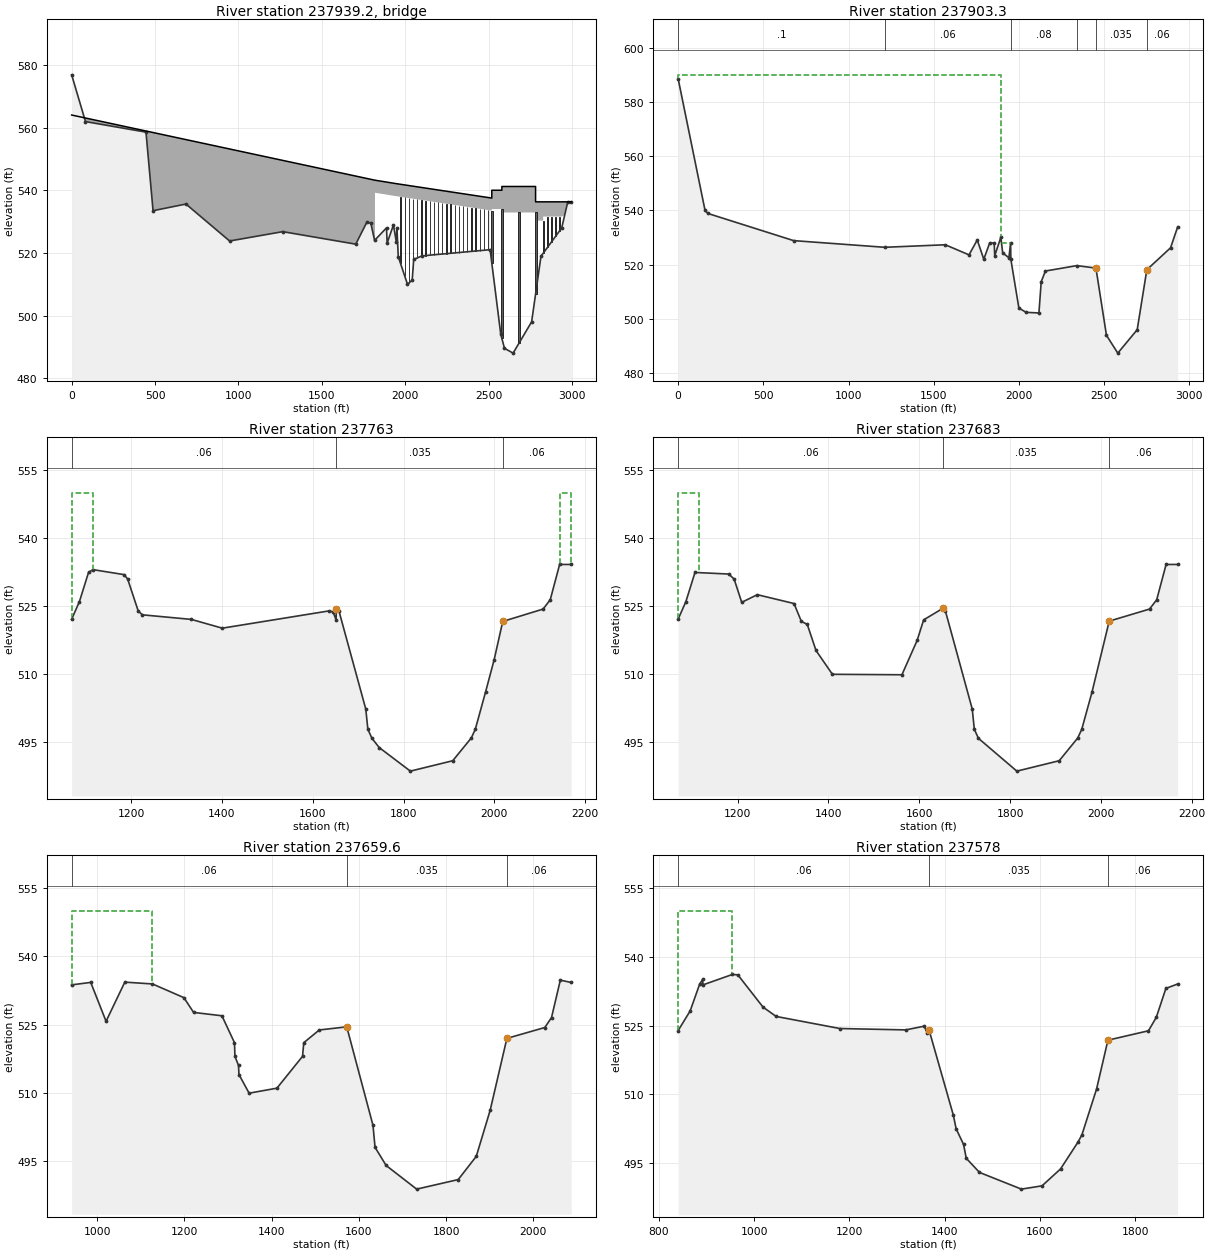
Type RM Length L Ch R = 3 ,237939.2,,,
BEGIN DESCRIPTION:
Union Pacific Railroad
Data from USACE 1949, 1975 survey, TRWD July 2007 field measurements.
END DESCRIPTION:
Node Name=Union Pacific RR
Bridge Culvert--1,0,-1,-1, 0
Deck Dist Width WeirC Skew NumUp NumDn MinLoCord MaxHiCord MaxSubmerge Is_Ogee
39.2,20,2.6,0, 16, 16, , , 0.95, 0, 0,0,,
       0    1818    1818    1946    2518    2518  2578.5  2578.5  2780.5  2780.5
    2826    2826    2826    2955    2955 2993.98
     564   543.2   543.2   542.1   537.5     540     540   541.2   541.2   536.3
   536.3   536.3   536.3   536.3   536.3   536.3
       0       0   539.2   538.1   533.5     534     534   532.9   532.9   530.3
   530.3   530.3   531.6   531.6     450     450
       0    1818    1818    1946    2518    2518  2578.5  2578.5  2780.5  2780.5
    2826    2826    2826    2955    2955 2993.98
     564   543.2   543.2   542.1   537.5     540     540   541.2   541.2   536.3
   536.3   536.3   536.3   536.3   536.3   536.3
       0   539.2   539.2   538.1   533.5     534     534   532.9   532.9   530.3
   530.3   530.3   531.6   531.6     450     450
Pier Skew, UpSta & Num, DnSta & Num=  ,1971, 2 ,1919.06, 2 , 0 , 0 , 0 ,,
       2       2
  487.37   538.1
       2       2
  487.37   538.1
Pier Skew, UpSta & Num, DnSta & Num=  ,1996, 2 ,1944.06, 2 , 0 , 0 , 0 ,,
       2       2
  487.37   538.1
       2       2
  487.37   538.1
Pier Skew, UpSta & Num, DnSta & Num=  ,2021, 2 ,1969.06, 2 , 0 , 0 , 0 ,,
       2       2
  487.37   538.1
       2       2
  487.37   538.1
Pier Skew, UpSta & Num, DnSta & Num=  ,2046, 2 ,1994.06, 2 , 0 , 0 , 0 ,,
       2       2
  487.37   538.1
       2       2
  487.37   538.1
Pier Skew, UpSta & Num, DnSta & Num=  ,2071, 2 ,2019.06, 2 , 0 , 0 , 0 ,,
       2       2
  487.37   538.1
       2       2
  487.37   538.1
Pier Skew, UpSta & Num, DnSta & Num=  ,2096, 2 ,2044.06, 2 , 0 , 0 , 0 ,,
       2       2
  487.37   538.1
       2       2
  487.37   538.1
Pier Skew, UpSta & Num, DnSta & Num=  ,2121, 2 ,2069.06, 2 , 0 , 0 , 0 ,,
       2       2
  487.37   538.1
       2       2
  487.37   538.1
Pier Skew, UpSta & Num, DnSta & Num=  ,2146, 2 ,2094.06, 2 , 0 , 0 , 0 ,,
       2       2
  487.37   538.1
       2       2
  487.37   538.1
Pier Skew, UpSta & Num, DnSta & Num=  ,2171, 2 ,2119.06, 2 , 0 , 0 , 0 ,,
       2       2
  487.37   538.1
       2       2
  487.37   538.1
Pier Skew, UpSta & Num, DnSta & Num=  ,2196, 2 ,2144.06, 2 , 0 , 0 , 0 ,,
       2       2
  487.37   538.1
       2       2
  487.37   538.1
Pier Skew, UpSta & Num, DnSta & Num=  ,2221, 2 ,2169.06, 2 , 0 , 0 , 0 ,,
       2       2
  487.37   538.1
       2       2
  487.37   538.1
Pier Skew, UpSta & Num, DnSta & Num=  ,2246, 2 ,2194.06, 2 , 0 , 0 , 0 ,,
       2       2
  487.37   538.1
       2       2
  487.37   538.1
Pier Skew, UpSta & Num, DnSta & Num=  ,2271, 2 ,2219.06, 2 , 0 , 0 , 0 ,,
       2       2
  487.37   538.1
       2       2
  487.37   538.1
Pier Skew, UpSta & Num, DnSta & Num=  ,2296, 2 ,2244.06, 2 , 0 , 0 , 0 ,,
       2       2
  487.37   538.1
       2       2
  487.37   538.1
Pier Skew, UpSta & Num, DnSta & Num=  ,2321, 2 ,2269.06, 2 , 0 , 0 , 0 ,,
       2       2
  487.37   538.1
       2       2
  487.37   538.1
Pier Skew, UpSta & Num, DnSta & Num=  ,2346, 2 ,2294.06, 2 , 0 , 0 , 0 ,,
       2       2
  487.37   538.1
       2       2
  487.37   538.1
Pier Skew, UpSta & Num, DnSta & Num=  ,2371, 2 ,2319.06, 2 , 0 , 0 , 0 ,,
       2       2
  487.37   538.1
       2       2
  487.37   538.1
Pier Skew, UpSta & Num, DnSta & Num=  ,2396, 2 ,2344.06, 2 , 0 , 0 , 0 ,,
       2       2
  487.37   538.1
       2       2
  487.37   538.1
Pier Skew, UpSta & Num, DnSta & Num=  ,2421, 2 ,2369.06, 2 , 0 , 0 , 0 ,,
       2       2
  487.37   538.1
       2       2
  487.37   538.1
Pier Skew, UpSta & Num, DnSta & Num=  ,2446, 2 ,2394.06, 2 , 0 , 0 , 0 ,,
       2       2
  487.37   538.1
       2       2
  487.37   538.1
Pier Skew, UpSta & Num, DnSta & Num=  ,2471, 2 ,2419.06, 2 , 0 , 0 , 0 ,,
       2       2
  487.37   538.1
       2       2
  487.37   538.1
Pier Skew, UpSta & Num, DnSta & Num=  ,2496, 2 ,2444.06, 2 , 0 , 0 , 0 ,,
       2       2
  487.37   538.1
       2       2
  487.37   538.1
Pier Skew, UpSta & Num, DnSta & Num=  ,2518, 2 ,2466.06, 2 , 0 , 0 , 0 ,,
     9.5       5
     506     535
     9.5       5
     506     535
Pier Skew, UpSta & Num, DnSta & Num=  ,2578, 2 ,2526.06, 2 , 0 , 0 , 0 ,,
    12.5       7
     450     535
    12.5       7
     450     535
Pier Skew, UpSta & Num, DnSta & Num=  ,2682, 2 ,2630.06, 2 , 0 , 0 , 0 ,,
    12.5       7
     450     535
    12.5       7
     450     535
Pier Skew, UpSta & Num, DnSta & Num=  ,2780.5, 2 ,2728.56, 2 , 0 , 0 , 0 ,,
    12.5       7
     450     535
    12.5       7
     450     535
Pier Skew, UpSta & Num, DnSta & Num=  ,2826, 2 ,2776.06, 2 , 0 , 0 , 0 ,,
     4.5       4
     518   535.3
     4.5       4
     518   535.3
Pier Skew, UpSta & Num, DnSta & Num=  ,2852, 4 ,2800.06, 4 , 3 , 3 , 0 ,,
       2       2    2.75    2.75
     500     528     528   535.3
       2       2    2.75    2.75
     500     528     528   535.3
Pier Skew, UpSta & Num, DnSta & Num=  ,2876.5, 4 ,2824.56, 4 , 3 , 3 , 0 ,,
       2       2    2.75    2.75
     500     528     528   535.3
       2       2    2.75    2.75
     500     528     528   535.3
Pier Skew, UpSta & Num, DnSta & Num=  ,2900, 4 ,2848.06, 4 , 3 , 3 , 0 ,,
       2       2    2.75    2.75
     500     528     528   535.3
       2       2    2.75    2.75
     500     528     528   535.3
Pier Skew, UpSta & Num, DnSta & Num=  ,2923, 4 ,2871.06, 4 , 3 , 3 , 0 ,,
       2       2    2.75    2.75
     500     528     528   535.3
       2       2    2.75    2.75
     500     528     528   535.3
BR Coef=-1 , 0 , 0 ,, 0 ,,,0.8,-1,,0,
WSPro=,,,, 1 ,,,, 0 ,,,, 0 ,,,,-1 ,-1 ,-1 , 0 , 0 , 0 , 0 , 0
BC Design=,, 0 ,, 0 ,,22,1971,1919.06,25,2
BC Use User HTab Curves=0
BC User HTab FreeFlow(D)= 0

Type RM Length L Ch R = 1 ,237903.3,245.79,140.31,69.57
BEGIN DESCRIPTION:
Downstream of the Union Pacific Railroad.
Ineffective flow in LOB - limit set at Northside Drive.
Effective flow limit in ROB set at West Fork Levee Loop.
END DESCRIPTION:
XS GIS Cut Line= 4
 2330760.7049439 6971875.6699999 2329799.0086144 6970314.8131738
 2329430.4429476  6969385.137721 2329392.8709887  6969294.134328
#Sta/Elev= 30
       0  588.62  158.03  540.01  174.56  538.88  677.91  528.86 1212.03   526.4
 1568.07  527.33 1707.31  523.61 1755.63  529.09 1793.98     522 1828.67     528
 1855.01     528 1858.19   523.3 1894.06  530.08 1904.96  524.35  1941.4  522.54
 1951.41     528 1952.87  521.95 1999.91     504 2042.22  502.41 2117.59  502.18
 2131.07  513.72 2155.75  517.65 2340.33  519.64 2452.18  518.73 2513.94  493.94
 2580.42  487.37 2694.37     496 2750.91  518.12 2890.15  526.21 2931.87  533.93
#Mann= 6 ,-1,0
       0      .1       0 1212.03     .06       0 1951.41     .08       0
 2340.33     .06       0 2452.18    .035       0 2750.91     .06       0
#XS Ineff= 2 ,-1
       0 1894.06     590 1894.06  1951.4     528
Permanent Ineff=
       F       F
Bank Sta=2452.18,2750.91
XS Rating Curve= 0 ,0
Exp/Cntr=0.5,0.3

Type RM Length L Ch R = 1 ,237763  ,90,80,50
XS GIS Cut Line= 2
  2330084.0096966970144.109417742329434.171506816969256.57895189
#Sta/Elev= 30
 1069.24  522.15 1086.28     526 1106.41  532.45 1116.16  533.07 1184.89  531.97
 1192.55     531 1215.91  523.93 1225.09  523.11 1332.77   522.1  1400.9  520.17
 1636.83  523.99  1644.7  523.76 1651.44     522 1651.79   524.5 1657.77  523.93
 1716.78  502.34 1721.37  497.88 1730.41  495.89 1746.31  493.86 1814.96  488.66
 1908.18  490.95 1949.02  495.96 1957.87  497.88 1980.43  506.08 1999.38  513.21
 2018.31  521.65 2107.13  524.38 2122.89  526.44 2143.54  534.21 2169.02  534.21
#Mann= 3 ,-1,0
 1069.24     .06       0 1651.79    .035       0 2018.31     .06       0
#XS Ineff= 2 , 0
       0 1116.16     550 2143.54       0     550
Permanent Ineff=
       T       T
Bank Sta=1651.79,2018.31
XS Rating Curve= 0 ,0
Exp/Cntr=0.3,0.1

Type RM Length L Ch R = 1 ,237683  ,63.75,23.4,25.2
XS GIS Cut Line= 2
  2330252.4992796970014.769140012329462.06525156 6969248.2587233
#Sta/Elev= 30
 1069.24  522.15 1086.28     526 1106.41  532.45 1180.66   532.1 1192.55     531
 1209.27  525.86  1243.6  527.55 1324.41   525.6 1340.54  521.67 1353.56     521
 1372.82  515.25 1408.92     510 1561.97   509.9 1595.55  517.49 1609.79     522
 1651.79  524.52 1657.77  523.93 1716.78  502.34 1721.37  497.88 1730.41  495.89
 1814.96  488.66 1908.18  490.95 1949.02  495.96 1957.87  497.88 1980.43  506.08
 2018.31  521.72 2107.13  524.38 2122.89  526.44 2143.54  534.21 2169.02  534.21
#Mann= 3 ,-1,0
 1069.24     .06       0 1651.79    .035       0 2018.31     .06       0
#XS Ineff= 2 ,-1
 1069.24 1114.86     550    1200 1651.78     524
Permanent Ineff=
       T       T
Bank Sta=1651.79,2018.31
XS Rating Curve= 0 ,0
Exp/Cntr=0.3,0.1

Type RM Length L Ch R = 1 ,237659.6,145.53,81.7,52.93
BEGIN DESCRIPTION:
Ineffective flow in LOB - limit set at Northside Drive.
Effective flow limit in ROB set at West Fork Levee Loop.
END DESCRIPTION:
XS GIS Cut Line= 3
2330313.484066516970021.67992338 2329859.0641411 6969593.9074122
 2329470.1031089 6969246.7822492
#Sta/Elev= 30
  941.45  533.72  985.21  534.26 1020.35  525.71 1063.36  534.32 1126.77  533.92
 1198.76  530.91 1221.09  527.66    1286  526.92 1314.84     521 1315.86     518
 1324.06     516 1325.08     514 1348.34   509.9 1412.09     511 1470.88     518
 1473.66     521 1509.26   523.8 1572.23  524.49 1632.41  502.82 1637.09     498
 1662.52     494 1732.53   488.8 1827.79   490.9 1869.19     496 1901.03  506.13
 1939.42  521.95 2026.32  524.34 2041.74  526.53 2061.95  534.76 2086.87  534.24
#Mann= 3 ,-1,0
  941.45     .06       0 1572.23    .035       0 1939.42     .06       0
#XS Ineff= 2 ,-1
  941.45 1126.77     550 1126.77 1558.93     524
Permanent Ineff=
       T       T
Bank Sta=1572.23,1939.42
XS Rating Curve= 0 ,0
Exp/Cntr=0.3,0.1

Type RM Length L Ch R = 1 ,237578  ,97.7,76.94,56.92
XS GIS Cut Line= 2
  2330341.8048346969827.500621442329496.535737726969207.92596866
#Sta/Elev= 30
  840.55   523.9  865.83  528.18  885.67     534  891.98  535.04  892.63  533.86
  954.43  536.13  965.91  536.05 1018.83  529.01 1046.41  526.98 1180.02  524.35
 1318.39  524.05 1357.23  524.87 1363.02   523.4 1367.05   524.1 1418.24  505.45
 1424.04  502.51 1439.66  499.09 1445.33  496.07 1473.09  492.99 1561.11  489.35
 1604.36  490.07 1643.12  493.74 1680.03  499.63 1688.03  501.18 1718.76  511.14
 1742.65  521.81 1827.76  523.86 1844.23   526.8 1864.29  533.09 1889.03  534.06
#Mann= 3 ,-1,0
  840.55     .06       0 1367.05    .035       0 1742.65     .06       0
#XS Ineff= 2 , 0
       0  954.43     550               0
Permanent Ineff=
       T       F
Bank Sta=1367.05,1742.65
XS Rating Curve= 0 ,0
Exp/Cntr=0.3,0.1

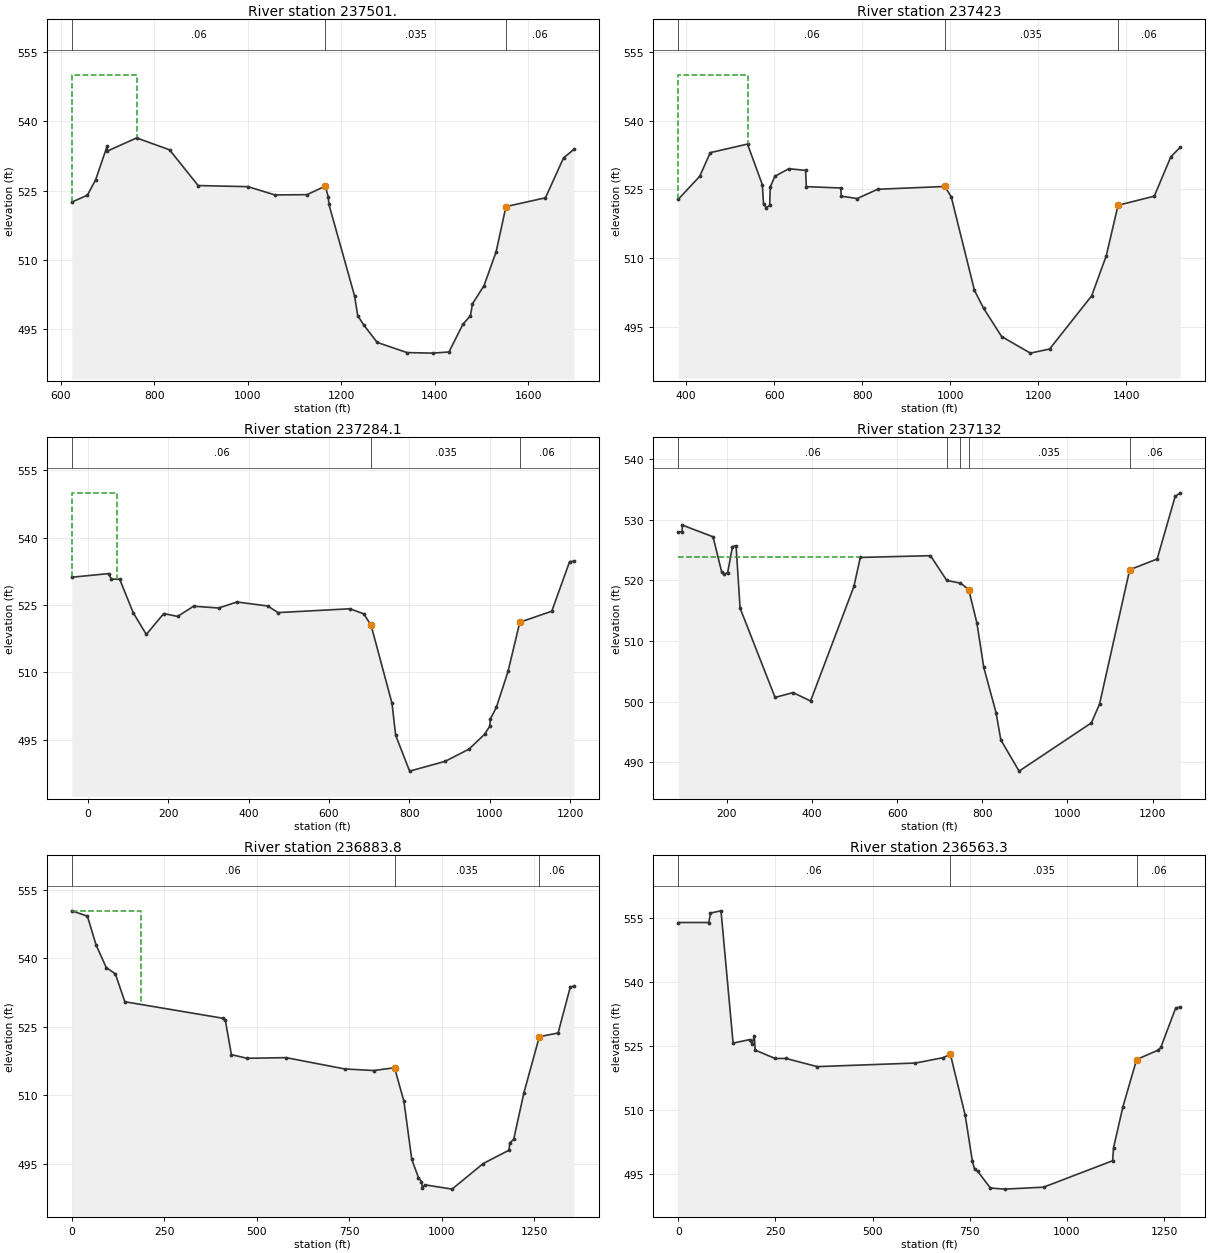
Type RM Length L Ch R = 1 ,237501. ,129.9,78,56.96
BEGIN DESCRIPTION:
Ineffective flow in LOB - limit set at Northside Drive.
Effective flow limit in ROB set at West Fork Levee Loop.
END DESCRIPTION:
XS GIS Cut Line= 3
2330459.574578046969705.29055011 2330374.3443123 6969656.9355291
 2329522.9821572  6969177.691889
#Sta/Elev= 30
  623.13   522.5  656.63     524  674.27  527.34  698.63  534.54  699.34  533.53
  762.05  536.37  832.43   533.8   893.8  526.08 1000.48  525.84 1057.93  524.06
 1126.75  524.11 1165.83  525.96 1172.23  523.68 1173.71     522 1228.59  502.25
 1235.37     498    1248     496 1277.01   492.2 1340.86     490 1395.67  489.88
 1430.69  490.13 1460.31  496.07 1476.81     498 1481.01  500.53 1505.68  504.44
 1531.67  511.76 1552.75  521.54 1637.26  523.43 1676.08  532.06  1698.1  533.88
#Mann= 3 ,-1,0
  623.13     .06       0 1165.83    .035       0 1552.75     .06       0
#XS Ineff= 2 , 0
       0  762.05     550               0
Permanent Ineff=
       T       F
Bank Sta=1165.83,1552.75
XS Rating Curve= 0 ,0
Exp/Cntr=0.3,0.1

Type RM Length L Ch R = 1 ,237423  ,158.17,138.9,116.11
XS GIS Cut Line= 2
  2330580.520112 6969615.91207982329548.619071046969124.37562145
#Sta/Elev= 30
  382.13   522.8  430.94  527.83  454.82     533  539.43  534.87  573.14     526
  575.82  521.75   581.9  520.99  589.83  521.46  590.98  525.47   601.7  527.84
  633.36  529.49  671.33  529.12  673.03  525.57  751.08  525.28  752.42   523.5
  788.31  522.97  835.09     525  987.52  525.61 1002.07  523.36 1054.86   502.9
  1075.5  499.01 1116.57  492.82 1181.83   489.2 1225.51   490.1 1320.98  501.72
 1354.06  510.43  1380.9   521.5 1463.12  523.49 1500.88  532.11 1522.31  534.19
#Mann= 3 ,-1,0
  382.13     .06       0  987.52    .035       0  1380.9     .06       0
#XS Ineff= 2 , 0
       0  539.43     550               0
Permanent Ineff=
       T       F
Bank Sta=987.52,1380.9
XS Rating Curve= 0 ,0
Exp/Cntr=0.3,0.1

Type RM Length L Ch R = 1 ,237284.1,146.86,152.11,152.43
BEGIN DESCRIPTION:
Ineffective flow in LOB - limit set at Northside Drive.
Effective flow limit in ROB set at West Fork Levee Loop.
END DESCRIPTION:
XS GIS Cut Line= 3
2331051.205796176969131.99021762 2331014.0152632 6969118.5635304
2329877.036682136968708.08660078
#Sta/Elev= 30
  -39.54   531.2   51.82     532   58.81  530.78   79.64  530.75  113.47  523.25
   145.8  518.45  189.25  523.11  223.53  522.46  263.37  524.74  325.44  524.34
  371.32  525.68  447.72  524.79  473.26  523.32  652.09  524.17  686.45  523.04
  704.67  520.49  756.63  503.13  765.77     496  800.48     488  888.72  490.18
  948.21  492.91   986.8   496.2  999.76     498  1001.1   499.6 1016.07  502.18
 1045.23  510.22 1074.43  521.17 1153.96  523.63 1198.24  534.67 1208.81  534.75
#Mann= 3 ,-1,0
  -39.54     .06       0  704.67    .035       0 1074.43     .06       0
#XS Ineff= 2 , 0
           72.53     550
Permanent Ineff=
       F       F
Bank Sta=704.67,1074.43
XS Rating Curve= 0 ,0
Exp/Cntr=0.3,0.1

Type RM Length L Ch R = 1 ,237132  ,245.87,248.2,252.86
XS GIS Cut Line= 2
  2330771.2029836969283.374464052329653.14742753 6968891.8814085
#Sta/Elev= 30
   86.39     528   95.36     528   96.08  529.11  168.04  527.18   188.3  521.41
  194.24  521.04  202.32  521.24  213.63  525.57  222.16   525.7  231.57  515.42
  313.69   500.7   355.9   501.5  396.95  500.11   498.7     519  513.75  523.78
  678.41  524.07  716.78  519.98  748.87  519.54   768.1  518.49  787.43  512.96
  803.49  505.66  832.26  498.21  843.55   493.7  886.41  488.55 1055.99   496.5
 1075.24  499.61 1145.99  521.75 1210.49  523.52  1252.7  533.84 1264.81  534.43
#Mann= 5 ,-1,0
   86.39     .06       0  716.78    .013       0  748.87     .06       0
   768.1    .035       0 1145.99     .06       0
#XS Ineff= 2 , 0
       0  513.92  523.81               0
Permanent Ineff=
       T       F
Bank Sta=768.1,1145.99
XS Rating Curve= 0 ,0
Exp/Cntr=0.3,0.1

Type RM Length L Ch R = 1 ,236883.8,293.54,320.49,340.9
BEGIN DESCRIPTION:
Ineffective flow in LOB.
Effective flow limit in ROB set at West Fork Levee Loop.
-------------------------------------------------------------
CDC FW030217-01 Riverfront Lofts Apartments
---------------------------------------------------------------
Project located in LOB.  Cross-sections 236883.8 - 237763
END DESCRIPTION:
XS GIS Cut Line= 2
 2331014.0152632 6969118.5635304 2329737.7838861 6968657.8129535
#Sta/Elev= 30
       0  550.44   42.28  549.28   65.74  542.94   93.31     538  117.89  536.62
  143.42  530.52  408.42   526.9  415.07  526.44  431.38  518.93  473.53  518.13
   579.3  518.27  738.03  515.79   816.3  515.45  872.34  516.06  897.73  508.67
  918.82     496   936.9     492  945.01   491.1  947.69  489.79  954.26  490.41
 1027.68  489.46 1111.96  495.07 1181.83     498 1183.55  499.57 1194.24  500.37
  1222.1  510.63 1263.64  522.86 1314.24  523.67 1347.36  533.78 1356.86   533.9
#Mann= 3 ,-1,0
       0     .06       0  872.34    .035       0 1263.64     .06       0
#XS Ineff= 2 , 0
       0  186.17  550.44               0
Permanent Ineff=
       T       F
Bank Sta=872.34,1263.64
XS Rating Curve= 0 ,0
Exp/Cntr=0.3,0.1

Type RM Length L Ch R = 1 ,236563.3,331.43,361.7,384.54
BEGIN DESCRIPTION:
Ineffective flow in LOB.
Effective flow limit in ROB set at West Fork Levee Loop.
END DESCRIPTION:
XS GIS Cut Line= 2
  2331000.180079 6968839.4023064 2329816.9359391 6968321.7329142
#Sta/Elev= 30
       0  553.91   78.83  553.91   82.99  556.13  109.99  556.65  141.09  525.61
  183.67  526.43   189.9  525.43  195.72   527.3  197.85  523.97  249.25     522
  277.49     522   357.5  520.09  610.29  520.93   681.4  522.19  700.05  522.98
  738.23  508.66  756.42     498  762.34     496  770.53   495.5  803.01   491.6
  839.37  491.34  939.77   491.8  1117.4     498 1119.82  501.06  1143.9  510.68
 1179.18  521.76  1234.6  523.96 1241.35   524.6 1279.61  533.83 1291.53  534.06
#Mann= 3 ,-1,0
       0     .06       0  700.05    .035       0 1179.18     .06       0
#XS Ineff= 2 , 0
           95.16     550
Permanent Ineff=
       F       F
Bank Sta=700.05,1179.18
XS Rating Curve= 0 ,0
Exp/Cntr=0.3,0.1