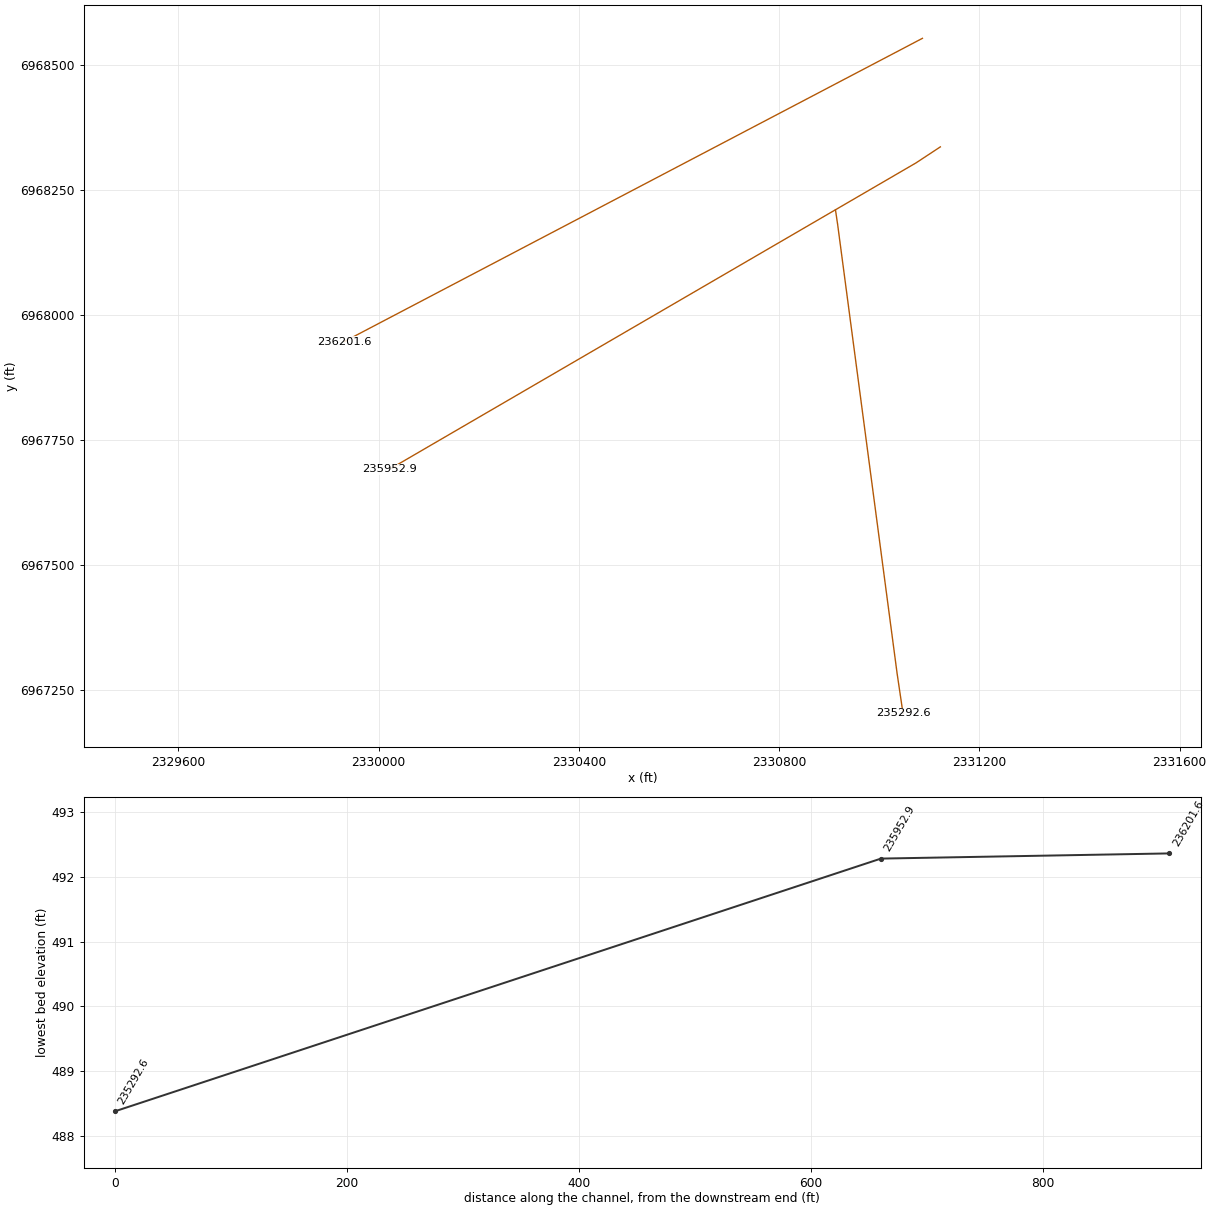
HEC-RAS study CDC_Consolidated_Model.prj: Upper Trinity CDC Consolidated Model

--- CDC_Consolidated_Model.g11 (geometry) --- (continued)

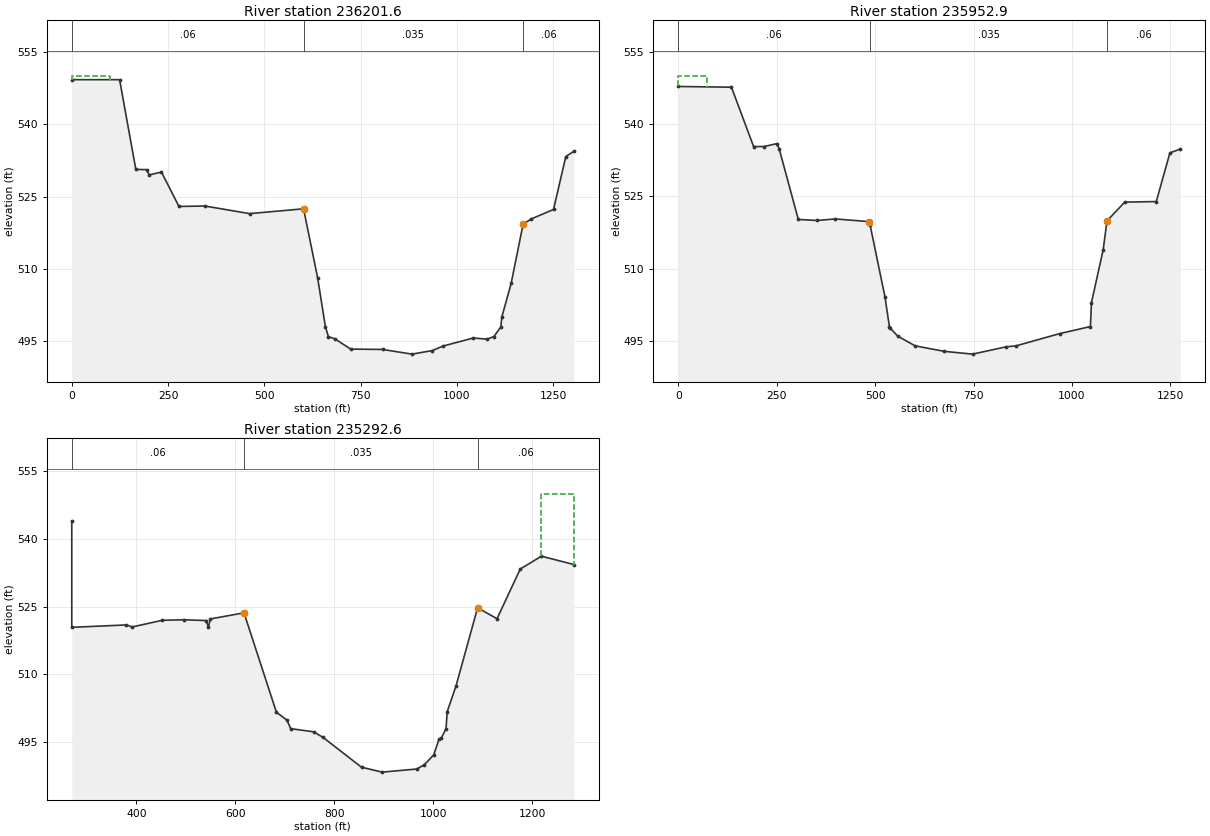
Type RM Length L Ch R = 1 ,236201.6,229.47,248.75,262.92
BEGIN DESCRIPTION:
Ineffective flow in LOB.
Effective flow limit in ROB set at West Fork Levee Loop.
END DESCRIPTION:
XS GIS Cut Line= 2
 2331086.4192901 6968552.6300588 2329931.4218874 6967946.9245486
#Sta/Elev= 30
       0   549.2  124.25   549.2  166.38  530.62  194.22  530.57  201.17  529.48
  233.03  530.06  278.35  522.95  346.03  523.03  461.88  521.46  602.08  522.46
  638.51  508.23  658.91     498  666.55     496  684.07   495.5  724.56   493.4
  807.19  493.33  883.86  492.36   936.6   493.1  964.33  494.03 1043.21   495.7
  1078.9  495.46 1096.51     496 1114.63     498 1117.01  500.01 1141.34  507.01
 1172.34  519.26 1192.99  520.34 1251.36  522.32 1283.34  533.29 1304.18  534.37
#Mann= 3 ,-1,0
       0     .06       0  602.08    .035       0 1172.34     .06       0
#XS Ineff= 2 , 0
           98.84     550
Permanent Ineff=
       F       F
Bank Sta=602.08,1172.34
XS Rating Curve= 0 ,0
Exp/Cntr=0.3,0.1

Type RM Length L Ch R = 1 ,235952.9,221.86,660.2,902.25
BEGIN DESCRIPTION:
Ineffective flow in LOB.
Effective flow limit in ROB set at West Fork Levee Loop.
END DESCRIPTION:
XS GIS Cut Line= 3
  2331122.208213 6968335.7960013 2331073.6685245 6968303.8157011
  2330021.733534 6967691.7099826
#Sta/Elev= 30
       0  547.79  135.13  547.64  191.45  535.33  217.48  535.33  249.58  535.92
  256.22  534.92  304.96  520.21  353.26     520   398.4  520.32  485.55  519.76
  487.21   519.1  525.14  504.12  536.28     498  539.06  497.61  557.74     496
  601.54     494   675.5  492.86  747.45  492.28  831.42  493.77  857.99     494
  968.59  496.53 1046.84     498 1049.54  502.96 1079.27  513.92 1089.03  519.93
 1089.94     520 1134.04  523.81 1214.13  523.92 1248.78  534.02 1275.19  534.81
#Mann= 3 ,-1,0
       0     .06       0  487.21    .035       0 1089.94     .06       0
#XS Ineff= 2 , 0
           73.57     550
Permanent Ineff=
       F       F
Bank Sta=485.55,1089.03
XS Rating Curve= 0 ,0
Exp/Cntr=0.3,0.1

Type RM Length L Ch R = 1 ,235292.6,574.46,500.25,562.86
BEGIN DESCRIPTION:
Upstream bounding cross-section IH 35W.
Ineffective flow in LOB.
Effective flow limit in ROB set at West Fork Levee Loop.
END DESCRIPTION:
XS GIS Cut Line= 4
       2330912.7      6968209.97      2330916.99      6968181.01
      2331035.77      6967284.22       2331047.6      6967204.06
#Sta/Elev= 30
   269.2     544   269.2  520.44  379.31  520.97  391.62  520.53  452.16     522
  495.57  522.11   540.7  521.94  545.41  520.52  549.47   522.3  617.33  523.65
  682.89  501.64  704.15   499.9  711.77     498  758.12  497.31  777.02  496.08
  854.88  489.47  896.59  488.38  966.77  489.07  981.69     490 1000.98   492.2
 1011.42  495.62 1016.53     496  1025.8     498 1028.06  501.74 1046.04  507.49
 1089.57  524.76 1128.86  522.35 1175.75  533.34 1218.52  536.19 1284.13  534.35
#Mann= 3 ,-1,0
   269.2     .06       0  617.33    .035       0 1089.57     .06       0
#XS Ineff= 2 , 0
       0                 1218.52       0     550
Permanent Ineff=
       F       T
Bank Sta=617.33,1089.57
XS Rating Curve= 0 ,0
Exp/Cntr=0.5,0.3