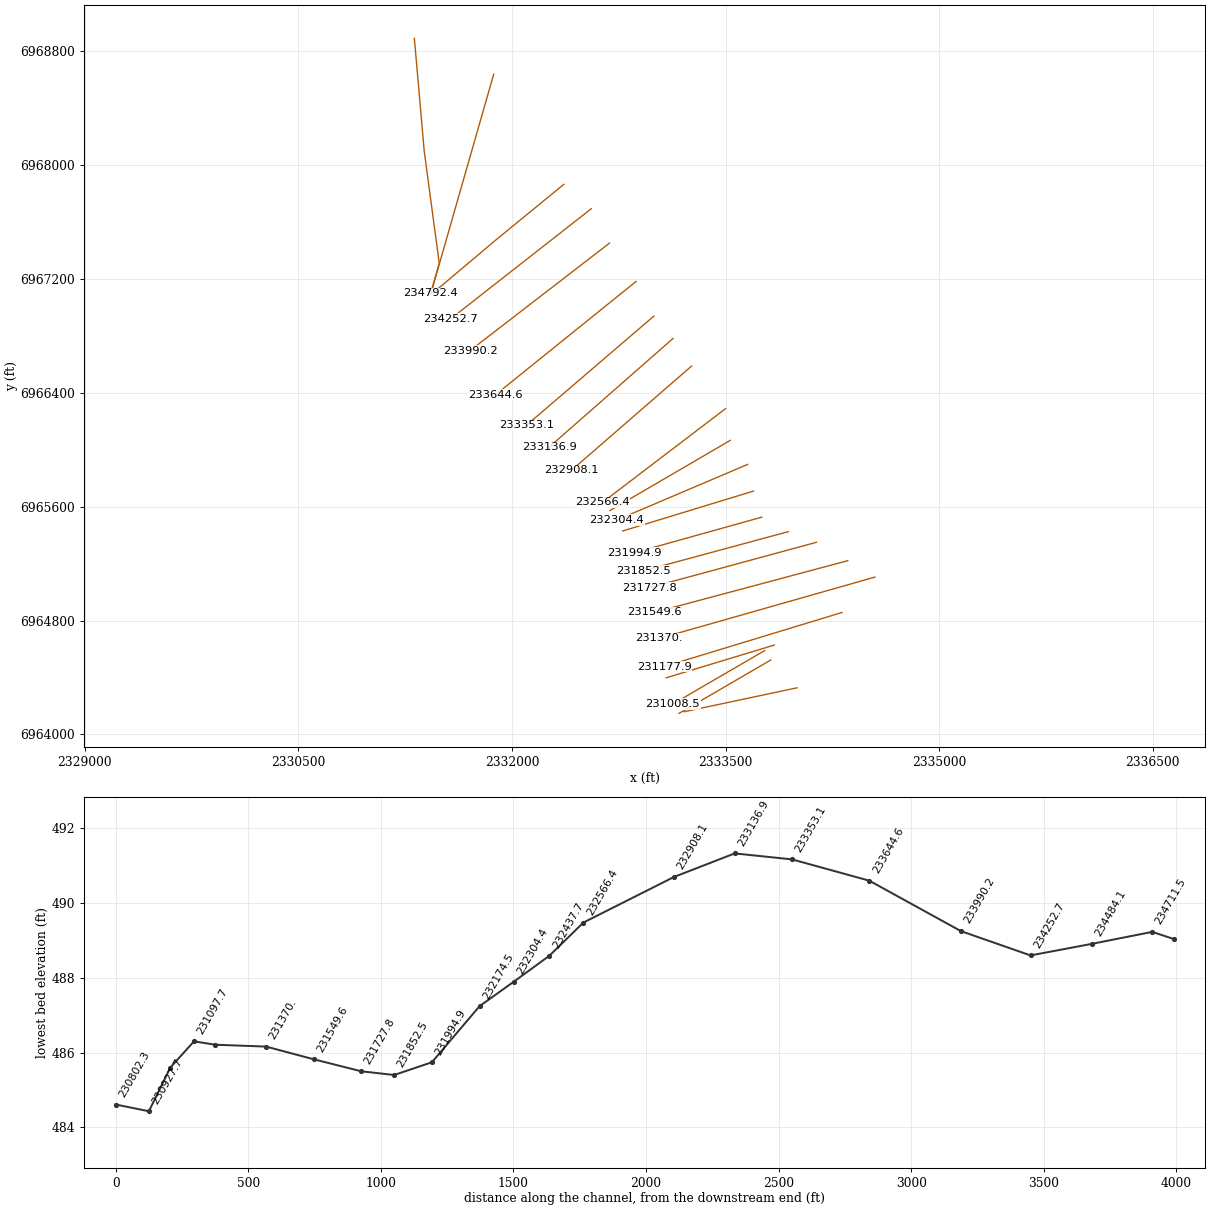
HEC-RAS study CDC_Consolidated_Model.prj: Upper Trinity CDC Consolidated Model

--- CDC_Consolidated_Model.g11 (geometry) --- (continued)

Type RM Length L Ch R = 3 ,235040.7,,,
BEGIN DESCRIPTION:
IH 35W
North Tarrant Express Project Segment 3A
END DESCRIPTION:
Node Name=IH 35W
Bridge Culvert--1,0,-1,-1, 0
Deck Dist Width WeirC Skew NumUp NumDn MinLoCord MaxHiCord MaxSubmerge Is_Ogee
11.41,480.94,2.6,0, 12, 12, , , 0.98, 0, 0,0,,
       0  292.85  292.85  405.87  518.85  631.84  744.82  851.69  959.41 1057.74
 1147.25 1285.98
  550.45  550.45  553.45  554.02  554.58  555.15  555.72  556.31  556.71  556.74
  556.39 555.848
     520     520  543.45  544.02  544.58  545.15  545.72  546.31  546.71  546.74
  546.39 545.848
       0   853.5   853.5  966.54 1079.57 1192.61 1305.65 1434.82 1562.71 1686.51
 1789.67 1809.83
  550.45  550.45  553.45  554.02  554.58  555.15  555.72  556.31  556.71  556.74
  556.39  556.32
     520     520  543.45  544.02  544.58  545.15  545.72  546.31  546.71  546.74
  546.39  546.32
Pier Skew, UpSta & Num, DnSta & Num=  ,405.87, 2 ,966.54, 2 , 0 , 0 , 0 ,,
       5       5
     480     550
       5       5
     480     550
Pier Skew, UpSta & Num, DnSta & Num=  ,518.85, 2 ,1079.57, 2 , 0 , 0 , 0 ,,
       5       5
     480     550
       5       5
     480     550
Pier Skew, UpSta & Num, DnSta & Num=  ,631.84, 2 ,1192.61, 2 , 0 , 0 , 0 ,,
       6       6
     480     550
       6       6
     480     550
Pier Skew, UpSta & Num, DnSta & Num=  ,744.82, 2 ,1305.65, 2 , 0 , 0 , 0 ,,
       6       6
     480     550
       6       6
     480     550
Pier Skew, UpSta & Num, DnSta & Num=  ,851.69, 2 ,1434.82, 2 , 0 , 0 , 0 ,,
       6       6
     480     550
       6       6
     480     550
Pier Skew, UpSta & Num, DnSta & Num=  ,959.41, 2 ,1562.71, 2 , 0 , 0 , 0 ,,
       6       6
     480     550
       6       6
     480     550
Pier Skew, UpSta & Num, DnSta & Num=  ,1057.74, 2 ,1686.51, 2 , 0 , 0 , 0 ,,
       5       5
     480     550
       5       5
     480     550
Pier Skew, UpSta & Num, DnSta & Num=  ,1147.25, 2 ,1789.67, 2 , 0 , 0 , 0 ,,
       5       5
     480     550
       5       5
     480     550
Abutment Skew #Up #Dn= , 4 , 4
  292.85   294.6   294.6 338.932
 543.416 543.416 542.166     520
   853.5  855.25  855.25 899.582
 543.416 543.416 542.166     520
BR Coef=-1 , 0 , 0 ,, 0 ,,,0.8,-1,,0,
WSPro=,,,, 1 ,,,, 0 ,,,, 0 ,,,,-1 ,-1 ,-1 , 0 , 0 , 0 , 0 , 0
BR U #Sta/Elev= 377
   269.2     544   269.2  520.44  379.31  520.97  391.62  520.53  403.47  520.88
  412.19  521.04  452.16     522   486.3     522  495.57  522.11  512.35  522.08
  513.66  522.08  531.25   522.1  537.67  521.99   540.7  521.94  545.08   520.6
  545.41  520.52  545.78  520.69  549.47   522.3  573.23  522.78  587.02  523.03
  603.82  523.27  617.33  523.65  621.44  522.27  622.23     522  624.93  521.09
  628.16     520  633.59  518.17  634.11     518  634.69   517.8  640.07     516
  645.76  514.09  645.93  514.03  646.03     514  649.97  512.68  651.99     512
  654.43  511.18  657.94     510  659.18  509.58  663.89     508  664.16  507.91
  665.77  507.37  669.04  506.26  669.81     506  673.98  504.59  675.71     504
  681.09  502.18  681.62     502  681.76  501.96  682.58  501.74  682.89  501.64
  694.15  500.76  696.01   500.6  701.98  500.09  703.05     500  703.17  499.99
  704.15   499.9  707.37  499.13  711.77     498  714.76  497.99  714.81  497.98
  715.17  497.98  715.43  497.99  715.55  497.99  715.64  497.98  716.12  497.98
  716.34  497.97  716.58  497.97  716.91  497.96  717.21  497.96  717.45  497.95
  718.07  497.97  730.34   497.9  730.73  497.89  735.96  497.87  736.35   497.8
  738.41  497.78  739.55  497.77   740.5  497.77  743.56  497.74  744.23  497.74
  747.88  497.71  748.82  497.71  749.51   497.7  749.53   497.7  750.07  497.67
  750.12  497.67  750.69  497.64  751.82  497.58  752.62  497.53  753.34   497.5
  753.98  497.46     754  497.46  754.33  497.44   754.6  497.43  754.88  497.42
  755.12   497.4  755.31  497.39  755.81  497.41  756.22  497.39  756.51  497.38
  756.54  497.38  756.57  497.34  756.91  497.32  757.39  497.24  757.59  497.27
     758  497.31  758.12  497.31  758.17  497.27  758.56  497.25  758.75  497.24
  759.04  497.17  759.42  497.16  759.81  497.14  761.07  497.05  761.25  497.04
  761.47  497.03  761.63  497.03  761.77  497.02   761.9  497.02  762.03  497.01
  762.15  497.01  762.25     497  762.48  496.99  762.59  496.95  762.68  496.95
  762.77  496.98  762.86  496.98  763.05  496.97  763.22  496.93  763.36  496.93
  763.45  496.96  764.21  496.94  764.49  496.87  765.19  496.86  765.31  496.85
  765.46  496.84  765.57  496.81  765.82   496.8  765.99   496.8   766.3  496.81
  766.53  496.81  766.67   496.8  766.98   496.8  767.13  496.76   767.3  496.76
  772.24  496.38  772.31   496.3  772.88   496.3  775.06     496  776.84  496.08
  777.02  496.08   799.4  494.08   800.3     494   803.3  493.75  820.07  492.35
  821.85  492.19  824.22     492  847.47     490  847.48     490  854.88  489.47
  855.29  489.45  856.01   489.4  856.06   489.4  856.59  489.38  856.88  489.38
  857.12  489.37  857.27  489.37  859.67   489.3   859.7   489.3   859.8  489.28
  859.87  489.28  860.12  489.27  860.43  489.27  861.36  489.24   861.4  489.26
  861.43  489.26  861.66  489.25   861.9  489.38  883.09  488.75  883.45   488.5
  886.05   488.5  886.66  488.52  887.53  488.52  887.56   488.5   888.7   488.5
  889.16  488.41   890.3  488.41  890.35   488.4  890.39   488.4  890.94  488.49
  891.44  488.49  891.46   488.5  892.69   488.5  893.41  488.49  894.06  488.49
  894.62  488.48   895.2  488.39  895.98  488.39  896.59  488.38  896.78  488.38
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BR U #Mann= 5
   269.2    .018  617.33    .018  711.77    .035 1016.53    .018 1089.57    .018
BR D #Sta/Elev= 480
       0  530.22    4.17  530.06   11.87  529.83   18.81  529.68   22.51  529.63
   27.14  529.55   44.12  529.33   45.97   529.3   55.14  529.22   62.69   529.2
   64.73  529.18   67.29  529.19   74.22  529.17   80.21  529.18   85.29  529.17
   86.19  529.18   93.84  529.15   99.91  529.15  106.14  529.12  113.36  529.11
  121.61  529.09  124.64  529.06  129.63  529.06  136.01  529.04  137.12  529.01
  143.54  528.99  147.72  528.99  153.67  528.94  163.43  528.93  167.58  528.91
  184.46  528.91  192.56  528.93  198.16  528.97  206.96  529.02  216.79  529.05
  225.04  529.05  229.84  529.04  241.96  528.93  251.14  528.78  261.87  528.52
  272.74   528.2   277.1  528.08  288.23  527.74  294.25  527.58  299.37  527.46
  309.19  527.27   315.7   527.2  319.83  527.14  326.36   527.1  330.49  527.05
  337.02  527.04  341.14     527  347.67     527   351.8  526.96  358.32  526.96
  360.49  526.89  363.19  526.48  365.65     526  368.25  525.79   368.8  525.79
  372.44  525.56   374.7  524.92  378.91  524.93  390.14  525.02  394.75  525.03
  400.23  525.08  405.52  525.11  410.71  525.12  415.65  525.17  421.14  525.17
  424.66   525.2  428.46  525.21  436.23  525.26  444.35  525.25  450.64  525.28
  459.11  525.24  465.73  525.26  472.42   525.2  476.32  525.21  483.09  525.13
  489.53  525.15  496.42  525.06  500.22  525.06  507.14  524.97  512.12  524.96
  517.43  524.89  523.43  524.85  527.54   524.8  539.14  524.68  553.43  524.48
  560.42  524.34  565.94  524.26  572.51  524.12  575.27  524.08   581.9  523.96
  584.28   523.9  587.31  523.85  590.29  523.83  594.28  523.75  599.84  523.66
  608.91  523.59  612.28  523.59  618.54  523.56  621.53  523.56  624.92   523.6
   630.7  523.59  634.02  523.62  640.25  523.71  644.31  523.71  647.78  523.75
  653.34  523.84  657.94  523.86  666.55  523.98  672.78  524.02  676.32  524.07
  685.47  524.15  696.99  524.28  701.73  524.31  711.67  524.45  723.06   524.6
  726.75  524.66  737.91  524.79     744  524.87  757.54  524.97  759.29  524.97
  771.61  524.93  772.51  524.95  778.26  524.91  779.64  524.94   784.9   524.9
  786.63  524.92  791.42  524.88  793.71   524.9  797.33  524.83  799.86  524.84
   804.1  524.75  808.94  524.67  819.13  524.52  821.96  524.46  823.78   524.4
  832.46   524.2  835.85     524  837.91  523.96  843.13   523.9  852.61  523.75
  856.54  523.65  857.98  523.66  863.82  523.55  868.74  523.47  877.96  523.28
  891.43  522.92  904.03  522.67  915.68  522.37  921.23  522.31   922.8  522.26
  926.74  522.22  936.77   522.2   949.6  522.16  957.37  522.08  965.25  522.03
  971.71  522.04  982.83  522.08  988.73  522.17  996.17  522.36 1002.75  522.51
 1007.73   522.6 1010.31  522.61 1038.97  522.01 1041.37  521.97 1049.96  521.71
 1054.44  521.61 1061.21   521.5 1068.36  521.45 1069.95  521.43 1075.26  521.42
 1096.15  521.44  1099.5  521.46 1103.29  521.45 1106.85  520.89 1110.11  520.47
  1116.1  521.33 1117.08  521.35  1143.9  521.41 1149.75  521.64 1151.77  521.63
 1153.17   521.7  1156.8   521.7 1160.57  521.97 1162.44     522 1167.57  522.42
 1176.25  523.55 1183.01  521.27 1189.09  519.24  1200.6  515.36 1209.47  512.39
 1224.37  507.48 1234.88  504.03 1238.69   502.9 1243.16  501.55 1248.03     500
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BR D #Mann= 5
       0    .018 1176.25    .018 1251.95    .035  1632.4    .018 1704.97    .018
BC Design=,, 0 ,, 0 ,,,,,,
BC Use User HTab Curves=0
BC User HTab FreeFlow(D)= 0

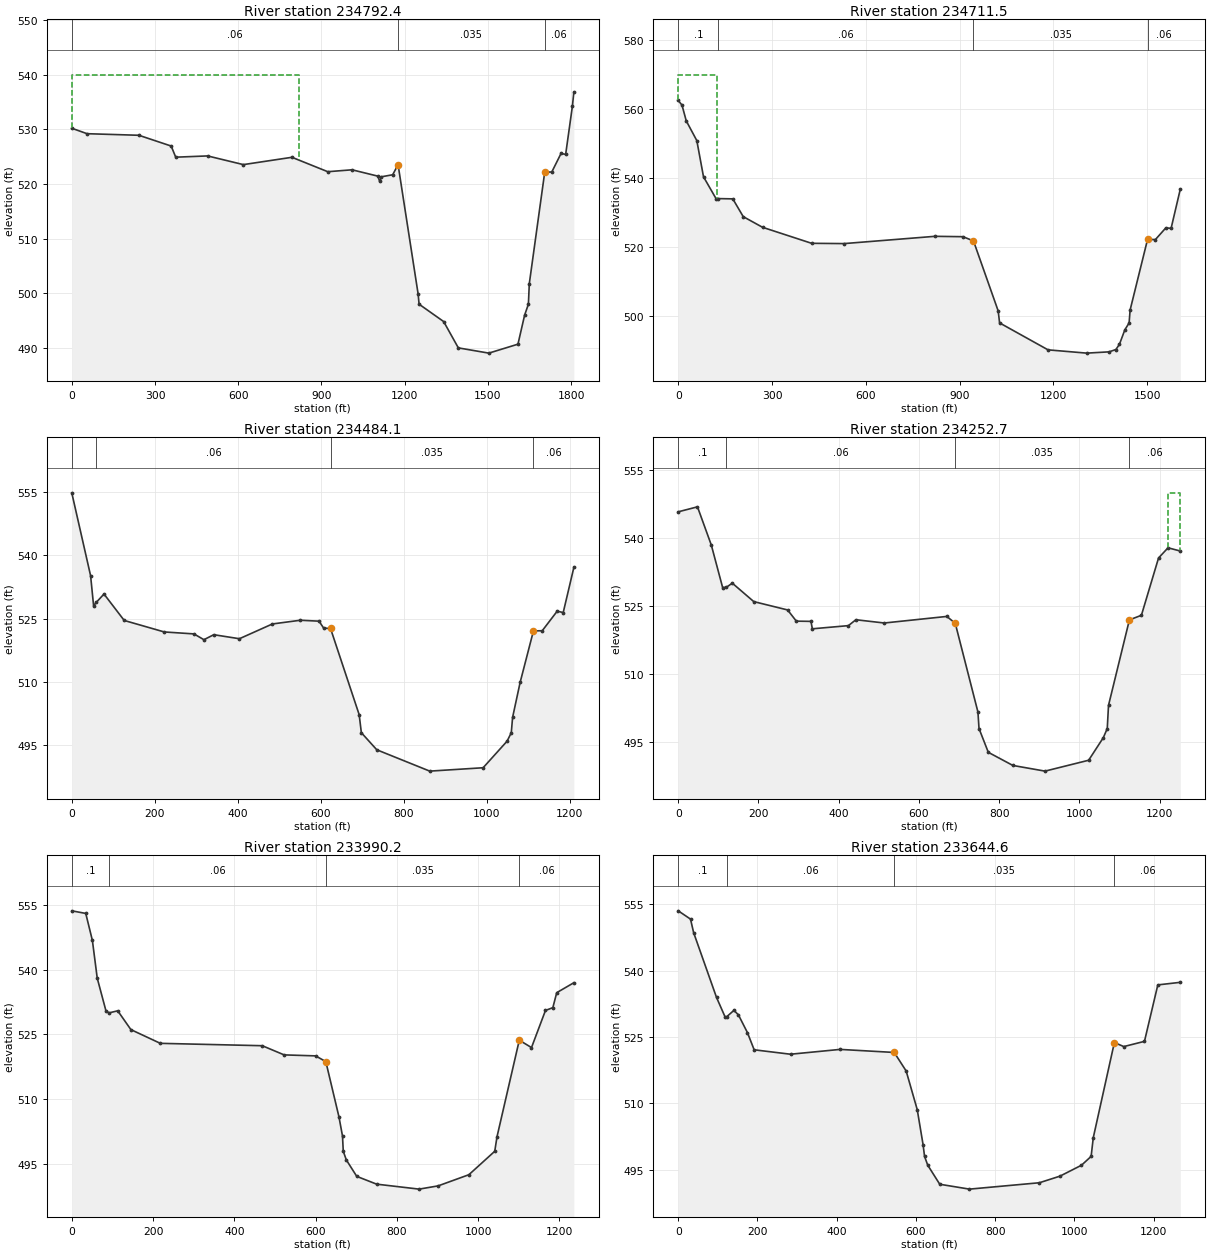
Type RM Length L Ch R = 1 ,234792.4,139.4,80.98,2
BEGIN DESCRIPTION:
Downstream bounding cross-section IH 35W.
Ineffective flow in LOB.
Effective flow limit in ROB set at West Fork Levee Loop.
**********************************************
CDC IH 35W Crossing Over Trinity River - North Tarrant Express Project Segment 3A CDC FW 091213-1
Cross-sections 234792.4 - 236883.8
**********************************************
END DESCRIPTION:
XS GIS Cut Line= 4
      2331314.77      6968888.29      2331383.65      6968097.57
      2331489.42      6967308.32      2331428.97      6967097.21
#Sta/Elev= 30
       0  530.22   55.14  529.22  241.96  528.93  358.32  526.96   374.7  524.92
  489.53  525.15  618.54  523.56  793.71   524.9   922.8  522.26 1010.31  522.61
 1103.29  521.45 1110.11  520.47  1116.1  521.33  1156.8   521.7 1176.25  523.55
 1248.58  499.85 1251.95     498 1340.55  494.82 1393.46     490 1503.36  489.04
 1608.37  490.68  1632.4     496 1646.04     498 1649.24  501.75 1704.97  522.21
 1730.26   522.2 1763.65   525.6 1780.31  525.43 1804.77  534.32 1809.83  536.84
#Mann= 3 ,-1,0
       0     .06       0 1176.25    .035       0 1704.97     .06       0
#XS Ineff= 1 ,-1
       0  819.32     540
Permanent Ineff=
       F
Bank Sta=1176.25,1704.97
XS Rating Curve= 0 ,0
Exp/Cntr=0.5,0.3

Type RM Length L Ch R = 1 ,234711.5,406.78,227.37,43.14
BEGIN DESCRIPTION:
Ineffective flow in LOB.
Effective flow limit in ROB set at West Fork Levee Loop.
END DESCRIPTION:
XS GIS Cut Line= 2
 2331871.8412788 6968636.6834503   2331429.62136 6967092.3296207
#Sta/Elev= 30
       0  562.55   11.98  561.22   25.63  556.64   59.45  550.91   80.87   540.4
  121.23  534.03  128.67  534.08  174.59     534  207.98  528.84  269.75  525.75
  426.87   521.1  530.85  521.02  821.19  523.13  911.12  523.02  944.65   521.8
 1023.72  501.47 1028.22     498 1183.22  490.18 1306.81  489.23 1378.53   489.6
 1400.35  490.28 1411.61  491.78 1428.99     496 1442.63     498 1445.83  501.75
 1501.56  522.21 1526.85   522.2 1560.24   525.6  1576.9  525.43 1606.42  536.84
#Mann= 4 ,-1,0
       0      .1       0  128.67     .06       0  944.65    .035       0
 1501.56     .06       0
#XS Ineff= 1 ,-1
       0  123.93     570
Permanent Ineff=
       F
Bank Sta=944.65,1501.56
XS Rating Curve= 0 ,0
Exp/Cntr=0.3,0.1

Type RM Length L Ch R = 1 ,234484.1,241.16,231.4,226.29
BEGIN DESCRIPTION:
Riverside Park in LOB.
Effective flow limit in ROB set at West Fork Levee Loop.
END DESCRIPTION:
XS GIS Cut Line= 3
 2332364.0520498 6967862.7505941 2331889.1915866 6967474.2082914
 2331432.7545712 6967089.6440481
#Sta/Elev= 30
       0  554.74   45.42  535.12   52.64     528   59.19  528.84   77.69   530.8
  126.45  524.55  223.02  521.83  294.53  521.37  318.54     520  342.36  521.18
  404.17  520.23  483.65  523.72   551.1   524.6  596.08  524.38  607.35  522.73
   623.8  522.66  692.85  502.27  698.14     498  735.33  493.96  863.05  488.91
  991.68  489.71 1049.48     496  1059.6     498 1062.76  501.63 1080.97  509.92
 1113.01  522.08 1134.22  522.12 1170.29  526.75 1184.79  526.42 1210.41  537.09
#Mann= 4 ,-1,0
       0      .1       0   59.19     .06       0   623.8    .035       0
 1113.01     .06       0
Bank Sta=623.8,1113.01
XS Rating Curve= 0 ,0
Exp/Cntr=0.3,0.1

Type RM Length L Ch R = 1 ,234252.7,266.75,262.51,262.65
BEGIN DESCRIPTION:
Riverside Park in LOB.
Effective flow limit in ROB set at West Fork Levee Loop.
Trib in Riverside Park removed from conveyance - original cross-section data removed.
END DESCRIPTION:
XS GIS Cut Line= 2
 2332557.0001198 6967691.7991732 2331571.7371001  6966920.104251
#Sta/Elev= 30
       0  545.81   47.95  546.91   82.48  538.47  110.68   529.1  120.14  529.17
  134.78  530.07  188.28     526  272.64  524.16  294.37  521.69  330.83  521.64
  334.31     520  424.22   520.7  442.86     522  513.62  521.28  669.52  522.73
   690.5  521.22  747.07  501.63  749.73     498   772.9  492.75   834.2  489.85
  914.28   488.6    1023     491 1059.71     496 1069.42     498 1072.51   503.1
 1124.61  521.97 1154.53  522.98 1197.27  535.63 1220.91  537.87  1251.5  537.16
#Mann= 4 ,-1,0
       0      .1       0  120.14     .06       0   690.5    .035       0
 1124.61     .06       0
#XS Ineff= 2 , 0
       0                 1220.91       0     550
Permanent Ineff=
       F       T
Bank Sta=690.5,1124.61
XS Rating Curve= 0 ,0
Exp/Cntr=0.3,0.1

Type RM Length L Ch R = 1 ,233990.2,340.9,345.59,353.16
BEGIN DESCRIPTION:
Riverside Park in LOB.
Effective flow limit in ROB set at West Fork Levee Loop.
END DESCRIPTION:
XS GIS Cut Line= 2
 2332684.8721876 6967450.0448794 2331706.4220129 6966695.8820169
#Sta/Elev= 30
       0  553.58   34.41  552.98   50.74  546.73   62.67  538.01   84.37  530.37
   92.16     530  113.07  530.47   145.5  526.12  217.84  522.95  468.72   522.4
  522.55  520.28  599.93  520.05  625.11  518.73  657.32     506  666.15  501.52
  668.02     498  675.56     496  701.22   492.2  750.11   490.4  854.63  489.25
   901.4     490  977.09  492.58 1040.75     498 1046.34  501.37 1101.14  523.68
 1131.17  521.97 1165.55  530.55 1183.71   531.2 1193.25  534.66 1235.37  536.96
#Mann= 4 ,-1,0
       0      .1       0   92.16     .06       0  625.11    .035       0
 1101.14     .06       0
Bank Sta=625.11,1101.14
XS Rating Curve= 0 ,0
Exp/Cntr=0.3,0.1

Type RM Length L Ch R = 1 ,233644.6,282.1,291.49,300.83
BEGIN DESCRIPTION:
Riverside Park in LOB.
Effective flow limit in ROB set at West Fork Levee Loop.
END DESCRIPTION:
XS GIS Cut Line= 2
 2332871.3950291 6967180.7900425 2331884.7011993 6966385.3632718
#Sta/Elev= 30
       0   553.5   30.96  551.63   38.93  548.55   96.63  533.93  118.76  529.42
  122.43  529.57  140.54     531  151.83     530  174.59  525.99  191.66  522.09
  283.42  521.09  408.59  522.18  545.27  521.49  575.36   517.3   603.3  508.57
  618.11  500.62  621.78     498  629.89     496  660.16   491.7  735.13   490.6
  911.51  492.04   963.5  493.53  1017.9     496 1042.28     498 1047.71  502.24
 1100.94  523.73 1124.73  522.82  1176.9     524 1210.62  536.76 1267.39  537.34
#Mann= 4 ,-1,0
       0      .1       0  122.43     .06       0  545.27    .035       0
 1100.94     .06       0
Bank Sta=545.27,1100.94
XS Rating Curve= 0 ,0
Exp/Cntr=0.3,0.1

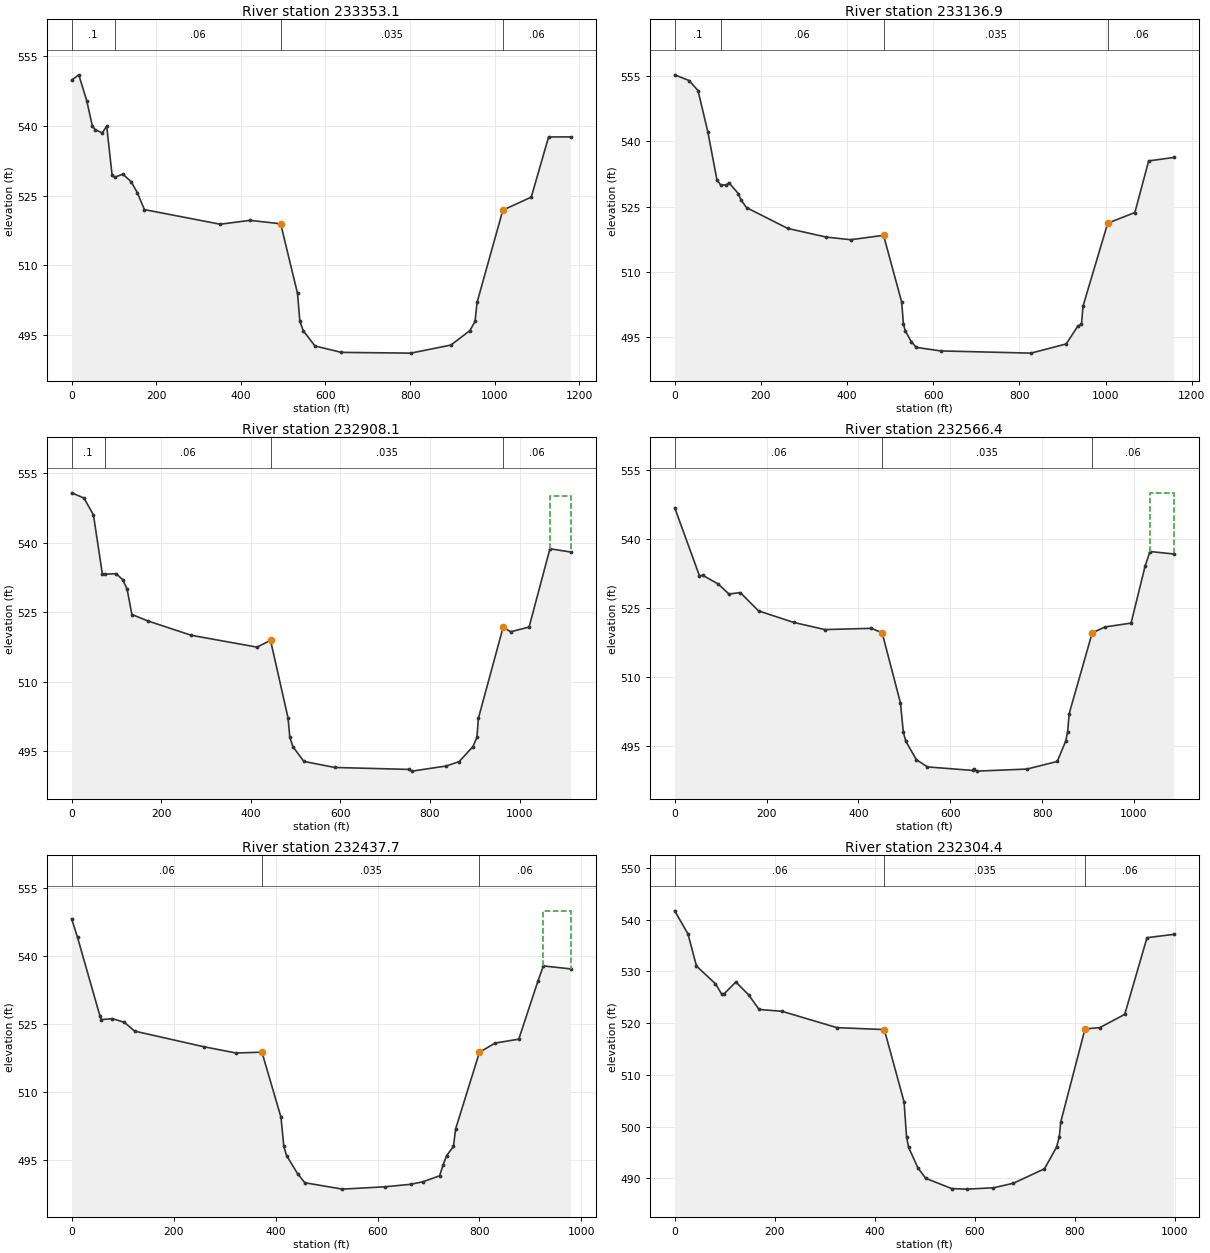
Type RM Length L Ch R = 1 ,233353.1,212.41,216.18,219.59
BEGIN DESCRIPTION:
Riverside Park in LOB.
Effective flow limit in ROB set at West Fork Levee Loop.
END DESCRIPTION:
XS GIS Cut Line= 2
 2332996.7072729 6966937.7860421 2332101.1121197 6966170.3895139
#Sta/Elev= 30
       0  549.77   16.94  550.91   35.95  545.28   48.83  539.99   55.34  539.16
   72.47  538.44   82.91  539.92   95.69  529.36  101.43  528.91  121.02  529.59
  140.44     528  155.09  525.65  172.11  521.98  351.23  518.84  421.34  519.67
  494.08  518.94  533.97  503.99  539.46     498  547.44     496  575.06  492.71
  637.59  491.33  801.82  491.17  896.37   492.9  941.35     496  953.58     498
  958.31  502.06 1019.24  521.86 1086.43  524.66 1127.36  537.57  1179.4  537.59
#Mann= 4 ,-1,0
       0      .1       0  101.43     .06       0  494.08    .035       0
 1019.24     .06       0
Bank Sta=494.08,1019.24
XS Rating Curve= 0 ,0
Exp/Cntr=0.3,0.1

Type RM Length L Ch R = 1 ,233136.9,231.03,228.81,226.98
BEGIN DESCRIPTION:
Riverside Park in LOB.
Effective flow limit in ROB set at West Fork Levee Loop.
END DESCRIPTION:
XS GIS Cut Line= 2
  2333131.140948 6966780.6311734 2332260.5242383 6966016.8603496
#Sta/Elev= 30
       0  555.31   33.43     554   54.18  551.69   77.02  542.17   98.03  531.17
  106.67     530  119.77     530  125.98  530.51  147.78     528  153.82  526.55
  166.98  524.77  262.33     520  352.23     518  408.85   517.4  484.79  518.42
  526.91  503.04   530.9     498  535.39  496.42  548.99     494  560.68  492.65
  617.46  491.84  827.09  491.33  908.72  493.44   935.4   497.5   944.2     498
  947.78  502.15 1005.11  521.21 1068.14  523.65 1100.04  535.52 1158.15  536.31
#Mann= 4 ,-1,0
       0      .1       0  106.67     .06       0  484.79    .035       0
 1005.11     .06       0
Bank Sta=484.79,1005.11
XS Rating Curve= 0 ,0
Exp/Cntr=0.3,0.1

Type RM Length L Ch R = 1 ,232908.1,363.66,341.7,324.54
BEGIN DESCRIPTION:
Riverside Park in LOB.
Effective flow limit in ROB set at West Fork Levee Loop.
END DESCRIPTION:
XS GIS Cut Line= 2
 2333260.7002492 6966586.3186676 2332419.7240106 6965856.2195258
#Sta/Elev= 30
       0  550.74   27.45  549.62   48.67     546   68.78  533.14   73.95  533.19
    99.6  533.29     114     532  123.84  529.96  134.59  524.49  171.13  523.07
  267.27     520  413.86  517.45  443.93  518.93  482.96  502.21  487.05     498
  493.76     496  518.35   492.8   587.2  491.49  752.93  491.07   759.6   490.7
  835.73   491.8  864.91  492.75  895.75     496   904.6     498  907.86  502.09
  962.99  521.71  980.31  520.77 1021.03  521.78 1067.54  538.68 1113.68  537.97
#Mann= 4 ,-1,0
       0      .1       0   73.95     .06       0  443.93    .035       0
  962.99     .06       0
#XS Ineff= 2 , 0
       0                 1067.54       0     550
Permanent Ineff=
       F       T
Bank Sta=443.93,962.99
XS Rating Curve= 0 ,0
Exp/Cntr=0.3,0.1

Type RM Length L Ch R = 1 ,232566.4,169.58,128.68,94.76
BEGIN DESCRIPTION:
Riverside Park in LOB.
Effective flow limit in ROB set at West Fork Levee Loop.
END DESCRIPTION:
XS GIS Cut Line= 2
 2333499.9264801 6966287.8844806  2332635.853747 6965629.3559255
#Sta/Elev= 30
       0  546.78   53.77     532   61.63  532.03   94.99  530.17  118.06     528
  142.99   528.3  182.62  524.32  258.82  521.83   326.9  520.26  428.05  520.53
  451.62  519.58  491.57  504.32  497.75     498  503.07     496  526.02     492
  550.27   490.4  650.14  489.62  650.92     490  657.44  489.48  766.94  489.93
  832.92  491.58   851.3     496  855.53     498  858.96     502  909.06  519.56
  937.25  520.84  993.68  521.67 1024.06  534.01 1034.82  537.24 1086.41   536.7
#Mann= 3 ,-1,0
       0     .06       0  451.62    .035       0  909.06     .06       0
#XS Ineff= 2 , 0
       0                 1034.82       0     550
Permanent Ineff=
       F       T
Bank Sta=451.62,909.06
XS Rating Curve= 0 ,0
Exp/Cntr=0.3,0.1

Type RM Length L Ch R = 1 ,232437.7,172.04,133.32,99.75
BEGIN DESCRIPTION:
Riverside Park in LOB.
Effective flow limit in ROB set at West Fork Levee Loop.
END DESCRIPTION:
XS GIS Cut Line= 2
 2333533.0862232 6966064.9106566 2332687.6096152 6965571.9455244
#Sta/Elev= 30
       0  548.25   11.64  544.12   55.79   526.7    58.1     526   80.16  526.21
  103.58  525.39  123.52  523.46  258.91  520.02  322.39  518.63  373.28  518.81
  410.62  504.46  416.25     498  421.61     496  443.21     492  457.43     490
  531.28  488.59  614.83  489.11  664.68  489.65  689.12  490.22  721.71  491.53
  728.85     494  735.54     496  748.92     498  753.19  501.87  799.92  518.79
  830.73  520.82  877.09  521.68  914.49  534.46   925.3  537.84   978.7  537.19
#Mann= 3 ,-1,0
       0     .06       0  373.28    .035       0  799.92     .06       0
#XS Ineff= 2 , 0
       0                   925.3       0     550
Permanent Ineff=
       F       T
Bank Sta=373.28,799.92
XS Rating Curve= 0 ,0
Exp/Cntr=0.3,0.1

Type RM Length L Ch R = 1 ,232304.4,161.1,129.93,102.41
BEGIN DESCRIPTION:
Riverside Park in LOB.
Effective flow limit in ROB set at West Fork Levee Loop.
END DESCRIPTION:
XS GIS Cut Line= 2
  2333654.553286 6965896.1174425 2332736.1471003 6965505.3772638
#Sta/Elev= 30
       0  541.69   26.56  537.24   43.61  531.01   81.58  527.59   94.04   525.6
   98.11  525.58  122.27  527.93  147.94  525.45  168.74  522.63  214.59  522.27
  324.65  519.11  419.31  518.74  458.86  504.74  463.74     498  467.87     496
  486.53     492  501.93     490  554.23     488  585.13   487.9   637.6  488.16
   677.5  489.04  739.66  491.83  763.72     496  769.25     498  772.19  500.88
   820.8  518.87  850.18  519.11  900.21  521.68  944.73   536.5  998.07  537.14
#Mann= 3 ,-1,0
       0     .06       0  419.31    .035       0   820.8     .06       0
Bank Sta=419.31,820.8
XS Rating Curve= 0 ,0
Exp/Cntr=0.3,0.1

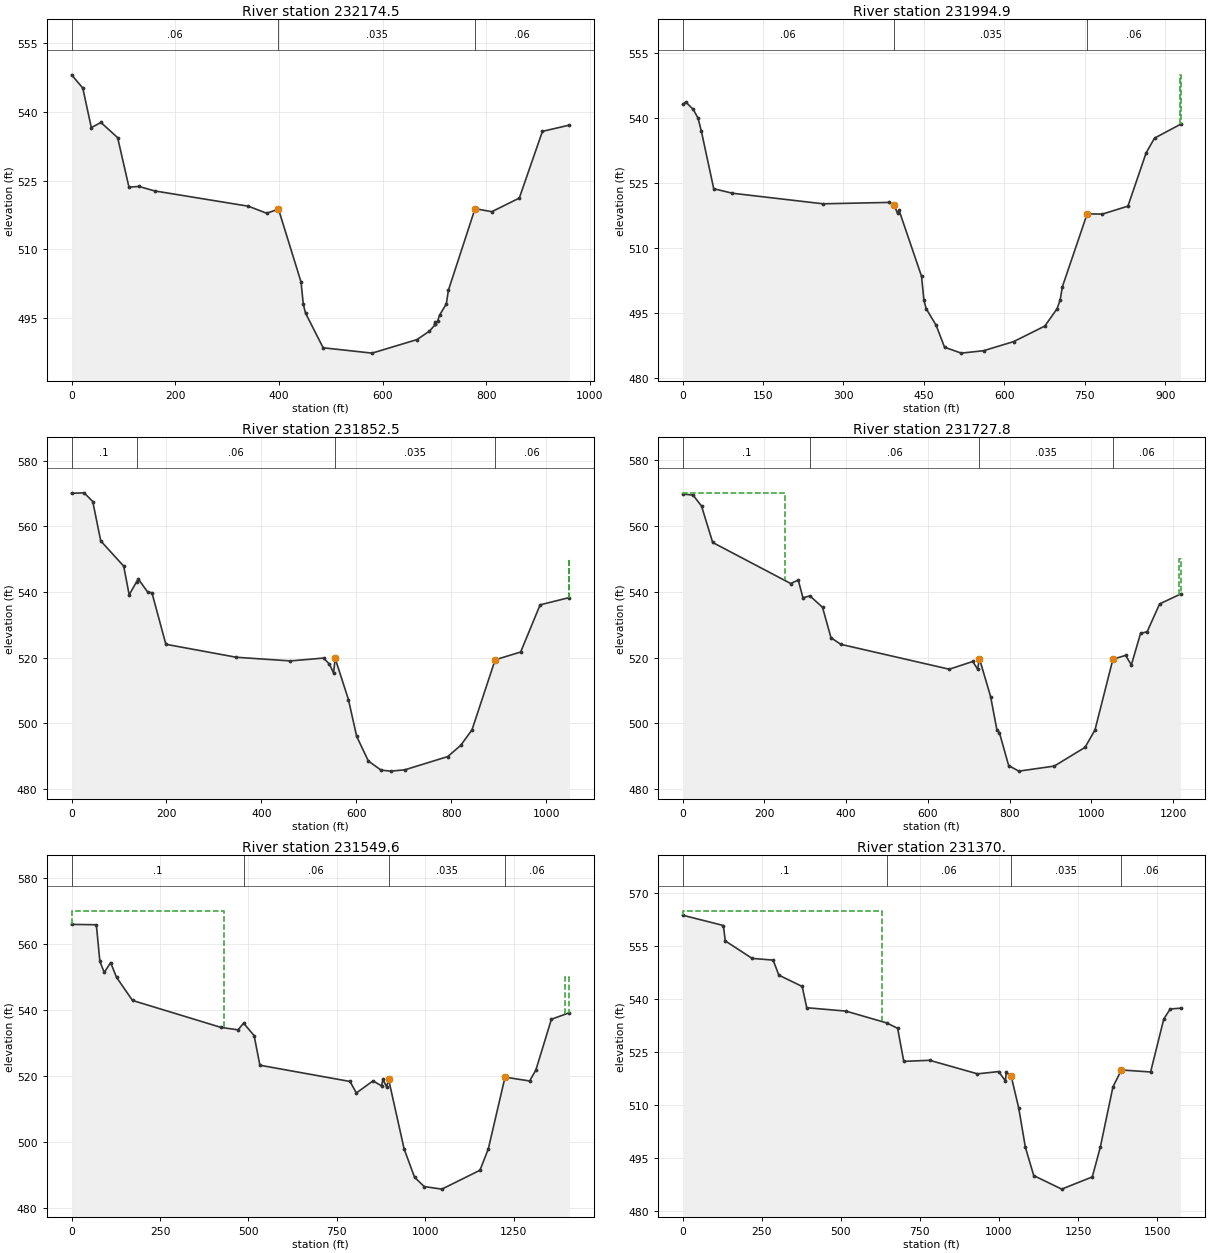
Type RM Length L Ch R = 1 ,232174.5,186.04,179.57,175.68
BEGIN DESCRIPTION:
Riverside Park in LOB.
Effective flow limit in ROB set at West Fork Levee Loop.
END DESCRIPTION:
XS GIS Cut Line= 2
 2333696.8969457 6965709.0459746 2332778.0291205 6965428.8047398
#Sta/Elev= 30
       0  548.14   21.61  545.26   38.11   536.6   56.74  537.71   88.93  534.39
  110.75  523.57  130.34  523.71  160.16  522.74  341.22  519.39  376.42  517.85
  399.29  518.75   442.8   502.8  447.06     498  451.43     496  485.41  488.41
  579.83  487.24  666.47   490.2  690.41  492.04  701.91  493.51  701.96     494
  702.08  493.63  706.19   494.2  709.96  495.53  723.08     498  727.13     501
  778.53  518.86  810.86  518.19  863.92  521.17  908.54  535.77  960.65  537.14
#Mann= 3 ,-1,0
       0     .06       0  399.29    .035       0  778.53     .06       0
Bank Sta=399.29,778.53
XS Rating Curve= 0 ,0
Exp/Cntr=0.3,0.1

Type RM Length L Ch R = 1 ,231994.9,144.79,142.42,141.92
BEGIN DESCRIPTION:
Riverside Park in LOB.
Effective flow limit in ROB set at West Fork Levee Loop.
END DESCRIPTION:
XS GIS Cut Line= 2
 2333754.0962968 6965525.7665363 2332859.6621779 6965275.9831375
#Sta/Elev= 30
       0  543.18    5.92  543.71   19.86     542   28.69     540   34.91  536.98
      58   523.7   92.96  522.66  261.85  520.22  384.63  520.54  394.12     520
  400.81     518  403.59  518.74  445.58  503.49     450     498  454.19     496
  472.72   492.2   488.5   487.1  519.68  485.74  561.35   486.3  617.31   488.4
  675.55  491.99  698.43     496  704.15     498  708.34  501.09  754.45  517.88
  783.01  517.85  830.56  519.68   864.6  532.01  880.19  535.39  928.66  538.58
#Mann= 3 ,-1,0
       0     .06       0  394.12    .035       0  754.45     .06       0
#XS Ineff= 2 , 0
       0                  927.96       0     550
Permanent Ineff=
       F       T
Bank Sta=394.12,754.45
XS Rating Curve= 0 ,0
Exp/Cntr=0.3,0.1

Type RM Length L Ch R = 1 ,231852.5,124.4,124.72,125.17
BEGIN DESCRIPTION:
Riverside Park in LOB.
Effective flow limit in ROB set at West Fork Levee Loop.
END DESCRIPTION:
XS GIS Cut Line= 2
 2333939.7886798 6965423.7894498 2332926.9656134 6965149.9138102
#Sta/Elev= 30
       0  570.08   26.41  570.22   44.68  567.57   61.49  555.57  109.87  547.88
  121.43  539.13  137.13  543.14  140.96   543.9  160.27     540  169.43  539.75
  198.71  524.06  347.38   520.1  461.18  518.99     531  519.86  543.56     518
  552.08  515.33  555.59  519.73  583.49  507.22  600.82     496  625.49  488.48
  652.31   485.7  672.91   485.4  702.45   485.8  792.82  489.84  820.14  493.26
  843.92     498  892.67  519.33  946.41   521.7  987.41  536.08  1049.2  538.31
#Mann= 4 ,-1,0
       0      .1       0  137.13     .06       0  555.59    .035       0
  892.67     .06       0
#XS Ineff= 2 , 0
       0                 1047.31       0     550
Permanent Ineff=
       F       T
Bank Sta=555.59,892.67
XS Rating Curve= 0 ,0
Exp/Cntr=0.3,0.1

Type RM Length L Ch R = 1 ,231727.8,179.25,178.16,177.24
BEGIN DESCRIPTION:
Ineffective flow in LOB.
Effective flow limit in ROB set at West Fork Levee Loop.
END DESCRIPTION:
XS GIS Cut Line= 2
 2334138.4505271 6965349.2436801 2332963.0318315 6965030.1437036
#Sta/Elev= 30
       0  569.66   25.54  569.29   46.12     566   73.52  554.92  264.39  542.46
  282.81  543.52  294.22  538.15  311.56   538.7  342.13  535.24  362.92     526
  387.01     524  652.26  516.44  709.69  518.79  721.57  516.46  726.03  519.66
  753.36  508.13  768.82     498  774.84   497.2  797.57  487.17  822.47   485.5
  909.12  487.03  984.47  492.73 1008.68     498 1052.59  519.48 1083.66  520.64
 1097.68  517.75 1120.17   527.3 1136.32  527.84 1166.83  536.27 1217.96  539.26
#Mann= 4 ,-1,0
       0      .1       0  311.56     .06       0  726.03    .035       0
 1052.59     .06       0
#XS Ineff= 2 , 0
       0  249.71     570 1214.01       0     550
Permanent Ineff=
       F       T
Bank Sta=726.03,1052.59
XS Rating Curve= 0 ,0
Exp/Cntr=0.3,0.1

Type RM Length L Ch R = 1 ,231549.6,175.32,179.65,183.77
BEGIN DESCRIPTION:
Ineffective flow in LOB.
Effective flow limit in ROB set at West Fork Levee Loop.
END DESCRIPTION:
XS GIS Cut Line= 2
 2334358.0441803 6965220.0708286 2332998.6697269 6964856.7544476
#Sta/Elev= 30
       0   565.9   70.03  565.79   80.06  554.68   92.42  551.35  110.38  554.35
  127.12  549.88  172.31  542.89  422.52  534.73  470.55     534  486.15  536.02
     516  532.25  532.28   523.3  786.99  518.38  804.91  514.91  852.11  518.57
  876.16  517.03  879.92  518.99  890.21   516.8  896.14  518.99  939.86     498
  969.36  489.42  996.58   486.6 1046.46  485.82 1154.24  491.53 1177.84     498
 1225.07  519.69 1294.55  518.54 1312.14  521.81 1356.12   537.2 1407.09  539.19
#Mann= 4 ,-1,0
       0      .1       0  486.15     .06       0  896.14    .035       0
 1225.07     .06       0
#XS Ineff= 2 , 0
       0  429.56     570  1395.8       0     550
Permanent Ineff=
       F       T
Bank Sta=896.14,1225.07
XS Rating Curve= 0 ,0
Exp/Cntr=0.3,0.1

Type RM Length L Ch R = 1 ,231370. ,187.56,192.09,197.21
BEGIN DESCRIPTION:
Upstream of Sump 29 outfall.
Ineffective flow in LOB.
Effective flow limit in ROB set at West Fork Levee Loop.
END DESCRIPTION:
XS GIS Cut Line= 2
 2334549.0972078 6965105.0326241 2333034.9116039 6964674.2008501
#Sta/Elev= 30
       0  563.76   128.8  560.84  134.75  556.48   219.8  551.52  286.08  551.04
   304.2  546.78     378  543.57  392.38  537.55  516.32  536.59  644.98  533.25
   679.8  531.72  699.19  522.35  780.88  522.66   932.3  518.82  998.99  519.46
  1020.5  516.85 1023.19   519.2 1038.94  518.12 1062.61  509.15 1083.76     498
 1110.14     490 1198.56  486.16 1295.26  489.62 1320.55     498 1360.53   515.1
 1387.24  519.91 1479.71  519.35  1521.3  534.34 1541.55  537.19 1574.28  537.42
#Mann= 4 ,-1,0
       0      .1       0  644.98     .06       0 1038.94    .035       0
 1387.24     .06       0
#XS Ineff= 1 ,-1
       0  631.83     565
Permanent Ineff=
       F
Bank Sta=1038.94,1387.24
XS Rating Curve= 0 ,0
Exp/Cntr=0.3,0.1

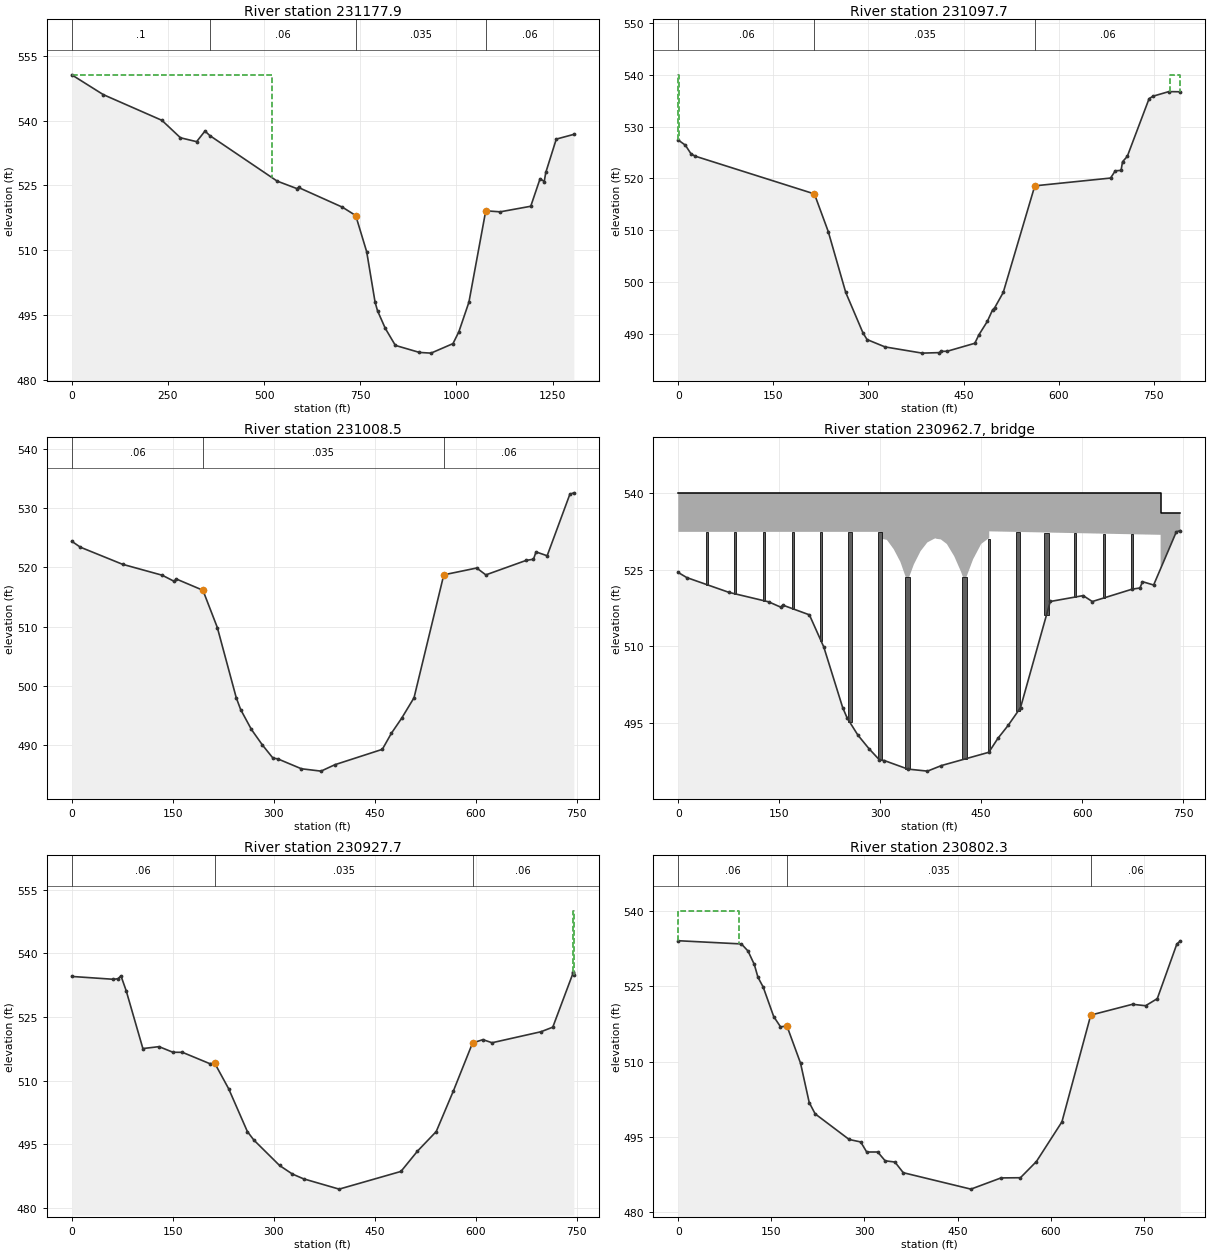
Type RM Length L Ch R = 1 ,231177.9,80.59,80.14,79.81
BEGIN DESCRIPTION:
Downstream of Sump 29 outfall.
Ineffective flow in LOB.
Effective flow limit in ROB set at West Fork Levee Loop.
END DESCRIPTION:
XS GIS Cut Line= 2
 2334317.8526344 6964856.4275015 2333069.2106022 6964476.6217361
#Sta/Elev= 30
       0  550.58   81.97     546  234.41  540.05  282.54  536.02  324.54  535.12
  346.34  537.58  358.78  536.53  533.88     526  584.84  524.28  589.55  524.52
  703.71  519.96  738.14  518.03  766.65  509.65  788.45     498  794.83     496
  814.97  491.94  841.15     488  903.81  486.37  933.86  486.21  990.97  488.41
 1006.22  491.15 1032.39     498 1076.12  519.13 1113.54  518.89 1193.09  520.18
 1217.34  526.55 1228.15   525.9 1232.17  527.99 1259.45  535.71 1305.13  536.81
#Mann= 4 ,-1,0
       0      .1       0  358.78     .06       0  738.14    .035       0
 1076.12     .06       0
#XS Ineff= 1 ,-1
       0  521.17 550.579
Permanent Ineff=
       F
Bank Sta=738.14,1076.12
XS Rating Curve= 0 ,0
Exp/Cntr=0.3,0.1

Type RM Length L Ch R = 1 ,231097.7,29.03,89.21,150.4
BEGIN DESCRIPTION:
Ineffective flow in LOB.
Effective flow limit in ROB set at West Fork Levee Loop.
END DESCRIPTION:
XS GIS Cut Line= 2
 2333841.3628859 6964627.2225165 2333083.6688247 6964397.8168525
#Sta/Elev= 30
       0  527.42    11.2  526.43    20.3  524.73   27.17  524.29  214.71  517.02
  236.56  509.75  264.15     498  291.23  490.22  297.71  488.92  326.03   487.5
  384.69   486.3   411.8   486.4  413.82  486.64     424  486.66  467.62   488.2
  474.07  489.83  487.28  492.41  495.59  494.63  498.95  495.05  512.42     498
  562.22  518.58  681.65  520.08  689.12  521.48  698.25  521.56  700.58  523.23
  708.07  524.27  742.42   535.4  748.49  535.87  773.47  536.76  791.66  536.73
#Mann= 3 ,-1,0
       0     .06       0  214.71    .035       0  562.22     .06       0
#XS Ineff= 2 , 0
       0     .84     540  775.35       0     540
Permanent Ineff=
       F       T
Bank Sta=214.71,562.22
XS Rating Curve= 0 ,0
Exp/Cntr=0.3,0.1

Type RM Length L Ch R = 1 ,231008.5,82.11,80.86,81.09
BEGIN DESCRIPTION:
Upstream of Belknap Street.
Effective flow limit in ROB set at West Fork Levee Loop.
END DESCRIPTION:
XS GIS Cut Line= 3
 2333775.1222195 6964589.1290256 2333157.0193358 6964229.5288361
 2333130.4401888 6964214.0656073
#Sta/Elev= 30
       0  524.43   12.73  523.43    75.4  520.54  134.38  518.69  151.95  517.67
  155.57  518.04  194.84  516.15  216.23  509.86  244.34     498  250.89     496
  266.87  492.64  283.29     490  298.89   487.8  306.08  487.67  341.11     486
  370.26   485.6  391.02  486.69  461.34  489.28  474.83     492  489.97  494.52
  508.45     498  552.66  518.76  601.53  519.91  615.11  518.75   674.6  521.18
  685.91   521.4  689.67  522.63  706.21  521.98  739.93  532.37  745.85  532.61
#Mann= 3 ,-1,0
       0     .06       0  194.84    .035       0  552.66     .06       0
#XS Ineff= 2 , 0
               0
Permanent Ineff=
       F       F
Bank Sta=194.84,552.66
XS Rating Curve= 0 ,0
Exp/Cntr=0.5,0.3

Type RM Length L Ch R = 3 ,230962.7,,,
BEGIN DESCRIPTION:
Belknap Street
Data from USACE 1949 survey, USACE 1975 survey, Fort Worth Floodway DPR.
Downstream cross-section represents fill area in LOB.
END DESCRIPTION:
Node Name=Belknap Street
Bridge Culvert--1,0,-1,-1, 0
Deck Dist Width WeirC Skew NumUp NumDn MinLoCord MaxHiCord MaxSubmerge Is_Ogee
19.8,52,2.6,0, 29, 29, , , 0.95, 0, 0,0,,
       0     300     300     310     320     330     338     343     350     360
     370     380     382     384     390     399     410     420     423     428
     438     450     460     462     462     462   716.6   716.6  745.85
     540     540     540     540     540     540     540     540     540     540
     540     540     540     540     540     540     540     540     540     540
     540     540     540     540     540     540     540     536     536
  532.37  532.37  531.07   530.8     529   526.5   523.5   523.5     526   528.6
   530.3     531   531.1     531   530.9     530   527.6   524.6   523.5   523.5
     527     530     531  531.07  531.07  532.47  531.79     450     450
       0     300     300     310     320     330     338     343     350     360
     370     380     382     384     390     399     410     420     423     428
     438     450     460     462     462     462   716.6   716.6  745.95
     540     540     540     540     540     540     540     540     540     540
     540     540     540     540     540     540     540     540     540     540
     540     540     540     540     540     540     540     536     536
  532.37  532.37  531.07   530.8     529   526.5   523.5   523.5     526   528.6
   530.3     531   531.1     531   530.9     530   527.6   524.6   523.5   523.5
     527     530     531  531.07  531.07  532.47  531.79     450     450
Pier Skew, UpSta & Num, DnSta & Num=  ,42.5, 2 ,42.5, 2 , 0 , 0 , 0 ,,
       3       3
     450     539
       3       3
     450     539
Pier Skew, UpSta & Num, DnSta & Num=  ,85, 2 ,85, 2 , 0 , 0 , 0 ,,
       3       3
     450     539
       3       3
     450     539
Pier Skew, UpSta & Num, DnSta & Num=  ,127.5, 2 ,127.5, 2 , 0 , 0 , 0 ,,
       3       3
     450     539
       3       3
     450     539
Pier Skew, UpSta & Num, DnSta & Num=  ,170, 2 ,170, 2 , 0 , 0 , 0 ,,
       3       3
     450     539
       3       3
     450     539
Pier Skew, UpSta & Num, DnSta & Num=  ,212.5, 2 ,212.5, 2 , 0 , 0 , 0 ,,
       3       3
     450     539
       3       3
     450     539
Pier Skew, UpSta & Num, DnSta & Num=  ,255, 4 ,255, 4 , 0 , 0 , 0 ,,
     6.2     6.2       3       3
     450     505     505     539
     6.2     6.2       3       3
     450     505     505     539
Pier Skew, UpSta & Num, DnSta & Num=  ,300, 4 ,300, 4 , 0 , 0 , 0 ,,
     6.2     6.2       3       3
     450     497     497     539
     6.2     6.2       3       3
     450     497     497     539
Pier Skew, UpSta & Num, DnSta & Num=  ,340.5, 2 ,340.5, 2 , 0 , 0 , 0 ,,
       8       5
     450   523.5
       8       5
     450   523.5
Pier Skew, UpSta & Num, DnSta & Num=  ,425.5, 2 ,425.5, 2 , 0 , 0 , 0 ,,
       8       5
     450   523.5
       8       5
     450   523.5
Pier Skew, UpSta & Num, DnSta & Num=  ,462, 2 ,462, 2 , 0 , 0 , 0 ,,
       3       3
     450     539
       3       3
     450     539
Pier Skew, UpSta & Num, DnSta & Num=  ,504.5, 4 ,504.5, 4 , 0 , 0 , 0 ,,
     6.2     6.2       3       3
     450     512     512     539
     6.2     6.2       3       3
     450     512     512     539
Pier Skew, UpSta & Num, DnSta & Num=  ,547, 4 ,547, 4 , 0 , 0 , 0 ,,
     6.2     6.2       3       3
     450     518     518     539
     6.2     6.2       3       3
     450     518     518     539
Pier Skew, UpSta & Num, DnSta & Num=  ,589.5, 2 ,589.5, 2 , 0 , 0 , 0 ,,
       3       3
     450     539
       3       3
     450     539
Pier Skew, UpSta & Num, DnSta & Num=  ,632, 2 ,632, 2 , 0 , 0 , 0 ,,
       3       3
     450     539
       3       3
     450     539
Pier Skew, UpSta & Num, DnSta & Num=  ,674.5, 2 ,674.5, 2 , 0 , 0 , 0 ,,
       3       3
     450     539
       3       3
     450     539
BR Coef=-1 , 0 , 0 ,, 0 ,,,0.8,-1,,0,
WSPro=,,,, 1 ,,,, 0 ,,,, 0 ,,,,-1 ,-1 ,-1 , 0 , 0 , 0 , 0 , 0
BC Design=,, 0 ,, 0 ,,,,,,
BC Use User HTab Curves=0
BC User HTab FreeFlow(D)= 0

Type RM Length L Ch R = 1 ,230927.7,205.31,125.38,42.25
BEGIN DESCRIPTION:
Downstream of Belknap Street.
Effective flow limit in ROB set at West Fork Levee Loop.
END DESCRIPTION:
XS GIS Cut Line= 3
  2333818.013987 6964522.9608267 2333199.9111032 6964163.3606372
 2333173.2886959 6964147.8722404
#Sta/Elev= 30
       0  534.54   61.87  533.87   68.56     534   73.09  534.67   80.86  531.17
  105.65  517.55  129.65     518  150.27  516.68  164.47  516.66  204.94     514
   212.5  514.06  233.08  508.08  260.87     498  270.48     496  308.73     490
  327.59     488   344.3  486.86  397.22  484.43  489.06   488.6  513.62  493.39
  541.47     498  567.08  507.62  595.43  518.87  610.84  519.65  624.41  518.92
  697.04  521.51  714.61  522.59  744.95  535.43  745.23  535.54   745.9  534.95
#Mann= 3 ,-1,0
       0     .06       0   212.5    .035       0  595.43     .06       0
#XS Ineff= 2 , 0
       0                  745.23       0     550
Permanent Ineff=
       F       T
Bank Sta=212.5,595.43
XS Rating Curve= 0 ,0
Exp/Cntr=0.5,0.3

Type RM Length L Ch R = 1 ,230802.3,44.59,44.09,43.75
BEGIN DESCRIPTION:
Ineffective flow in LOB.
Effective flow limit in ROB set at West Fork Levee Loop.
END DESCRIPTION:
XS GIS Cut Line= 2
 2334001.8821097 6964327.3501299 2333210.8084401  6964159.465805
#Sta/Elev= 30
       0  534.05  101.73  533.41  112.38     532  122.52  529.33  128.36  526.79
  136.92   524.8  153.75  518.96  164.71  516.92  175.17  517.05  196.97  509.69
  210.96  501.85  220.54  499.59  275.31  494.49  293.91     494  303.54     492
  321.26     492   333.3  490.25  349.03     490  362.46  487.88  471.41  484.61
  519.86  486.84  551.16  486.88  576.89   490.1  618.01     498  664.47  519.25
  731.69   521.4  752.74  521.11   771.6  522.52  803.09  533.39  808.69     534
#Mann= 3 ,-1,0
       0     .06       0  175.17    .035       0  664.47     .06       0
#XS Ineff= 1 ,-1
       0    98.5     540
Permanent Ineff=
       F
Bank Sta=175.17,664.47
XS Rating Curve= 0 ,0
Exp/Cntr=0.3,0.1