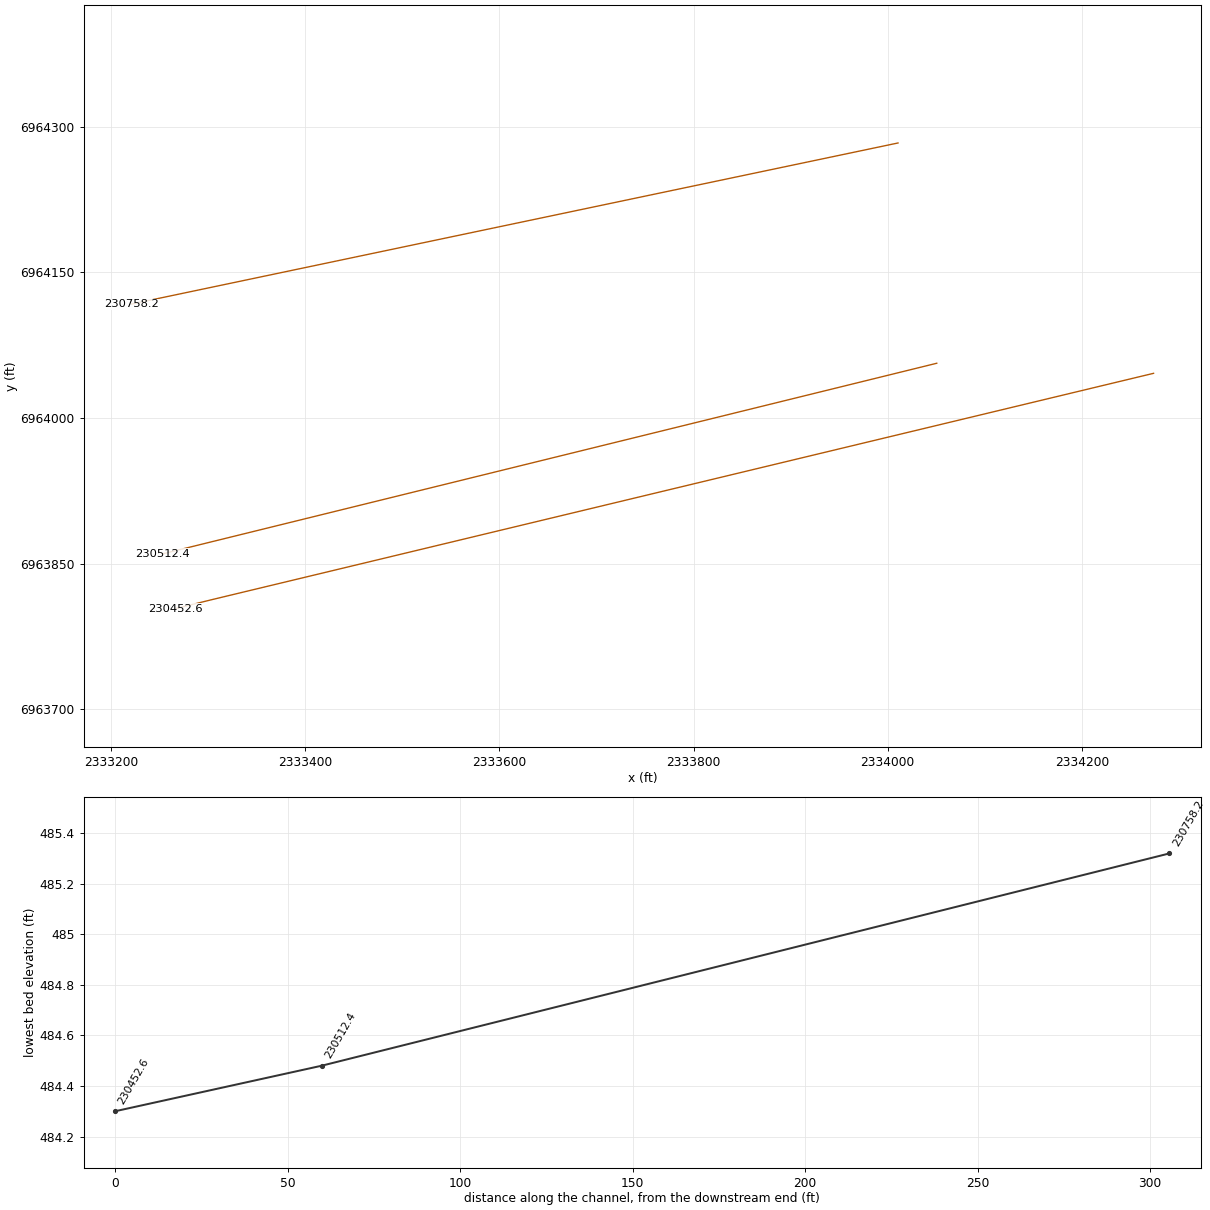
HEC-RAS study CDC_Consolidated_Model.prj: Upper Trinity CDC Consolidated Model

--- CDC_Consolidated_Model.g11 (geometry) --- (continued)

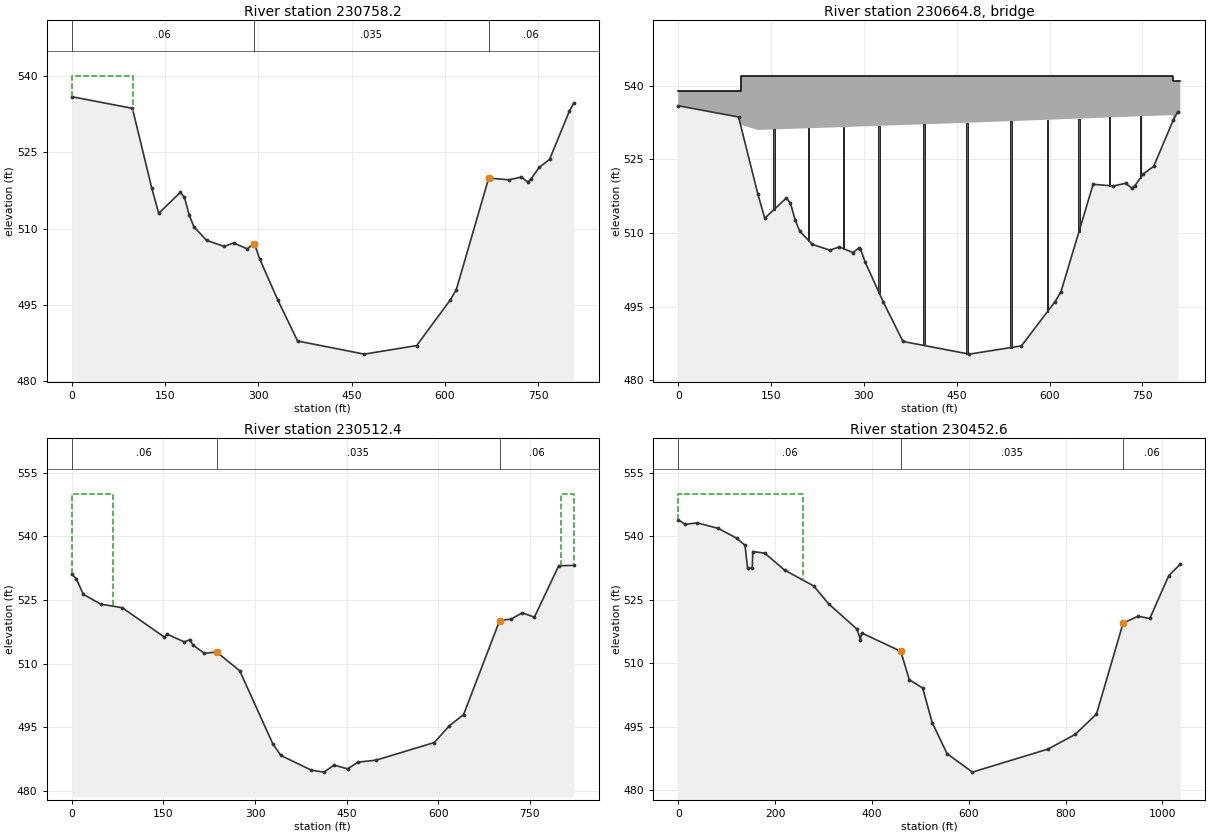
Type RM Length L Ch R = 1 ,230758.2,236.96,245.78,256.24
BEGIN DESCRIPTION:
Upstream of SH 121.
Ineffective flow in LOB.
Effective flow limit in ROB set at West Fork Levee Loop.
END DESCRIPTION:
XS GIS Cut Line= 2
 2334010.6965592 6964283.2567515 2333220.5357976 6964117.1720558
#Sta/Elev= 30
       0   535.9   97.52  533.61  128.52     518  139.81  512.99  174.65  517.11
  181.25  516.11  188.96  512.61  196.41  510.36  216.73  507.67  245.02  506.49
  260.54  507.16  282.25     506  292.36  506.96  294.49  506.74  302.32     504
  331.18     496  363.14   487.9  470.44  485.32  554.64     487  608.87     496
  618.43     498  670.49  519.91  702.94  519.57  723.02  520.11  733.18  519.14
  738.09  519.66  751.54     522  768.35  523.58  800.07  533.02  807.43  534.68
#Mann= 3 ,-1,0
       0     .06       0  292.36    .035       0  670.49     .06       0
#XS Ineff= 1 ,-1
       0   98.78     540
Permanent Ineff=
       F
Bank Sta=292.36,670.49
XS Rating Curve= 0 ,0
Exp/Cntr=0.5,0.3

Type RM Length L Ch R = 3 ,230664.8,,,
BEGIN DESCRIPTION:
SH 121
North (west bound) bridge represented.  Bridge length 698.5 feet.  Double bridges - total bridge width set at 156 feet.
Data from USACE 1975 survey.
Note:  Internal bridge cross-sections modified to represent geometry under bridge.
END DESCRIPTION:
Node Name=SH 121
Bridge Culvert--1,0,-1,-1, 0
Deck Dist Width WeirC Skew NumUp NumDn MinLoCord MaxHiCord MaxSubmerge Is_Ogee
15.4,156,2.6,0, 8, 8, , , 0.95, 0, 0,0,,
       0  100.63  100.63  435.85  799.13  799.13  807.43  811.35
     539     539     542     542     542     541     541     541
     470     470  530.85   532.3     534     470     470     470
       0  100.63  100.63  435.85  799.13  799.13  807.43  821.92
     539     539     542     542     542     541     541     541
     470     470  530.85   532.3     534     470     470     470
Pier Skew, UpSta & Num, DnSta & Num=  ,154.78, 2 ,146, 2 , 0 , 0 , 0 ,,
     2.5     2.5
     470     537
     2.5     2.5
     470     537
Pier Skew, UpSta & Num, DnSta & Num=  ,210.78, 2 ,202, 2 , 0 , 0 , 0 ,,
     2.5     2.5
     470     537
     2.5     2.5
     470     537
Pier Skew, UpSta & Num, DnSta & Num=  ,266.78, 2 ,258, 2 , 0 , 0 , 0 ,,
     2.5     2.5
     470     537
     2.5     2.5
     470     537
Pier Skew, UpSta & Num, DnSta & Num=  ,324.78, 2 ,316, 2 , 0 , 0 , 0 ,,
     2.5     2.5
     470     537
     2.5     2.5
     470     537
Pier Skew, UpSta & Num, DnSta & Num=  ,396.78, 2 ,388, 2 , 0 , 0 , 0 ,,
     2.5     2.5
     470     537
     2.5     2.5
     470     537
Pier Skew, UpSta & Num, DnSta & Num=  ,466.78, 2 ,458, 2 , 0 , 0 , 0 ,,
     2.5     2.5
     470     537
     2.5     2.5
     470     537
Pier Skew, UpSta & Num, DnSta & Num=  ,537.78, 2 ,529, 2 , 0 , 0 , 0 ,,
     2.5     2.5
     470     537
     2.5     2.5
     470     537
Pier Skew, UpSta & Num, DnSta & Num=  ,596.78, 2 ,588, 2 , 0 , 0 , 0 ,,
     2.5     2.5
     470     537
     2.5     2.5
     470     537
Pier Skew, UpSta & Num, DnSta & Num=  ,647.28, 2 ,638.5, 2 , 0 , 0 , 0 ,,
     2.5     2.5
     470     537
     2.5     2.5
     470     537
Pier Skew, UpSta & Num, DnSta & Num=  ,696.78, 2 ,688, 2 , 0 , 0 , 0 ,,
     2.5     2.5
     470     537
     2.5     2.5
     470     537
Pier Skew, UpSta & Num, DnSta & Num=  ,747.28, 2 ,738.5, 2 , 0 , 0 , 0 ,,
     2.5     2.5
     470     537
     2.5     2.5
     470     537
BR Coef=-1 , 0 , 0 ,, 0 ,,,0.8,-1,,0,
WSPro=,,,, 1 ,,,, 0 ,,,, 0 ,,,,-1 ,-1 ,-1 , 0 , 0 , 0 , 0 , 0
BR U #Sta/Elev= 202
       0  536.32   95.94  535.62   98.55  535.56  100.63  536.32  105.36  534.01
  146.43  512.57  169.71  515.56  173.29  516.04  183.14  517.15  183.54  517.19
  183.95  517.13  192.17   515.6  228.08  512.53   246.8  510.94  247.54  510.88
  250.64   510.6  251.75  510.58  252.18  510.56  253.25  510.53  253.72  510.52
   268.3  510.08     298  502.68  300.86  501.94  325.45  496.31  336.49  493.82
  340.87  492.83  362.05  488.38  393.54  487.27  393.92  487.23  394.31  487.25
  394.69  487.26  395.25  487.21  395.65   487.2  396.08  487.19  396.53  487.17
  396.96  487.15  397.42   487.1   397.9  487.12   398.4  487.07   398.9  487.05
  399.39  487.07  399.55  487.03  400.09  487.05  400.64  487.03  401.21  487.01
  401.79  487.03  402.36  487.05  402.98  487.06  403.61  487.04  404.24  486.98
  404.91  486.92  405.61  486.98  405.82  486.97  406.55  486.99  407.31  486.97
  408.04  486.99  408.84  486.92  409.66  486.85  410.52  486.78   411.4  486.75
  412.28  486.77  413.23  486.74  414.54  486.65  415.57  486.61  416.65  486.63
  417.71   486.7  418.88  486.67   419.7  486.64   421.3  486.48  422.18  486.68
  423.99  486.69  425.42  486.35  426.94   486.3  428.94  486.24  430.63  486.19
  432.38  486.13  434.25  486.07  438.16  486.09  440.31  486.03  442.62  485.96
  444.91  485.89   447.5  485.73  451.13  485.62  454.12  485.53  456.29  485.46
  460.53  485.33  464.14  485.12  468.01     485  468.02     485   468.8  485.03
  469.57  485.06  469.75  485.08  470.13  485.09  471.34  485.15  472.01  485.18
  472.32  485.17  473.69   485.3  474.26  485.32   474.9  485.37  475.98  485.41
  476.55  485.43  477.27  485.45   478.2  485.49  479.07  485.51  479.57  485.53
  480.74  485.52  481.53   485.5  481.87  485.55   482.2  485.56  483.38  485.59
  484.02  485.61  484.28  485.62  485.56  485.59  487.28  485.62  487.73  485.66
  487.91  485.66  488.26  485.67  489.53  485.69  489.69   485.7  491.67  485.73
  491.84  485.74  491.93  485.74  493.75  485.87  493.82  485.87  493.85  485.87
  495.29   485.9   495.7  485.91  495.71  485.91  497.68  485.94  497.76  485.94
   499.4  485.96  499.51  485.96  501.15  485.99  502.97  486.02  503.18  486.02
  504.45  486.04  506.15  486.07   506.6  486.08  508.05   486.1  509.41  486.12
  510.94  486.14   512.2  486.16  513.41  486.18  514.76   486.2  520.56  486.39
  521.59  486.41  522.96  486.44  524.06  486.46  525.12  486.48  526.29  486.51
  527.27  486.53  528.22  486.55  529.12  486.57  531.28  486.62  532.27  486.64
  532.94   486.7  534.35  486.73  535.22  486.75  536.53  486.78  537.23  486.79
  537.89  486.77  540.72  486.84  541.93  486.87  543.72  486.91   544.2  486.92
  544.73  486.96  546.33     487  546.65  487.01  548.38  487.05  548.76  487.06
  550.55   487.1  550.81  487.11  553.04  487.16  553.22  487.17  553.42  487.16
  555.38  487.31  557.54  487.27  557.57  487.28  557.61  487.27  558.51   487.3
  561.55  488.12  567.26  489.77  571.73  490.98   575.9  492.11  579.72  493.15
  583.83  494.26  587.09  495.14  590.13  495.97  680.66  519.97  687.56  519.92
  711.06  519.72  718.29  519.73  734.21  519.65  740.67  519.63   741.5  519.88
  747.36  521.25   767.9  523.76  770.46  524.11  799.93  538.66  804.06  540.49
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BR U #Mann= 3
       0     .06   268.3    .035  680.66     .06
BR U Banks=268.3,680.66
BR D #Sta/Elev= 202
       0  536.32   95.94  535.62   98.55  535.56  100.63  536.32  105.36  534.01
  146.43  512.57  169.71  515.56  173.29  516.04  183.14  517.15  183.54  517.19
  183.95  517.13  192.17   515.6  228.08  512.53   246.8  510.94  247.54  510.88
  250.64   510.6  251.75  510.58  252.18  510.56  253.25  510.53  253.72  510.52
   268.3  510.08     298  502.68  300.86  501.94  325.45  496.31  336.49  493.82
  340.87  492.83  362.05  488.38  393.54  487.27  393.92  487.23  394.31  487.25
  394.69  487.26  395.25  487.21  395.65   487.2  396.08  487.19  396.53  487.17
  396.96  487.15  397.42   487.1   397.9  487.12   398.4  487.07   398.9  487.05
  399.39  487.07  399.55  487.03  400.09  487.05  400.64  487.03  401.21  487.01
  401.79  487.03  402.36  487.05  402.98  487.06  403.61  487.04  404.24  486.98
  404.91  486.92  405.61  486.98  405.82  486.97  406.55  486.99  407.31  486.97
  408.04  486.99  408.84  486.92  409.66  486.85  410.52  486.78   411.4  486.75
  412.28  486.77  413.23  486.74  414.54  486.65  415.57  486.61  416.65  486.63
  417.71   486.7  418.88  486.67   419.7  486.64   421.3  486.48  422.18  486.68
  423.99  486.69  425.42  486.35  426.94   486.3  428.94  486.24  430.63  486.19
  432.38  486.13  434.25  486.07  438.16  486.09  440.31  486.03  442.62  485.96
  444.91  485.89   447.5  485.73  451.13  485.62  454.12  485.53  456.29  485.46
  460.53  485.33  464.14  485.12  468.01     485  468.02     485   468.8  485.03
  469.57  485.06  469.75  485.08  470.13  485.09  471.34  485.15  472.01  485.18
  472.32  485.17  473.69   485.3  474.26  485.32   474.9  485.37  475.98  485.41
  476.55  485.43  477.27  485.45   478.2  485.49  479.07  485.51  479.57  485.53
  480.74  485.52  481.53   485.5  481.87  485.55   482.2  485.56  483.38  485.59
  484.02  485.61  484.28  485.62  485.56  485.59  487.28  485.62  487.73  485.66
  487.91  485.66  488.26  485.67  489.53  485.69  489.69   485.7  491.67  485.73
  491.84  485.74  491.93  485.74  493.75  485.87  493.82  485.87  493.85  485.87
  495.29   485.9   495.7  485.91  495.71  485.91  497.68  485.94  497.76  485.94
   499.4  485.96  499.51  485.96  501.15  485.99  502.97  486.02  503.18  486.02
  504.45  486.04  506.15  486.07   506.6  486.08  508.05   486.1  509.41  486.12
  510.94  486.14   512.2  486.16  513.41  486.18  514.76   486.2  520.56  486.39
  521.59  486.41  522.96  486.44  524.06  486.46  525.12  486.48  526.29  486.51
  527.27  486.53  528.22  486.55  529.12  486.57  531.28  486.62  532.27  486.64
  532.94   486.7  534.35  486.73  535.22  486.75  536.53  486.78  537.23  486.79
  537.89  486.77  540.72  486.84  541.93  486.87  543.72  486.91   544.2  486.92
  544.73  486.96  546.33     487  546.65  487.01  548.38  487.05  548.76  487.06
  550.55   487.1  550.81  487.11  553.04  487.16  553.22  487.17  553.42  487.16
  555.38  487.31  557.54  487.27  557.57  487.28  557.61  487.27  558.51   487.3
  561.55  488.12  567.26  489.77  571.73  490.98   575.9  492.11  579.72  493.15
  583.83  494.26  587.09  495.14  590.13  495.97  680.66  519.97  687.56  519.92
  711.06  519.72  718.29  519.73  734.21  519.65  740.67  519.63   741.5  519.88
  747.36  521.25   767.9  523.76  770.46  524.11  799.93  538.66  804.06  540.49
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BR D #Mann= 3
       0     .06   268.3    .035  680.66     .06
BR D Banks=268.3,680.66
BC Design=,, 0 ,, 0 ,,,,,,
BC Use User HTab Curves=0
BC User HTab FreeFlow(D)= 0

Type RM Length L Ch R = 1 ,230512.4,61.55,59.84,58.34
BEGIN DESCRIPTION:
Downstream of SH 121.
Ineffective flow in LOB.
Effective flow limit in ROB set at West Fork Levee Loop.
END DESCRIPTION:
XS GIS Cut Line= 2
 2334050.6056247 6964056.3118685 2333252.5234871 6963859.8154876
#Sta/Elev= 30
       0  531.12    7.38     530   18.95  526.34   47.19  524.04   82.64  523.19
  151.78  516.25  156.05  516.96  184.35  515.13  193.78   515.7  197.83  514.47
  216.88  512.47  237.24  512.74  274.99  508.34  329.28  491.09  342.42   488.4
  392.16  484.94  412.89  484.48  429.13  486.14   451.4  485.25  468.75  486.83
     498   487.3  593.36  491.44  618.13   495.4  641.33     498  700.52  520.17
  719.18  520.52   737.4  521.98  757.33  520.96  797.12  533.06  821.92  533.16
#Mann= 3 ,-1,0
       0     .06       0  237.24    .035       0  700.52     .06       0
#XS Ineff= 2 , 0
       0   68.31     550  800.62       0     550
Permanent Ineff=
       F       T
Bank Sta=237.24,700.52
XS Rating Curve= 0 ,0
Exp/Cntr=0.5,0.3

Type RM Length L Ch R = 1 ,230452.6,127.58,126.07,123.26
BEGIN DESCRIPTION:
Ineffective flow in LOB.
Effective flow limit in ROB set at West Fork Levee Loop.
END DESCRIPTION:
XS GIS Cut Line= 3
 2334273.9717321 6964045.9358044 2333305.3543102 6963813.1350612
 2333265.7452261 6963803.3957771
#Sta/Elev= 30
       0  543.88   14.29  542.81   39.34  543.14   82.37  541.85  120.39  539.55
  137.99  537.85  143.17   532.5  152.87   532.5  153.89  536.38  178.64     536
  219.68     532  279.83  528.25  310.92     524  369.34  518.05  376.18  515.61
  378.67  517.16   459.6  512.83  477.19  506.13  504.84  504.15  524.52     496
  555.15  488.67  607.49   484.3  763.86  489.75  819.87  493.21  863.84     498
  918.79  519.47  949.51  521.09  973.99  520.57 1013.09  530.69 1036.99   533.4
#Mann= 3 ,-1,0
       0     .06       0   459.6    .035       0  918.79     .06       0
#XS Ineff= 2 , 0
       0  258.28     550               0
Permanent Ineff=
       F       F
Bank Sta=459.6,918.79
XS Rating Curve= 0 ,0
Exp/Cntr=0.3,0.1