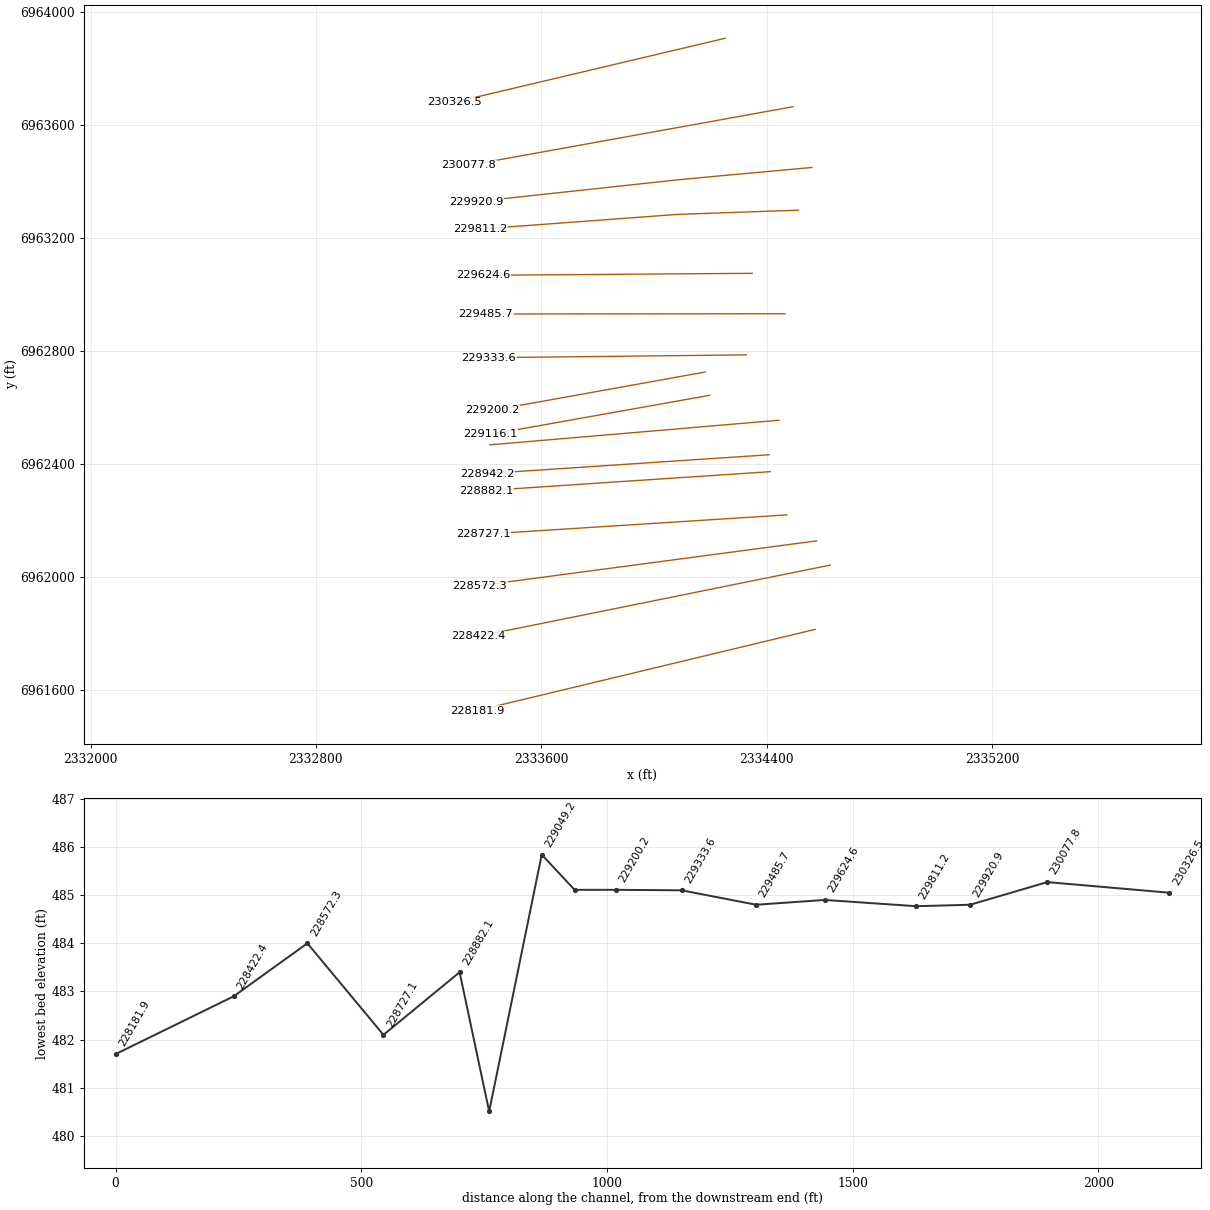
HEC-RAS study CDC_Consolidated_Model.prj: Upper Trinity CDC Consolidated Model

--- CDC_Consolidated_Model.g11 (geometry) --- (continued)

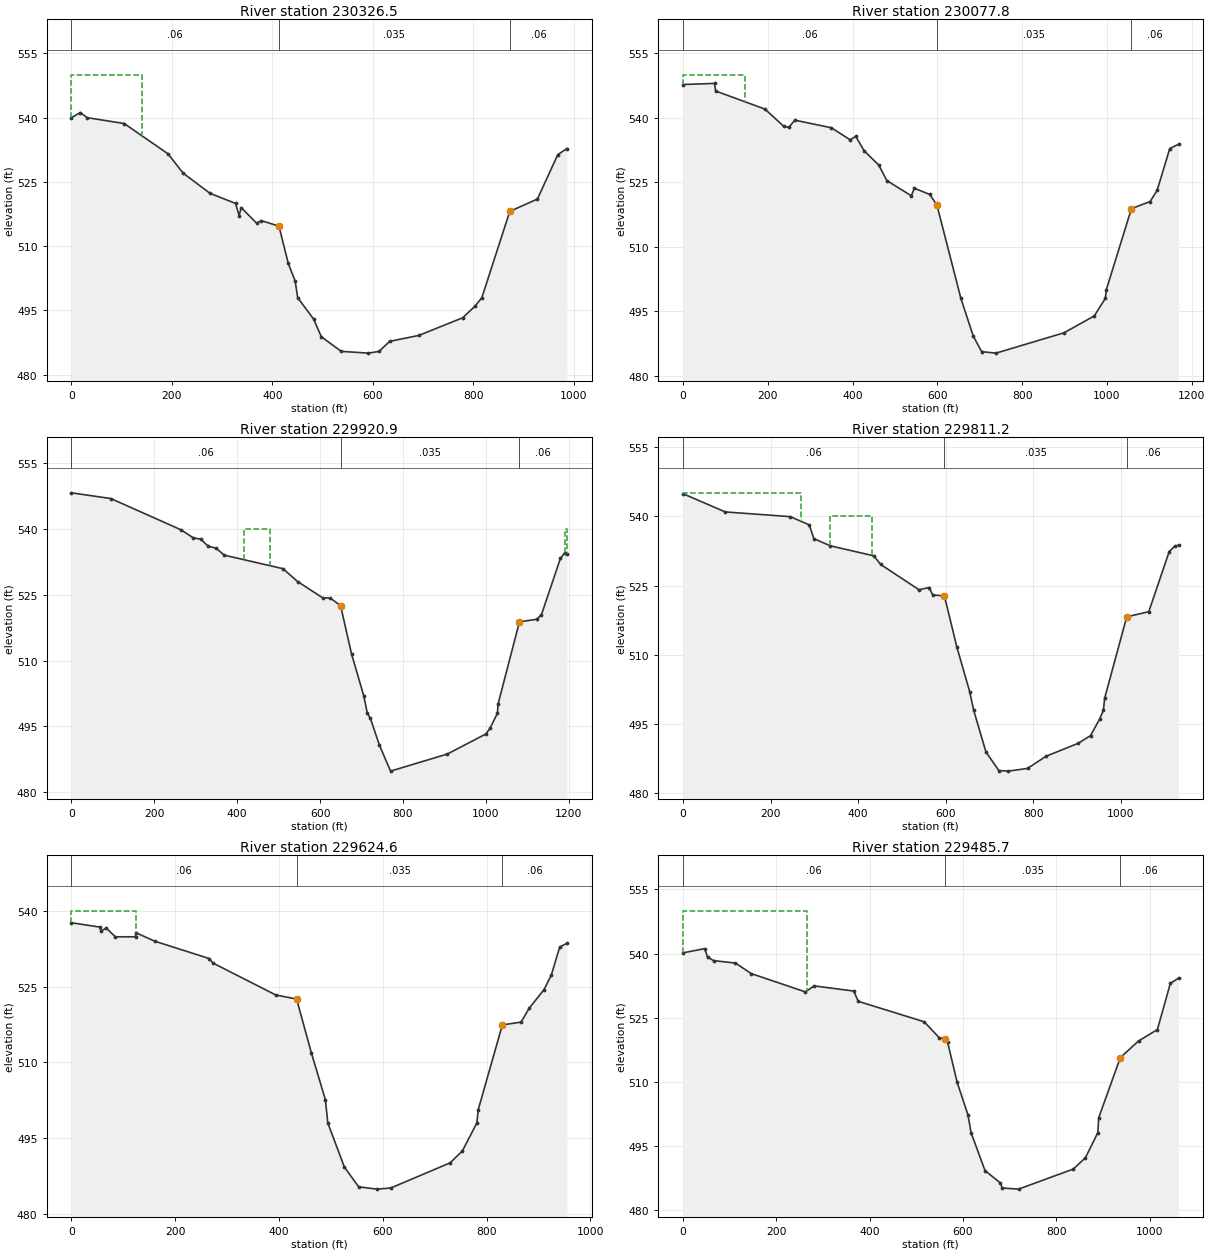
Type RM Length L Ch R = 1 ,230326.5,261.76,248.68,233.16
BEGIN DESCRIPTION:
Ineffective flow in LOB.
Effective flow limit in ROB set at West Fork Levee Loop.
END DESCRIPTION:
XS GIS Cut Line= 2
 2334253.1858982 6963908.7496638 2333292.6916981 6963682.1161702
#Sta/Elev= 30
       0     540    17.7   541.2   31.24     540  105.01  538.64  192.48  531.55
  222.34  527.06  275.92  522.35  326.83  519.98  333.89  517.14  338.11  519.01
  368.65   515.4  378.29  515.97  413.31  514.68  431.83  505.97   445.6  501.87
  450.54     498  482.57  492.95  497.67  488.87  537.36  485.46  591.37  485.05
  612.48  485.45  633.84   487.8  691.78  489.18  779.15   493.3  803.64     496
  817.38     498  873.01  518.13  928.05  521.01  968.52  531.36  986.87   532.8
#Mann= 3 ,-1,0
       0     .06       0  413.31    .035       0  873.01     .06       0
#XS Ineff= 2 , 0
       0  140.91     550               0
Permanent Ineff=
       F       F
Bank Sta=413.31,873.01
XS Rating Curve= 0 ,0
Exp/Cntr=0.3,0.1

Type RM Length L Ch R = 1 ,230077.8,173.61,156.96,136.62
BEGIN DESCRIPTION:
Ineffective flow in LOB.
Effective flow limit in ROB set at West Fork Levee Loop.
END DESCRIPTION:
XS GIS Cut Line= 2
 2334492.8010419 6963666.0220508 2333342.3399182 6963458.6617797
#Sta/Elev= 30
       0  547.75   74.31     548   76.92  546.24  193.28  542.03  237.84     538
  249.86  537.79  263.54  539.46  350.21  537.68  394.15  534.89  407.55  535.68
  427.03  532.35  461.67  529.02  480.84   525.4   538.5  521.87  545.79  523.62
  581.93  522.18  598.73  519.78  655.49     498  684.44  489.29  704.39  485.62
  738.35  485.27  898.81     490  970.14  493.92   996.3     498  998.55     500
 1057.79  518.87    1102  520.53 1118.57  523.16 1148.27  532.85    1169  533.85
#Mann= 3 ,-1,0
       0     .06       0  598.73    .035       0 1057.79     .06       0
#XS Ineff= 2 , 0
       0  145.44     550               0
Permanent Ineff=
       F       F
Bank Sta=598.73,1057.79
XS Rating Curve= 0 ,0
Exp/Cntr=0.3,0.1

Type RM Length L Ch R = 1 ,229920.9,117.69,109.64,101.27
BEGIN DESCRIPTION:
Ineffective flow in LOB.
Effective flow limit in ROB set at West Fork Levee Loop.
END DESCRIPTION:
XS GIS Cut Line= 4
 2334560.2601721 6963450.8613555 2334206.3674077 6963418.6596343
 2334082.2150316 6963406.8449818 2333370.5528199 6963330.2436782
#Sta/Elev= 30
       0  548.21   94.99  546.91  264.01   539.8  293.29     538  312.79  537.61
  330.17  536.02  348.73  535.61  369.03     534  510.44  530.93  545.71     528
  606.17   524.3  624.82  524.23  649.53  522.49  676.12  511.44   705.7  501.89
  713.91     498  721.26  496.85  743.26  490.72  770.11   484.8  907.28   488.7
 1000.54  493.29 1010.25  494.59 1028.05     498 1029.57  500.08 1081.14  518.81
 1123.24  519.41 1134.34  520.48 1180.03  533.26  1189.9  534.47 1195.84  534.38
#Mann= 3 ,-1,0
       0     .06       0  649.53    .035       0 1081.14     .06       0
#XS Ineff= 2 ,-1
  415.71  480.13     540  1189.9 1195.84     540
Permanent Ineff=
       F       T
Bank Sta=649.53,1081.14
XS Rating Curve= 0 ,0
Exp/Cntr=0.3,0.1

Type RM Length L Ch R = 1 ,229811.2,202.6,186.62,171.17
BEGIN DESCRIPTION:
Ineffective flow in LOB.
Effective flow limit in ROB set at West Fork Levee Loop.
END DESCRIPTION:
XS GIS Cut Line= 3
 2334512.1804375 6963299.7526549 2334081.9806468 6963284.5720917
  2333382.811222 6963232.9480649
#Sta/Elev= 30
       0  544.93   96.48  540.98  244.88  539.96  288.13  538.18  298.87  535.18
  336.47  533.63  435.53  531.46  451.35  529.59  538.92   524.1  561.59  524.59
  570.12     523  596.91  522.74   625.4  511.64   654.7  501.96  663.64     498
  691.68  488.94  721.07   484.9  742.71  484.77  786.63  485.36  829.04     488
  902.15  490.79  930.46  492.47  951.01     496  960.02     498  962.74  500.58
 1013.21  518.23 1063.58  519.35 1110.18  532.39 1123.15  533.58 1131.54  533.76
#Mann= 3 ,-1,0
       0     .06       0  596.91    .035       0 1013.21     .06       0
#XS Ineff= 2 ,-1
       0   269.4 545.126  335.16  430.75     540
Permanent Ineff=
       F       F
Bank Sta=596.91,1013.21
XS Rating Curve= 0 ,0
Exp/Cntr=0.3,0.1

Type RM Length L Ch R = 1 ,229624.6,140.21,138.89,138.81
BEGIN DESCRIPTION:
Ineffective flow in LOB.
Effective flow limit in ROB set at West Fork Levee Loop.
END DESCRIPTION:
XS GIS Cut Line= 2
 2334348.8005007 6963076.0052833   2333393.84766  6963069.060208
#Sta/Elev= 30
       0  537.64   54.68  536.78   57.11     536   67.04  536.59   84.54  534.86
  123.55  534.86  124.05  535.68  160.21     534  265.91  530.54  272.61  529.67
  393.74  523.34  433.92  522.54  462.54  511.82  489.44  502.59  494.08     498
  526.02  489.27  553.53  485.35  589.25   484.9  615.33  485.12  729.81   490.1
  753.49  492.48  781.35     498  784.02  500.64  830.45  517.41  866.49  517.97
  882.18  520.71  910.87  524.42  924.72  527.25     941  532.83  954.98  533.57
#Mann= 3 ,-1,0
       0     .06       0  433.92    .035       0  830.45     .06       0
#XS Ineff= 2 , 0
       0   123.9     540               0
Permanent Ineff=
       F       F
Bank Sta=433.92,830.45
XS Rating Curve= 0 ,0
Exp/Cntr=0.3,0.1

Type RM Length L Ch R = 1 ,229485.7,149.79,152.1,155.12
BEGIN DESCRIPTION:
Ineffective flow in LOB.
Effective flow limit in ROB set at West Fork Levee Loop.
END DESCRIPTION:
XS GIS Cut Line= 2
 2334464.9417915 6962932.7723263 2333403.0820057 6962931.9334414
#Sta/Elev= 30
       0  540.16   46.44  541.15   52.44  539.19    65.4  538.34  112.39  537.76
   145.8  535.31   262.1  531.01  280.92  532.41  365.77  531.21  375.38   528.8
  516.67  524.01  549.02  520.27  562.39  519.96  567.02   519.2  587.33  509.85
  610.49  502.22  617.31     498  647.15  489.13  680.02  486.25     684  485.07
  718.92   484.8  836.38   489.5  862.28  492.15  888.77     498  890.81  501.53
     937  515.61   976.1   519.5 1016.49  522.18 1044.25  532.99 1061.86  534.24
#Mann= 3 ,-1,0
       0     .06       0  562.39    .035       0     937     .06       0
#XS Ineff= 2 , 0
       0     266     550               0
Permanent Ineff=
       F       F
Bank Sta=562.39,937
XS Rating Curve= 0 ,0
Exp/Cntr=0.3,0.1

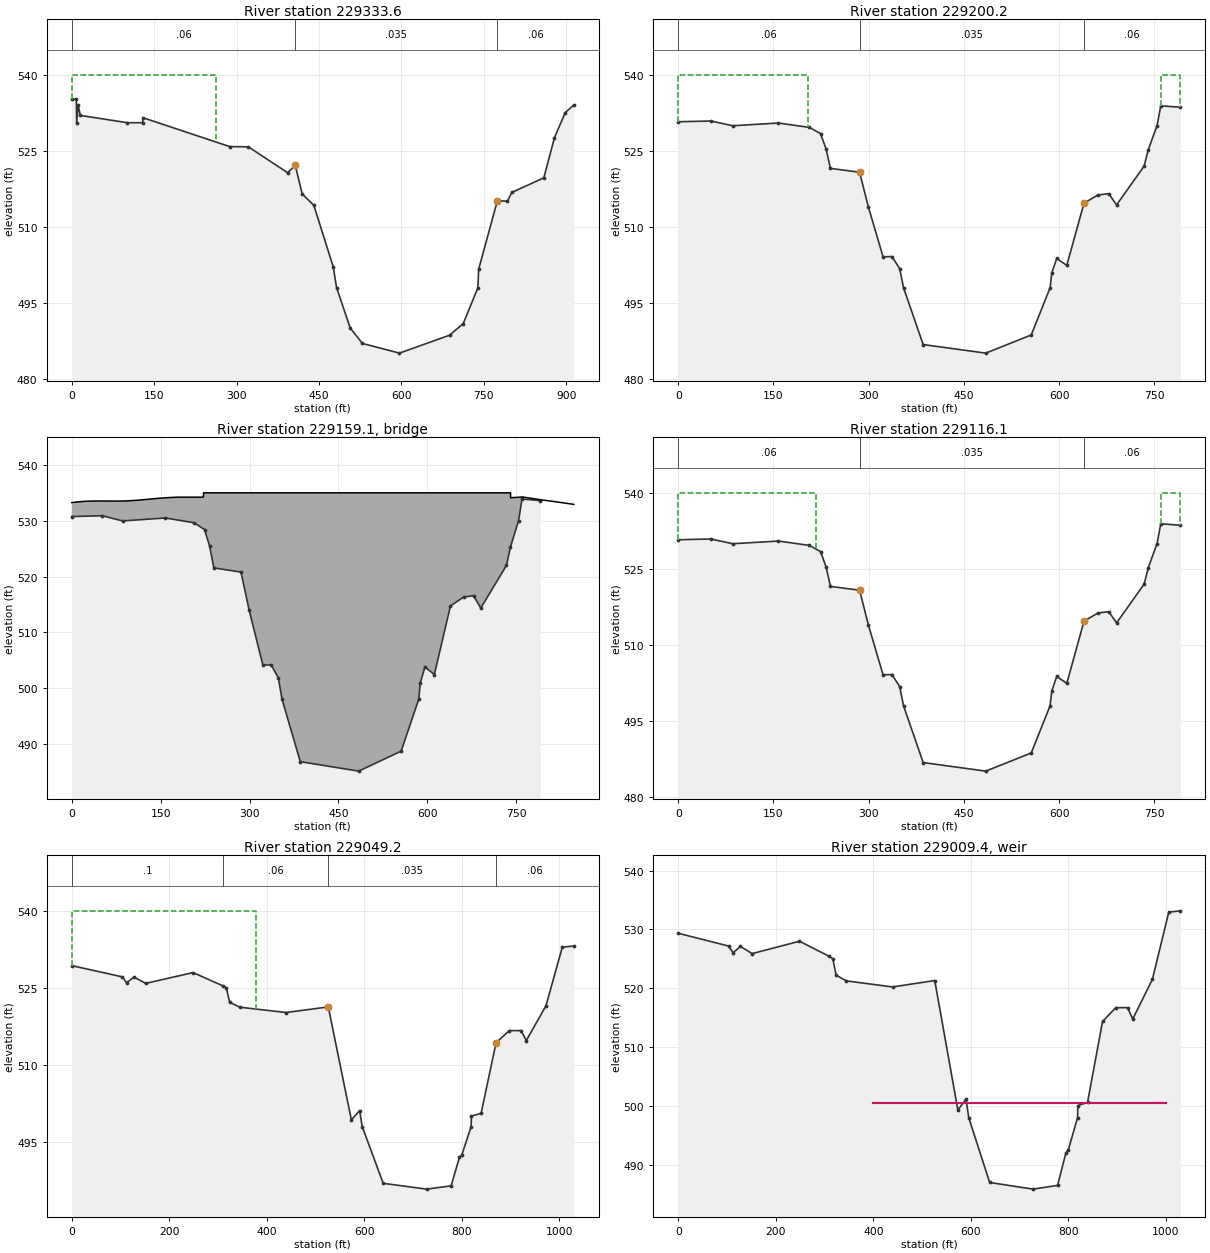
Type RM Length L Ch R = 1 ,229333.6,92.02,133.41,168.08
BEGIN DESCRIPTION:
Ineffective flow in LOB.
Effective flow limit in ROB set at West Fork Levee Loop.
END DESCRIPTION:
XS GIS Cut Line= 2
  2334327.362849 6962787.1288878 2333413.5064245 6962777.1335694
#Sta/Elev= 30
       0  535.29    8.35  535.14    8.85  530.55    11.7     534   15.51     532
  101.35  530.55  129.14  530.55  129.64  531.54  287.38  525.85  321.55  525.79
  393.05  520.68  406.75  522.19  419.38  516.51  440.66  514.24  475.86  502.15
  482.08     498   506.9  490.04  529.13  487.01  596.44   485.1   687.6  488.63
  712.59  490.93  739.27     498  740.67  501.66  774.79  515.19  792.96  515.04
  800.99   516.8  859.28  519.68  878.66   527.6  898.13  532.53  913.91  534.04
#Mann= 3 ,-1,0
       0     .06       0  406.75    .035       0  774.79     .06       0
#XS Ineff= 1 ,-1
       0  262.59     540
Permanent Ineff=
       F
Bank Sta=406.75,774.79
XS Rating Curve= 0 ,0
Exp/Cntr=0.3,0.1

Type RM Length L Ch R = 1 ,229200.2,84.97,84.14,83.35
BEGIN DESCRIPTION:
Upstream of 4th Street.
Copy of cross-section 229200.2
Ineffective flow in LOB.
Effective flow limit in ROB set at West Fork Levee Loop.
END DESCRIPTION:
XS GIS Cut Line= 2
  2334181.162228 6962726.3352045 2333426.0563816 6962590.7729045
#Sta/Elev= 30
       0  530.75   51.59  530.89   85.78  529.96  157.85  530.49  206.42  529.63
  224.07  528.41  232.65  525.45  239.75  521.54  285.57  520.79  299.39  513.95
  322.56  504.11  336.51  504.16  348.71  501.79  354.81     498  385.71   486.8
  484.26  485.11   555.9  488.69   585.6     498  588.27  500.92  596.01  503.78
  611.91  502.42  639.07  514.71  661.27  516.31     678  516.56   690.3  514.34
  733.68     522   740.3  525.25  754.04     530  759.91  533.89  790.66  533.61
#Mann= 3 ,-1,0
       0     .06       0  285.57    .035       0  639.07     .06       0
#XS Ineff= 2 , 0
       0  204.98     540  759.91       0     540
Permanent Ineff=
       F       T
Bank Sta=285.57,639.07
XS Rating Curve= 0 ,0
Exp/Cntr=0.5,0.3

Type RM Length L Ch R = 3 ,229159.1,,,
BEGIN DESCRIPTION:
4th Street
Data from USACE 1975 survey.
Bridge length 518.2 feet.
Note:  Internal bridge cross-sections modified to represent geometry under bridge.
END DESCRIPTION:
Node Name=4th Street
Bridge Culvert--1,0,-1,-1, 0
Deck Dist Width WeirC Skew NumUp NumDn MinLoCord MaxHiCord MaxSubmerge Is_Ogee
10.1,62,2.6,0, 63, 63, , , 0.95, 0, ,0,,
       0    5.67    7.26   20.41   21.65   34.79   35.97   49.33   50.27    63.8
   64.58   78.24   78.88   92.68   93.16  108.94  109.28  125.26   125.3  127.55
  141.32  141.44  157.34  157.53  157.72  173.57  173.77  182.89  192.09  192.18
   200.8  201.42  201.43  203.57  203.58  203.65  210.86  211.32  220.15  222.36
  222.36  442.36  740.56  740.56  756.92  759.66  760.68  760.71  760.73  760.76
  761.85  762.03  789.64  789.88  790.12  817.97  818.15  818.33   818.5  846.55
  846.76  846.96  847.35
  533.25  533.32  533.34  533.46  533.48  533.52  533.53  533.53  533.54  533.52
  533.53  533.52  533.52  533.55  533.56  533.66  533.66  533.81  533.81  533.83
  533.97  533.97  534.11  534.11  534.11   534.2   534.2  534.22  534.22  534.22
  534.22  534.22  534.22  534.22  534.22  534.22  534.22  534.22  534.22  534.28
     535     535     535  534.12  534.23  534.25  534.26  534.26  534.26  534.26
  534.26  534.23  533.79  533.79  533.78  533.38  533.37  533.37  533.37  532.94
  532.93  532.93  532.92
   530.3   530.7     529     529
       0    5.67    7.26   20.41   21.65   34.79   35.97   49.33   50.27    63.8
   64.58   78.24   78.88   92.68   93.16  108.94  109.28  125.26   125.3  127.55
  141.32  141.44  157.34  157.53  157.72  173.57  173.77  182.89  192.09  192.18
   200.8  201.42  201.43  203.57  203.58  203.65  210.86  211.32  220.15  222.36
  222.36  442.36  740.56  740.56  756.92  759.66  760.68  760.71  760.73  760.76
  761.85  762.03  789.64  789.88  790.12  817.97  818.15  818.33   818.5  846.55
  846.76  846.96  847.35
  533.25  533.32  533.34  533.46  533.48  533.52  533.53  533.53  533.54  533.52
  533.53  533.52  533.52  533.55  533.56  533.66  533.66  533.81  533.81  533.83
  533.97  533.97  534.11  534.11  534.11   534.2   534.2  534.22  534.22  534.22
  534.22  534.22  534.22  534.22  534.22  534.22  534.22  534.22  534.22  534.28
     535     535     535  534.12  534.23  534.25  534.26  534.26  534.26  534.26
  534.26  534.23  533.79  533.79  533.78  533.38  533.37  533.37  533.37  532.94
  532.93  532.93  532.92
   530.3   530.7     529     529
Pier Skew, UpSta & Num, DnSta & Num=  ,279.86, 2 ,279.86, 2 , 0 , 0 , 0 ,,
     2.5     2.5
     470     534
     2.5     2.5
     470     534
Pier Skew, UpSta & Num, DnSta & Num=  ,335.16, 2 ,335.16, 2 , 0 , 0 , 0 ,,
     2.5     2.5
     470     534
     2.5     2.5
     470     534
Pier Skew, UpSta & Num, DnSta & Num=  ,405.36, 2 ,405.36, 2 , 0 , 0 , 0 ,,
     2.5     2.5
     470     534
     2.5     2.5
     470     534
Pier Skew, UpSta & Num, DnSta & Num=  ,490.36, 2 ,490.36, 2 , 0 , 0 , 0 ,,
     2.5     2.5
     470     534
     2.5     2.5
     470     534
Pier Skew, UpSta & Num, DnSta & Num=  ,559.86, 2 ,559.86, 2 , 0 , 0 , 0 ,,
     2.5     2.5
     470     534
     2.5     2.5
     470     534
Pier Skew, UpSta & Num, DnSta & Num=  ,620.36, 2 ,620.36, 2 , 0 , 0 , 0 ,,
     2.5     2.5
     470     534
     2.5     2.5
     470     534
Pier Skew, UpSta & Num, DnSta & Num=  ,680.36, 2 ,680.36, 2 , 0 , 0 , 0 ,,
     2.5     2.5
     470     534
     2.5     2.5
     470     534
BR Coef=-1 , 0 , 0 ,, 0 ,,,0.8,-1,,0,
WSPro=,,,, 1 ,,,, 0 ,,,, 0 ,,,,-1 ,-1 ,-1 , 0 , 0 , 0 , 0 , 0
BR U #Sta/Elev= 322
       0  533.25    5.67  533.32    7.26  533.34   20.41  533.46   21.65  533.48
   34.79  533.52   35.97  533.53   49.33  533.53   50.27  533.54    63.8  533.52
   64.58  533.53   78.24  533.52   78.88  533.52   92.68  533.55   93.16  533.56
  108.94  533.66  109.28  533.66  125.26  533.81   125.3  533.81  127.55  533.83
  141.32  533.97  141.44  533.97  157.34  534.11  157.53  534.11  157.72  534.11
  173.57   534.2  173.77   534.2  182.89  534.22  192.09  534.22  192.18  534.22
   200.8  534.22  201.42  534.22  201.43  534.22  203.57  534.22  203.58  534.22
  203.65  534.22  210.86  534.22  211.32  534.22  220.15  534.22  222.36  534.28
  231.75   527.5  239.73  521.96  252.92  521.26  277.55  520.35  283.05  517.71
  290.58  514.23  300.49  510.31   309.5  506.93  318.32  506.82  323.17  506.78
   327.1  505.48  328.21  505.15  330.23  504.63     341  501.77  356.53  495.69
  357.43  495.34  358.41  494.95  359.52  494.52  360.76  494.04  362.17  493.49
  363.78  492.86  365.64  492.13   367.8  491.29  370.36  490.29  373.43  489.09
  375.15  488.42  376.53  488.14  378.39  487.76  379.53  487.53  380.31  487.37
  380.87  487.26   381.3  487.17  381.63   487.1  385.35  486.41  389.11  486.33
  389.16  486.31  389.27  486.31  389.33  486.31  389.51  486.31  389.57  486.31
  389.77  486.31  389.98   486.3  390.05   486.3  390.27   486.3   390.5   486.3
  390.59  486.29  390.84  486.28  391.02  486.27  391.22  486.27  391.33  486.28
  391.63  486.28  391.76  486.28  391.98  486.27  392.09  486.27  392.48  486.27
  392.61  486.28  392.87  486.26  393.04  486.26   393.5  486.23  393.67  486.23
   395.7  486.19   396.3  486.21  397.44  486.19  398.36  486.17  398.88  486.13
  399.44  486.12   401.2  486.15  402.14  486.13  402.44  486.13  404.07  486.15
  404.64  486.14  405.41  486.12  406.03  486.05  406.62  486.04  407.19  486.08
  408.34  486.05  408.91  486.04  409.31  486.08  409.83  486.06  410.27  486.05
  411.08  486.03  411.53  486.02  412.31  486.04   412.6  486.03  412.98  485.98
   413.3  485.97  413.61  485.97  413.91  485.96  414.24  485.95  414.52  485.94
  414.83  485.94  415.34  485.96  429.89  485.74  430.25  485.71  430.43  485.71
  430.73   485.7  431.23  485.78  431.42  485.78  431.57  485.77  431.75  485.78
  432.81  485.68  433.37  485.67  433.91  485.58  434.01  485.58  434.59  485.65
  435.14  485.65  435.27  485.63  435.37  485.63  436.51  485.61   436.6  485.61
  437.47   485.6  437.64   485.6  438.75  485.58   439.7  485.47  440.26  485.56
  440.31  485.56  441.54  485.54  441.58  485.54  443.13  485.52  443.16  485.52
  444.42   485.4  444.43   485.4   444.6   485.4  444.61  485.35  444.74   485.3
  445.24   485.5  445.27   485.5   445.5   485.5  445.78  485.41  445.85  485.41
  446.31  485.41   446.4  485.41  446.63   485.5   446.9   485.5   447.3   485.5
  447.45   485.5  447.65   485.5  447.88   485.5  447.98   485.5  448.14   485.5
  448.52   485.5  448.74   485.5  449.09   485.5  449.37   485.5  449.68   485.5
     450   485.5  450.15   485.5  450.27   485.5  450.42  485.45  450.83  485.45
  451.07   485.5  451.18  485.46   451.6  485.34   451.7  485.34  451.88  485.33
  452.15   485.4  452.41   485.4  452.47   485.4  452.55   485.4  452.61  485.42
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BR U #Mann= 3
       0     .06  277.55    .035  638.28     .06
BR U Banks=277.55,638.28
BR D #Sta/Elev= 322
       0  533.25    5.67  533.32    7.26  533.34   20.41  533.46   21.65  533.48
   34.79  533.52   35.97  533.53   49.33  533.53   50.27  533.54    63.8  533.52
   64.58  533.53   78.24  533.52   78.88  533.52   92.68  533.55   93.16  533.56
  108.94  533.66  109.28  533.66  125.26  533.81   125.3  533.81  127.55  533.83
  141.32  533.97  141.44  533.97  157.34  534.11  157.53  534.11  157.72  534.11
  173.57   534.2  173.77   534.2  182.89  534.22  192.09  534.22  192.18  534.22
   200.8  534.22  201.42  534.22  201.43  534.22  203.57  534.22  203.58  534.22
  203.65  534.22  210.86  534.22  211.32  534.22  220.15  534.22  222.36  534.28
  231.75   527.5  239.73  521.96  252.92  521.26  277.55  520.35  283.05  517.71
  290.58  514.23  300.49  510.31   309.5  506.93  318.32  506.82  323.17  506.78
   327.1  505.48  328.21  505.15  330.23  504.63     341  501.77  356.53  495.69
  357.43  495.34  358.41  494.95  359.52  494.52  360.76  494.04  362.17  493.49
  363.78  492.86  365.64  492.13   367.8  491.29  370.36  490.29  373.43  489.09
  375.15  488.42  376.53  488.14  378.39  487.76  379.53  487.53  380.31  487.37
  380.87  487.26   381.3  487.17  381.63   487.1  385.35  486.41  389.11  486.33
  389.16  486.31  389.27  486.31  389.33  486.31  389.51  486.31  389.57  486.31
  389.77  486.31  389.98   486.3  390.05   486.3  390.27   486.3   390.5   486.3
  390.59  486.29  390.84  486.28  391.02  486.27  391.22  486.27  391.33  486.28
  391.63  486.28  391.76  486.28  391.98  486.27  392.09  486.27  392.48  486.27
  392.61  486.28  392.87  486.26  393.04  486.26   393.5  486.23  393.67  486.23
   395.7  486.19   396.3  486.21  397.44  486.19  398.36  486.17  398.88  486.13
  399.44  486.12   401.2  486.15  402.14  486.13  402.44  486.13  404.07  486.15
  404.64  486.14  405.41  486.12  406.03  486.05  406.62  486.04  407.19  486.08
  408.34  486.05  408.91  486.04  409.31  486.08  409.83  486.06  410.27  486.05
  411.08  486.03  411.53  486.02  412.31  486.04   412.6  486.03  412.98  485.98
   413.3  485.97  413.61  485.97  413.91  485.96  414.24  485.95  414.52  485.94
  414.83  485.94  415.34  485.96  429.89  485.74  430.25  485.71  430.43  485.71
  430.73   485.7  431.23  485.78  431.42  485.78  431.57  485.77  431.75  485.78
  432.81  485.68  433.37  485.67  433.91  485.58  434.01  485.58  434.59  485.65
  435.14  485.65  435.27  485.63  435.37  485.63  436.51  485.61   436.6  485.61
  437.47   485.6  437.64   485.6  438.75  485.58   439.7  485.47  440.26  485.56
  440.31  485.56  441.54  485.54  441.58  485.54  443.13  485.52  443.16  485.52
  444.42   485.4  444.43   485.4   444.6   485.4  444.61  485.35  444.74   485.3
  445.24   485.5  445.27   485.5   445.5   485.5  445.78  485.41  445.85  485.41
  446.31  485.41   446.4  485.41  446.63   485.5   446.9   485.5   447.3   485.5
  447.45   485.5  447.65   485.5  447.88   485.5  447.98   485.5  448.14   485.5
  448.52   485.5  448.74   485.5  449.09   485.5  449.37   485.5  449.68   485.5
     450   485.5  450.15   485.5  450.27   485.5  450.42  485.45  450.83  485.45
  451.07   485.5  451.18  485.46   451.6  485.34   451.7  485.34  451.88  485.33
  452.15   485.4  452.41   485.4  452.47   485.4  452.55   485.4  452.61  485.42
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BR D #Mann= 3
       0     .06  277.55    .035  638.28     .06
BR D Banks=277.55,638.28
BC Design=,, 0 ,, 0 ,,,,,,
BC Use User HTab Curves=0
BC User HTab FreeFlow(D)= 0

Type RM Length L Ch R = 1 ,229116.1,89.63,66.9,48.32
BEGIN DESCRIPTION:
Downstream of 4th Street.
Ineffective flow in LOB.
Effective flow limit in ROB set at West Fork Levee Loop.
END DESCRIPTION:
XS GIS Cut Line= 2
 2334197.6894666  6962643.938063 2333419.2410735 6962505.5378662
#Sta/Elev= 30
       0  530.75   51.59  530.89   85.78  529.96  157.85  530.49  206.42  529.63
  224.07  528.41  232.65  525.45  239.75  521.54  285.57  520.79  299.39  513.95
  322.56  504.11  336.51  504.16  348.71  501.79  354.81     498  385.71   486.8
  484.26  485.11   555.9  488.69   585.6     498  588.27  500.92  596.01  503.78
  611.91  502.42  639.07  514.71  661.27  516.31     678  516.56   690.3  514.34
  733.68     522   740.3  525.25  754.04     530  759.91  533.89  790.66  533.61
#Mann= 3 ,-1,0
       0     .06       0  285.57    .035       0  639.07     .06       0
#XS Ineff= 2 , 0
       0  217.28     540  759.91       0     540
Permanent Ineff=
       F       T
Bank Sta=285.57,639.07
XS Rating Curve= 0 ,0
Exp/Cntr=0.5,0.3

Type RM Length L Ch R = 1 ,229049.2,111.47,106.98,103.16
BEGIN DESCRIPTION:
Upstream of 4th Street Dam.
Ineffective flow in LOB.
Effective flow limit in ROB set at West Fork Levee Loop..
END DESCRIPTION:
XS GIS Cut Line= 2
 2334443.1380432  6962555.6258172333417.075304126962468.46982463
#Sta/Elev= 30
       0  529.34  103.69  527.15  112.37     526  127.53  527.11  151.62  525.88
  248.67  527.98     310   525.4  317.07  525.01  323.77  522.21   344.9  521.24
  439.54  520.21  526.11   521.3  573.48   499.3  590.37  501.14  595.77     498
  638.74  486.97  727.84  485.84  778.06  486.48  795.07     492  799.75  492.43
  819.03     498  819.66  500.05  839.53  500.59  870.26  514.34  897.44  516.69
  921.62  516.69  932.19  514.76  972.52   521.5 1006.11  532.93 1029.76  533.15
#Mann= 4 ,-1,0
       0      .1       0     310     .06       0  526.11    .035       0
  870.26     .06       0
#XS Ineff= 1 ,-1
       0   377.4     540
Permanent Ineff=
       F
Bank Sta=526.11,870.26
XS Rating Curve= 0 ,0
Exp/Cntr=0.3,0.1

Type RM Length L Ch R = 5 ,229009.4,,,
BEGIN DESCRIPTION:
4th Street Dam
Constructed by TRWD.  Data from TRWD plans.  Top of dam road surface elevation 500.5
-------------------------------
CDC FW121296-02
-------------------------------
END DESCRIPTION:
Node Name=4th Street Dam
IW Pilot Flow=0
#Inline Weir SE= 2
     400   500.5    1000   500.5
IW Dist,WD,Coef,Skew,MaxSub,Min_El,Is_Ogee,SpillHt,DesHd
31.8,16,3,0,0.95,, 0 ,,,1.5,3,
Inline Weir Flap Gates= 0
IW Outlet Rating Curve= 0 ,False,,

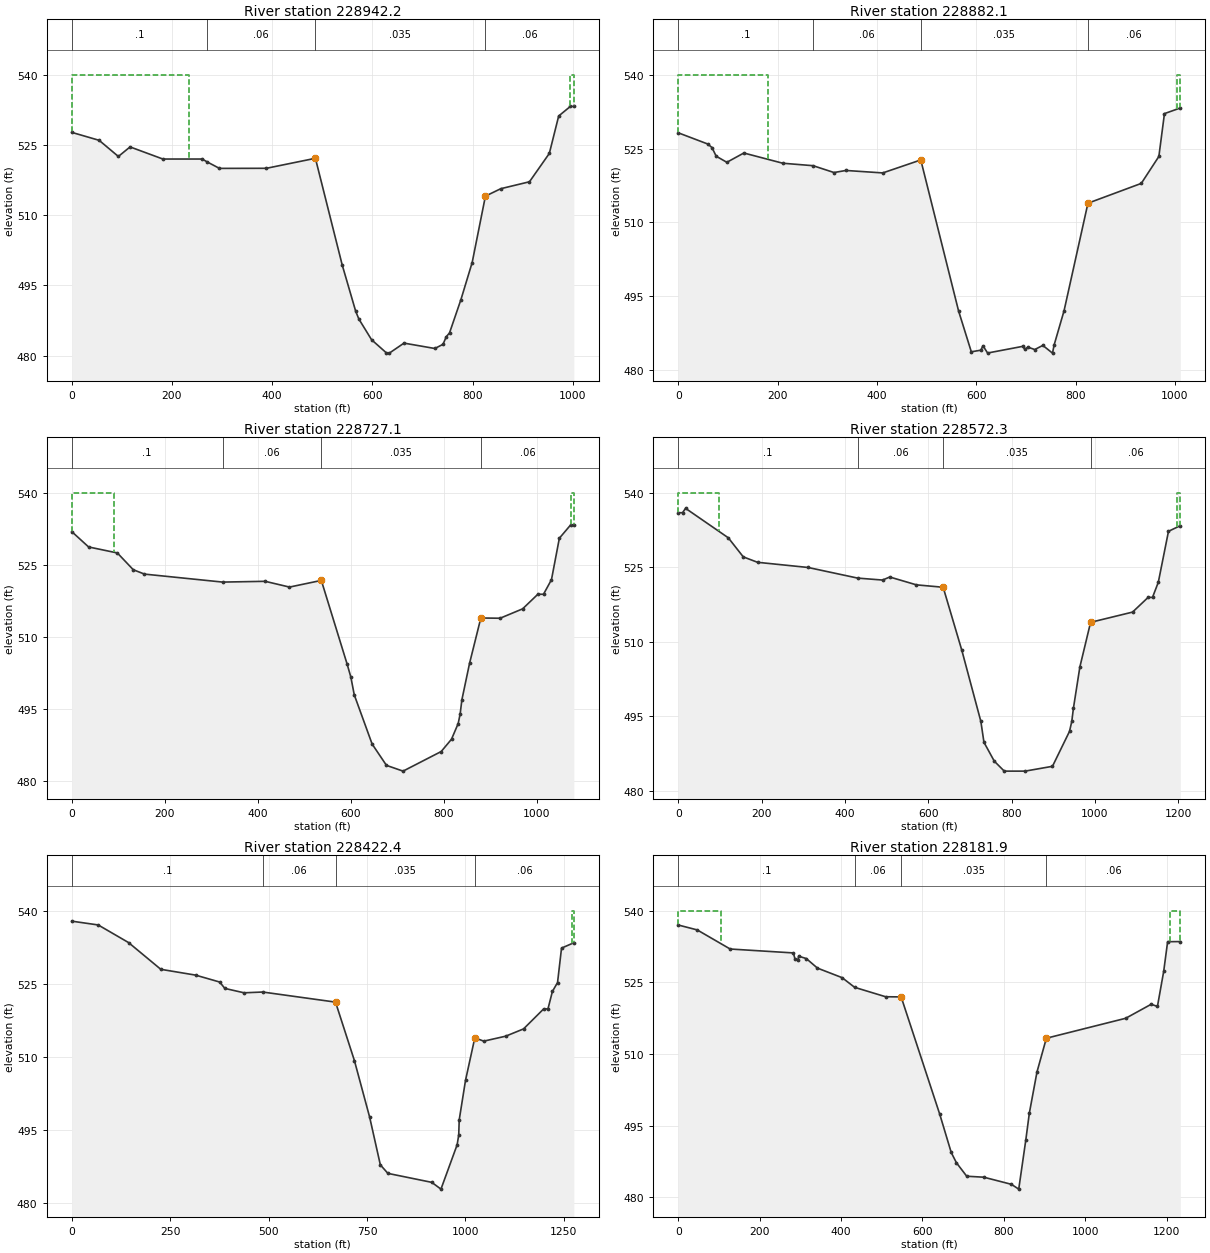
Type RM Length L Ch R = 1 ,228942.2,60.01,60.11,60.05
BEGIN DESCRIPTION:
Downstream of 4th Street Dam.
Ineffective flow in LOB.
Effective flow limit in ROB set at West Fork Levee Loop.
END DESCRIPTION:
XS GIS Cut Line= 2
 2334408.3579598 6962433.3273882 2333408.4067405 6962366.9662885
#Sta/Elev= 30
       0   527.7   54.62     526   93.02  522.55  116.37  524.59  181.85     522
  260.35     522  269.78  521.41  294.82     520  388.51  520.02  486.31  522.16
  539.75  499.37  566.74  489.45  573.15  487.78  598.44  483.37  627.59   480.6
  633.86  480.51  663.13  482.65  724.75   481.5  741.05   482.4  747.44     484
  754.02  484.84  776.79  491.96  799.21  499.88  825.66  514.07  856.35  515.66
  913.58  517.14  953.21   523.2  971.88   531.2  995.26  533.25 1002.15  533.24
#Mann= 4 ,-1,0
       0      .1       0  269.78     .06       0  486.31    .035       0
  825.66     .06       0
#XS Ineff= 2 , 0
       0  234.47     540  995.26       0     540
Permanent Ineff=
       F       T
Bank Sta=486.31,825.66
XS Rating Curve= 0 ,0
Exp/Cntr=0.3,0.1

Type RM Length L Ch R = 1 ,228882.1,155.41,154.97,154.47
BEGIN DESCRIPTION:
Ineffective flow in LOB.
Effective flow limit in ROB set at West Fork Levee Loop.
END DESCRIPTION:
XS GIS Cut Line= 2
  2334412.331093 6962373.4590582 2333403.6808018 6962306.5206822
#Sta/Elev= 30
       0  528.21   59.19  525.94   67.85  525.22   76.43  523.45   97.87  522.21
  132.09   524.1   210.5  522.02  271.52  521.52   313.6  520.13  337.65  520.55
  411.78  520.05  488.33  522.69  564.37     492  590.06  483.67  609.23     484
  613.55   484.9  622.86  483.42  693.16  484.77  697.92  484.18  703.93  484.62
  717.82  484.13  734.05  484.97  753.54   483.4  756.86  485.08  776.76     492
   824.9  513.89  932.29  517.92   967.7   523.4  978.94  532.11 1010.87  533.26
#Mann= 4 ,-1,0
       0      .1       0  271.52     .06       0  488.33    .035       0
   824.9     .06       0
#XS Ineff= 2 , 0
       0  181.22     540 1004.17       0     540
Permanent Ineff=
       F       T
Bank Sta=488.33,824.9
XS Rating Curve= 0 ,0
Exp/Cntr=0.3,0.1

Type RM Length L Ch R = 1 ,228727.1,137.32,154.83,168.76
BEGIN DESCRIPTION:
Ineffective flow in LOB.
Effective flow limit in ROB set at West Fork Levee Loop.
END DESCRIPTION:
XS GIS Cut Line= 2
 2334470.8247459  6962220.370921 2333393.3676119 6962151.6806225
#Sta/Elev= 30
       0  531.93   36.17  528.74   98.01  527.49  132.24     524  156.39  523.09
  324.43  521.43  415.85  521.59  468.17  520.39  536.63  521.78  591.91  504.43
  600.11  501.67  607.44  497.98  645.85  487.74  676.69   483.3   712.4   482.1
  794.41  486.18  816.56  488.74  830.93     492  835.18     494   838.9  496.95
  855.34  504.51  879.62  513.96  921.07  513.91  969.45  515.86 1002.28   518.9
  1014.4   518.9 1031.53  521.93 1048.51  530.56 1072.75  533.32 1079.64  533.32
#Mann= 4 ,-1,0
       0      .1       0  324.43     .06       0  536.63    .035       0
  879.62     .06       0
#XS Ineff= 2 , 0
       0   90.67     540 1072.75       0     540
Permanent Ineff=
       F       T
Bank Sta=536.63,879.62
XS Rating Curve= 0 ,0
Exp/Cntr=0.3,0.1

Type RM Length L Ch R = 1 ,228572.3,132.91,149.87,163.53
BEGIN DESCRIPTION:
Ineffective flow in LOB.
Effective flow limit in ROB set at West Fork Levee Loop.
END DESCRIPTION:
XS GIS Cut Line= 2
 2334576.6286047 6962128.3562251 2333382.2208523 6961970.0287843
#Sta/Elev= 30
       0     536    10.3     536    17.6  536.88  120.14  530.95  156.09  527.11
  190.34  526.02  311.52  524.98  430.62  522.84  490.32  522.45   507.6  523.06
  571.69  521.48  635.75     521  680.62  508.29  726.23     494  733.64   489.8
   758.5     486  782.38     484  832.45     484  898.07  484.97  938.98     492
   944.4     494  948.37  496.66  963.81  504.96  989.55  513.94 1090.26     516
  1127.6  518.96 1138.13  518.96 1152.06     522 1176.48  532.26 1204.86  533.39
#Mann= 4 ,-1,0
       0      .1       0  430.62     .06       0  635.75    .035       0
  989.55     .06       0
#XS Ineff= 2 , 0
       0   96.83     540 1197.24       0     540
Permanent Ineff=
       F       T
Bank Sta=635.75,989.55
XS Rating Curve= 0 ,0
Exp/Cntr=0.3,0.1

Type RM Length L Ch R = 1 ,228422.4,232.27,240.49,248.69
BEGIN DESCRIPTION:
Effective flow limit in ROB set at West Fork Levee Loop.
END DESCRIPTION:
XS GIS Cut Line= 2
 2334625.3843995 6962042.5235575 2333375.2118657 6961790.2314119
#Sta/Elev= 30
       0  537.88   67.16   537.1  144.17  533.49  226.17     528  314.47  526.81
  375.72  525.39  388.84  524.08  437.69  523.18  485.15  523.34  669.99  521.27
  717.97  509.27   756.6  497.69  783.84  487.88  803.06  486.13   914.5  484.29
  937.83   482.9  978.92     492  982.95     494  984.19   497.1 1000.19  505.22
 1023.84  513.95 1046.51  513.26 1102.27  514.28 1147.54  515.77 1198.63  519.87
 1209.66  519.88 1220.88  523.45 1233.97  525.29 1244.11  532.35 1275.38  533.45
#Mann= 4 ,-1,0
       0      .1       0  485.15     .06       0  669.99    .035       0
 1023.84     .06       0
#XS Ineff= 2 , 0
       0                 1269.57       0     540
Permanent Ineff=
       F       T
Bank Sta=669.99,1023.84
XS Rating Curve= 0 ,0
Exp/Cntr=0.3,0.1

Type RM Length L Ch R = 1 ,228181.9,318.68,315.89,310.63
BEGIN DESCRIPTION:
Upstream of Sump 30 outfall.
Ineffective flow in LOB due to Trinity Railway Express bridge.
Effective flow limit in ROB set at West Fork Levee Loop.
END DESCRIPTION:
XS GIS Cut Line= 2
 2334571.6151297 6961814.8302766 2333371.6605732 6961527.2691842
#Sta/Elev= 30
       0  537.03   46.67     536  127.66     532  283.04  531.18  287.02  529.86
  293.86  529.68     296   530.5  314.69     530  342.18     528  402.75     526
   433.6  523.97  509.79     522  547.84  521.97  642.74  497.38  670.89  489.38
  683.65  487.23  709.02   484.4  750.86   484.2  818.73  482.71  836.84   481.7
  854.23     492   862.9  497.62   881.7  506.25  904.72  513.31  1099.7  517.49
 1162.22  520.42 1177.73  519.98 1193.05  527.29 1202.74  533.53 1233.93  533.56
#Mann= 4 ,-1,0
       0      .1       0   433.6     .06       0  547.84    .035       0
  904.72     .06       0
#XS Ineff= 2 , 0
       0     104     540 1208.34       0     540
Permanent Ineff=
       F       T
Bank Sta=547.84,904.72
XS Rating Curve= 0 ,0
Exp/Cntr=0.3,0.1