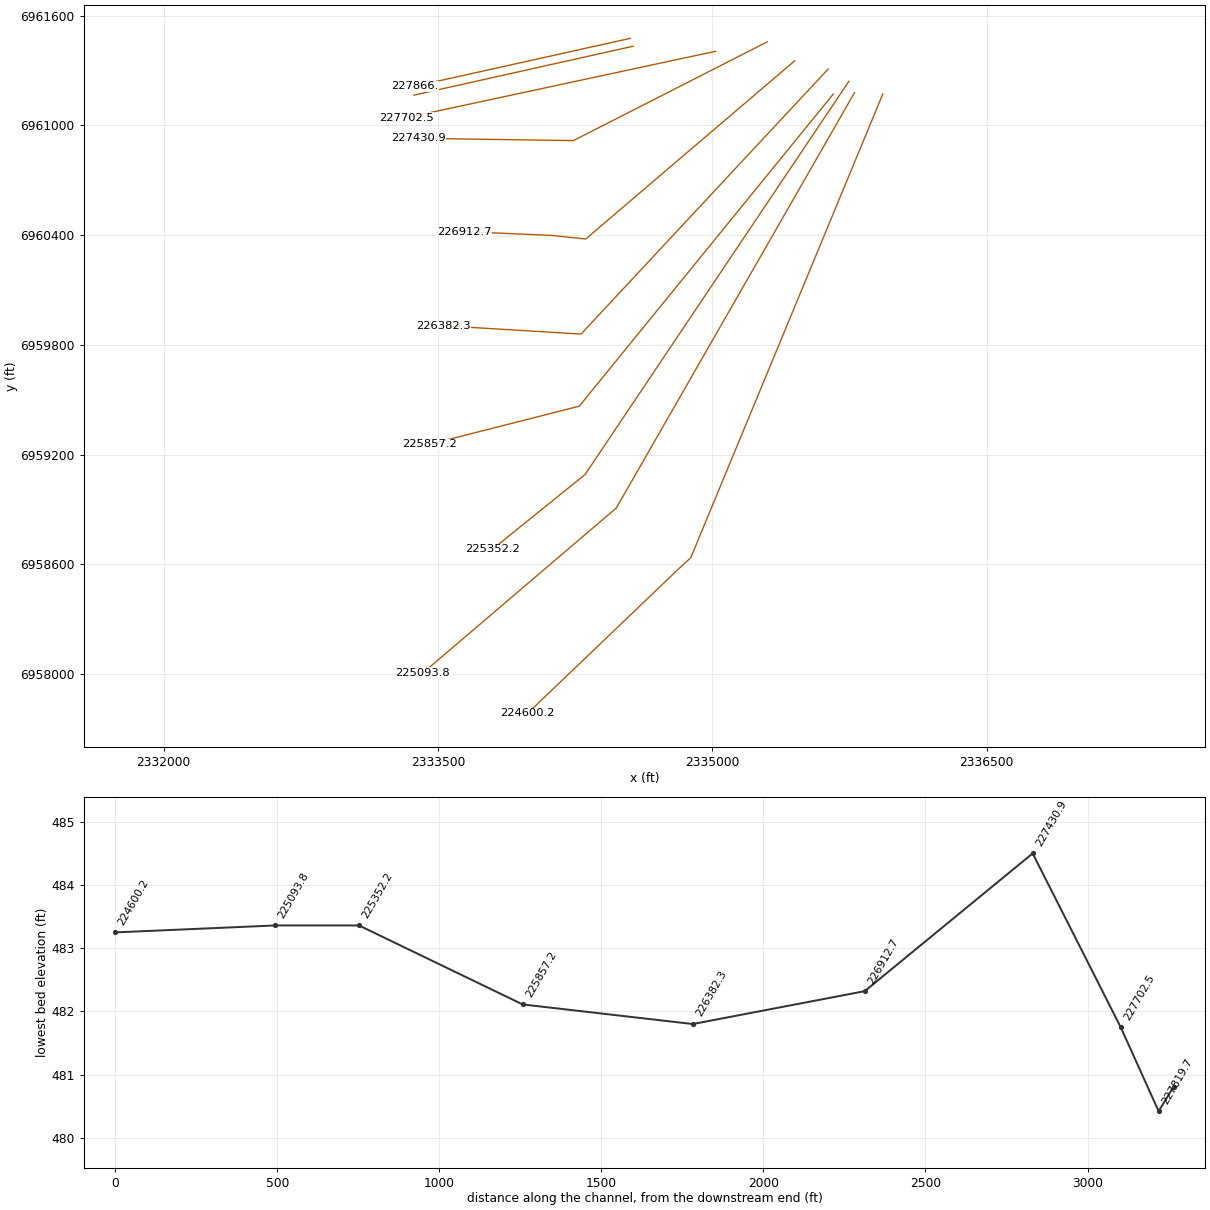
HEC-RAS study CDC_Consolidated_Model.prj: Upper Trinity CDC Consolidated Model

--- CDC_Consolidated_Model.g11 (geometry) --- (continued)

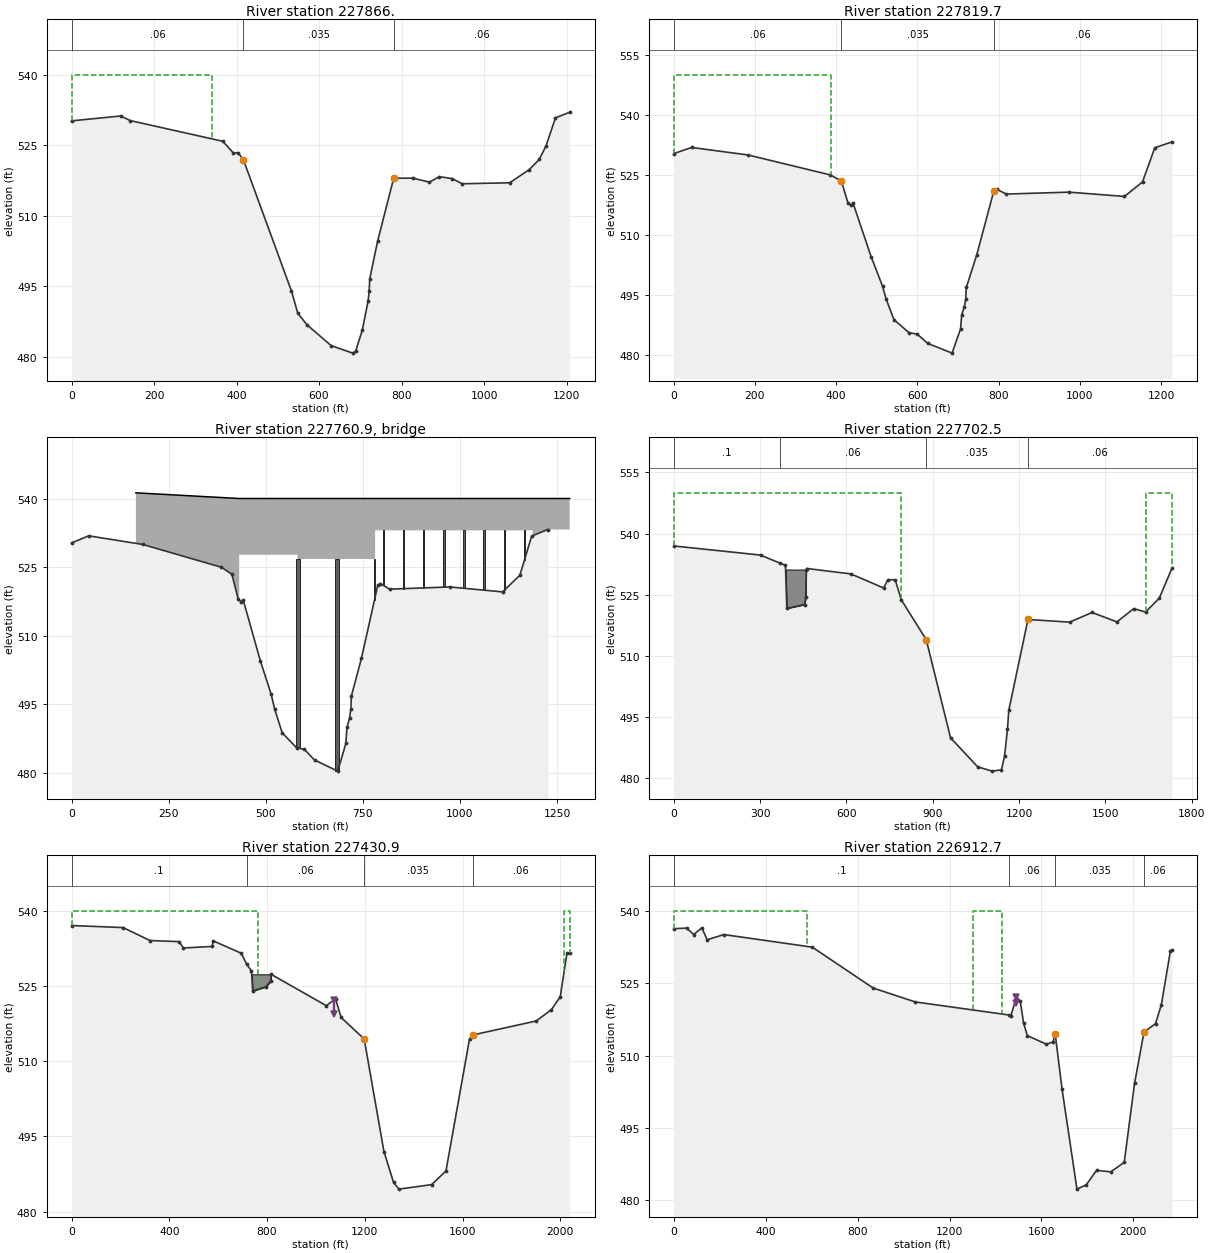
Type RM Length L Ch R = 1 ,227866. ,45.81,46.38,46.44
BEGIN DESCRIPTION:
Downstream of Sump 30 outfall.
Ineffective flow in LOB due to Trinity Railway Express bridge.
Effective flow limit in ROB set at West Fork Levee Loop.
END DESCRIPTION:
XS GIS Cut Line= 2
 2334551.8954355  6961476.329644  2333372.918058 6961214.4605205
#Sta/Elev= 30
       0  530.21  119.55  531.25  142.02  530.27  366.51  525.87  392.19  523.38
  403.67  523.43  416.45  521.97  533.19     494  548.36  489.31  570.61  486.84
  629.36   482.4   681.8  480.81  688.42  481.16  704.82  485.69  719.17     492
  721.46     494  722.89  496.63  742.13  504.69  780.93  518.01  827.89  518.02
  867.63  517.17  891.47  518.35  922.53  517.93  947.29  516.83 1062.11  517.04
 1109.34  519.82 1133.86     522 1150.27  524.89 1173.16  530.85 1207.71  532.04
#Mann= 3 ,-1,0
       0     .06       0  416.45    .035       0  780.93     .06       0
#XS Ineff= 2 , 0
       0  340.28     540               0
Permanent Ineff=
       F       F
Bank Sta=416.45,780.93
XS Rating Curve= 0 ,0
Exp/Cntr=0.3,0.1

Type RM Length L Ch R = 1 ,227819.7,118.68,117.11,114.58
BEGIN DESCRIPTION:
Upstream of the Trinity Railway Express bridge.
Ineffective flow in LOB due to Trinity Railway Express bridge.
Effective flow limit in ROB set at West Fork Levee Loop.
END DESCRIPTION:
XS GIS Cut Line= 2
 2334566.1085133 6961432.9930899  2333368.851456 6961165.8064912
#Sta/Elev= 30
       0   530.3   44.17  531.84  183.02  529.96  385.92  524.97  412.87  523.44
  428.97     518  436.97  517.39  441.96  517.83   486.2  504.51  514.18  497.18
   522.9     494  542.26   488.8  579.76   485.5  599.24   485.2  625.81  482.84
  685.52  480.42   706.4  486.49  709.23     490  715.77     492  719.23     494
  720.57  496.84   746.4  505.04  788.45  521.03  795.24   521.4     819  520.19
  973.81  520.67 1109.97  519.59 1154.46  523.23 1184.77  531.78 1226.71  533.22
#Mann= 3 ,-1,0
       0     .06       0  412.87    .035       0  788.45     .06       0
#XS Ineff= 2 , 0
       0  386.59     550               0
Permanent Ineff=
       F       F
Bank Sta=412.87,788.45
XS Rating Curve= 0 ,0
Exp/Cntr=0.5,0.3

Type RM Length L Ch R = 3 ,227760.9,,,
BEGIN DESCRIPTION:
Trinity Railway Express
Bridge project includes construction of parallel bridge.  Both bridges modeled as single structure.  Timber trestle span section replaced with 42-inch dia. columns, bridge low chords were resurveyed (January 2017 analysis).
----------------------
CDC FW082515-01
----------------------
END DESCRIPTION:
Node Name=TRE Railroad
Bridge Culvert--1,0,-1,-1, 0
Deck Dist Width WeirC Skew NumUp NumDn MinLoCord MaxHiCord MaxSubmerge Is_Ogee
49.8,53,2.6,0, 12, 13, , , 0.95, 0, 0,0,,
   165.6   431.6   431.6   581.6   581.6   781.6   781.6   811.6   811.6  1187.6
  1187.6 1282.78
  541.24     540     540     540     540     540     540     540     540     540
     540     540
     450     450  527.71  527.71  526.78  526.78  533.03  533.03  533.03  533.03
     450     450
       0     614     880     880    1030    1030    1230    1230    1260    1260
    1636    1636 1731.18
     542  541.24     540     540     540     540     540     540     540     540
     540     540     540
     450     450     450  527.71  527.71  526.78  526.78  533.03  533.03  533.03
  533.03     450     450
Pier Skew, UpSta & Num, DnSta & Num=  ,583.1, 2 ,1031.5, 2 , 0 , 0 , 0 ,,
      10       3
     450     531
      10       3
     450     531
Pier Skew, UpSta & Num, DnSta & Num=  ,683.1, 2 ,1131.5, 2 , 0 , 0 , 0 ,,
      10       3
     450     531
      10       3
     450     531
Pier Skew, UpSta & Num, DnSta & Num=  ,780.1, 2 ,1228.5, 2 , 0 , 0 , 0 ,,
       4       4
     450     531
       4       3
     450     531
Pier Skew, UpSta & Num, DnSta & Num=  ,803.1, 2 ,1251.5, 2 , 0 , 0 , 0 ,,
     3.5     3.5
  480.42   536.8
     3.5     3.5
  480.42   536.8
Pier Skew, UpSta & Num, DnSta & Num=  ,854.93, 2 ,1303.33, 2 , 0 , 0 , 0 ,,
     3.5     3.5
  480.42   536.8
     3.5     3.5
  480.42   536.8
Pier Skew, UpSta & Num, DnSta & Num=  ,906.77, 2 ,1355.17, 2 , 0 , 0 , 0 ,,
     3.5     3.5
  480.42   536.8
     3.5     3.5
  480.42   536.8
Pier Skew, UpSta & Num, DnSta & Num=  ,958.6, 2 ,1407, 2 , 0 , 0 , 0 ,,
     3.5     3.5
  480.42   536.8
     3.5     3.5
  480.42   536.8
Pier Skew, UpSta & Num, DnSta & Num=  ,1010.43, 2 ,1458.83, 2 , 0 , 0 , 0 ,,
     3.5     3.5
  480.42   536.8
     3.5     3.5
  480.42   536.8
Pier Skew, UpSta & Num, DnSta & Num=  ,1062.27, 2 ,1510.67, 2 , 0 , 0 , 0 ,,
     3.5     3.5
  480.42   536.8
     3.5     3.5
  480.42   536.8
Pier Skew, UpSta & Num, DnSta & Num=  ,1114.1, 2 ,1562.5, 2 , 0 , 0 , 0 ,,
     3.5     3.5
  480.42   536.8
     3.5     3.5
  480.42   536.8
Pier Skew, UpSta & Num, DnSta & Num=  ,1165.93, 2 ,1614.33, 2 , 0 , 0 , 0 ,,
     3.5     3.5
  480.42   536.8
     3.5     3.5
  480.42   536.8
BR Coef=-1 , 0 , 0 ,, 0 ,,,0.8,-1,,0,
WSPro=,,,, 1 ,,,, 0 ,,,, 0 ,,,,-1 ,-1 ,-1 , 0 , 0 , 0 , 0 , 0
BR U #Sta/Elev= 310
   165.6  541.24  170.15  541.17  179.45  541.05  187.53  540.96  196.16  540.85
  204.37  540.78  212.66  540.67  220.97  540.63  229.02  540.53  237.52  540.52
  242.82  540.52  251.42  540.52  259.79  540.54  269.96  540.54  278.15  540.54
  287.46  540.54  295.07  540.49  297.64  540.47  305.11  540.41  315.62  540.31
  322.97  540.24  333.05  540.15   338.7  540.11  348.48  540.02  354.02  539.98
   363.7  539.89  369.11  539.82  371.25  539.79  382.15  539.69  384.29  539.67
  386.41  539.56  387.34   539.5  388.24  539.43   390.2  539.24  395.08  538.51
  396.61  538.35  401.37   538.4  402.81  538.22  404.32  538.04  405.76     538
  406.82  537.97  411.74  537.89  417.32  538.18  421.66  538.55  427.77  538.44
   431.6  538.77  436.96  518.61  438.26  514.58  452.29  512.49  454.86  512.06
  457.26  511.37  468.54  508.19  483.98  503.51  498.59  499.18  502.23  498.09
  509.49  495.87  511.69   495.2  515.82  493.95  526.31  490.76  529.18  489.89
  530.66  489.44     538  488.49  542.21  487.94  545.85  487.47     551  486.79
   552.7  486.71   552.8  486.71  553.22  486.69  553.69  486.67  559.44  486.41
  559.98  486.33  560.68   486.3  561.52  486.26  563.85  486.14  564.66   486.1
  567.63  485.96  568.84   485.9  568.86  485.88  581.63  485.16  582.31  485.12
  582.68   485.1  583.86  485.04  584.32  485.02  584.81  484.99  585.33  484.96
  586.45  484.87  587.74   484.8  588.49  484.76  589.24  484.72     591  484.63
  592.03  484.57  593.16  484.51  595.72  484.38  604.66  483.87   607.3  483.73
  608.82  483.65  613.96  483.55  616.07  483.45   618.4  483.44  620.97  483.32
  621.34   483.3  621.41  483.29  621.92  483.24  622.41   483.1  622.49   483.1
   623.4  482.93  623.55  482.91  623.98  482.87  624.41  482.75  624.82  482.72
  625.18  482.69  625.59  482.66  625.96  482.63  626.33   482.6  626.68  482.55
  627.02  482.52  627.37  482.49  627.75  482.47  628.08  482.44   628.4  482.41
  628.89  482.38  629.18  482.36  629.45  482.34  629.69  482.28  629.98  482.25
  630.24  482.23  630.83  482.19  631.33  482.15  631.97   482.1  632.39  482.11
   632.7  482.09  632.91  482.07   633.1  482.05  633.85     482  634.18  481.94
  634.92  481.82  635.37  481.81  636.23  481.75  636.47  481.73  636.87   481.7
  637.34  481.66  638.32  481.59  638.41  481.59  638.49  481.58  638.57  481.57
  638.65  481.57  639.63   481.5  639.68  481.49  639.74  481.49  640.83  481.41
  641.93  481.34  641.95  481.34  641.96  481.34  641.97  481.33  641.98  481.33
  642.49  481.23   642.5  481.21   642.5   481.2  642.53   481.2  644.02  480.87
   644.1  480.86  644.14  480.86  644.87   480.8  645.91  480.71  646.41  480.67
  647.32  480.67  648.12   480.6  648.91  480.53   649.1  480.51  649.46  480.47
  651.06  480.25  651.84  480.18  652.08  480.15  652.31  480.08  653.03  480.06
  653.33  480.08   653.6  480.09  654.25  480.07  654.52  480.03  657.25  479.69
   657.5  479.67  658.17  479.59  658.37  479.53  658.74  479.49  659.06  479.43
  659.37  479.37  659.66  479.34  660.16  479.27  660.28  479.21  660.61  479.18
  661.12  479.12   661.3  479.06  661.39  479.06  661.62  478.97  661.83  478.95
  661.96  478.93  662.01  478.93  662.13  478.92  662.18  478.92  662.23  478.91
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BR U #Mann= 3
   165.6     .06  454.86    .035  781.84     .06
BR U Banks=454.86,781.84
BR D #Sta/Elev= 405
       0  536.97    6.58  536.87    8.21  536.83    8.48  536.83   20.04  536.43
   28.84  536.08   31.38     536   33.55  535.98   49.34  535.62  104.11  535.68
   118.8  535.82  121.92  535.82  128.97  535.77  153.64  535.46  158.33  535.42
  162.06  535.41  165.81  535.38  174.19  535.06   181.4  534.95  184.04  534.93
  188.55  534.95  195.32  534.72  197.07  534.72  198.82   534.7     210  534.52
  215.42  534.43  216.22  534.41  220.59  534.38  222.83  534.34  224.49  534.33
  226.55  534.33  229.61  534.31  233.32  534.37   237.3  534.35   243.4  534.49
  249.12  534.44  254.75  534.59  259.92   534.5   285.1  534.79  290.07  534.69
  302.15  534.73  309.94   534.5  336.07  534.01   336.2     534   336.3     534
  368.82  532.75  370.47   532.7  377.75  532.44  385.93  532.33   386.2  532.31
   387.1  532.29  387.21  532.28  387.96     532  388.28     532  388.36  532.22
  388.45  532.27  389.24  530.48  389.45     530  392.51  522.74  392.82     522
  392.96  521.66  406.19  522.47  414.39     522  434.87     522  439.59  522.14
   448.8  522.47  455.19  522.61  459.11  524.57  459.37     526  459.43   526.3
  459.74     528  460.06  529.76   460.1     530   460.5  531.04  460.56  531.19
  462.83  531.44  471.01  531.38  477.73  531.51  479.15  531.53   493.9  531.43
  494.65  531.43  504.32  531.29  504.73  531.29  520.79  531.16  521.23  531.16
   521.4  531.15  521.99  531.15  523.78  531.12  537.57     531  542.62  530.92
  567.58  530.68  575.01  530.54  585.38  530.47  591.64  530.34     610   530.2
  615.57  530.12  618.55  541.17  627.85  541.05  635.93  540.96  644.56  540.85
  652.77  540.78  661.06  540.67  669.37  540.63  677.42  540.53  685.92  540.52
  691.22  540.52  699.82  540.52  708.19  540.54  718.36  540.54  726.55  540.54
  735.86  540.54  743.47  540.49  746.04  540.47  753.51  540.41  764.02  540.31
  771.37  540.24  781.45  540.15   787.1  540.11  796.88  540.02  802.42  539.98
   812.1  539.89  817.51  539.82  819.65  539.79  830.55  539.69  832.69  539.67
  834.81  539.56  835.74   539.5  836.64  539.43   838.6  539.24  843.48  538.51
  845.01  538.35  849.77   538.4  851.21  538.22  852.72  538.04  854.16     538
  855.22  537.97  860.14  537.89  865.72  538.18  870.06  538.55  876.17  538.44
     880  538.77  885.36  518.61  886.66  514.58  900.69  512.49  903.26  512.06
  905.66  511.37  916.94  508.19  932.38  503.51  946.99  499.18  950.63  498.09
  957.89  495.87  960.09   495.2  964.22  493.95  974.71  490.76  977.58  489.89
  979.06  489.44   986.4  488.49  990.61  487.94  994.25  487.47   999.4  486.79
  1001.1  486.71  1001.2  486.71 1001.62  486.69 1002.09  486.67 1007.84  486.41
 1008.38  486.33 1009.08   486.3 1009.92  486.26 1012.25  486.14 1013.06   486.1
 1016.03  485.96 1017.24   485.9 1017.26  485.88 1030.03  485.16 1030.71  485.12
 1031.08   485.1 1032.26  485.04 1032.72  485.02 1033.21  484.99 1033.73  484.96
 1034.85  484.87 1036.14   484.8 1036.89  484.76 1037.64  484.72  1039.4  484.63
 1040.43  484.57 1041.56  484.51 1044.12  484.38 1053.06  483.87  1055.7  483.73
 1057.22  483.65 1062.36  483.55 1064.47  483.45  1066.8  483.44 1069.37  483.32
 1069.74   483.3 1069.81  483.29 1070.32  483.24 1070.81   483.1 1070.89   483.1
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BR D #Mann= 4
       0      .1  370.47     .06  903.26    .035 1230.24     .06
BR D Banks=903.26,1230.24
BC Design=,, 0 ,, 0 ,,29,811.6,1259.5,13,1
BC Use User HTab Curves=0
BC User HTab FreeFlow(D)= 0

Type RM Length L Ch R = 1 ,227702.5,316.58,271.6,195.61
BEGIN DESCRIPTION:
Downstream of the Trinity Railway Express bridge.
Ineffective flow in LOB due to Trinity Railway Express bridge.
Effective flow limit in ROB due to Trinity Railway Express bridge at West Fork Levee Loop.
END DESCRIPTION:
XS GIS Cut Line= 2
 2335018.5882112 6961405.7378211 2333326.0136178 6961042.1918519
#Sta/Elev= 30
       0  536.97  302.15  534.73  370.47   532.7  388.45  532.27  392.96  521.66
  455.19  522.61  459.11  524.57  460.56  531.19  462.83  531.44  615.57  530.12
  729.78  526.66  744.16  528.69  769.74  528.67   790.7  523.78  877.53     514
  962.05  489.94 1056.29   482.8 1106.96  481.75 1139.05  482.08 1149.81  485.46
 1159.86     492 1164.42  496.65 1231.17  518.94 1376.26  518.29 1453.73  520.66
 1540.26  518.35  1598.7   521.6 1639.83  520.77 1687.48  524.16 1731.18  531.45
#Mann= 4 ,-1,0
       0      .1       0  370.47     .06       0  877.53    .035       0
 1231.17     .06       0
#XS Ineff= 2 , 0
       0  791.03     550 1640.68       0     550
Permanent Ineff=
       F       F
#Block Obstruct= 1 ,-1
     350  460.56  531.19
Bank Sta=877.53,1231.17
XS Rating Curve= 0 ,0
Exp/Cntr=0.5,0.3

Type RM Length L Ch R = 1 ,227430.9,542.78,518.24,510.5
BEGIN DESCRIPTION:
Flow confined up to 50-year flood at non-federal levee in LOB.
Ineffective flow in LOB due to Trinity Railway Express bridge.
Effective flow limit in ROB due to Trinity Railway Express bridge at West Fork Levee Loop.
END DESCRIPTION:
XS GIS Cut Line= 3
 2335300.2794426 6961457.1405564 2334240.5619181 6960917.2453158
 2333391.1667544 6960929.6154655
#Sta/Elev= 30
       0  537.07  210.88  536.66  320.76  534.08  440.74  533.85  457.28  532.59
  575.64   532.9  579.22  534.02  694.22  531.55  716.64  529.35  736.29     528
  741.27     524  795.64  524.87  814.84  525.95  816.57  527.34 1042.72  521.08
 1080.21  522.47 1103.12  518.73 1197.65  514.45 1278.45     492 1317.61  485.87
 1339.46   484.5 1473.61   485.4 1532.31  488.12 1628.87  514.47 1641.46  515.24
 1901.53  518.03    1964   520.3    2000  522.86 2027.61  531.57 2038.81  531.59
#Mann= 4 ,-1,0
       0      .1       0  716.64     .06       0 1197.65    .035       0
 1641.46     .06       0
Levee=-1,1075.19,519.5,0,,,,
#XS Ineff= 2 , 0
       0  761.93     540 2015.81       0     540
Permanent Ineff=
       F       T
#Block Obstruct= 1 ,-1
     700  816.57  527.34
Bank Sta=1197.65,1641.46
XS Rating Curve= 0 ,0
Exp/Cntr=0.3,0.1

Type RM Length L Ch R = 1 ,226912.7,379.26,530.38,523.74
BEGIN DESCRIPTION:
Flow confined up to 50-year flood at non-federal levee in LOB.
Ineffective flow in LOB due to structures.
Effective flow limit in ROB set at West Fork Levee Loop.
END DESCRIPTION:
XS GIS Cut Line= 4
 2335450.7030085  6961353.846352 2334307.8239992 6960379.3582913
 2334121.3908669 6960399.0467429 2333643.7652336 6960419.6037664
#Sta/Elev= 30
       0   536.3   55.71  536.42   87.05  535.09   122.4  536.48  145.55     534
  218.27  535.08  603.09  532.47  867.75     524 1050.65  521.12 1459.14  518.41
 1466.16   518.1 1490.93  522.08 1507.93   521.3 1522.19  516.76 1538.75  514.14
 1621.43  512.35 1649.96  512.82 1659.74  514.52  1689.9  502.99 1754.55  482.32
 1794.81   483.2 1839.73   486.2 1902.01  485.91 1960.25  487.87 2005.21  504.25
 2046.13  514.84 2096.36  516.62 2121.58  520.49 2161.28  531.73 2167.47   531.9
#Mann= 4 ,-1,0
       0      .1       0 1459.14     .06       0 1659.74    .035       0
 2046.13     .06       0
Levee=-1,1490.83,521,0,,,,
#XS Ineff= 2 ,-1
 1303.65 1428.89     540       0  578.51     540
Permanent Ineff=
       F       F
Bank Sta=1659.74,2046.13
XS Rating Curve= 0 ,0
Exp/Cntr=0.3,0.1

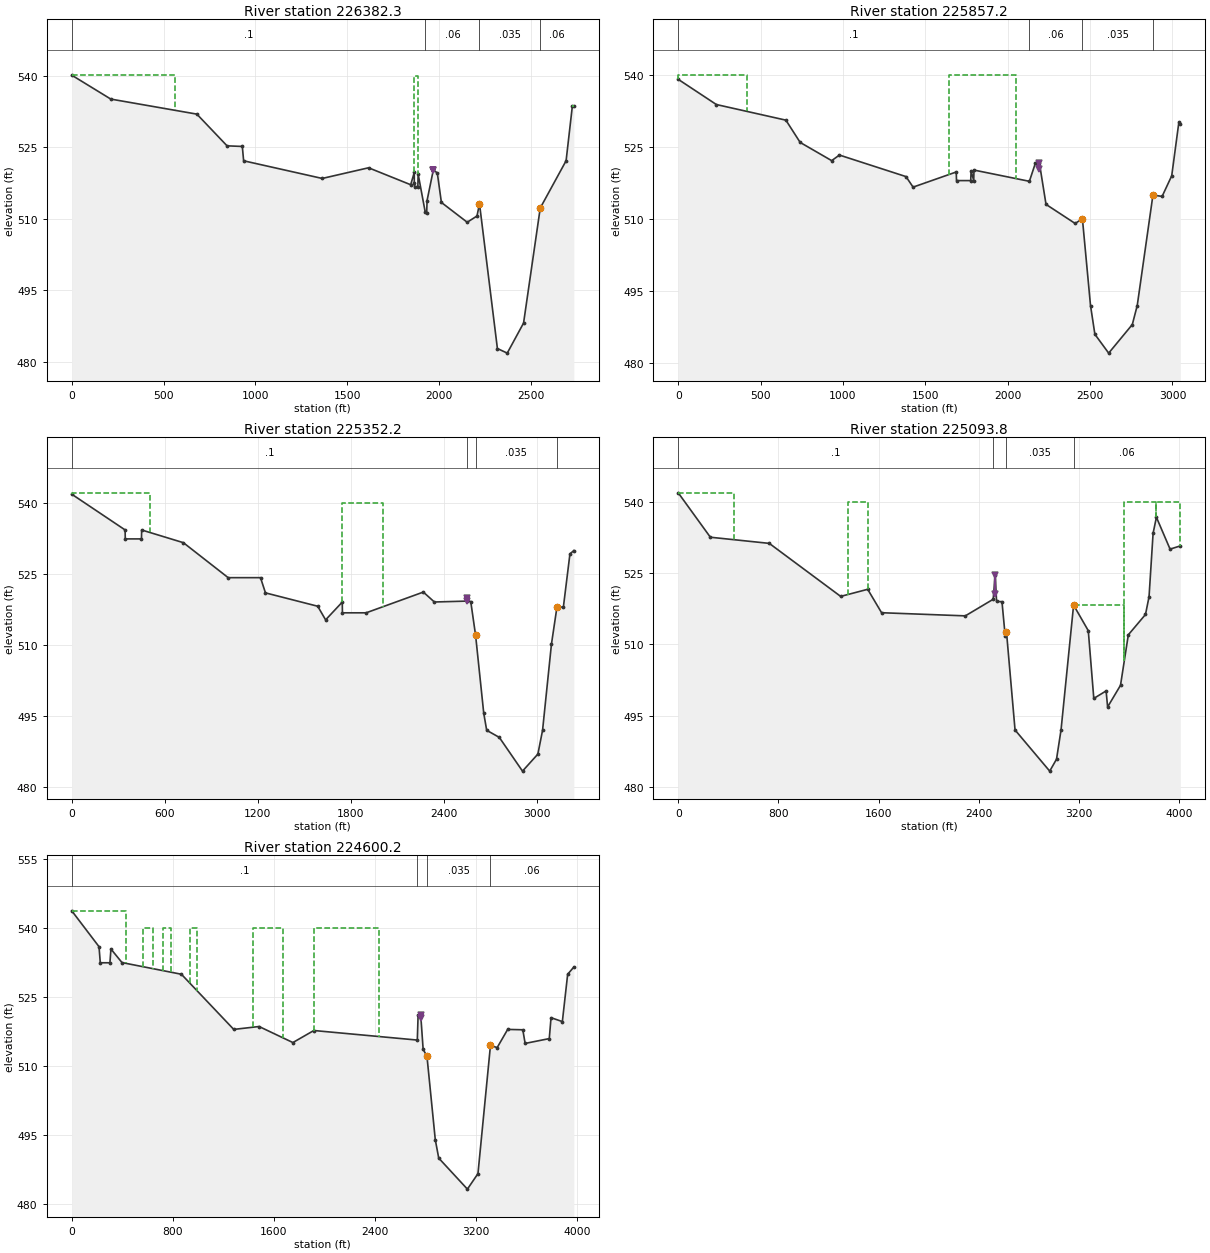
Type RM Length L Ch R = 1 ,226382.3,239.28,525.08,622.21
BEGIN DESCRIPTION:
Flow confined up to 50-year flood at non-federal levee in LOB.
Ineffective flow in LOB due to structures.
Effective flow limit in ROB set at West Fork Levee Loop.
END DESCRIPTION:
XS GIS Cut Line= 3
 2335632.9331601 6961308.2888465 2334282.1645693 6959859.4303528
 2333530.1269856 6959905.1167181
#Sta/Elev= 30
       0  540.18  212.51  535.16  681.28     532   845.7  525.34  928.82  525.21
  935.94   522.2    1364  518.49 1616.41  520.73 1845.72  517.17 1865.34  519.75
  1865.4  517.56 1866.65  516.79 1884.76  516.78 1886.27  519.42 1924.66  511.48
 1932.76  511.16 1934.96  513.85 1968.86  520.25 1990.66  519.66 2012.93  513.45
 2153.51  509.29 2206.86   510.6 2220.44  513.18 2317.94  482.77 2371.57   481.8
 2460.48  488.12  2551.3  512.28 2692.12  522.21 2726.27  533.73 2734.27  533.67
#Mann= 4 ,-1,0
       0      .1       0 1924.66     .06       0 2220.44    .035       0
  2551.3     .06       0
Levee=-1,1968.86,520.25,0,,,,
#XS Ineff= 3 ,-1
 1865.33 1886.56     540       0  562.36 540.255 2726.27 2734.27  533.73
Permanent Ineff=
       F       F       T
Bank Sta=2220.44,2551.3
XS Rating Curve= 0 ,0
Exp/Cntr=0.3,0.1

Type RM Length L Ch R = 1 ,225857.2,198.39,505.08,630.83
BEGIN DESCRIPTION:
Flow confined up to 50-year flood at non-federal levee in LOB.
Ineffective flow in LOB due to structures.
Effective flow limit in ROB set at West Fork Levee Loop.
END DESCRIPTION:
XS GIS Cut Line= 3
 2335661.4097447 6961171.9360164 2334272.4561389 6959465.2077192
 2333451.6294728 6959256.3397627
#Sta/Elev= 30
       0  539.06   231.5  533.82  653.47  530.57  740.06  525.94  931.35  522.15
  978.36  523.31 1382.46  518.83 1425.49  516.64 1687.44  519.79 1688.99     518
 1775.36     518 1777.59     520 1793.65     518 1794.95  520.19  2131.4  517.85
 2168.28  521.67 2191.97   521.7 2232.35  513.05  2409.3  509.08 2453.22  510.07
 2502.45     492 2528.99  486.03 2612.68  482.11 2756.15  488.06 2785.97     492
 2881.32  514.99 2936.94  514.71 2995.27  518.99 3038.64  530.12 3047.47  529.74
#Mann= 4 ,-1,0
       0      .1       0  2131.4     .06       0 2453.22    .035       0
 2881.32     .06       0
Levee=-1,2191.97,520.5,0,,,,
#XS Ineff= 2 ,-1
 1641.17 2052.44     540       0  419.32     540
Permanent Ineff=
       F       F
Bank Sta=2453.22,2881.32
XS Rating Curve= 0 ,0
Exp/Cntr=0.3,0.1

Type RM Length L Ch R = 1 ,225352.2,192.4,258.36,269.36
BEGIN DESCRIPTION:
Flow confined up to 50-year flood at non-federal levee in LOB.
Ineffective flow in LOB due to structures.
Effective flow limit in ROB set at West Fork Levee Loop.
END DESCRIPTION:
XS GIS Cut Line= 3
 2335746.4564195 6961241.5196476  2334304.264021 6959091.6393373
 2333796.9657666 6958682.4374677
#Sta/Elev= 30
       0  541.96  344.16   534.4  345.38   532.5  449.88   532.5  451.09  534.39
  720.46   531.7 1009.41   524.3 1218.19   524.3 1250.16  521.08 1587.44  518.25
  1638.4  515.37 1745.89  519.13 1746.94  516.86 1899.97  516.86 2269.13  521.25
  2340.3  519.15  2551.3  519.34 2575.16  519.25 2606.44  512.09 2659.14  495.58
 2678.07     492 2759.48   490.5 2909.17  483.36 3008.49  486.97 3038.67     492
 3096.12  510.26 3132.02  518.17 3172.88  518.03 3215.39  529.33 3240.57  530.04
#Mann= 4 ,-1,0
       0      .1       0  2551.3     .06       0 2606.44    .035       0
 3132.02     .06       0
Levee=-1,2549.91,520,0,,,,
#XS Ineff= 2 ,-1
 1745.89 2007.41     540       0   503.8 542.251
Permanent Ineff=
       F       F
Bank Sta=2606.44,3132.02
XS Rating Curve= 0 ,0
Exp/Cntr=0.3,0.1

Type RM Length L Ch R = 1 ,225093.8,391.77,493.58,522.37
BEGIN DESCRIPTION:
Flow confined up to 50-year flood at non-federal levee in LOB.
Ineffective flow in LOB due to structures.
Ineffective flow in ROB due to Fort Worth Floodway Levee.
Ham Branch channel in ROB.
END DESCRIPTION:
XS GIS Cut Line= 3
 2335777.3825067 6961179.6674733  2334475.146734 6958908.7648868
 2333416.8729834 6958006.3841126
#Sta/Elev= 30
       0  541.83  256.54   532.5  726.85  531.21 1296.87  520.07 1512.56  521.56
 1623.49  516.64 2292.28  515.98 2514.63  519.47 2530.52  524.63 2541.51     519
 2584.74  518.96 2610.64  511.68 2620.53  512.66 2689.13     492 2965.88  483.36
 3020.22  485.87 3056.23     492 3156.58  518.24 3273.78  512.87 3317.81  498.63
 3416.06  500.21 3428.18  496.84 3531.05  501.39 3593.53     512 3730.55  516.27
 3758.93     520 3791.23  533.33 3817.72   536.7 3926.82     530 4008.55  530.68
#Mann= 4 ,-1,0
       0      .1       0 2514.63     .06       0 2620.53    .035       0
 3156.58     .06       0
Levee=-1,2530.52,520.5,0,,,,
#XS Ineff= 5 ,-1
       0  445.65 541.768 1353.12 1518.89     540 3561.59 3817.72     540
 3817.72 4008.55     540 3156.58 3561.59  518.24
Permanent Ineff=
       F       F       F       T       F
Bank Sta=2620.53,3156.58
XS Rating Curve= 0 ,0
Exp/Cntr=0.3,0.1

Type RM Length L Ch R = 1 ,224600.2,315.01,480.92,510.44
BEGIN DESCRIPTION:
Flow confined up to 50-year flood at non-federal levee in LOB.
Ineffective flow in LOB due to structures.
Effective flow set at top of US 287 in ROB.
END DESCRIPTION:
XS GIS Cut Line= 4
 2335932.0128127 6961171.9360164 2334881.8416716 6958635.9885741
 2334837.8977654 6958596.9788046 2333989.8180344  6957785.778638
#Sta/Elev= 30
       0   543.8  215.87     536  225.83   532.5  302.31   532.5  310.21  535.49
  397.92  532.54  868.45     530 1283.05     518 1483.75  518.63 1751.57  515.14
 1917.55  517.76 2737.21  515.68 2743.46  521.13 2763.94  521.24 2783.34  513.66
 2813.57  512.17 2879.52     494 2906.83     490 3133.95  483.25  3217.6  486.62
 3316.61   514.5 3369.88  514.05 3453.02     518 3572.85  517.92 3591.22  514.95
  3782.5     516 3796.42  520.55 3886.08   519.7  3928.2     530 3977.13  531.57
#Mann= 4 ,-1,0
       0      .1       0 2737.21     .06       0 2813.57    .035       0
 3316.61     .06       0
Levee=-1,2763.94,520.5,0,,,,
#XS Ineff= 6 ,-1
    1439 1675.82     540 1915.16 2434.15     540       0  433.03 543.796
  934.09  993.45     540  724.94   787.2     540  562.27  643.52     540
Permanent Ineff=
       F       F       F       F       F       F
Bank Sta=2813.57,3316.61
XS Rating Curve= 0 ,0
Exp/Cntr=0.3,0.1