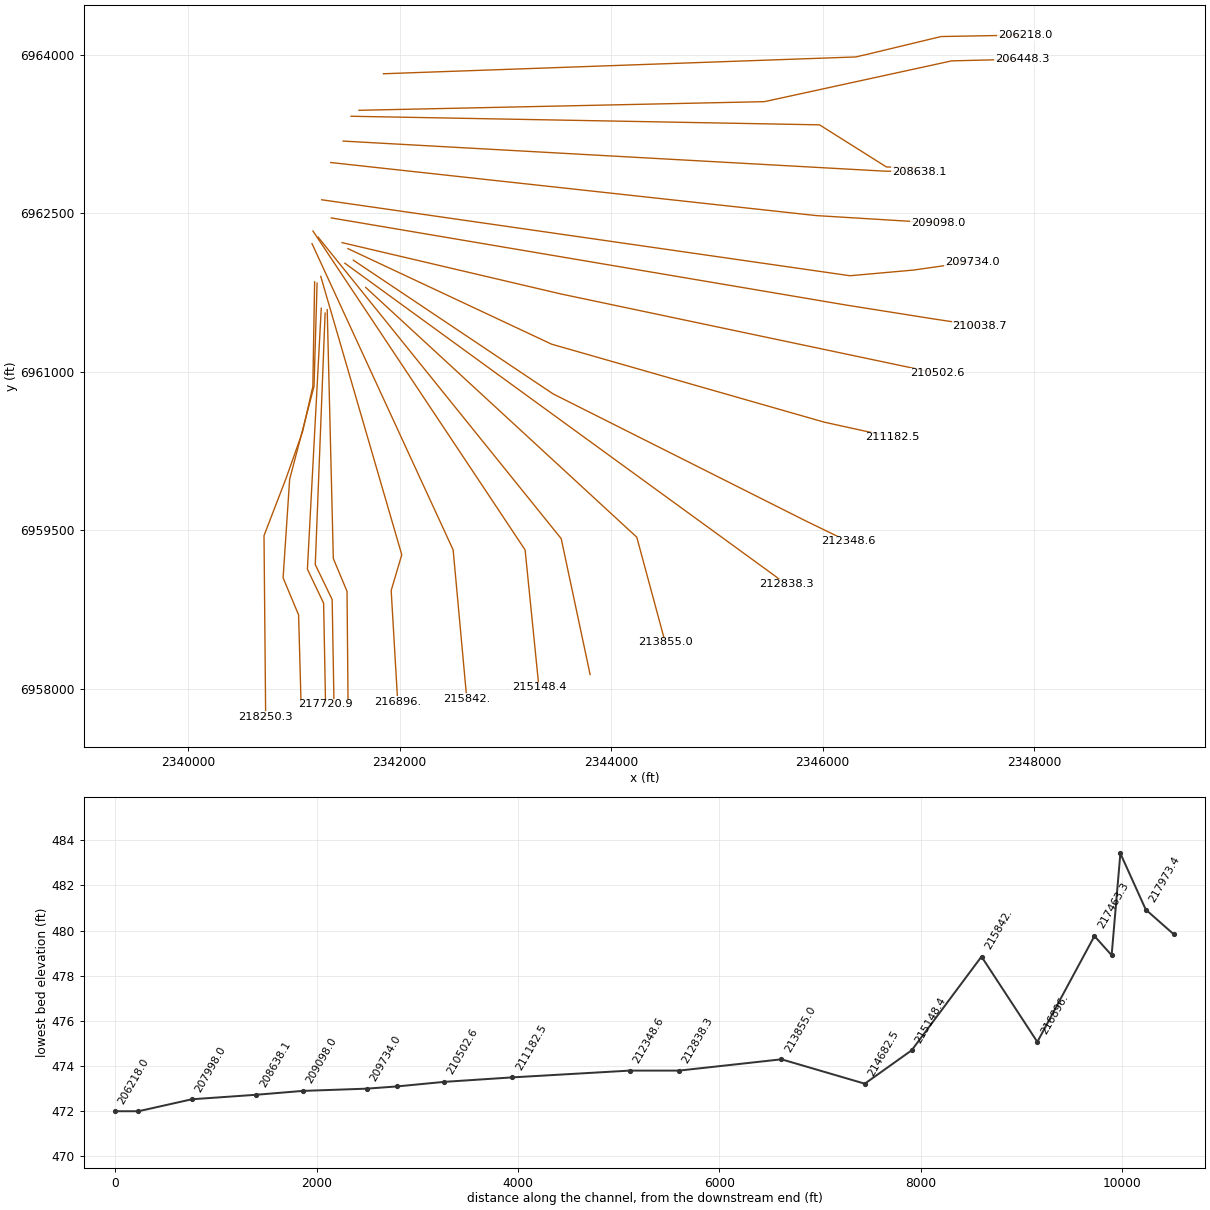
HEC-RAS study CDC_Consolidated_Model.prj: Upper Trinity CDC Consolidated Model

--- CDC_Consolidated_Model.g11 (geometry) --- (continued)

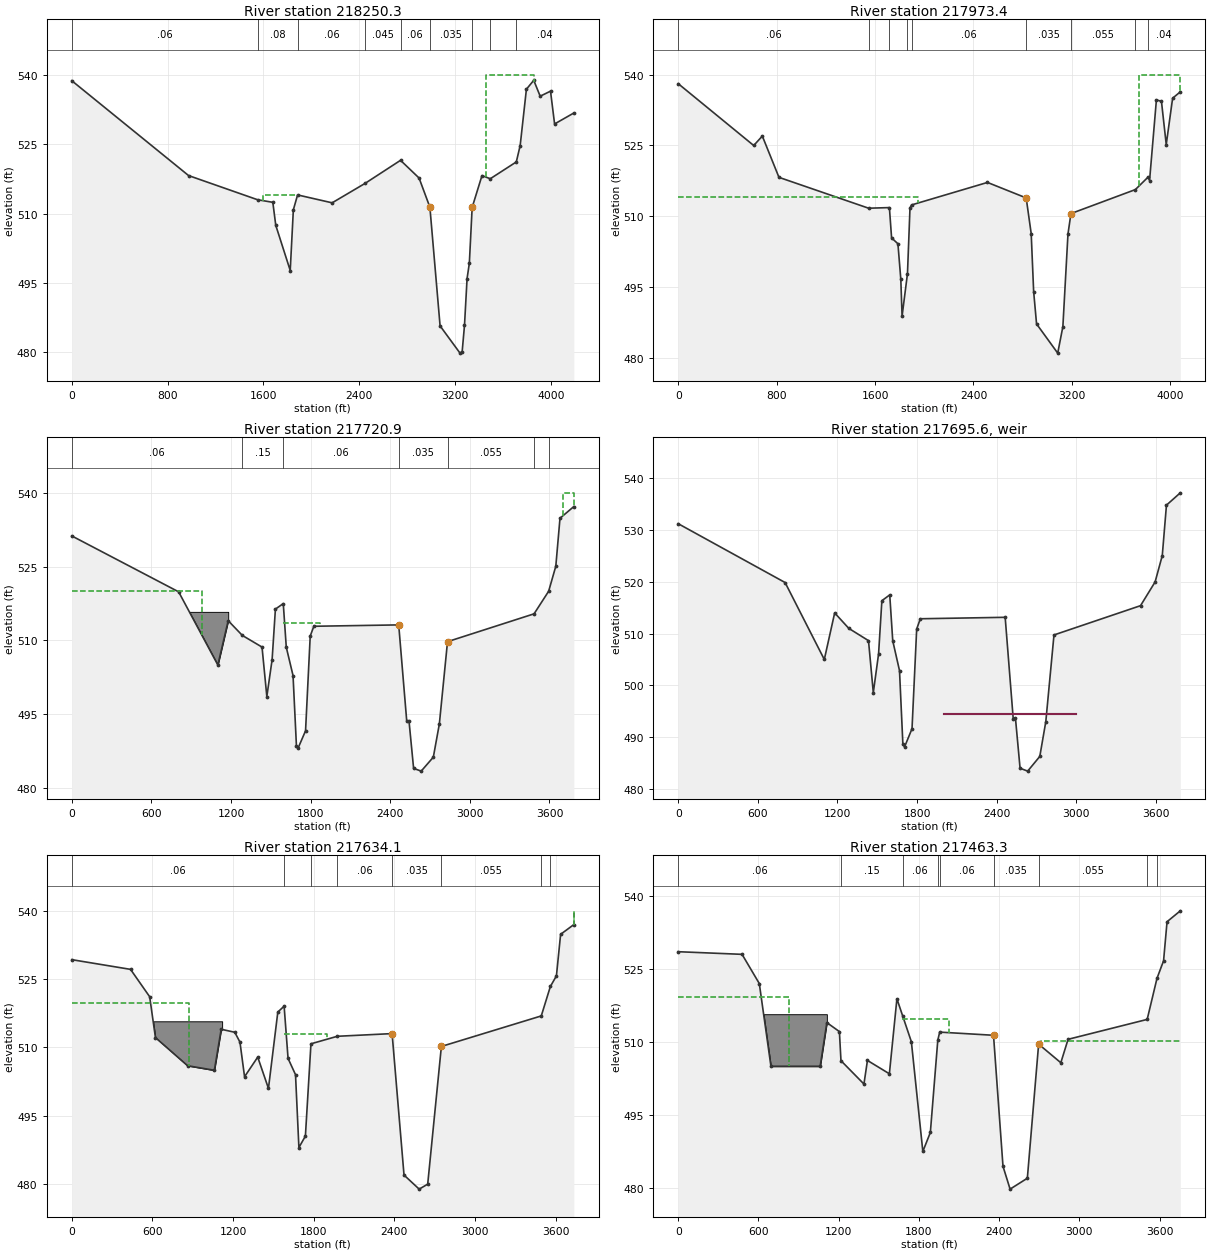
Type RM Length L Ch R = 1 ,218250.3,127.69,276.96,340.42
BEGIN DESCRIPTION:
2019 with channel
Ineffective flow in ROB due to Beach Street bridge.
Old West Fork oxbow channel in LOB.
END DESCRIPTION:
XS GIS Cut Line= 6
 2341195.0499155 6961849.8119465 2341178.0685564 6960859.5104318
 2341080.4784064 6960430.1140054 2340924.6108391 6959990.4702451
 2340716.1789835 6959448.9070871   2340731.84128 6957736.5101265
#Sta/Elev= 30
       0  538.73  975.17  518.22 1550.76     513 1678.14  512.44 1702.77  507.46
  1823.4   497.7 1849.46  510.82 1884.81  514.04 2173.23  512.33 2448.51  516.54
 2744.14  521.52 2898.83  517.69 2989.14  511.38 3074.18  485.73 3240.54  479.84
 3258.34  480.12 3277.97  485.84 3299.48  495.97 3318.45  499.28 3341.88  511.33
 3423.88  518.21 3493.29  517.54  3710.4  521.17 3742.67  524.71 3794.73  536.89
 3856.03  538.81 3909.65  535.38 3995.94  536.47 4029.96  529.38 4190.66  531.75
#Mann= 9 ,-1,0
       0     .06       0 1550.76     .08       0 1884.81     .06       0
 2448.51    .045       0 2744.14     .06       0 2989.14    .035       0
 3341.88    .045       0 3493.29     .15       0  3710.4     .04       0
#XS Ineff= 3 ,-1
 1600.03 1884.81     514 3454.52 3861.05     540 4190.66 4190.66     540
Permanent Ineff=
       T       F       T
Bank Sta=2989.14,3341.88
XS Rating Curve= 0 ,0
Exp/Cntr=0.5,0.3

Type RM Length L Ch R = 1 ,217973.4,217.76,252.48,245.74
BEGIN DESCRIPTION:
2019 with channel
Ineffective flow in ROB due to Beach Street bridge.
Old West Fork oxbow channel in LOB.
END DESCRIPTION:
XS GIS Cut Line= 6
2341218.313668226961837.016945732341189.234001966960861.10977681
 2340958.65309836959981.296575812340896.791345396959049.53433172
2341043.372088976958699.289953472341067.738510066957822.22313806
#Sta/Elev= 30
       0  538.12  613.49     525  683.61     527  818.71  518.24 1547.49  511.69
 1716.48  511.82 1734.23  505.39 1785.76  504.14 1809.23   496.6 1819.58  488.78
 1863.39  497.81 1883.88  511.76  1896.3  512.38 2513.68  517.16  2828.4  513.87
 2869.07  506.31 2889.04     494 2912.64  487.13 3084.69  480.93 3126.56  486.55
 3168.08  506.23 3192.24  510.55  3715.7  515.64 3819.08  518.29 3831.25  517.57
 3886.81  534.67  3927.9  534.38 3966.81  525.21  4018.7  535.04  4081.2  536.39
#Mann= 9 ,-1,0
       0     .06       0 1547.49     .15       0 1716.48     .06       0
 1863.39     .15       0  1896.3     .06       0  2828.4    .035       0
 3192.24    .055       0  3715.7     .15       0 3819.08     .04       0
#XS Ineff= 2 , 0
       0 1948.62     514 3744.83       0     540
Permanent Ineff=
       T       F
Bank Sta=2828.4,3192.24
XS Rating Curve= 0 ,0
Exp/Cntr=0.3,0.1

Type RM Length L Ch R = 1 ,217720.9,64.48,86.76,81.37
BEGIN DESCRIPTION:
Upstream of the Beach Street Dam
Ineffective flow in ROB due to Beach Street bridge.
Old West Fork oxbow channel in LOB.
END DESCRIPTION:
XS GIS Cut Line= 4
2341257.664967466961600.143075652341126.614704646959132.16835281
 2341280.11505386958809.907186312341298.222629136957854.53048815
#Sta/Elev= 30
       0  531.24  805.46  519.87 1100.88     505 1178.98     514 1285.56  511.01
  1433.9  508.64 1470.17  498.59  1509.9  506.08 1534.73  516.36    1594  517.48
 1616.68  508.61 1667.61  502.85  1693.1  488.61 1705.86  488.11 1761.94  491.62
 1797.08  510.88 1824.41  512.87 2464.01  513.15 2524.69  493.54 2541.44  493.67
 2576.27  483.98  2633.5  483.42 2724.94  486.26 2770.29     493 2831.87  509.74
 3484.19   515.4 3594.04  519.99 3648.02  525.08 3679.52  534.83 3783.95  537.21
#Mann= 7 ,-1,0
       0     .06       0 1285.56     .15       0    1594     .06       0
 2464.01    .035       0 2831.87    .055       0 3484.19     .15       0
 3594.04     .04       0
#XS Ineff= 4 ,-1
       0     980     520 1178.98 1589.73  512.85 1589.73 1870.39  513.44
 3701.37 3783.95     540
Permanent Ineff=
       F       F       T       T
#Block Obstruct= 1 ,-1
     500 1178.98   515.8
Bank Sta=2464.01,2831.87
XS Rating Curve= 0 ,0
Exp/Cntr=0.3,0.1

Type RM Length L Ch R = 5 ,217695.6,,,
BEGIN DESCRIPTION:
Beach Street Dam
Constructed by TRWD.  Data from TRWD plans.  Top of dam road surface elevation 494.5
-------------------------------
CDC FW112598-01
-------------------------------
END DESCRIPTION:
Node Name=Beach Street Dam
IW Pilot Flow=0
#Inline Weir SE= 2
    2000   494.5    3000   494.5
IW Dist,WD,Coef,Skew,MaxSub,Min_El,Is_Ogee,SpillHt,DesHd
16.55,17.5,3,0,0.95,, 0 ,,,1.5,3,
Inline Weir Flap Gates= 0
IW Outlet Rating Curve= 0 ,False,,

Type RM Length L Ch R = 1 ,217634.1,135.98,170.79,139.09
BEGIN DESCRIPTION:
Downstream of the Beach Street Dam
Ineffective flow in ROB due to Beach Street bridge.
Old West Fork oxbow channel in LOB.
END DESCRIPTION:
XS GIS Cut Line= 4
2341294.152755386961553.703864072341201.120789226959175.25619315
2341360.904918486958844.018666642341378.177521726957857.22700506
#Sta/Elev= 30
       0  529.28  437.22  527.15  579.58  521.14  622.36  512.18  861.36     506
  1060.7     505 1111.74     514 1212.87  513.34 1251.23  511.17 1285.38  503.58
 1383.33  507.89 1463.15  501.02  1532.8  517.78 1579.73  519.07 1609.02   507.6
 1664.44  504.04 1689.67  488.04 1737.99  490.55 1779.34  510.81 1975.47  512.46
 2382.97  513.05 2471.61     482  2584.3  478.91  2647.8     480 2749.55  510.23
 3492.69  516.93 3560.46   523.4 3605.39  525.72 3636.54  534.84 3734.97  536.98
#Mann= 8 ,-1,0
       0     .06       0 1579.73     .06       0 1779.34     .15       0
 1975.47     .06       0 2382.97    .035       0 2749.55    .055       0
 3492.69     .15       0 3560.46     .04       0
#XS Ineff= 4 ,-1
       0     870  519.75  1118.5 1576.34   512.6 1576.34 1898.39  512.86
 3732.57 3734.97     540
Permanent Ineff=
       F       F       T       T
#Block Obstruct= 1 ,-1
     500  1118.5  515.75
Bank Sta=2382.97,2749.55
XS Rating Curve= 0 ,0
Exp/Cntr=0.3,0.1

Type RM Length L Ch R = 1 ,217463.3,527.78,567.28,504.42
BEGIN DESCRIPTION:
Old West Fork oxbow channel in LOB.
END DESCRIPTION:
XS GIS Cut Line= 4
2341314.055274646961586.874729482341371.756602816959232.75345348
2341501.476487736958921.949941232341511.300943146957859.08231631
#Sta/Elev= 30
       0  528.54   477.2     528  606.24     522  693.27     505 1061.38     505
 1111.39  513.97 1205.13  512.13 1216.91  506.15  1388.7  501.35 1414.91   506.2
 1578.86  503.46 1635.29  518.87 1679.03  515.29 1743.31  510.05 1829.15   487.5
 1885.31   491.4 1940.99  510.36 1955.16  512.02 2357.64  511.37 2428.56  484.45
 2481.58  479.76  2610.7     482 2695.08  509.55 2860.95  505.73 2915.23  510.54
 3506.74  514.63 3580.19  523.07 3629.36  526.68 3655.34   534.7 3754.53  536.94
#Mann= 9 ,-1,0
       0     .06       0 1216.91     .15       0 1679.03     .06       0
 1940.99     .15       0 1955.16     .06       0 2357.64    .035       0
 2695.08    .055       0 3506.74     .15       0 3580.19     .04       0
#XS Ineff= 4 ,-1
       0     825  519.25    1150 1676.54   512.5 1676.54 2022.06  514.65
  2709.9 3754.53  510.14
Permanent Ineff=
       F       F       T       F
#Block Obstruct= 1 ,-1
     500 1111.39   515.7
Bank Sta=2357.64,2695.08
XS Rating Curve= 0 ,0
Exp/Cntr=0.3,0.1

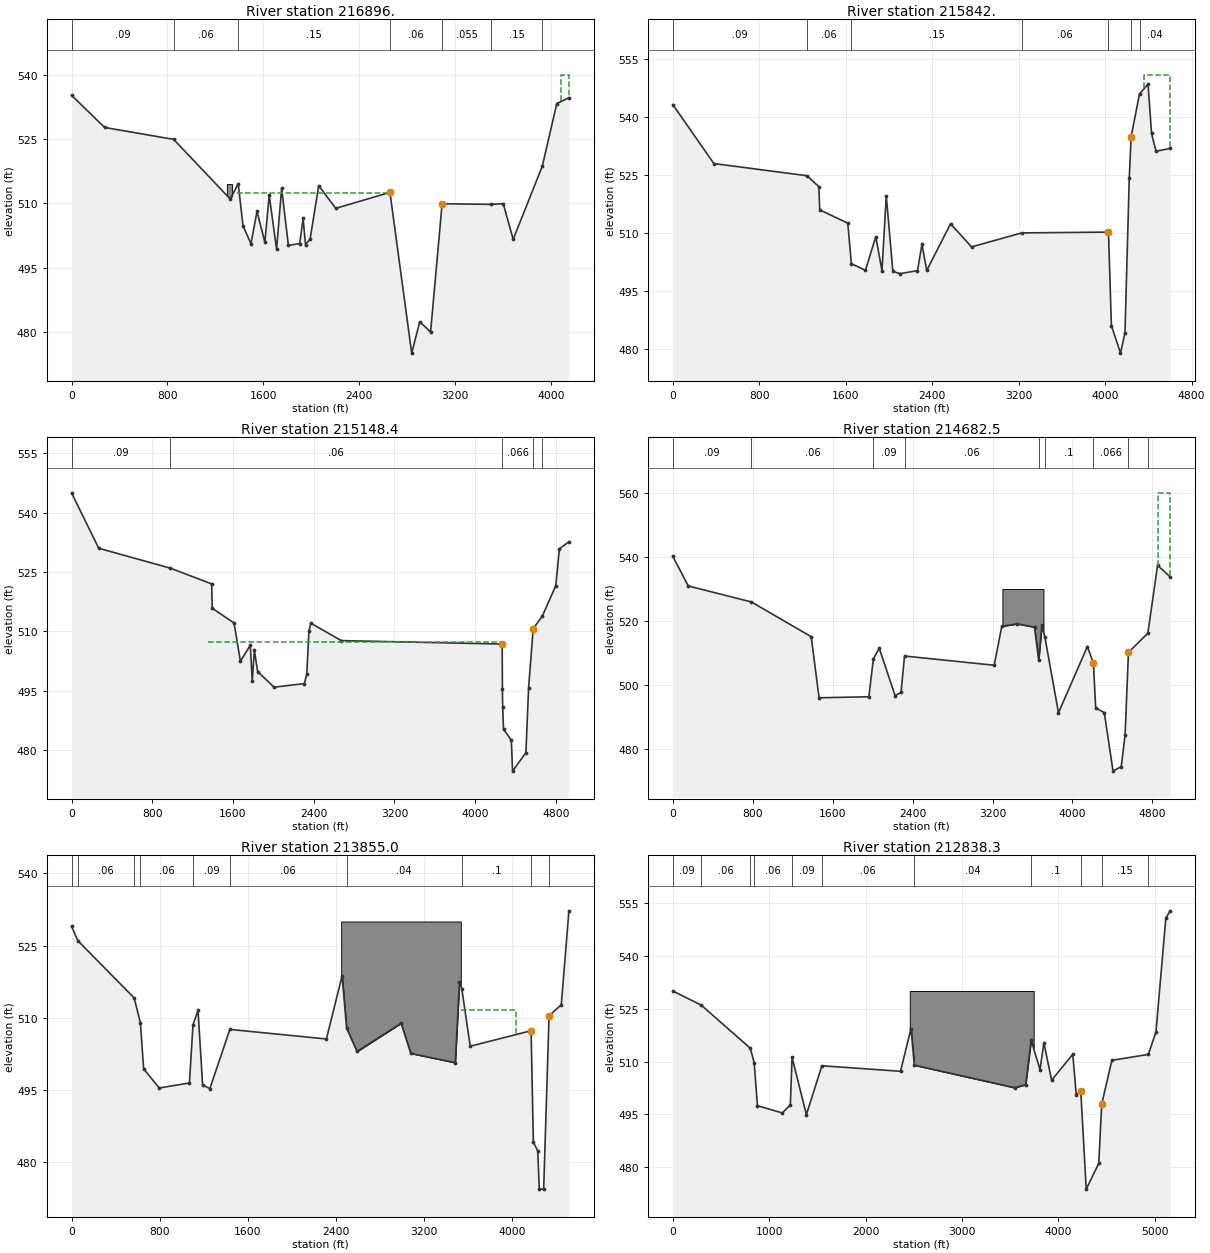
Type RM Length L Ch R = 1 ,216896. ,402.34,554.6,672.8
BEGIN DESCRIPTION:
Located at the old West Fork oxbow channel/modified West Fork river channel confluence.
Effective flow limit set at IH 30 in ROB.
Channel reach length modified to account for reduced effective length for high flows and to better compute volume.
END DESCRIPTION:
XS GIS Cut Line= 4
 2341253.09148586961901.052250732342019.223811816959268.51814573
2341919.096715476958930.021775482341980.787865066957875.72795232
#Sta/Elev= 30
       0  535.24  276.24  527.72  852.18  524.94 1325.02  511.01 1391.31   514.6
 1430.83  504.79 1497.31  500.62 1547.95  508.13  1613.3  500.94 1649.67  511.91
 1711.16  499.32 1753.33  513.52 1809.78  500.21 1904.58  500.64 1932.72  506.48
  1952.7  500.41 1991.11  501.72 2062.89  514.14 2204.82  508.85 2657.33  512.57
 2838.72  475.07 2906.29  482.41 2996.48     480 3092.66  509.92 3504.64  509.78
 3603.05  509.93 3685.76  501.62 3928.71  518.67 4049.69  533.29 4150.84  534.65
#Mann= 7 ,-1,0
       0     .09       0  852.18     .06       0 1391.31     .15       0
 2657.33     .06       0 3092.66    .055       0 3504.64     .15       0
 3928.71     .04       0
#XS Ineff= 4 ,-1
                            1380 2657.96  512.46 3091.63 4087.84  509.35
 4087.84 4150.84     540
Permanent Ineff=
       F       F       F       T
#Block Obstruct= 1 ,-1
 1296.19    1340   514.5
Bank Sta=2657.33,3092.66
XS Rating Curve= 0 ,0
Exp/Cntr=0.3,0.1

Type RM Length L Ch R = 1 ,215842. ,488.59,693.6,688
BEGIN DESCRIPTION:
Effective flow limit set at IH 30 in ROB.
END DESCRIPTION:
XS GIS Cut Line= 3
2341170.32131013 6962210.95976742342505.236619316959314.28117757
2342633.97389464 6957908.2400264
#Sta/Elev= 30
       0  543.28  379.84     528 1241.07  524.84 1351.18     522 1358.89     516
 1618.72  512.54 1651.76  502.03  1781.9  500.33 1877.93  509.06 1934.98  500.21
 1974.66  519.69 2035.47  500.07 2101.56  499.45 2263.55  500.25 2305.01  507.08
 2348.97  500.28  2569.5  512.39 2763.84  506.39 3228.03  510.02 4030.44  510.22
 4057.44     486 4141.53  478.85 4182.94  484.06  4222.6  524.14 4239.81  534.93
 4317.41  546.08 4396.65  548.55 4428.91  535.79 4470.39  531.18  4601.4  531.92
#Mann= 7 ,-1,0
       0     .09       0 1241.07     .06       0 1651.76     .15       0
 3228.03     .06       0 4030.44    .066       0 4239.81     .15       0
 4317.41     .04       0
#XS Ineff= 3 ,-1
    1500 1974.66   511.5 1974.66 3966.15     508 4363.11  4601.4     551
Permanent Ineff=
       F       F       T
Bank Sta=4030.44,4239.81
XS Rating Curve= 0 ,0
Exp/Cntr=0.3,0.1

Type RM Length L Ch R = 1 ,215148.4,258.51,465.92,467.53
XS GIS Cut Line= 3
 2341179.04635836962330.491680562343185.781518066959314.28117757
2343316.655600136958014.26606107
#Sta/Elev= 30
       0     545  269.45     531  978.93  525.97 1388.74     522 1394.46  515.84
 1611.05  512.11 1673.67  502.45 1771.79   506.5 1791.02  497.41 1811.73  505.26
 1844.66  499.83 2007.26  495.91 2307.16  496.81 2331.39  499.15 2352.98  510.14
 2370.41  512.08  2673.6  507.67 4267.99   506.8 4270.48  495.32  4273.1  490.83
 4281.21  485.29 4358.89  482.48 4371.08   474.7 4503.25  479.38 4529.62  495.64
 4575.43  510.69 4665.88  513.86 4799.44  521.56 4834.98  530.84 4929.37  532.65
#Mann= 5 ,-1,0
       0     .09       0  978.93     .06       0 4267.99    .066       0
 4575.43     .15       0 4665.88     .04       0
#XS Ineff= 2 ,-1
                            1350    4267   507.3
Permanent Ineff=
       F       F
Bank Sta=4267.99,4575.43
XS Rating Curve= 0 ,0
Exp/Cntr=0.3,0.1

Type RM Length L Ch R = 1 ,214682.5,449.83,827.51,751.01
BEGIN DESCRIPTION:
Abandoned sewage treatment plant in LOB - leveed plant blocked for conveyance and storage per CDC Model procedure.
END DESCRIPTION:
XS GIS Cut Line= 3
2341227.431760226962273.247372482343527.294286476959420.63299897
2343800.809159386958135.26549098
#Sta/Elev= 30
       0  540.21  154.53  530.96  786.85  525.97 1385.08  515.14 1463.95  496.09
 1962.41  496.41 2007.33  508.21 2066.07  511.55 2224.55  496.78 2284.24  497.78
 2319.17  509.11 3216.76  506.24 3292.73  518.37 3447.08  519.14 3620.16  518.11
 3662.06  507.77 3693.63  518.67 3724.74  514.89  3860.3  491.43 4149.54  512.08
 4210.03  506.87 4232.29  492.97  4318.9  491.46 4406.24  473.22 4488.38  474.63
 4526.81   484.4 4560.69  510.28  4754.9  516.22 4852.01  537.36  4978.4  533.79
#Mann= 9 ,-1,0
       0     .09       0  786.85     .06       0 2007.33     .09       0
 2319.17     .06       0 3662.06     .04       0 3724.74      .1       0
 4210.03    .066       0 4560.69     .15       0  4754.9    .035       0
#XS Ineff= 4 ,-1
                            1300 3298.86   507.1 3709.71 4149.54  512.08
 4857.87  4978.4     560
Permanent Ineff=
       F       F       F       T
#Block Obstruct= 1 ,-1
 3298.86 3709.71     530
Bank Sta=4210.03,4560.69
XS Rating Curve= 0 ,0
Exp/Cntr=0.5,0.3

Type RM Length L Ch R = 1 ,213855.0,412.13,1016.67,1085.46
BEGIN DESCRIPTION:
Abandoned sewage treatment plant in LOB - leveed plant blocked for conveyance and storage per CDC Model procedure.
Channel data estimated from USACE 1975 survey.
END DESCRIPTION:
XS GIS Cut Line= 3
2341678.095557056961796.997668822344242.183276646959434.27831289
2344510.673881386958440.86199264
#Sta/Elev= 30
       0     529   57.39     526  568.52  514.09  625.12  508.93  654.71  499.33
  796.26  495.35 1070.43  496.39 1102.75  508.48  1148.5  511.49 1190.19     496
 1255.63  495.21 1437.54  507.54 2313.83  505.55 2456.58  518.69 2497.54  507.77
 2592.41  502.95 2992.23  508.82 3079.51  502.55 3483.93  500.61 3522.22  517.45
 3543.19  516.03 3619.95  504.04 4172.55  507.27 4192.94   484.1 4233.06  482.26
  4246.6   474.3  4286.6   474.3 4335.61  510.37 4446.57  512.67 4515.75  532.22
#Mann= 10 ,-1,0
       0     .09       0   57.39     .06       0  568.52     .15       0
  625.12     .06       0 1102.75     .09       0 1437.54     .06       0
 2497.54     .04       0 3543.19      .1       0 4172.55    .066       0
 4335.61    .035       0
#XS Ineff= 3 ,-1
                             540 2448.23  507.27 3534.12 4037.12   511.5
Permanent Ineff=
       F       F       F
#Block Obstruct= 1 ,-1
 2448.23 3534.12     530
Bank Sta=4172.55,4335.61
XS Rating Curve= 0 ,0
Exp/Cntr=0.5,0.3

Type RM Length L Ch R = 1 ,212838.3,313.47,489.71,559.47
BEGIN DESCRIPTION:
Abandoned sewage treatment plant in LOB - leveed plant blocked for conveyance and storage per CDC Model procedure.
Channel data estimated from USACE 1975 survey.
END DESCRIPTION:
XS GIS Cut Line= 3
2341481.024756976962025.578576482345544.363743146959071.81578323
 2345653.0846543 6958987.1709394
#Sta/Elev= 30
       0  530.01  295.81  525.97   804.1  513.76  843.74   509.7  878.39  497.46
 1136.03  495.41 1219.65  497.72 1237.38  511.17  1385.9  494.93 1546.87  508.79
 2362.66  507.23 2471.92  519.34 2506.19  508.96 3546.53  502.57 3661.42  503.43
 3718.45  516.06 3810.12  507.71 3850.77  515.28 3930.64  504.69  4150.2  512.04
 4186.49  500.58 4233.38  501.54    4290   473.8 4420.25  481.11 4450.23  497.88
 4556.21  510.34 4934.07  512.01 5013.34  518.33 5116.09  550.69 5161.28  552.74
#Mann= 11 ,-1,0
       0     .09       0  295.81     .06       0   804.1     .15       0
  843.74     .06       0 1237.38     .09       0 1546.87     .06       0
 2506.19     .04       0 3718.45      .1       0 4233.38    .066       0
 4450.23     .15       0 4934.07    .035       0
#XS Ineff= 3 ,-1
                             640 2458.77     508 3744.61  4150.2   511.8
Permanent Ineff=
       F       F       F
#Block Obstruct= 1 ,-1
 2458.77 3744.61     530
Bank Sta=4233.38,4450.23
XS Rating Curve= 0 ,0
Exp/Cntr=0.5,0.3

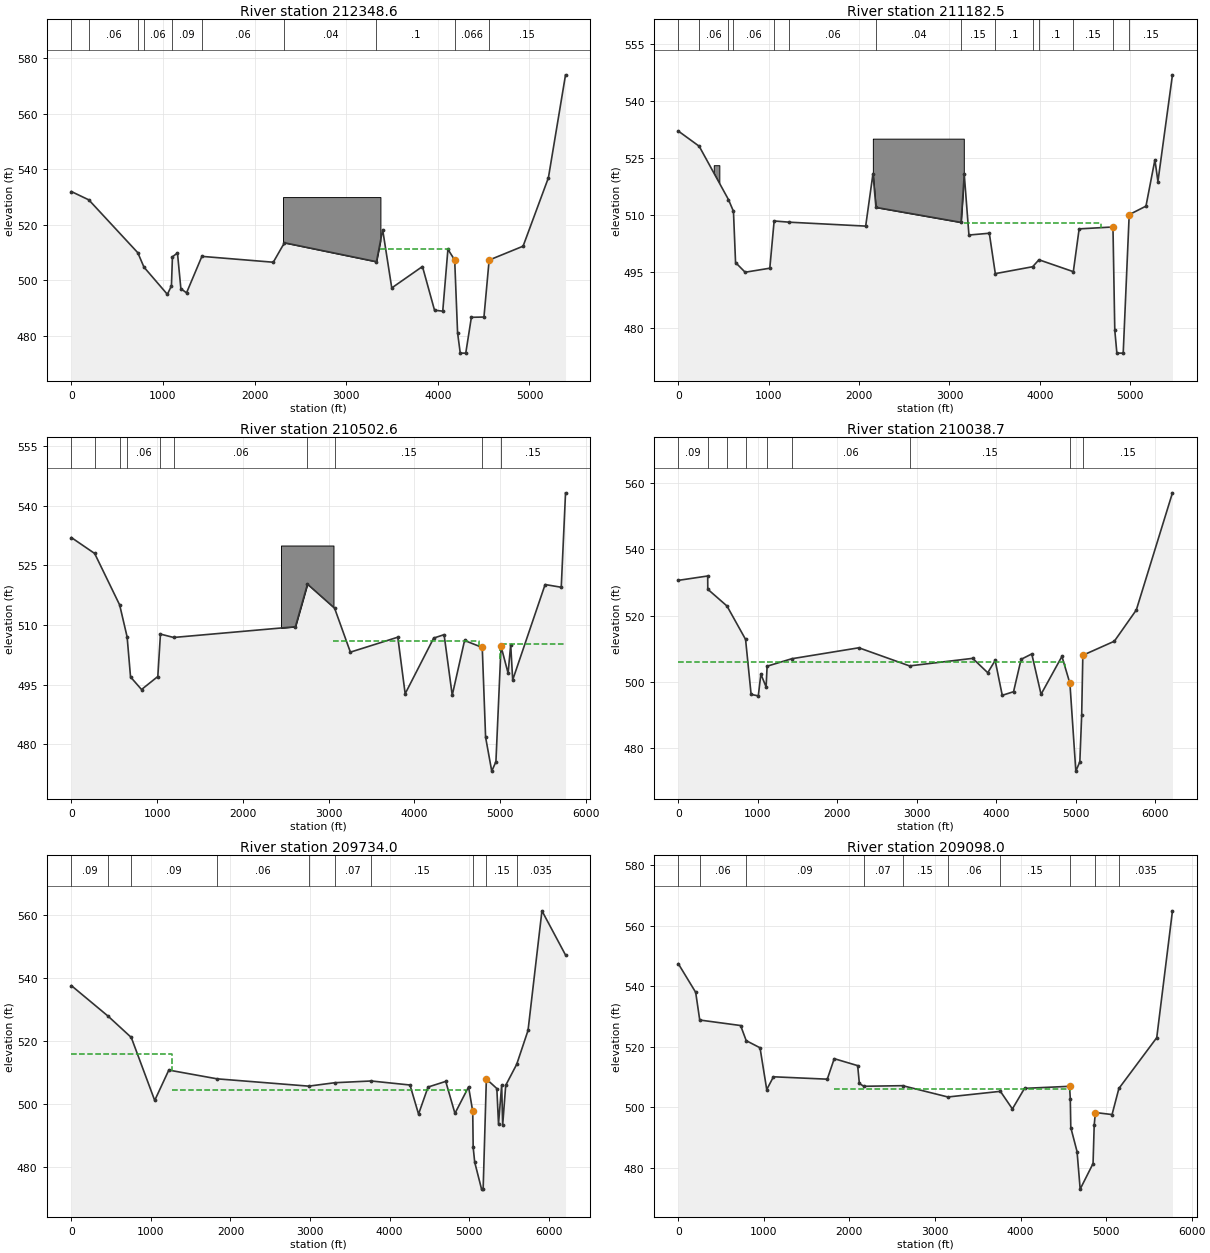
Type RM Length L Ch R = 1 ,212348.6,683.26,1166.14,1000.77
BEGIN DESCRIPTION:
Abandoned sewage treatment plant in LOB - leveed plant blocked for conveyance and storage per CDC Model procedure.
Channel data estimated from USACE 1975 survey.
END DESCRIPTION:
XS GIS Cut Line= 4
2341561.000974976962054.660867392343450.134991976960790.15683472
2345826.279189816959595.372806982346240.354149066959393.78790832
#Sta/Elev= 30
       0     532  190.49     529  725.32  509.95  791.92  504.79 1047.76  494.97
 1092.16  498.03 1103.02  508.49 1157.86  509.89 1195.06  497.03 1256.79   495.5
 1424.55  508.65 2203.71  506.54  2325.2  513.55 3329.64  506.73 3397.46  518.27
 3496.76  497.28 3831.77     505 3963.58  489.25 4053.28  488.92 4109.71  511.19
 4183.56  507.35 4215.14  481.13  4244.4   473.8  4304.4   473.8 4365.76   486.7
 4503.05   486.8 4559.56  507.32 4930.11  512.32 5206.41  536.96 5393.44  574.04
#Mann= 10 ,-1,0
       0     .09       0  190.49     .06       0  725.32     .15       0
  791.92     .06       0 1103.02     .09       0 1424.55     .06       0
  2325.2     .04       0 3329.64      .1       0 4183.56    .066       0
 4559.56     .15       0
#XS Ineff= 3 ,-1
                               0 2309.83   508.9 3373.04 4116.14   511.2
Permanent Ineff=
       F       F       F
#Block Obstruct= 1 ,-1
 2309.83 3373.04     530
Bank Sta=4183.56,4559.56
XS Rating Curve= 0 ,0
Exp/Cntr=0.5,0.3

Type RM Length L Ch R = 1 ,211182.5,598.23,679.85,681.95
BEGIN DESCRIPTION:
Abandoned sewage treatment plant in LOB - leveed plant blocked for conveyance and storage per CDC Model procedure.
Channel data estimated from USACE 1975 survey.
END DESCRIPTION:
XS GIS Cut Line= 4
2341510.107047896962163.718720142343436.710806226961260.01580314
2346014.283406976960522.688209562346657.48126756 6960381.2803559
#Sta/Elev= 30
       0     532  231.06     528   554.7  513.96  610.24  510.86  633.47  497.36
  739.64  494.81  1012.4  495.87 1060.26  508.31 1230.18  507.99 2073.13  506.96
 2153.96  520.79 2186.59  511.89 3128.49  507.94 3163.78  520.58 3215.58  504.61
 3441.08  505.08 3507.43  494.44 3920.65  496.26 3990.16  498.09 4370.61  494.96
    4435  506.23 4809.22  506.73 4829.36  479.53  4852.5   473.5  4922.5   473.5
 4988.72  509.98 5174.29  512.22 5273.23  524.42 5306.69  518.71 5467.54  546.81
#Mann= 14 ,-1,0
       0     .09       0  231.06     .06       0   554.7     .15       0
  610.24     .06       0 1060.26     .15       0 1230.18     .06       0
 2186.59     .04       0 3128.49     .15       0 3507.43      .1       0
 3920.65     .15       0 3990.16      .1       0 4370.61     .15       0
 4809.22    .066       0 4988.72     .15       0
#XS Ineff= 3 ,-1
                               0 2152.36  507.85 3158.62 4681.52  507.85
Permanent Ineff=
       F       F       F
#Block Obstruct= 2 ,-1
  392.33  454.18     523 2152.36 3158.62     530
Bank Sta=4809.22,4988.72
XS Rating Curve= 0 ,0
Exp/Cntr=0.5,0.3

Type RM Length L Ch R = 1 ,210502.6,424.16,463.91,470.54
BEGIN DESCRIPTION:
Channel data estimated from USACE 1975 survey.
Abandoned sewage treatment plant in LOB - leveed plant blocked for conveyance and storage per CDC Model procedure.
END DESCRIPTION:
XS GIS Cut Line= 3
2341454.800728056962220.429892812343520.837606476961735.80422165
2347085.76781255 6960984.6256059
#Sta/Elev= 30
       0     532  271.68     528  563.39  515.06  650.49  507.02  690.29  496.97
  818.55  493.81 1008.47  497.08 1039.14  507.74 1193.18  506.89 2613.76  509.59
 2754.51  520.29 3070.83  514.25 3255.17   503.2  3808.4  506.96 3894.31  492.75
 4226.84  506.73 4348.38   507.6 4443.45  492.37 4587.26  506.13 4793.63  504.38
 4832.63  481.83  4904.3   473.3 4953.13  475.66 5012.78  504.67 5095.19  497.91
 5125.47  505.08 5148.78  496.22    5527  520.19 5715.24  519.51 5765.32  543.24
#Mann= 10 ,-1,0
       0     .09       0  271.68     .06       0  563.39     .15       0
  650.49     .06       0 1039.14     .15       0 1193.18     .06       0
 2754.51     .04       0 3070.83     .15       0 4793.63    .066       0
 5012.78     .15       0
#XS Ineff= 4 ,-1
                               0 2445.58     506 3057.89 4752.77     506
 5006.34 5765.34  505.19
Permanent Ineff=
       F       F       F       F
#Block Obstruct= 1 ,-1
 2445.58 3057.89     530
Bank Sta=4793.63,5012.78
XS Rating Curve= 0 ,0
Exp/Cntr=0.5,0.3

Type RM Length L Ch R = 1 ,210038.7,265.25,304.71,330.74
BEGIN DESCRIPTION:
Channel data estimated from USACE 1975 survey.
END DESCRIPTION:
XS GIS Cut Line= 4
2341352.77402923 6962454.24077692346229.463094736961628.95601015
2347035.440485396961501.198719732347483.075416896961433.50430131
#Sta/Elev= 30
       0  530.68  369.71     532  370.72     528  612.11  522.94  845.96  512.86
  915.66  496.26 1006.01  495.81  1038.4  502.38  1104.2  498.51 1116.94  504.77
 1426.61  507.02 2270.71  510.33 2908.05  504.86 3702.16  507.14 3891.75   502.8
 3984.88  506.51 4074.09  495.98 4216.12  497.07 4311.12  506.85 4445.44  508.47
 4561.96  496.29 4824.56  507.73 4925.08  499.58  4999.5   473.1 5049.88  475.92
 5073.08  490.11  5087.5  508.07 5483.82  512.31  5760.1  521.74 6214.79   557.1
#Mann= 9 ,-1,0
       0     .09       0  370.72     .06       0  612.11     .09       0
  845.96     .06       0 1116.94     .15       0 1426.61     .06       0
 2908.05     .15       0 4925.08    .066       0  5087.5     .15       0
#XS Ineff= 2 ,-1
                               0 4864.49     506
Permanent Ineff=
       F       F
Bank Sta=4925.08,5087.5
XS Rating Curve= 0 ,0
Exp/Cntr=0.3,0.1

Type RM Length L Ch R = 1 ,209734.0,502.61,635.99,521.33
BEGIN DESCRIPTION:
Channel data estimated from USACE 1975 survey.
END DESCRIPTION:
XS GIS Cut Line= 4
2341261.937596726962626.003228652346258.771435056961907.38524331
2346859.399826976961960.996028482347415.36689089 6962040.2750694
#Sta/Elev= 30
       0  537.66  461.06  527.97  753.03  521.19 1047.72  501.18    1225  510.82
 1832.76  508.04 2984.07  505.72 3312.63  506.81 3769.24  507.36 4257.12  506.08
 4364.82  496.84 4484.28  505.43 4706.62  507.23 4822.44  497.06 4993.84  505.49
 5046.06  497.71 5051.63  486.28 5071.02  481.54    5157     473    5177     473
 5217.43     508 5349.09  504.96 5370.06  493.72 5409.88  506.03 5422.56  493.38
 5460.83  505.99 5598.86  512.66 5741.28  523.42 5916.18  561.42 6212.85  547.38
#Mann= 10 ,-1,0
       0     .09       0  461.06     .06       0  753.03     .09       0
 1832.76     .06       0 2984.07     .15       0 3312.63     .07       0
 3769.24     .15       0 5046.06    .066       0 5217.43     .15       0
 5598.86    .035       0
#XS Ineff= 3 ,-1
       0 1265.19  516.04 1265.19  4956.3  504.53 5217.43 6212.85     508
Permanent Ineff=
       F       F       F
Bank Sta=5046.06,5217.43
XS Rating Curve= 0 ,0
Exp/Cntr=0.3,0.1

Type RM Length L Ch R = 1 ,209098.0,427.51,459.96,465.95
BEGIN DESCRIPTION:
Channel data estimated from USACE 1975 survey.
END DESCRIPTION:
XS GIS Cut Line= 4
2341347.33079864 6962978.2495714 2345937.21203886962476.56487922
 2346696.29910336962430.144696472347093.643781056962406.59454672
#Sta/Elev= 30
       0  547.45  203.17  537.98  250.45  528.82  728.28     527  793.67     522
  955.16  519.64 1033.52  505.82  1112.1  510.05  1741.2  509.26 1822.34  516.04
 2096.29  513.74  2116.1  507.83 2168.73  506.91 2621.88  507.11 3150.84  503.37
 3764.67  505.24 3904.74  499.42 4046.56  506.22 4572.78   506.9 4581.58  502.73
 4587.36  493.27  4660.5  485.32    4697   472.9 4847.56  481.36 4861.03  494.08
 4874.82  498.23 5069.72  497.56  5149.4  506.18 5591.98  522.98 5775.76  564.93
#Mann= 10 ,-1,0
       0     .09       0  250.45     .06       0  793.67     .09       0
 2168.73     .07       0 2621.88     .15       0 3150.84     .06       0
 3764.67     .15       0 4572.78    .066       0 4874.82     .15       0
  5149.4    .035       0
#XS Ineff= 2 ,-1
       0 1822.34  516.04 1822.34 4576.29     506
Permanent Ineff=
       F       F
Bank Sta=4572.78,4874.82
XS Rating Curve= 0 ,0
Exp/Cntr=0.3,0.1

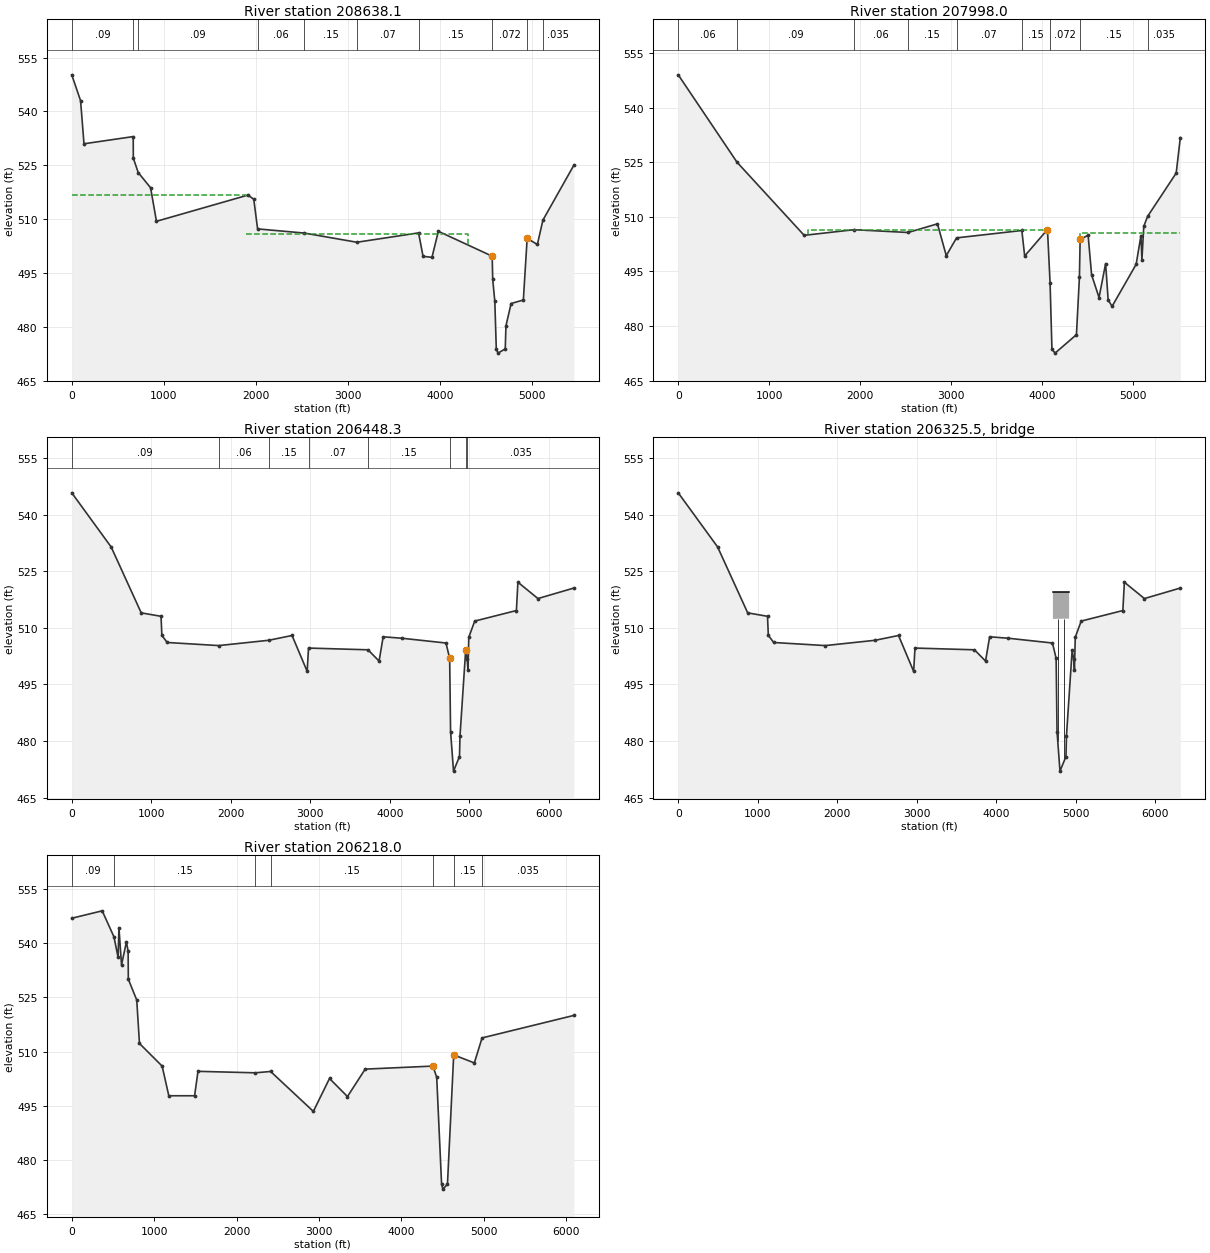
Type RM Length L Ch R = 1 ,208638.1,383.67,640.09,96.03
BEGIN DESCRIPTION:
Channel data estimated from USACE 1975 survey.
END DESCRIPTION:
XS GIS Cut Line= 3
2341464.746246226963181.058548972346581.710749816962896.83897306
2346910.535879556962891.71431139
#Sta/Elev= 30
       0  550.19    95.7  542.99  132.76     531  667.58     533  668.58     527
  721.66     523  856.18  518.75  919.85  509.42 1913.93  516.72 1977.12  515.56
 2018.43  507.31 2527.86  506.14 3096.93  503.59 3767.13   506.2 3815.74  499.68
 3912.59  499.39 3981.82  506.64  4566.8  499.71 4572.47  493.24 4595.26  487.17
  4611.3  473.89 4629.93  472.73 4708.56  473.91  4716.2  480.33 4772.24  486.54
 4905.18  487.52 4946.54  504.66 5057.61  502.97 5117.52  509.74 5453.71  525.03
#Mann= 10 ,-1,0
       0     .09       0  667.58     .06       0  721.66     .09       0
 2018.43     .06       0 2527.86     .15       0 3096.93     .07       0
 3767.13     .15       0  4566.8    .072       0 4946.54     .15       0
 5117.52    .035       0
#XS Ineff= 2 ,-1
       0 1892.38  516.73 1892.38    4303     506
Permanent Ineff=
       F       F
Bank Sta=4566.8,4946.54
XS Rating Curve= 0 ,0
Exp/Cntr=0.3,0.1

Type RM Length L Ch R = 1 ,207998.0,207.87,530.53,853.19
BEGIN DESCRIPTION:
Channel data estimated from USACE 1975 survey.
Channel reach length modified to account for reduced effective length for high flows and to better compute volume.
---------
CDC FW 030722-1 Scannell Properties.
Cross-sections 207988 - 218250.3
Located in LOB.
--------
END DESCRIPTION:
XS GIS Cut Line= 4
2341539.465256886963415.889772222345970.481329226963334.76690298
2346603.80781847 6962936.00556142346946.993155726962930.34973282
#Sta/Elev= 30
       0  549.03  646.94     525 1385.39  504.91 1933.37  506.46 2528.21  505.69
 2851.74  508.07 2948.68  499.33 3061.79  504.21 3780.08  506.24 3811.24  499.23
 4062.15  506.51 4090.84  491.72 4111.16  473.65  4145.3  472.53 4380.84  477.61
 4413.58  493.45 4421.31  503.78 4509.24  504.93 4547.34  494.07 4629.21  487.81
  4701.7  497.14 4729.64  487.14  4772.7  485.39 5037.61  496.94 5090.39  504.85
 5100.96  498.18 5121.48  507.38 5163.82  510.13 5478.17  522.02  5523.4  531.77
#Mann= 9 ,-1,0
       0     .06       0  646.94     .09       0 1933.37     .06       0
 2528.21     .15       0 3061.79     .07       0 3780.08     .15       0
 4090.84    .072       0 4421.31     .15       0 5163.82    .035       0
#XS Ineff= 3 ,-1
    1432    4062  506.38 4421.31  5523.4  505.56
Permanent Ineff=
       F       F       F
Bank Sta=4062.15,4421.31
XS Rating Curve= 0 ,0
Exp/Cntr=0.3,0.1

Type RM Length L Ch R = 1 ,206448.3,392.86,230.35,235.73
BEGIN DESCRIPTION:
Upstream bounding cross-section East 1st Street.
Channel data estimated from USACE 1975 survey.
*********************************************************************
CDC FW070700-01 Dyer Addition
Located in LOB.
Cross-sections 206448.3 - 209088.06
*********************************************************************
END DESCRIPTION:
XS GIS Cut Line= 4
 2341614.8601598  6963472.279432 2345449.1497094 6963553.9425653
 2347221.6992953  6963939.931137 2347885.2533845 6963955.9284139
#Sta/Elev= 30
       0  545.86  495.22  531.49  873.42     514 1122.44  513.09  1132.8  508.03
 1200.06  506.14 1848.69  505.32 2477.39  506.73 2769.83     508 2960.08  498.47
 2976.68  504.66 3724.65   504.2 3864.07  501.21 3915.52  507.65 4150.01  507.27
 4705.57     506 4751.54  501.92 4762.99   482.5    4800     472 4875.04  475.87
 4881.39  481.32  4952.9  504.12 4971.28  501.78 4982.15  498.97 4992.12  507.53
 5066.66  511.82  5590.6  514.62 5609.65  522.14 5861.49   517.8 6312.99  520.59
#Mann= 8 ,-1,0
       0     .09       0 1848.69     .06       0 2477.39     .15       0
 2976.68     .07       0 3724.65     .15       0 4751.54    .066       0
  4952.9     .15       0 4971.28    .035       0
#XS Ineff= 2 , 0
                         6312.99
Permanent Ineff=
       F       F
Bank Sta=4751.54,4952.9
XS Rating Curve= 0 ,0
Exp/Cntr=0.3,0.1

Type RM Length L Ch R = 3 ,206325.5,,,
BEGIN DESCRIPTION:
East 1st Street
Data from USACE 1975 survey.
Note:  Internal bridge cross-sections modified to represent geometry under bridge.
END DESCRIPTION:
Node Name=East 1st Street
Bridge Culvert--1,0,-1,-1, 0
Deck Dist Width WeirC Skew NumUp NumDn MinLoCord MaxHiCord MaxSubmerge Is_Ogee
110.3,25,2.6,0, 2, 2, , , 0.95, 0, 0,0,,
 4711.04 4914.96
   519.5   519.5
  512.38  512.48
 4711.04 4914.96
   519.5   519.5
  512.38  512.48
Pier Skew, UpSta & Num, DnSta & Num=  ,4772.04, 2 ,4772.04, 2 , 0 , 0 , 0 ,,
       6       6
     450     515
       6       6
     450     515
Pier Skew, UpSta & Num, DnSta & Num=  ,4852.04, 2 ,4852.04, 2 , 0 , 0 , 0 ,,
       6       6
     450     515
       6       6
     450     515
BR Coef=-1 , 0 , 0 ,, 0 ,,,0.8,-1,,0,
WSPro=,,,, 1 ,,,, 0 ,,,, 0 ,,,,-1 ,-1 ,-1 , 0 , 0 , 0 , 0 , 0
BR U #Sta/Elev= 492
       0  548.23     .68  548.22   26.63   547.6   27.12   547.6   52.94  546.99
   53.64  546.98   80.06  546.35  105.64  545.75  162.76     544  171.86  543.86
  211.57  542.72  231.62     542  238.86  541.94  254.87  541.48  270.84  541.01
  301.83  540.12  348.43  538.63  360.89  538.22   364.2  538.08  364.98   538.1
  393.81  537.18  396.27  537.09  401.23  537.12  401.85  536.89   423.5  536.11
  426.57  535.99  471.45  534.37  478.54  534.06  480.08  534.02  521.09   532.3
  526.97  531.96  530.23  531.92   542.2  531.41  543.35  531.34  571.34  530.16
  574.93  529.98  588.42  529.39  600.27  528.86  611.35  528.39  619.77  528.05
  625.98  527.69  629.29  527.53  653.23  526.46  659.35  526.18  662.23     526
  675.29  525.33  676.51  525.35  696.28  524.38  708.11  523.81  713.31  523.51
   718.9  523.28  729.93  522.75  744.06     522  759.93  521.24  766.58  520.91
   767.2  520.93  775.99  520.49  784.52     520  817.55  518.52  821.63  518.31
  873.18  516.03  875.77  515.95  880.24  515.73  880.66  515.66  887.62  515.32
  894.53  514.96  894.88  515.05  907.57  514.48  911.05  514.48  913.81  514.38
  944.92  513.38   975.2  512.43  983.79  512.15  992.43  511.97  996.47  511.75
 1008.81  511.36    1014  511.31 1056.69  509.98 1059.18  510.13  1072.4     510
  1080.1  509.75  1106.4  509.28  1119.5  509.04 1123.71  509.41 1125.76  509.94
 1127.82  509.32 1132.46  508.04 1134.21     508 1135.66  507.66  1142.1  507.51
 1145.23  507.48 1157.49  507.47 1181.85  506.99 1194.92  506.98 1222.42  506.45
 1236.26  506.44  1248.7  506.35 1252.43  506.08 1259.65   505.9 1267.88  505.89
 1271.51   505.6 1277.21  505.72  1286.3  505.66 1291.02  505.68 1292.98  505.64
 1298.38  505.61 1302.78  505.51 1308.31  505.48 1312.57  505.39 1318.34  505.36
 1322.47  505.28 1336.45   505.2 1350.87   505.1 1364.84  505.02 1365.34  504.99
 1372.72  504.95 1406.64  504.74 1420.29  504.64 1438.49  504.56  1467.8  504.46
 1483.46  504.38 1507.54  504.38 1518.44   504.4  1529.6   504.4 1540.82  504.42
 1566.07  504.43 1577.53  504.45  1598.2  504.45 1599.99  504.46 1618.06  504.46
 1644.37  504.48 1664.86  504.48 1686.21   504.5 1702.13   504.5 1703.67  504.51
 1721.45  504.51 1729.55  504.52 1750.18  504.69 1769.61  504.84 1816.08  505.23
 1826.01   505.3 1835.91  505.39  1869.8  505.66 1890.25  505.83 1899.43  505.89
 1911.13  506.03  1921.1  506.08 1925.48  506.07 1928.99     506 1937.39  506.07
 1937.53  506.44 1963.88   506.8 1971.65   506.9 2017.44  506.92 2043.85  506.94
 2054.01  506.94 2117.31  506.98  2143.9  507.02 2170.31  507.07 2187.23  507.09
 2194.71  507.11 2218.62  507.15 2236.69  507.15 2238.36  507.16 2256.36  507.16
 2258.73  507.17 2277.34  507.17 2284.32  507.18 2312.38  507.18 2313.98  507.19
 2334.23  507.19 2387.86  507.25 2396.26  507.25 2407.53  507.27 2416.05  507.27
 2446.08  507.31 2453.59  507.31 2478.63  507.35 2488.36  507.44 2493.46  507.46
 2511.34  507.62 2517.63  507.66 2522.86  507.72 2544.98   507.9 2557.96  507.97
 2568.12  507.99 2598.98     508 2609.65  508.01  2628.1  508.01 2676.41  508.04
 2706.41  508.05 2726.55  508.07 2745.67  508.08 2752.97  508.11 2770.37  508.13
 2779.42  508.15 2785.39  507.98 2789.73  507.97  2812.7  508.02 2827.69  508.06
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BR U #Mann= 3
       0     .06 4711.04    .055 4914.96     .06
BR U Banks=4711.04,4914.96
BR D #Sta/Elev= 492
       0  548.23     .68  548.22   26.63   547.6   27.12   547.6   52.94  546.99
   53.64  546.98   80.06  546.35  105.64  545.75  162.76     544  171.86  543.86
  211.57  542.72  231.62     542  238.86  541.94  254.87  541.48  270.84  541.01
  301.83  540.12  348.43  538.63  360.89  538.22   364.2  538.08  364.98   538.1
  393.81  537.18  396.27  537.09  401.23  537.12  401.85  536.89   423.5  536.11
  426.57  535.99  471.45  534.37  478.54  534.06  480.08  534.02  521.09   532.3
  526.97  531.96  530.23  531.92   542.2  531.41  543.35  531.34  571.34  530.16
  574.93  529.98  588.42  529.39  600.27  528.86  611.35  528.39  619.77  528.05
  625.98  527.69  629.29  527.53  653.23  526.46  659.35  526.18  662.23     526
  675.29  525.33  676.51  525.35  696.28  524.38  708.11  523.81  713.31  523.51
   718.9  523.28  729.93  522.75  744.06     522  759.93  521.24  766.58  520.91
   767.2  520.93  775.99  520.49  784.52     520  817.55  518.52  821.63  518.31
  873.18  516.03  875.77  515.95  880.24  515.73  880.66  515.66  887.62  515.32
  894.53  514.96  894.88  515.05  907.57  514.48  911.05  514.48  913.81  514.38
  944.92  513.38   975.2  512.43  983.79  512.15  992.43  511.97  996.47  511.75
 1008.81  511.36    1014  511.31 1056.69  509.98 1059.18  510.13  1072.4     510
  1080.1  509.75  1106.4  509.28  1119.5  509.04 1123.71  509.41 1125.76  509.94
 1127.82  509.32 1132.46  508.04 1134.21     508 1135.66  507.66  1142.1  507.51
 1145.23  507.48 1157.49  507.47 1181.85  506.99 1194.92  506.98 1222.42  506.45
 1236.26  506.44  1248.7  506.35 1252.43  506.08 1259.65   505.9 1267.88  505.89
 1271.51   505.6 1277.21  505.72  1286.3  505.66 1291.02  505.68 1292.98  505.64
 1298.38  505.61 1302.78  505.51 1308.31  505.48 1312.57  505.39 1318.34  505.36
 1322.47  505.28 1336.45   505.2 1350.87   505.1 1364.84  505.02 1365.34  504.99
 1372.72  504.95 1406.64  504.74 1420.29  504.64 1438.49  504.56  1467.8  504.46
 1483.46  504.38 1507.54  504.38 1518.44   504.4  1529.6   504.4 1540.82  504.42
 1566.07  504.43 1577.53  504.45  1598.2  504.45 1599.99  504.46 1618.06  504.46
 1644.37  504.48 1664.86  504.48 1686.21   504.5 1702.13   504.5 1703.67  504.51
 1721.45  504.51 1729.55  504.52 1750.18  504.69 1769.61  504.84 1816.08  505.23
 1826.01   505.3 1835.91  505.39  1869.8  505.66 1890.25  505.83 1899.43  505.89
 1911.13  506.03  1921.1  506.08 1925.48  506.07 1928.99     506 1937.39  506.07
 1937.53  506.44 1963.88   506.8 1971.65   506.9 2017.44  506.92 2043.85  506.94
 2054.01  506.94 2117.31  506.98  2143.9  507.02 2170.31  507.07 2187.23  507.09
 2194.71  507.11 2218.62  507.15 2236.69  507.15 2238.36  507.16 2256.36  507.16
 2258.73  507.17 2277.34  507.17 2284.32  507.18 2312.38  507.18 2313.98  507.19
 2334.23  507.19 2387.86  507.25 2396.26  507.25 2407.53  507.27 2416.05  507.27
 2446.08  507.31 2453.59  507.31 2478.63  507.35 2488.36  507.44 2493.46  507.46
 2511.34  507.62 2517.63  507.66 2522.86  507.72 2544.98   507.9 2557.96  507.97
 2568.12  507.99 2598.98     508 2609.65  508.01  2628.1  508.01 2676.41  508.04
 2706.41  508.05 2726.55  508.07 2745.67  508.08 2752.97  508.11 2770.37  508.13
 2779.42  508.15 2785.39  507.98 2789.73  507.97  2812.7  508.02 2827.69  508.06
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BR D #Mann= 3
       0     .06 4711.04    .055 4914.96     .06
BR D Banks=4711.04,4914.96
BC Design=,, 0 ,, 0 ,,,,,,
BC Use User HTab Curves=0
BC User HTab FreeFlow(D)= 0

Type RM Length L Ch R = 1 ,206218.0,0,0,0
BEGIN DESCRIPTION:
Downstream bounding cross-section East 1st Street.
Central City model begins here.
********************************************************************* Rating curve as downstream condition developed from the current Upper Trinity River CDC Model.
*********************************************************************
Channel data estimated from USACE 1975 survey.
END DESCRIPTION:
XS GIS Cut Line= 6
 2341845.9053506 6963817.9431903 2346312.9119604 6963976.7416045
 2346371.6292382 6963990.4388543 2346418.4155785 6964000.7863981
 2347120.3884165 6964169.8681855  2347913.795191 6964184.3126089
#Sta/Elev= 30
       0  546.85  369.23   548.9  512.04  541.71  562.18  536.03  572.53  544.23
  603.81  533.98  663.08  540.28  684.12  537.77  686.41     530  788.51  524.26
  821.63  512.25 1096.67     506  1177.8   497.8 1490.48   497.8  1532.1  504.55
 2227.97  504.14 2413.28  504.51 2932.16  493.48 3128.06  502.57 3345.99  497.58
 3560.99  505.16 4383.29     506 4429.29  502.89 4488.22  473.47 4503.96     472
 4559.71  473.37 4635.51  509.09 4886.06  506.87 4979.55  513.78 6093.63     520
#Mann= 7 ,-1,0
       0     .09       0  512.04     .15       0 2227.97     .06       0
 2413.28     .15       0 4383.29    .066       0 4635.51     .15       0
 4979.55    .035       0
#XS Ineff= 2 , 0
                         6093.63
Permanent Ineff=
       F       F
Bank Sta=4383.29,4635.51
XS Rating Curve= 0 ,0
Exp/Cntr=0.3,0.1
Stream Node=Clear Fork      ,cf              , 0 , 0 ,Upstream end
Stream Node=Clear Fork      ,cf              , 0 , 1 ,Downstream end
Stream Node=West Fork       ,wf4             , 0 , 0 ,Upstream end
Stream Node=West Fork       ,wf4             , 0 , 1 ,Downstream end
Stream Node=West Fork       ,wf3             , 0 , 0 ,Upstream end
Stream Node=West Fork       ,wf3             , 0 , 1 ,Downstream end
LCMann Table=0

Chan Stop Cuts=-1
Use User Specified Reach Order=0
User Specified Reach Order=West Fork       ,wf2
User Specified Reach Order=West Fork       ,wf3
User Specified Reach Order=West Fork       ,wf4
User Specified Reach Order=Clear Fork      ,cf
Composite Channel Slope=5

--- CDC_Consolidated_Model.g01 (geometry) ---

Geom Title=Exist: 10%, 4%, 2%, 1% AEP [WF/EF/TRMS]
Program Version=6.60
BEGIN GEOM DESCRIPTION:
Existing: Geometry file for use with 10%, 4%, 2%, 1% AEP peak flows for the WF/EF/TRMS, and for the FEMA Floodway
END GEOM DESCRIPTION:

Junct Name=ef-wf
Junct Desc=, 0 , 0 , 0 ,0
Up River,Reach=Elm Fork        ,ef1
Up River,Reach=West Fork       ,wf1
Dn River,Reach=Main Stem       ,ms
Junc L&A=3040,20
Junc L&A=1494,0

Junct Name=ef5-ef4-efs2
Junct Desc=, 0 , 0 , 0 ,0
Up River,Reach=Elm Fork        ,ef5
Dn River,Reach=Elm Fork        ,ef4
Dn River,Reach=Elm Fork Split2 ,efs2
Junc L&A=2415,
Junc L&A=1129,

Junct Name=ef4-efs2-ef3
Junct Desc=, 0 , 0 , 0 ,0
Up River,Reach=Elm Fork        ,ef4
Up River,Reach=Elm Fork Split2 ,efs2
Dn River,Reach=Elm Fork        ,ef3
Junc L&A=513,
Junc L&A=1010,

Junct Name=ef6-efl-ef5
Junct Desc=, 0 , 0 , 0 ,0
Up River,Reach=Elm Fork        ,ef6
Up River,Reach=Elm Fork L-Spill,efl
Dn River,Reach=Elm Fork        ,ef5
Junc L&A=612,0
Junc L&A=2000,80

Junct Name=ef3-ef2-efs1
Junct Desc=, 0 , 0 ,-1 ,0
Up River,Reach=Elm Fork        ,ef3
Dn River,Reach=Elm Fork        ,ef2
Dn River,Reach=Elm Fork Split1 ,efs1
Junc L&A=1005,
Junc L&A=500,

Junct Name=ef2-efs1-ef1
Junct Desc=, 0 , 0 ,-1 ,0
Up River,Reach=Elm Fork        ,ef2
Up River,Reach=Elm Fork Split1 ,efs1
Dn River,Reach=Elm Fork        ,ef1
Junc L&A=275,
Junc L&A=100,

Junct Name=wf3gwf3ewf3f
Junct Desc=, 0 , 0 ,-1 ,0
Up River,Reach=West Fork       ,wf3
Dn River,Reach=West Fork       ,wf3f
Dn River,Reach=West Fork       ,wf3e
Junc L&A=180,0
Junc L&A=895,0

Junct Name=wf3ewf3fwf3d
Junct Desc=, 0 , 0 ,-1 ,0
Up River,Reach=West Fork       ,wf3f
Up River,Reach=West Fork       ,wf3e
Dn River,Reach=West Fork       ,wf3d
Junc L&A=550,0
Junc L&A=305,0

Junct Name=wf3dwf3bwf3c
Junct Desc=, 0 , 0 ,-1 ,0
Up River,Reach=West Fork       ,wf3d
Dn River,Reach=West Fork       ,wf3b
Dn River,Reach=West Fork       ,wf3c
Junc L&A=1327,0
Junc L&A=840,0

Junct Name=wf3bwf3cwf3a
Junct Desc=, 0 , 0 ,-1 ,0
Up River,Reach=West Fork       ,wf3b
Up River,Reach=West Fork       ,wf3c
Dn River,Reach=West Fork       ,wf3a
Junc L&A=3192,0
Junc L&A=740,0

Junct Name=wf3a-wf2-wfs
Junct Desc=, 0 , 0 ,-1 ,0
Up River,Reach=West Fork       ,wf3a
Dn River,Reach=West Fork       ,wf2
Dn River,Reach=West Fork Split ,wfs
Junc L&A=1500,0
Junc L&A=500,0

Junct Name=wfs-wf2-wf1
Junct Desc=, 0 , 0 ,-1 ,0
Up River,Reach=West Fork       ,wf2
Up River,Reach=West Fork Split ,wfs
Dn River,Reach=West Fork       ,wf1
Junc L&A=937,0
Junc L&A=937,0

River Reach=Elm Fork L-Spill,efl
Reach XY= 30
      2451737.34      7074615.52      2451160.73      7070671.78
      2450672.18      7070144.08      2449903.65      7069914.65
      2449400.97      7069330.44      2448360.65      7069030.65
      2447453.37       7069372.2      2446791.42      7069358.45
      2446224.26      7069727.31      2445576.06      7069838.23
      2443448.88      7069483.23      2442684.97      7069013.34
       2442525.1      7069212.15      2441972.49      7069020.23
      2441526.94      7069208.05       2441203.1      7069005.14
      2440850.56      7069029.73      2440955.29      7068759.25
       2440630.7      7068827.13      2440501.92      7068571.07
      2441216.66      7068357.13      2441211.29       7068119.7
       2440934.6      7068021.32      2441088.32      7067781.51
      2440856.71      7067752.82       2440958.6       7067428.5
      2440655.07      7067329.59      2440432.53       7067546.2
      2439901.58      7067254.76      2439760.19      7066982.89