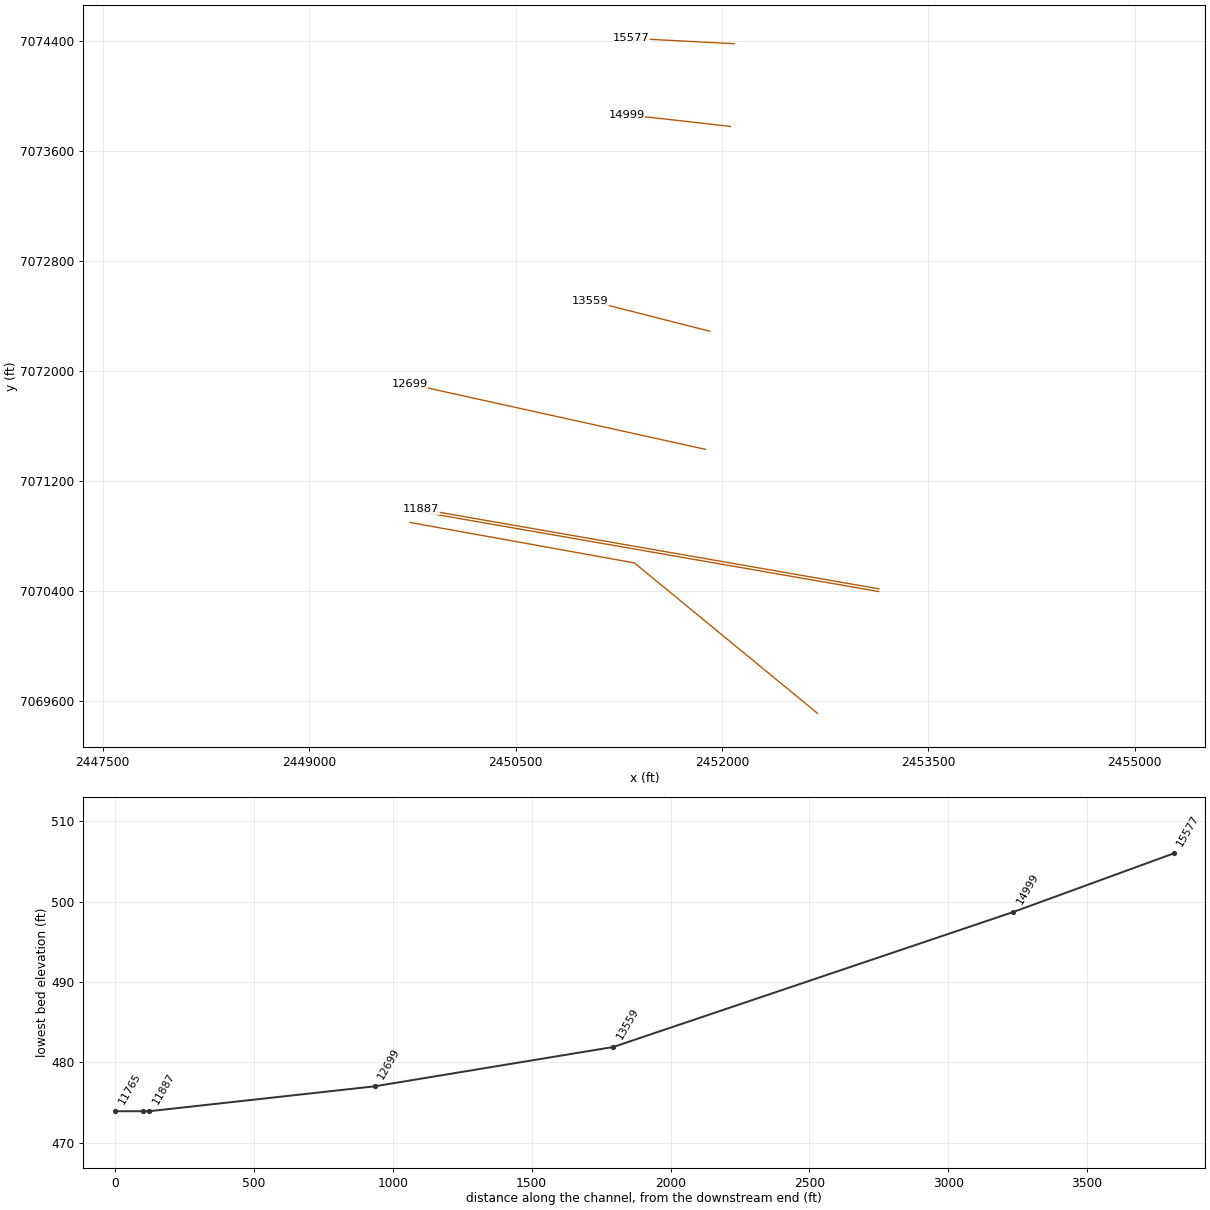
HEC-RAS study CDC_Consolidated_Model.prj: Upper Trinity CDC Consolidated Model

--- CDC_Consolidated_Model.g01 (geometry) --- (continued)

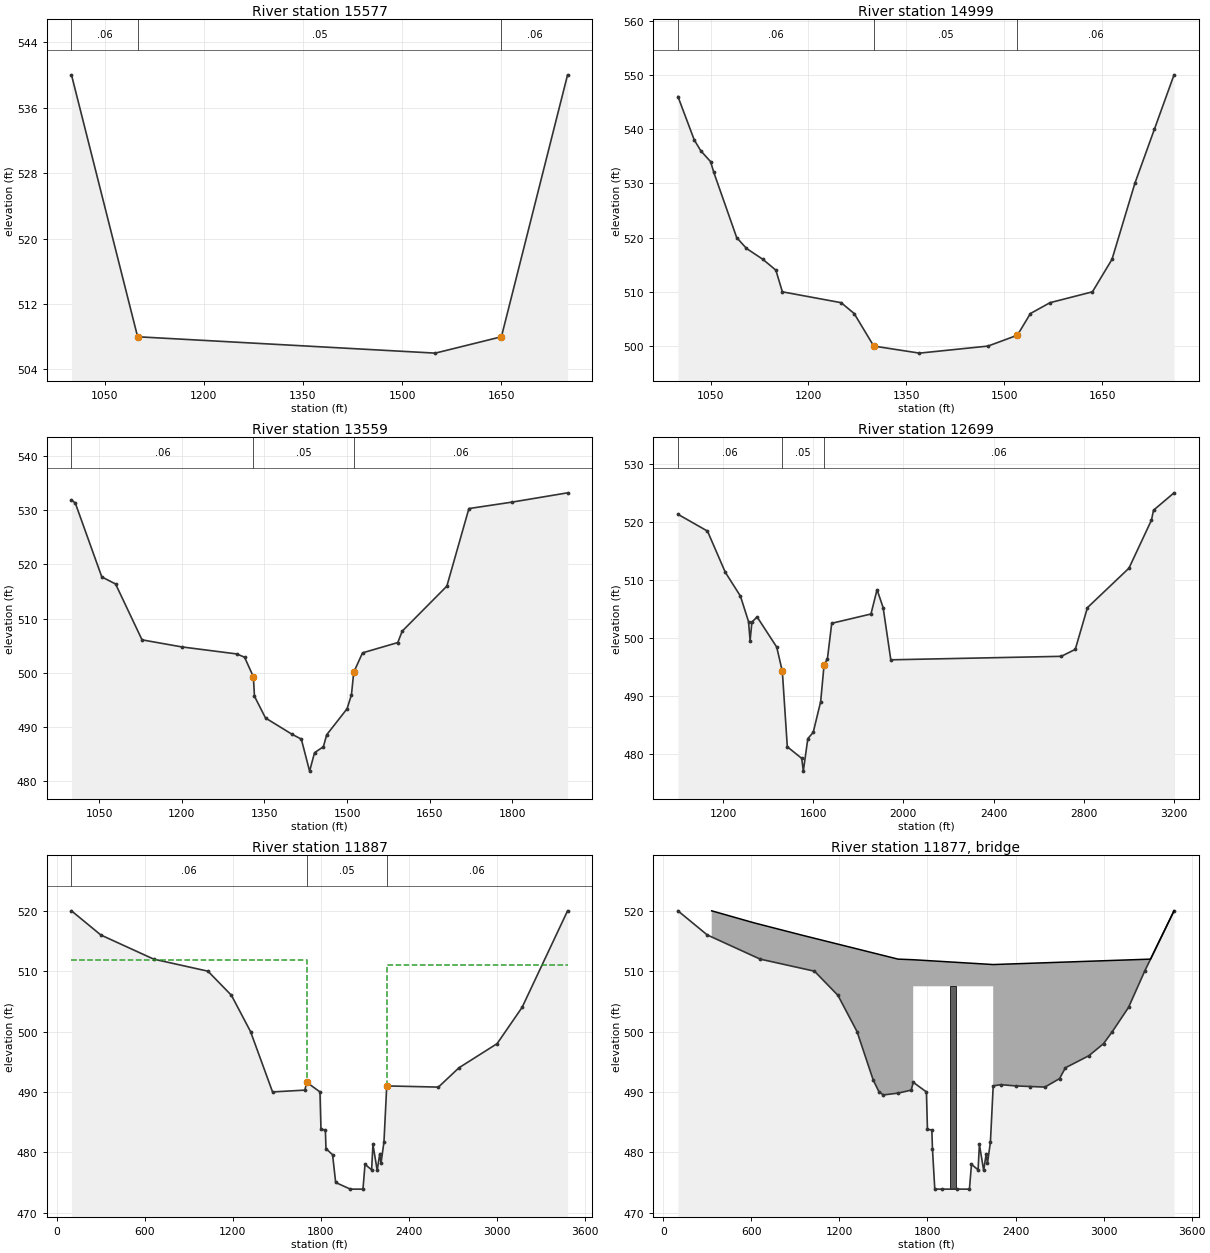
Type RM Length L Ch R = 1 ,15577   ,578,578,578
BEGIN DESCRIPTION:
This cross section corresponds to cross section 15590 of the non-georeferenced CDC model which was the source of this model.
Cross-section surveyed December 1990.
END DESCRIPTION:
XS GIS Cut Line= 4
 2452088.23102657074382.826383382452048.285240267074384.91299339
2451350.368657087074421.371581882451339.251881427074421.95228939
#Sta/Elev= 5
    1000     540    1100     508    1550     506    1650     508    1750     540
#Mann= 3 ,0,0
    1000     .06       0    1100     .05       0    1650     .06       0
Bank Sta=1100,1650
XS Rating Curve= 0 ,0
Exp/Cntr=0.3,0.1

Type RM Length L Ch R = 1 ,14999   ,1440,1440,1440
BEGIN DESCRIPTION:
This cross section corresponds to cross section 15010 of the non-georeferenced CDC model which was the source of this model.
Cross-section surveyed December 1990.
END DESCRIPTION:
XS GIS Cut Line= 2
2452061.263888847073781.360066642451306.078063257073866.76770422
#Sta/Elev= 23
    1000     546    1025     538    1035     536    1050     534    1055     532
    1090     520    1105     518    1130     516    1150     514    1160     510
    1250     508    1270     506    1300     500    1370   498.7    1475     500
    1520     502    1540     506    1570     508    1635     510    1665     516
    1700     530    1730     540    1760     550
#Mann= 3 ,0,0
    1000     .06       0    1300     .05       0    1520     .06       0
Bank Sta=1300,1520
XS Rating Curve= 0 ,0
Exp/Cntr=0.3,0.1

Type RM Length L Ch R = 1 ,13559   ,850,860,870
BEGIN DESCRIPTION:
This cross section corresponds to cross section 13580 of the non-georeferenced CDC model which was the source of this model.
Cross-section surveyed December 1990.
END DESCRIPTION:
XS GIS Cut Line= 3
2451912.20742843 7072291.41685232451863.757722177072303.77148639
2451040.115996757072513.80453089
#Sta/Elev= 27
    1000   531.9    1007   531.3    1055   517.7    1080   516.4    1128   506.1
    1200   504.8    1300   503.5    1314   502.9    1330   499.3    1332   495.7
    1352   491.7    1400   488.7    1417   487.8    1432   481.9    1441   485.3
    1457   486.4    1463   488.6    1500   493.4    1508     496    1512   500.1
    1528   503.7    1592   505.6    1600   507.7    1681     516    1721   530.3
    1800   531.5    1900   533.2
#Mann= 3 ,0,0
    1000     .06       0    1330     .05       0    1512     .06       0
Bank Sta=1330,1512
XS Rating Curve= 0 ,0
Exp/Cntr=0.3,0.1

Type RM Length L Ch R = 1 ,12699   ,802,812,822
BEGIN DESCRIPTION:
This cross section corresponds to cross section 12720 of the non-georeferenced CDC model which was the source of this model.
Cross-section surveyed December 1990.
END DESCRIPTION:
XS GIS Cut Line= 3
2451879.478491257071432.729593312451820.891666177071445.67510547
2449731.297092087071907.40482505
#Sta/Elev= 30
    1000   521.3    1131   518.4    1210   511.3    1277   507.2    1313   502.8
    1320   499.5    1328   502.7    1351   503.6    1438   498.4    1463   494.2
    1485   481.2    1549   479.2    1556     477    1576   482.6    1600   483.7
    1633     489    1648   495.3    1663   496.4    1682   502.5    1856   504.1
    1883   508.3    1910   505.2    1944   496.2    2700   496.8    2762     498
    2816   505.2    3000     512    3100   520.3    3109     522    3200     525
#Mann= 3 ,0,0
    1000     .06       0    1463     .05       0    1648     .06       0
Bank Sta=1463,1648
XS Rating Curve= 0 ,0
Exp/Cntr=0.5,0.3

Type RM Length L Ch R = 1 ,11887   ,20,20,20
BEGIN DESCRIPTION:
This cross section corresponds to cross section 11890 of the non-georeferenced CDC model which was the source of this model.
Cross-section surveyed December 1990.
END DESCRIPTION:
XS GIS Cut Line= 3
     2453141.913     7070417.875     2452811.884     7070475.371
     2449812.067     7070997.987
#Sta/Elev= 30
     100     520     300     516     660     512    1030     510    1190     506
    1320     500    1470     490    1690   490.3    1703   491.6    1793     490
    1800   483.8    1830   483.7    1834   480.6    1879   479.6    1900     475
    2000   473.9    2086   473.9    2100     478    2145   477.1    2154   481.3
    2183     477    2200   479.7    2209   478.2    2229   481.7    2248     491
    2600   490.8    2740     494    3000     498    3170     504    3480     520
#Mann= 3 ,0,0
     100     .06       0    1703     .05       0    2248     .06       0
#XS Ineff= 2 , 0
            1703   511.9    2248           511.1
Permanent Ineff=
       F       F
Bank Sta=1703,2248
XS Rating Curve= 0 ,0
Exp/Cntr=0.5,0.3

Type RM Length L Ch R = 3 ,11877   ,,,
BEGIN DESCRIPTION:
Atchinson, Topeka, and Sante Fe Railroad
END DESCRIPTION:
Node Name=ATSF Railroad
Bridge Culvert--1,0,-1,-1, 0
Deck Dist Width WeirC Skew NumUp NumDn MinLoCord MaxHiCord MaxSubmerge Is_Ogee
1,18,2.7,0, 10, 10, 511.1, , 0.95, 0, 0,0,,
     330     620     940    1600    1703    1703    2248    2248    3320    3480
     520     518     516     512   511.9   511.9   511.1   511.1     512     520
   473.9   473.9   473.9   473.9   473.9   507.5   507.5   473.9   473.9   473.9
     330     620     940    1600    1703    1703    2248    2248    3320    3480
     520     518     516     512   511.9   511.9   511.1   511.1     512     520
   473.9   473.9   473.9   473.9   473.9   507.5   507.5   473.9   473.9   473.9
Pier Skew, UpSta & Num, DnSta & Num=  ,1975.5, 2 ,1975.5, 2 , 0 , 0 , 0 ,,
      38      38
   473.9   507.5
      38      38
   473.9   507.5
Abutment Skew #Up #Dn= , 2 , 2
    1703    1898
   507.5   473.9
    1703    1898
   507.5   473.9
Abutment Skew #Up #Dn= , 2 , 2
    2053    2248
   473.9   507.5
    2053    2248
   473.9   507.5
BR Coef= 0 , 0 ,-1 ,1.05, 0 ,,,0.7905694,0,2,2,507.5
WSPro=,,,, 1 ,,,, 0 ,,,, 0 ,,,,-1 ,-1 ,-1 , 0 , 0 , 0 , 0 , 0
BR U #Sta/Elev= 40
     100     520     300     516     660     512    1030     510    1190     506
    1320     500    1430     492    1470     490    1500   489.5    1600   489.8
    1690   490.3    1703   491.6    1793     490    1800   483.8    1830   483.7
    1834   480.6    1850   473.9    1900   473.9    2000   473.9    2086   473.9
    2100     478    2145   477.1    2154   481.3    2183     477    2200   479.7
    2209   478.2    2229   481.7    2248     491    2300   491.2    2400     491
    2500   490.9    2600   490.8    2700   492.2    2740     494    2900     496
    3000     498    3060     500    3170     504    3280     510    3480     520
BR U #Mann= 3
     100     .06    1703     .05    2248     .06
BR D #Sta/Elev= 40
     100     520     300     516     660     512    1030     510    1190     506
    1320     500    1430     492    1470     490    1500   489.5    1600   489.8
    1690   490.3    1703   491.6    1793     490    1800   483.8    1830   483.7
    1834   480.6    1850   473.9    1900   473.9    2000   473.9    2086   473.9
    2100     478    2145   477.1    2154   481.3    2183     477    2200   479.7
    2209   478.2    2229   481.7    2248     491    2300   491.2    2400     491
    2500   490.9    2600   490.8    2700   492.2    2740     494    2900     496
    3000     498    3060     500    3170     504    3280     510    3480     520
BR D #Mann= 3
     100     .06    1703     .05    2248     .06
BC Design=,, 0 ,, 0 ,,,,,,
BC HTab HWMax=520
BC Use User HTab Curves=0
BC User HTab FreeFlow(D)= 0

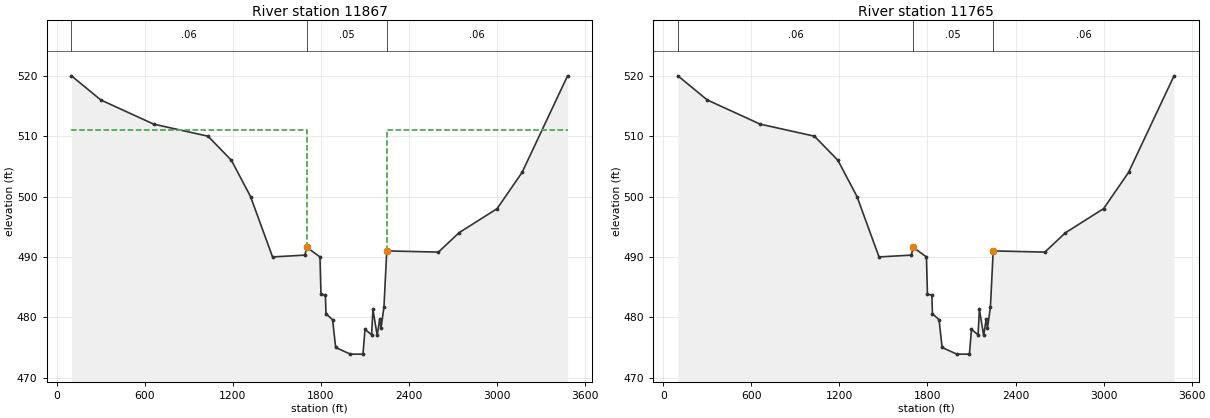
Type RM Length L Ch R = 1 ,11867   ,102,102,102
BEGIN DESCRIPTION:
This cross section corresponds to cross section 11870 of the non-georeferenced CDC model which was the source of this model.
Cross-section surveyed December 1990.
END DESCRIPTION:
XS GIS Cut Line= 3
     2453138.952     7070398.394     2452808.923      7070455.89
     2449809.107     7070978.506
#Sta/Elev= 30
     100     520     300     516     660     512    1030     510    1190     506
    1320     500    1470     490    1690   490.3    1703   491.6    1793     490
    1800   483.8    1830   483.7    1834   480.6    1879   479.6    1900     475
    2000   473.9    2086   473.9    2100     478    2145   477.1    2154   481.3
    2183     477    2200   479.7    2209   478.2    2229   481.7    2248     491
    2600   490.8    2740     494    3000     498    3170     504    3480     520
#Mann= 3 ,0,0
     100     .06       0    1703     .05       0    2248     .06       0
#XS Ineff= 2 , 0
       0    1703     511    2248       0     511
Permanent Ineff=
       F       F
Bank Sta=1703,2248
XS Rating Curve= 0 ,0
Exp/Cntr=0.5,0.3

Type RM Length L Ch R = 1 ,11765   ,1302,1262,1202
BEGIN DESCRIPTION:
This cross section corresponds to cross section 11770 of the non-georeferenced CDC model which was the source of this model.
Cross-section surveyed December 1990.
END DESCRIPTION:
XS GIS Cut Line= 4
2452694.99457675 7069512.09563932452648.642635357069550.19464447
2451363.500848687070606.511757552449733.389607587070900.72704838
#Sta/Elev= 30
     100     520     300     516     660     512    1030     510    1190     506
    1320     500    1470     490    1690   490.3    1703   491.6    1793     490
    1800   483.8    1830   483.7    1834   480.6    1879   479.6    1900     475
    2000   473.9    2086   473.9    2100     478    2145   477.1    2154   481.3
    2183     477    2200   479.7    2209   478.2    2229   481.7    2248     491
    2600   490.8    2740     494    3000     498    3170     504    3480     520
#Mann= 3 ,0,0
     100     .06       0    1703     .05       0    2248     .06       0
Bank Sta=1703,2248
XS Rating Curve= 0 ,0
Exp/Cntr=0.5,0.3