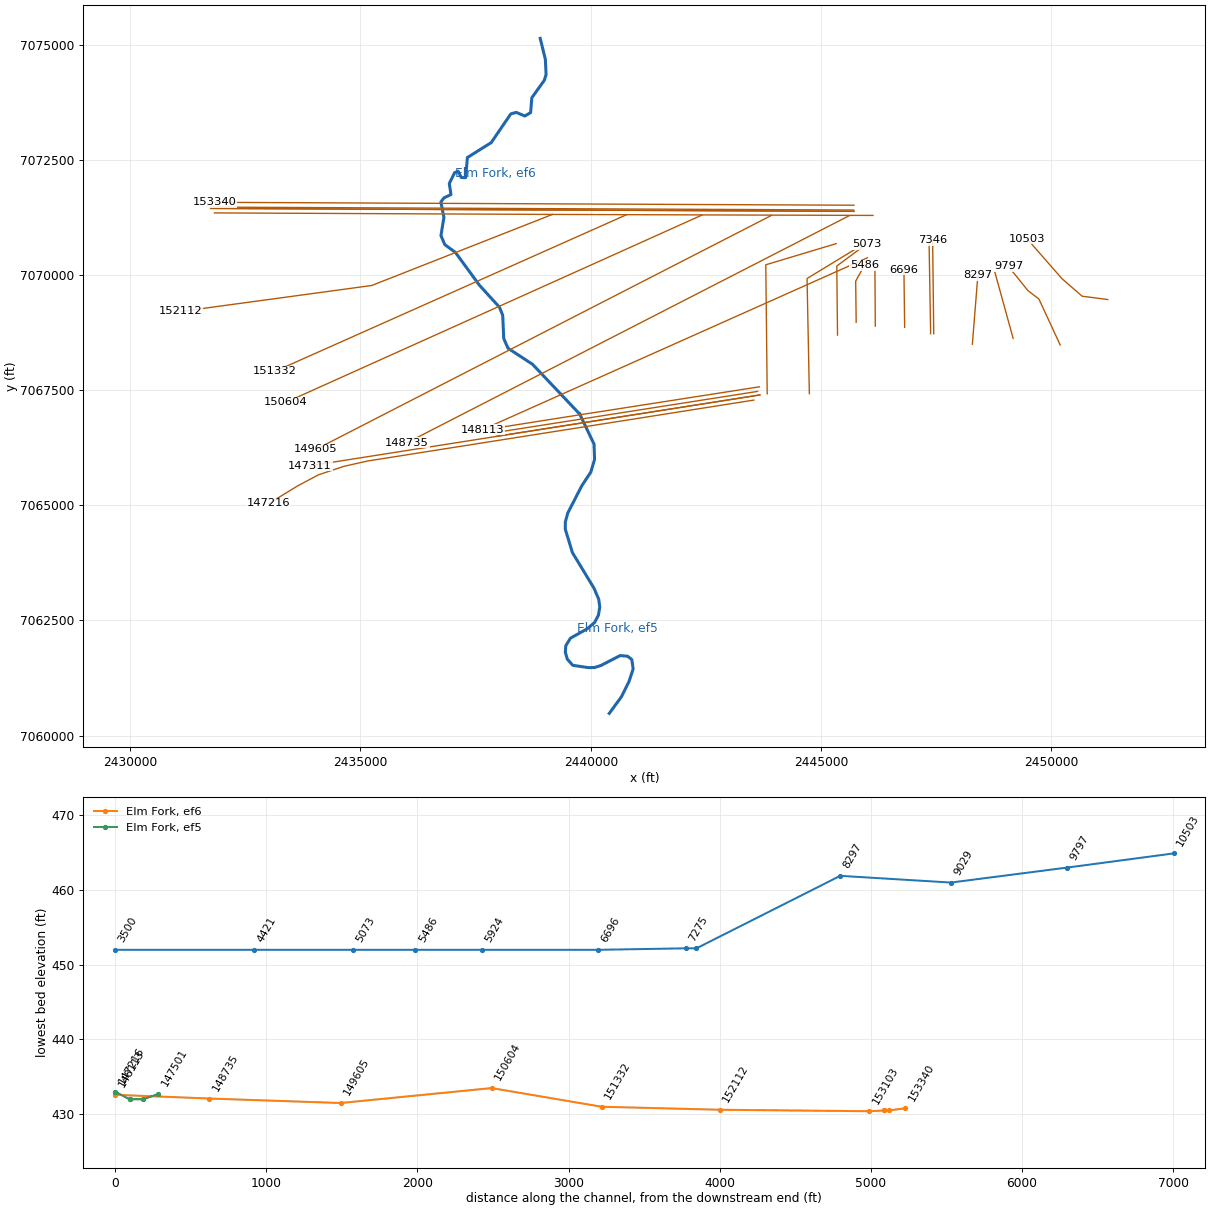
HEC-RAS study CDC_Consolidated_Model.prj: Upper Trinity CDC Consolidated Model

--- CDC_Consolidated_Model.g01 (geometry) --- (continued)

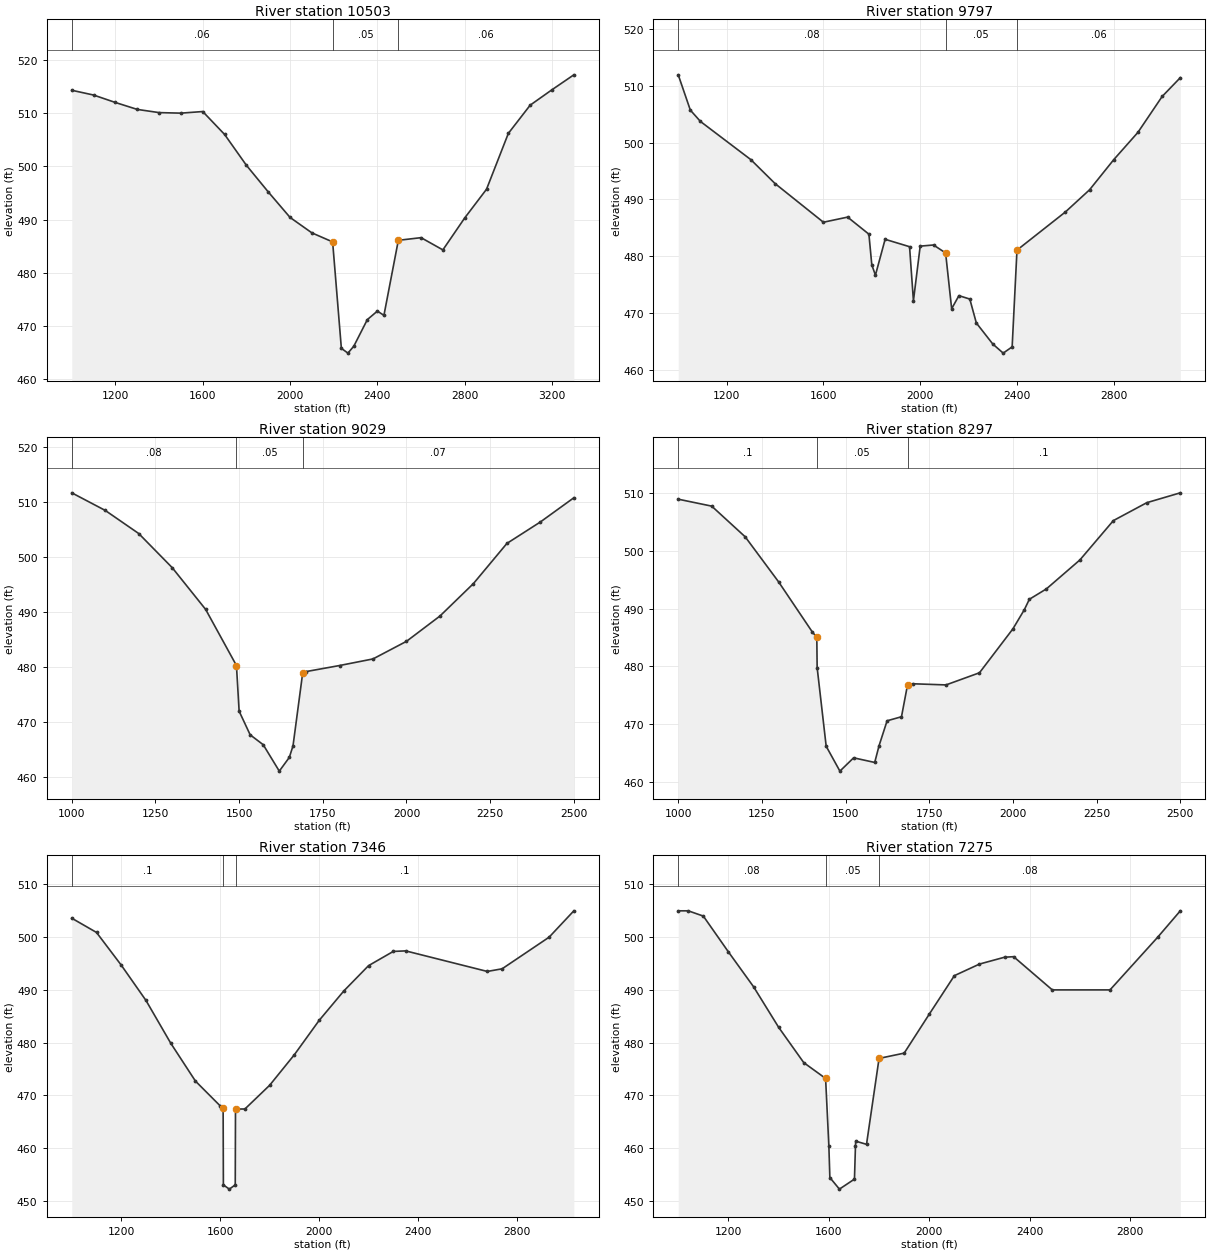
Type RM Length L Ch R = 1 ,10503   ,857,706,726
BEGIN DESCRIPTION:
This cross section corresponds to cross section 10510 of the non-georeferenced CDC model which was the source of this model.
Cross-section surveyed December 1990.
END DESCRIPTION:
XS GIS Cut Line= 5
 2451223.2524415 7069472.47367132450667.106572187069544.81768672
2450226.302663747069927.493758632449504.546889427070753.39532205
2449465.985942937070797.52056189
#Sta/Elev= 28
    1000   514.3    1100   513.4    1200     512    1300   510.7    1400   510.1
    1500     510    1600   510.3    1700     506    1800   500.2    1900   495.2
    2000   490.4    2100   487.5    2195   485.8    2235   465.8    2265   464.9
    2292   466.2    2354   471.2    2400   472.8    2430     472    2496   486.1
    2600   486.6    2700   484.3    2800   490.3    2900   495.7    3000   506.2
    3100   511.5    3200   514.4    3300   517.2
#Mann= 3 ,0,0
    1000     .06       0    2195     .05       0    2496     .06       0
Bank Sta=2195,2496
XS Rating Curve= 0 ,0
Exp/Cntr=0.3,0.1

Type RM Length L Ch R = 1 ,9797    ,887,768,493
BEGIN DESCRIPTION:
This cross section corresponds to cross section 9810 of the non-georeferenced CDC model which was the source of this model.
Cross-section surveyed December 1990.
END DESCRIPTION:
XS GIS Cut Line= 6
2450189.009431247068487.324722962450182.706622337068500.93624429
2449727.370918847069484.267939052449490.014766257069665.91783822
2449071.009042597070186.647439792449065.304329577070193.73732063
#Sta/Elev= 30
    1000   511.9    1050   505.7    1092   503.7    1300     497    1400   492.8
    1600     486    1700   486.9    1788   483.9    1800   478.5    1815   476.7
    1855     483    1956   481.7    1972   472.2    2000   481.8    2055     482
    2105   480.6    2130   470.8    2160   473.1    2205   472.5    2232   468.3
    2300   464.6    2343     463    2380   464.1    2400   481.1    2600   487.8
    2700   491.7    2800     497    2900   501.8    3000   508.1    3075   511.4
#Mann= 3 ,0,0
    1000     .08       0    2105     .05       0    2400     .06       0
Bank Sta=2105,2400
XS Rating Curve= 0 ,0
Exp/Cntr=0.3,0.1

Type RM Length L Ch R = 1 ,9029    ,802,732,552
BEGIN DESCRIPTION:
This cross section corresponds to cross section 9030 of the non-georeferenced CDC model which was the source of this model.
Cross-section surveyed December 1990.
END DESCRIPTION:
XS GIS Cut Line= 3
2449167.433390417068631.139067892449162.114831517068650.41921306
 2448768.54081557070077.12502106
#Sta/Elev= 22
    1000   511.6    1100   508.4    1200   504.2    1300     498    1400   490.4
    1492   480.2    1500   471.9    1533   467.6    1572   465.8    1620     461
    1650   463.5    1661   465.6    1690   478.9    1700   479.1    1800   480.2
    1900   481.4    2000   484.6    2100   489.2    2200   495.1    2300   502.4
    2400   506.3    2500   510.7
#Mann= 3 ,0,0
    1000     .08       0    1492     .05       0    1690     .07       0
Bank Sta=1492,1690
XS Rating Curve= 0 ,0
Exp/Cntr=0.3,0.1

Type RM Length L Ch R = 1 ,8297    ,940,951,1013
BEGIN DESCRIPTION:
This cross section corresponds to cross section 8300 of the non-georeferenced CDC model which was the source of this model.
Cross-section surveyed December 1990.
END DESCRIPTION:
XS GIS Cut Line= 3
2448282.807206937068503.407039882448402.276456187069997.66389388
2448402.353883837069998.63075547
#Sta/Elev= 26
    1000   508.9    1100   507.7    1200   502.4    1300   494.6    1400     486
    1414     485    1415   479.8    1442   466.2    1483   461.9    1524   464.2
    1587   463.4    1600   466.3    1624   470.6    1667   471.3    1685   476.8
    1700     477    1800   476.8    1900   478.9    2000   486.5    2034   489.8
    2049   491.6    2100   493.4    2200   498.4    2300   505.2    2400   508.3
    2500     510
#Mann= 3 ,0,0
    1000      .1       0    1414     .05       0    1685      .1       0
Bank Sta=1414,1685
XS Rating Curve= 0 ,0
Exp/Cntr=0.3,0.1

Type RM Length L Ch R = 1 ,7346    ,71,71,71
BEGIN DESCRIPTION:
This cross section corresponds to cross section 7380 of the non-georeferenced CDC model which was the source of this model.
Cross-section surveyed December 1990.
END DESCRIPTION:
XS GIS Cut Line= 3
2447444.033950097068729.586377552447420.596332917070755.62792914
2447420.552041687070759.44780338
#Sta/Elev= 24
    1000   503.6    1100   500.9    1200   494.7    1300     488    1400   479.9
    1500   472.7    1600     468    1612   467.5    1613     453    1637   452.2
    1661     453    1662   467.4    1700   467.4    1800   471.9    1900   477.7
    2000   484.2    2100   489.8    2200   494.6    2300   497.3    2350   497.4
    2680   493.5    2740     494    2930     500    3030     505
#Mann= 3 ,0,0
    1000      .1       0    1612     .05       0    1662      .1       0
Bank Sta=1612,1662
XS Rating Curve= 0 ,0
Exp/Cntr=0.3,0.1

Type RM Length L Ch R = 1 ,7275    ,579,579,579
BEGIN DESCRIPTION:
This cross section corresponds to cross section 7310 of the non-georeferenced CDC model which was the source of this model.
Cross-section surveyed December 1990.
END DESCRIPTION:
XS GIS Cut Line= 3
2447376.834609427068730.840640132447376.325424087068760.83631505
2447342.897013257070730.55153571
#Sta/Elev= 26
    1000     505    1040     505    1100     504    1200   497.2    1300   490.6
    1400   482.9    1500   476.2    1587   473.2    1600   460.4    1604   454.4
    1642   452.2    1702   454.1    1706   460.4    1707   461.3    1750   460.7
    1800     477    1900     478    2000   485.4    2100   492.7    2200   494.9
    2300   496.2    2336   496.3    2490     490    2720     490    2910     500
    3000     505
#Mann= 3 ,0,0
    1000     .08       0    1587     .05       0    1800     .08       0
Bank Sta=1587,1800
XS Rating Curve= 0 ,0
Exp/Cntr=0.3,0.1

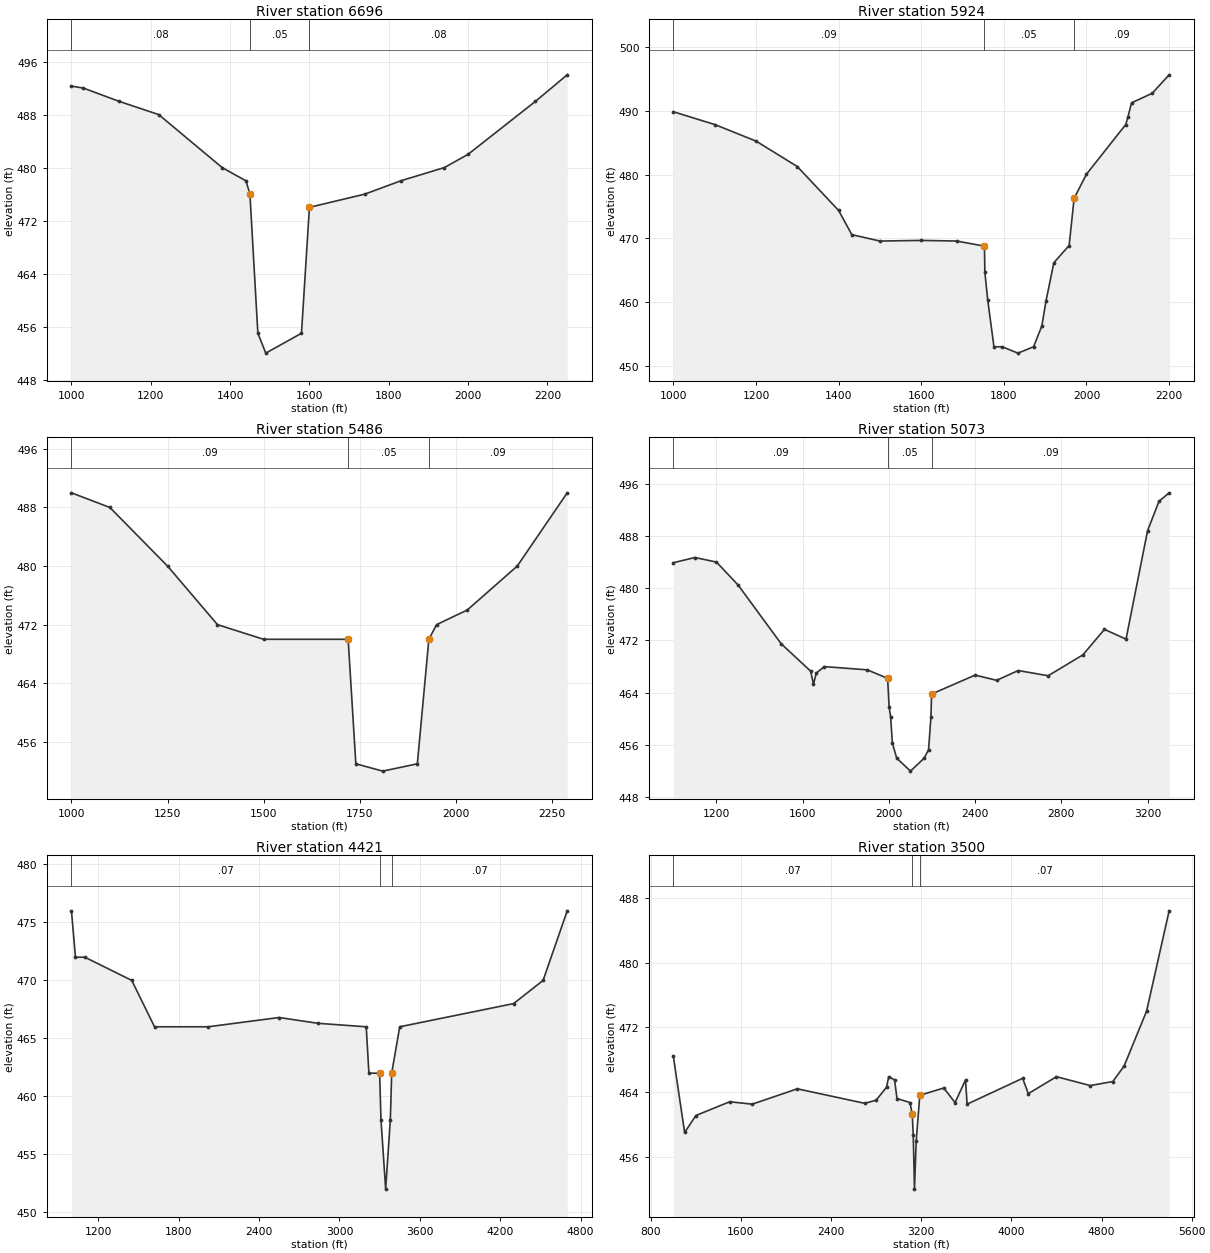
Type RM Length L Ch R = 1 ,6696    ,635,772,654
BEGIN DESCRIPTION:
This cross section corresponds to cross section 6730 of the non-georeferenced CDC model which was the source of this model.
Cross-section surveyed December 1990.
END DESCRIPTION:
XS GIS Cut Line= 3
2446812.794070847068868.818054472446797.875793587070072.74379621
2446797.305912857070118.72008222
#Sta/Elev= 17
    1000   492.3    1030     492    1120     490    1220     488    1380     480
    1440     478    1450     476    1470     455    1490     452    1580     455
    1600     474    1740     476    1830     478    1940     480    2000     482
    2170     490    2250     494
#Mann= 3 ,0,0
    1000     .08       0    1450     .05       0    1600     .08       0
Bank Sta=1450,1600
XS Rating Curve= 0 ,0
Exp/Cntr=0.3,0.1

Type RM Length L Ch R = 1 ,5924    ,418,438,358
BEGIN DESCRIPTION:
This cross section corresponds to cross section 5940 of the non-georeferenced CDC model which was the source of this model.
Cross-section surveyed December 1990.
END DESCRIPTION:
XS GIS Cut Line= 3
2446175.645082687068894.611966132446168.066357677070089.04100771
2446168.030924687070094.59086539
#Sta/Elev= 27
    1000   489.9    1100   487.9    1200   485.3    1300   481.3    1400   474.4
    1432   470.6    1500   469.6    1600   469.7    1686   469.6    1753   468.8
    1754   464.7    1761   460.3    1776     453    1796     453    1834     452
    1872     453    1892   456.3    1902   460.2    1921   466.2    1958   468.9
    1970   476.3    2000   480.1    2095   487.9    2100     489    2109   491.3
    2159   492.8    2200   495.7
#Mann= 3 ,0,0
    1000     .09       0    1753     .05       0    1970     .09       0
Bank Sta=1753,1970
XS Rating Curve= 0 ,0
Exp/Cntr=0.3,0.1

Type RM Length L Ch R = 1 ,5486    ,413,413,491
BEGIN DESCRIPTION:
This cross section corresponds to cross section 5500 of the non-georeferenced CDC model which was the source of this model.
Cross-section surveyed December 1990.
END DESCRIPTION:
XS GIS Cut Line= 5
2445760.451359247068978.989093962445759.62524542 7069048.9843608
2445749.912338357069871.806862132445924.744665837070188.17040263
2445941.992990917070219.38162629
#Sta/Elev= 14
    1000     490    1100     488    1250     480    1380     472    1500     470
    1720     470    1740     453    1810     452    1900     453    1930     470
    1950     472    2030     474    2160     480    2290     490
#Mann= 3 ,0,0
    1000     .09       0    1720     .05       0    1930     .09       0
Bank Sta=1720,1930
XS Rating Curve= 0 ,0
Exp/Cntr=0.3,0.1

Type RM Length L Ch R = 1 ,5073    ,643,652,198
BEGIN DESCRIPTION:
This cross section corresponds to cross section 5080 of the non-georeferenced CDC model which was the source of this model.
Cross-section surveyed December 1990.
END DESCRIPTION:
XS GIS Cut Line= 4
2445355.492195437068700.940437472445339.867226667070200.94039021
  2445931.0130267070638.440499472445982.850520767070676.80492406
#Sta/Elev= 30
    1000   483.9    1100   484.7    1200     484    1300   480.5    1500   471.5
    1637   467.3    1650   465.3    1663     467    1700     468    1900   467.5
    1994   466.2    2001   461.8    2008   460.3    2016   456.3    2036     454
    2100     452    2164     454    2184   455.3    2195   460.3    2198   463.8
    2400   466.7    2500   465.9    2600   467.4    2739   466.6    2900   469.8
    3000   473.7    3100   472.2    3200   488.8    3253   493.3    3300   494.6
#Mann= 3 ,0,0
    1000     .09       0    1994     .05       0    2198     .09       0
Bank Sta=1994,2198
XS Rating Curve= 0 ,0
Exp/Cntr=0.3,0.1

Type RM Length L Ch R = 1 ,4421    ,921,921,500
BEGIN DESCRIPTION:
This cross section corresponds to cross section 4420 of the non-georeferenced CDC model which was the source of this model.
Cross-section surveyed December 1990.
END DESCRIPTION:
XS GIS Cut Line= 4
2444744.335937417067427.858337972444743.030821927067492.84508464
2444694.105066757069928.996052222445717.367783997070552.69067097
#Sta/Elev= 19
    1000     476    1030     472    1100     472    1450     470    1620     466
    2020     466    2550   466.8    2840   466.3    3200     466    3220     462
    3300     462    3310     458    3345     452    3380     458    3390     462
    3450     466    4300     468    4520     470    4700     476
#Mann= 3 ,0,0
    1000     .07       0    3300     .05       0    3390     .07       0
Bank Sta=3300,3390
XS Rating Curve= 0 ,0
Exp/Cntr=0.3,0.1

Type RM Length L Ch R = 1 ,3500    ,0,0,0
BEGIN DESCRIPTION:
This cross section corresponds to cross section 3500 of the non-georeferenced CDC model which was the source of this model.
Lewisville Lake Spillway Reach
This reach represents discharge from Lewisville Lake uncontrolled spillway for rare flood events: 50 year, 100 year, 500 year. During these rare events the Lewisville Lake outlet works are closed per normal lake regulation plan for flood control.  10-year flood event not considered since no flow occurs.  Cross-section river stations from this point upstream represent distance from McWhorter Creek/Stewart Creek confluence. Cross-section surveyed December 1990.
END DESCRIPTION:
XS GIS Cut Line= 5
 2443829.15338467067423.683805632443829.021823177067435.68312547
2443828.91224334 7067445.68244932443798.415913257070227.65063864
2445326.70878842 7070687.1110058
#Sta/Elev= 30
    1000   468.4    1100     459    1200   461.1    1500   462.8    1700   462.5
    2100   464.4    2700   462.6    2800     463    2892   464.6    2911   465.9
    2963   465.5    2985   463.2    3100   462.7    3120   461.3    3129   458.7
    3140     452    3155   457.9    3187   463.6    3400   464.5    3500   462.7
    3593   465.5    3607   462.5    4100   465.7    4150   463.8    4400   465.9
    4700   464.8    4900   465.3    5000   467.2    5200     474    5400   486.4
#Mann= 3 ,0,0
    1000     .07       0    3120     .05       0    3187     .07       0
Bank Sta=3120,3187
XS Rating Curve= 0 ,0
Exp/Cntr=0.3,0.1

River Reach=Elm Fork        ,ef6
Reach XY= 30
      2438900.87      7075147.22      2439012.72      7074695.68
      2439028.98      7074361.69      2438990.53      7074235.22
      2438718.77       7073855.4      2438693.57      7073534.74
      2438568.22      7073459.89       2438383.1       7073538.6
      2438263.42       7073506.2      2437837.47       7072881.9
      2437320.02      7072557.43      2437283.59      7072120.52
      2437188.54      7072123.44      2437118.44      7072261.15
      2437042.75      7072228.18      2436927.72      7071991.37
      2436964.65      7071752.62      2436813.18       7071682.7
      2436745.65      7071591.11      2436810.76      7071256.41
      2436746.66      7070860.99      2436830.46      7070666.22
      2437062.03      7070494.61      2437584.49      7069780.49
      2438016.21       7069306.3      2438087.58       7069129.3
      2438109.78      7068625.16      2438202.12      7068414.42
      2438735.14      7068065.71      2439760.19      7066982.89

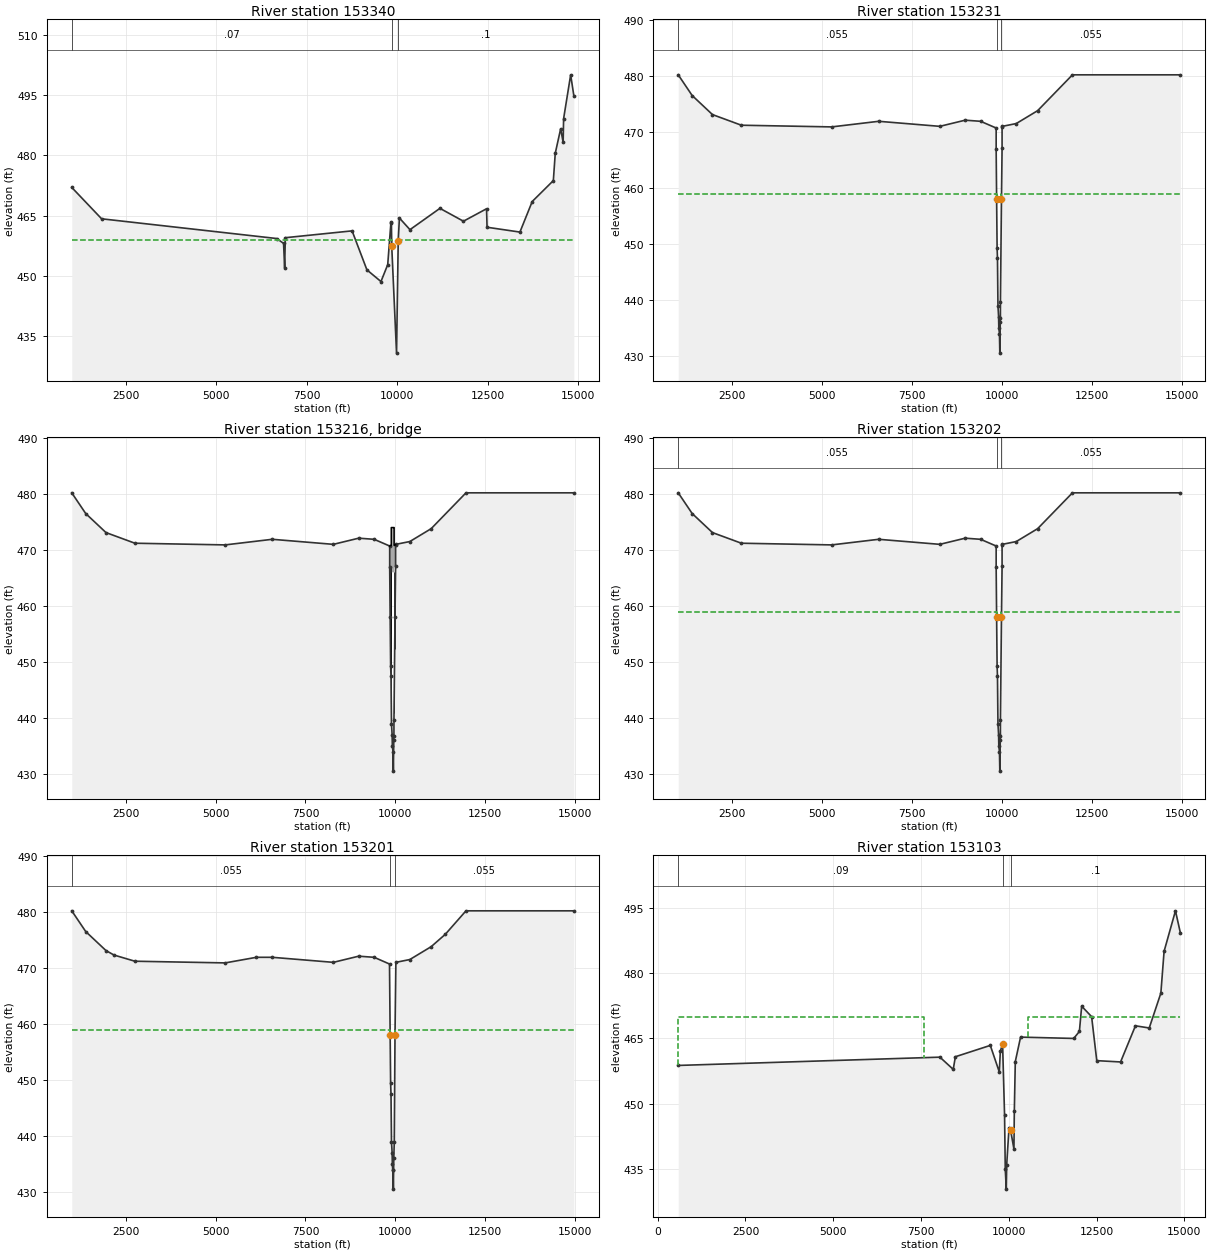
Type RM Length L Ch R = 1 ,153340  ,109,109,109
BEGIN DESCRIPTION:
This cross section corresponds to cross section 153328 of the non-georeferenced CDC model which was the source of this model.
Cross-section EF182.  108 feet upstream of Atchinson, Topeka, and Sante Fe Railroad.  Lewisville Dam at river sta 158878, river mile 30.09.  Effective flow limit set at sta 9710 in LOB, at sta 10060 in ROB. Channel data from USACOE Elm Fork channel survey.
END DESCRIPTION:
XS GIS Cut Line= 2
 2445712.8819006  7071521.728103 2431829.0248258 7071584.6895912
#Sta/Elev= 30
    1000     472    1825   464.2    6664   459.3    6857   458.1    6887     452
    6905   459.5    8752   461.2    9162   451.5    9550   448.6    9737   452.8
    9827   463.4    9839   463.1    9848   457.4    9981   430.8   10028   458.8
   10060   464.4   10352   461.5   11181   466.8   11831   463.6   12470   466.7
   12484   462.1   13393   460.9   13733   468.5   14317   473.7   14370   480.5
   14520   486.6   14588   483.2   14601   489.1   14796     500   14884   494.8
#Mann= 3 ,0,0
    1000     .07       0    9848     .05       0   10028      .1       0
#XS Ineff= 2 , 0
       0    9848     459   10028       0     459
Permanent Ineff=
       F       F
Bank Sta=9848,10028
XS Rating Curve= 0 ,0
Exp/Cntr=0.3,0.1

Type RM Length L Ch R = 1 ,153231  ,29,29,29
BEGIN DESCRIPTION:
This cross section corresponds to cross section 153221 of the non-georeferenced CDC model which was the source of this model.
END DESCRIPTION:
XS GIS Cut Line= 3
2445706.509866097071417.480936142434742.620048497071467.20065297
2431742.650895467071480.80509622
#Sta/Elev= 30
    1000   480.2    1388   476.5    1952   473.1    2756   471.2    5267   470.9
    6575   471.9    8275     471    8980   472.1    9410   471.9  9842.4   470.7
  9842.4   466.9    9855     458  9868.5  449.31    9879   447.4    9892     439
    9910     437    9916     435    9934     434    9944   430.5    9956     436
    9960   436.8    9961  439.63    9990     458 10006.8   467.1 10006.8   470.9
   10014     471   10402   471.5   10996   473.8   11964   480.2   14964   480.2
#Mann= 3 ,0,0
    1000    .055       0    9855     .05       0    9990    .055       0
#XS Ineff= 2 , 0
       0    9855     459    9990       0     459
Permanent Ineff=
       F       F
Bank Sta=9855,9990
XS Rating Curve= 0 ,0
Exp/Cntr=0.5,0.3

Type RM Length L Ch R = 3 ,153216  ,,,
BEGIN DESCRIPTION:
Atchinson, Topeka, and Santa Fe Railroad
Data from bridge plans.  Minimum low chord elev. 466.0.
END DESCRIPTION:
Node Name=ATSF Railroad
Bridge Culvert--1,0,-1,-1, 0
Deck Dist Width WeirC Skew NumUp NumDn MinLoCord MaxHiCord MaxSubmerge Is_Ogee
2,26,2.6,0, 18, 18, , , 0.95, 0, ,,,
  9842.4  9856.5  9857.5  9870.5  9871.5    9886    9886    9886    9890    9961
    9965    9966    9966  9980.5  9981.5  9994.5  9995.5 10006.8
   470.7  470.74  470.74  470.77  470.77   470.8     474     474     474     474
     474     474   470.8  470.86  470.86  470.92  470.92   470.9
  466.92  466.94  466.94  466.97  466.97     467     466     466     466     466
     466     466     467  467.03  467.03  467.06  467.06   467.1
  9842.4  9856.5  9857.5  9870.5  9871.5    9886    9886    9886    9890    9961
    9965    9966    9966  9980.5  9981.5  9994.5  9995.5 10006.8
   470.7  470.74  470.74  470.77  470.77   470.8     474     474     474     474
     474     474   470.8  470.86  470.86  470.92  470.92   470.9
  466.92  466.94  466.94  466.97  466.97     467     466     466     466     466
     466     466     467  467.03  467.03  467.06  467.06   467.1
Pier Skew, UpSta & Num, DnSta & Num=  ,9857, 2 ,9857, 2 , 0 , 0 , 0 ,,
       1       1
     435     469
       1       1
     435     469
Pier Skew, UpSta & Num, DnSta & Num=  ,9871, 2 ,9871, 2 , 0 , 0 , 0 ,,
       1       1
     435     469
       1       1
     435     469
Pier Skew, UpSta & Num, DnSta & Num=  ,9888, 2 ,9888, 2 , 0 , 0 , 0 ,,
       4       4
     435     469
       4       4
     435     469
Pier Skew, UpSta & Num, DnSta & Num=  ,9963, 2 ,9963, 2 , 0 , 0 , 0 ,,
       4       4
     435     469
       4       4
     435     469
Pier Skew, UpSta & Num, DnSta & Num=  ,9981, 2 ,9981, 2 , 0 , 0 , 0 ,,
       1       1
     435     469
       1       1
     435     469
Pier Skew, UpSta & Num, DnSta & Num=  ,9995, 2 ,9995, 2 , 0 , 0 , 0 ,,
       1       1
     435     469
       1       1
     435     469
BR Coef= 1 , 0 , 0 ,1.05, 0 ,,,0.8,-1,0.5,1,
WSPro=,,,, 1 ,,,, 0 ,,,, 0 ,,,,-1 ,-1 ,-1 , 0 , 0 , 0 , 0 , 0
BC Design=,, 0 ,, 0 ,,,,,,
BC HTab HWMax=480.2
BC Use User HTab Curves=0
BC User HTab FreeFlow(D)= 0

Type RM Length L Ch R = 1 ,153202  ,1,1,1
BEGIN DESCRIPTION:
This cross section corresponds to cross section 153192 of the non-georeferenced CDC model which was the source of this model.
END DESCRIPTION:
XS GIS Cut Line= 3
2445717.119424917071389.170953382434753.231903917071438.89067021
2431753.262750897071452.49511631
#Sta/Elev= 30
    1000   480.2    1388   476.5    1952   473.1    2756   471.2    5267   470.9
    6575   471.9    8275     471    8980   472.1    9410   471.9  9842.4   470.7
  9842.4   466.9    9855     458  9868.5  449.31    9879   447.4    9892     439
    9910     437    9916     435    9934     434    9944   430.5    9956     436
    9960   436.8    9961  439.63    9990     458 10006.8   467.1 10006.8   470.9
   10014     471   10402   471.5   10996   473.8   11964   480.2   14964   480.2
#Mann= 3 ,0,0
    1000    .055       0    9855     .05       0    9990    .055       0
#XS Ineff= 2 , 0
       0    9855     459    9990       0     459
Permanent Ineff=
       F       F
Bank Sta=9855,9990
XS Rating Curve= 0 ,0
Exp/Cntr=0.5,0.3

Type RM Length L Ch R = 1 ,153201  ,98,98,98
BEGIN DESCRIPTION:
This cross section corresponds to cross section 153191 of the non-georeferenced CDC model which was the source of this model.
One-foot downstream of Atchinson, Topeka, and Sante Fe Railroad.  Duplication of following bridge cross-section (153192) without bridge piers.
Channel data from USACOE Elm Fork channel survey.
END DESCRIPTION:
XS GIS Cut Line= 3
2445709.209663847071388.232635052434745.31754968 7071437.9520238
2431745.348396237071451.55637443
#Sta/Elev= 30
    1000   480.2    1388   476.5    1952   473.1    2176   472.3    2756   471.2
    5267   470.9    6136   471.9    6575   471.9    8275     471    8980   472.1
    9410   471.9    9837   470.7    9855     458    9868   449.4    9879   447.4
    9892     439    9910     437    9916     435    9926     434    9934     434
    9944   430.5    9956     436    9970     439    9990     458   10014     471
   10402   471.5   10996   473.8   11388     476   11964   480.2   14964   480.2
#Mann= 3 ,0,0
    1000    .055       0    9855     .05       0    9990    .055       0
#XS Ineff= 2 , 0
       0    9855     459    9990       0     459
Permanent Ineff=
       F       F
Bank Sta=9855,9990
XS Rating Curve= 0 ,0
Exp/Cntr=0.3,0.1

Type RM Length L Ch R = 1 ,153103  ,849,991,1049
BEGIN DESCRIPTION:
This cross section corresponds to cross section 153092 of the non-georeferenced CDC model which was the source of this model.
Cross-section EF180.  100 feet downstream of Atchinson, Topeka, and Sante Fe Road.  At Elm Fork/Prairie Creek confluence. Channel data from USACOE Elm Fork channel survey - cross-section EF#6 surveyed March 1983.
END DESCRIPTION:
XS GIS Cut Line= 3
  2446125.834582 7071299.8535518 2439125.9065575 7071321.5969416
 2431827.9818489 7071354.6916916
#Sta/Elev= 30
     586   458.8    8038   460.7    8417   457.9    8479   460.8    9473   463.4
    9729   457.3    9759   462.1    9823   463.7    9879   447.4    9899     435
    9928   430.4    9940     436   10006   444.5   10052   443.9   10146   439.6
   10157   448.3   10185   459.7   10335   465.3   11848     465   12010   466.6
   12075   472.4   12358     470   12505   459.9   13183   459.6   13606   467.9
   13999   467.4   14330   475.4   14422     485   14746   494.3   14884   489.3
#Mann= 3 ,0,0
     586     .09       0    9823     .05       0   10052      .1       0
#XS Ineff= 3 ,-1
     586    7586     470    7586    9823     459   10552   14884     470
Permanent Ineff=
       F       F       F
Bank Sta=9823,10052
XS Rating Curve= 0 ,0
Exp/Cntr=0.3,0.1

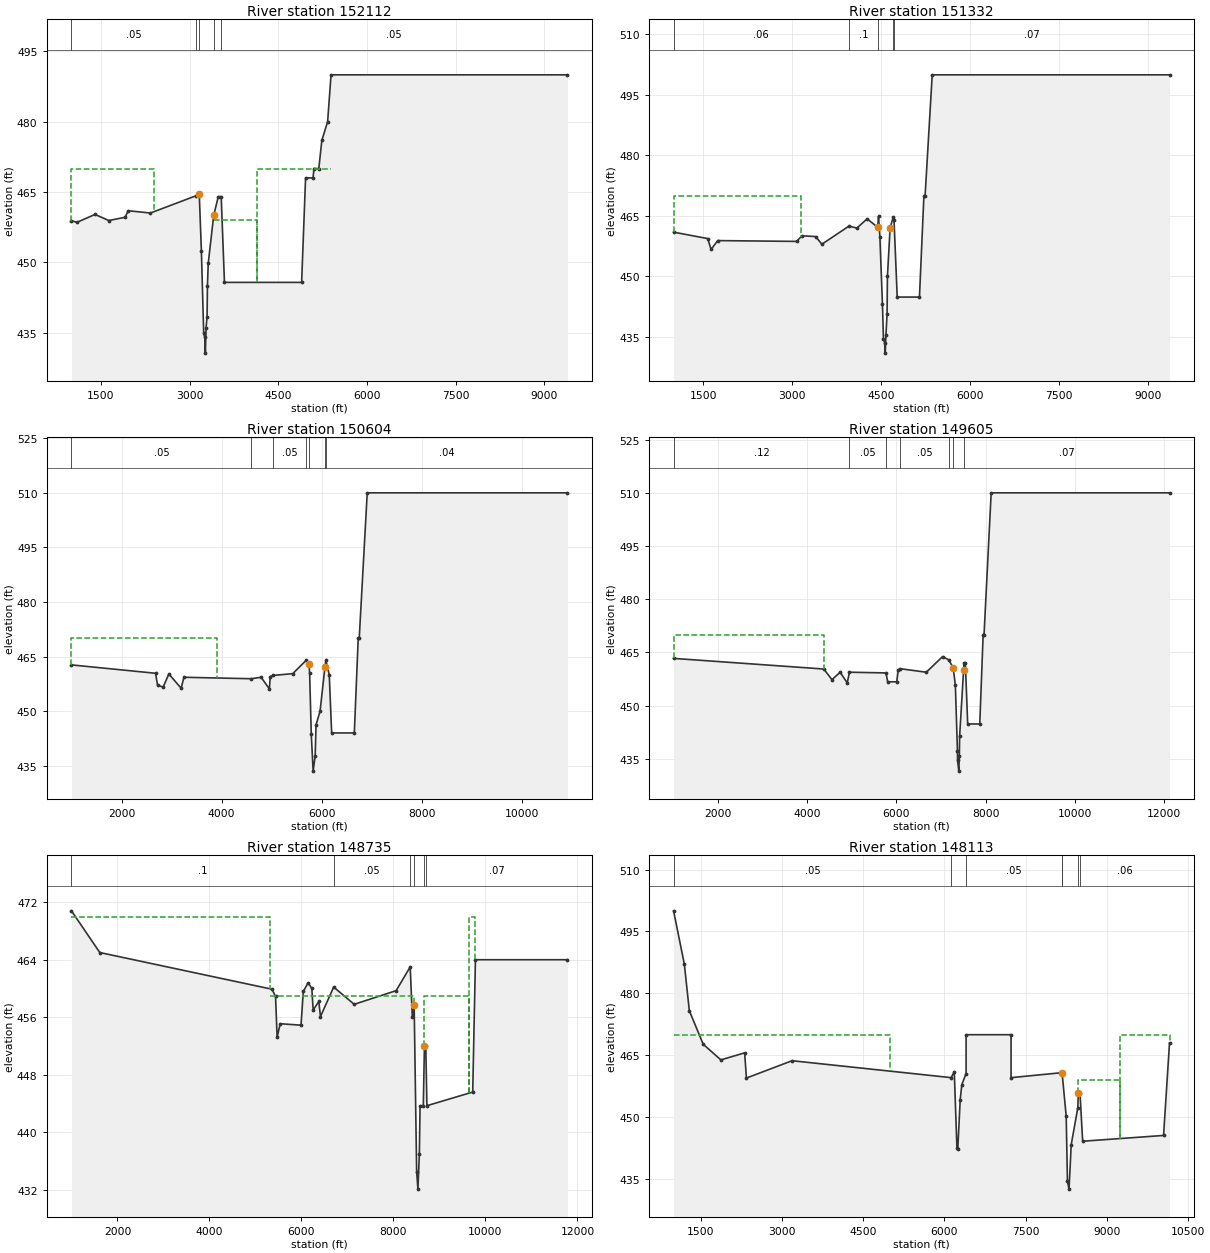
Type RM Length L Ch R = 1 ,152112  ,850,780,1050
BEGIN DESCRIPTION:
This cross section corresponds to cross section 152100 of the non-georeferenced CDC model which was the source of this model.
Cross-section EF179.  Effective flow limit set at sta 2400 in LOB, at sta 4140 in ROB.  Riverpark project in ROB.
Channel data from NDM Elm Fork channel survey.
END DESCRIPTION:
XS GIS Cut Line= 4
2439165.977999667071321.415183382435243.193850527069777.64103997
2435067.435999937069753.726717712431103.95652817 7069214.4397098
#Sta/Elev= 30
    1000   458.9    1089   458.5    1399   460.2    1632   458.9    1909   459.6
    1959     461    2335   460.5    3111   464.2    3163   464.5    3199   452.3
    3238   434.8    3256     434    3266   430.6    3278     436    3295   438.4
    3301     445    3315   449.8    3407     460    3485     464    3534     464
    3589   445.7    4895   445.7    4962     468    5088     468    5104     470
    5186     470    5237     476    5335     480    5393     490    9393     490
#Mann= 5 ,-1,0
    1000     .05       0    3111     .09       0    3163     .05       0
    3407     .09       0    3534     .05       0
#XS Ineff= 4 ,-1
    2400    3163     459    3407    4140     459    4140    5393     470
    1000    2400     470
Permanent Ineff=
       F       F       F       F
Bank Sta=3163,3407
XS Rating Curve= 0 ,0
Exp/Cntr=0.3,0.1

Type RM Length L Ch R = 1 ,151332  ,700,728,700
BEGIN DESCRIPTION:
This cross section corresponds to cross section 151320 of the non-georeferenced CDC model which was the source of this model.
END DESCRIPTION:
XS GIS Cut Line= 3
 2440772.67885457071314.129108712436790.555257087069538.65989064
 2433137.23078757067909.78901793
#Sta/Elev= 30
    1000     461    1575   459.4    1633   456.7    1744   458.9    3075   458.7
    3164   460.1    3395   459.9    3500     458    3957   462.5    4090     462
    4263   464.3    4440   462.2    4455   464.9    4478   459.8    4521   443.1
    4538   434.6    4558   433.6    4568     431    4580   435.5    4599   440.7
    4605     450    4650     462    4704   464.8    4716     464    4770   444.9
    5145   444.9    5220     470    5240     470    5360     500    9360     500
#Mann= 5 ,-1,0
    1000     .06       0    3957      .1       0    4440     .05       0
    4704     .09       0    4716     .07       0
#XS Ineff= 3 ,-1
    1000    3150     470    3150    4440     459    4650    5360     459
Permanent Ineff=
       F       F       F
Bank Sta=4440,4650
XS Rating Curve= 0 ,0
Exp/Cntr=0.3,0.1

Type RM Length L Ch R = 1 ,150604  ,901,999,991
BEGIN DESCRIPTION:
This cross section corresponds to cross section 150592 of the non-georeferenced CDC model which was the source of this model.
END DESCRIPTION:
XS GIS Cut Line= 3
2442410.498085417071306.700973972437021.811684347068879.73601164
2433374.646610477067237.12013324
#Sta/Elev= 30
    1000   462.7    2680   460.4    2721   457.1    2832   456.6    2946   460.2
    3191   456.3    3248   459.3    4594   458.9    4789   459.3    4955   456.1
    4972   459.5    5029   459.8    5422   460.3    5693     464    5747     463
    5759   460.5    5792   443.6    5829   433.5    5870   437.7    5887   446.2
    5968     450    6064     462    6083     464    6151     460    6199     444
    6652     444    6730     470    6750     470    6910     510   10910     510
#Mann= 7 ,-1,0
    1000     .05       0    4594     .07       0    5029     .05       0
    5693     .09       0    5747     .05       0    6064     .08       0
    6083     .04       0
#XS Ineff= 3 ,-1
    1000    3900     470    3900    5747     459    6064    6910     459
Permanent Ineff=
       F       F       F
Bank Sta=5747,6064
XS Rating Curve= 0 ,0
Exp/Cntr=0.3,0.1

Type RM Length L Ch R = 1 ,149605  ,779,870,779
BEGIN DESCRIPTION:
This cross section corresponds to cross section 149594 of the non-georeferenced CDC model which was the source of this model.
END DESCRIPTION:
XS GIS Cut Line= 3
2443919.972100597071299.856171382437583.829917257068043.37416729
2434026.198034917066214.91706093
#Sta/Elev= 30
    1000   463.3    4369   460.3    4553   457.3    4736   459.4    4895   456.4
    4946   459.4    5766   459.2    5802   456.7    6005   456.7    6039   459.9
    6077   460.4    6669   459.4    7034   463.8    7172   462.9    7273   460.6
    7321   455.7    7367   437.3    7370   434.5    7398   431.5    7410   435.7
    7416   441.3    7505     460    7515     462    7545     462    7597   444.8
    7868   444.8    7944     470    7964     470    8124     510   12124     510
#Mann= 7 ,-1,0
    1000     .12       0    4946     .05       0    5766     .08       0
    6077     .05       0    7172     .09       0    7273     .05       0
    7505     .07       0
#XS Ineff= 3 ,-1
    1000    4370     470    4370    7273     459    7505    8124     459
Permanent Ineff=
       F       F       F
Bank Sta=7273,7505
XS Rating Curve= 0 ,0
Exp/Cntr=0.3,0.1

Type RM Length L Ch R = 1 ,148735  ,750,622,570
BEGIN DESCRIPTION:
This cross section corresponds to cross section 148723 of the non-georeferenced CDC model which was the source of this model.
END DESCRIPTION:
XS GIS Cut Line= 3
2445605.16886142 7071292.21412632437792.88658574 7067278.5705788
2436013.93126713 7066364.6132634
#Sta/Elev= 30
    1000   470.8    1616     465    5359   459.9    5437   458.9    5472   453.2
    5538   455.1    5991   454.9    6041   459.6    6146   460.8    6226     460
    6255     457    6377   458.2    6414   456.1    6701   460.2    7147   457.8
    8059   459.7    8365     463    8411     456    8451   457.7    8505   434.5
    8533   432.1    8564     437    8579   443.7    8650   443.7    8674     452
    8704     452    8728   443.7    9724   445.6    9783     464   11783     464
#Mann= 6 ,-1,0
    1000      .1       0    6701     .05       0    8365     .09       0
    8451     .05       0    8674     .09       0    8704     .07       0
#XS Ineff= 4 ,-1
    5320    8451     459    8674    9650     459    9650    9783     470
    1000    5320     470
Permanent Ineff=
       F       F       F       F
Bank Sta=8451,8674
XS Rating Curve= 0 ,0
Exp/Cntr=0.3,0.1

Type RM Length L Ch R = 1 ,148113  ,0,0,0
BEGIN DESCRIPTION:
This cross section corresponds to cross section 148101 of the non-georeferenced CDC model which was the source of this model.
------------------------------------
CDC LEW012804-01 Lewisville Landfill
Cross-section 148101 - 152100
Located in LOB.
------------------------------------
EF u/s of Stewart Creek. The 2, 5, 10, 25-year discharges are discharge-frequency releases from Lewisville Lake and are considered critical discharges as they exceed the local discharges.  7000 cfs is released from the Lewisville Lake outlet per normal lake regulation plan for flood control. During the 50-year and 100-year flood events,the outlet works is closed, therefore a nominal discharge of 1 cfs is used.
END DESCRIPTION:
XS GIS Cut Line= 2
2446002.700874757070379.352106882437644.630648677066643.48753138
#Sta/Elev= 30
    1000     500    1199   487.1    1291   475.8    1547   467.7    1873   463.9
    2312   465.6    2345   459.5    3187   463.7    6123   459.6    6182     461
    6231   442.5    6247   442.4    6291   454.2    6321   457.9    6400   460.6
    6400     470    7230     470    7230   459.6    8165   460.8    8172   460.8
    8248   450.2    8271   434.5    8300   432.6    8341   443.4    8462   452.3
    8473     456    8502     456    8552   444.2   10045   445.6   10155     468
#Mann= 7 ,-1,0
    1000     .05       0    6123     .12       0    6400     .05       0
    8165     .09       0    8172     .04       0    8473     .08       0
    8502     .06       0
#XS Ineff= 4 ,-1
    5000    8172     459    8473    9250     459    9250   10155     470
    1000    5000     470
Permanent Ineff=
       F       F       F       F
Bank Sta=8172,8473
XS Rating Curve= 0 ,0
Exp/Cntr=0.3,0.1

River Reach=Elm Fork        ,ef5
Reach XY= 30
      2439760.19      7066982.89       2440070.1      7066331.29
      2440081.26       7065998.9       2439999.6      7065722.59
      2439807.97      7065433.87      2439498.65      7064832.26
      2439446.53      7064639.71      2439447.03      7064479.92
      2439599.85      7063975.96      2440069.73      7063200.98
      2440172.81      7062957.74      2440193.97      7062791.14
       2440165.5      7062617.14      2440083.72      7062458.84
      2439922.97        7062320.      2439557.08      7062114.87
      2439456.28      7061950.22       2439446.5      7061811.99
      2439489.79      7061659.83      2439608.05      7061525.81
      2439951.53      7061475.85      2440082.51      7061478.57
      2440219.71      7061522.72      2440636.29      7061737.72
      2440798.38        7061724.      2440890.21      7061651.06
      2440919.48      7061448.08       2440828.3      7061172.42
      2440666.25      7060845.77      2440400.92      7060482.14

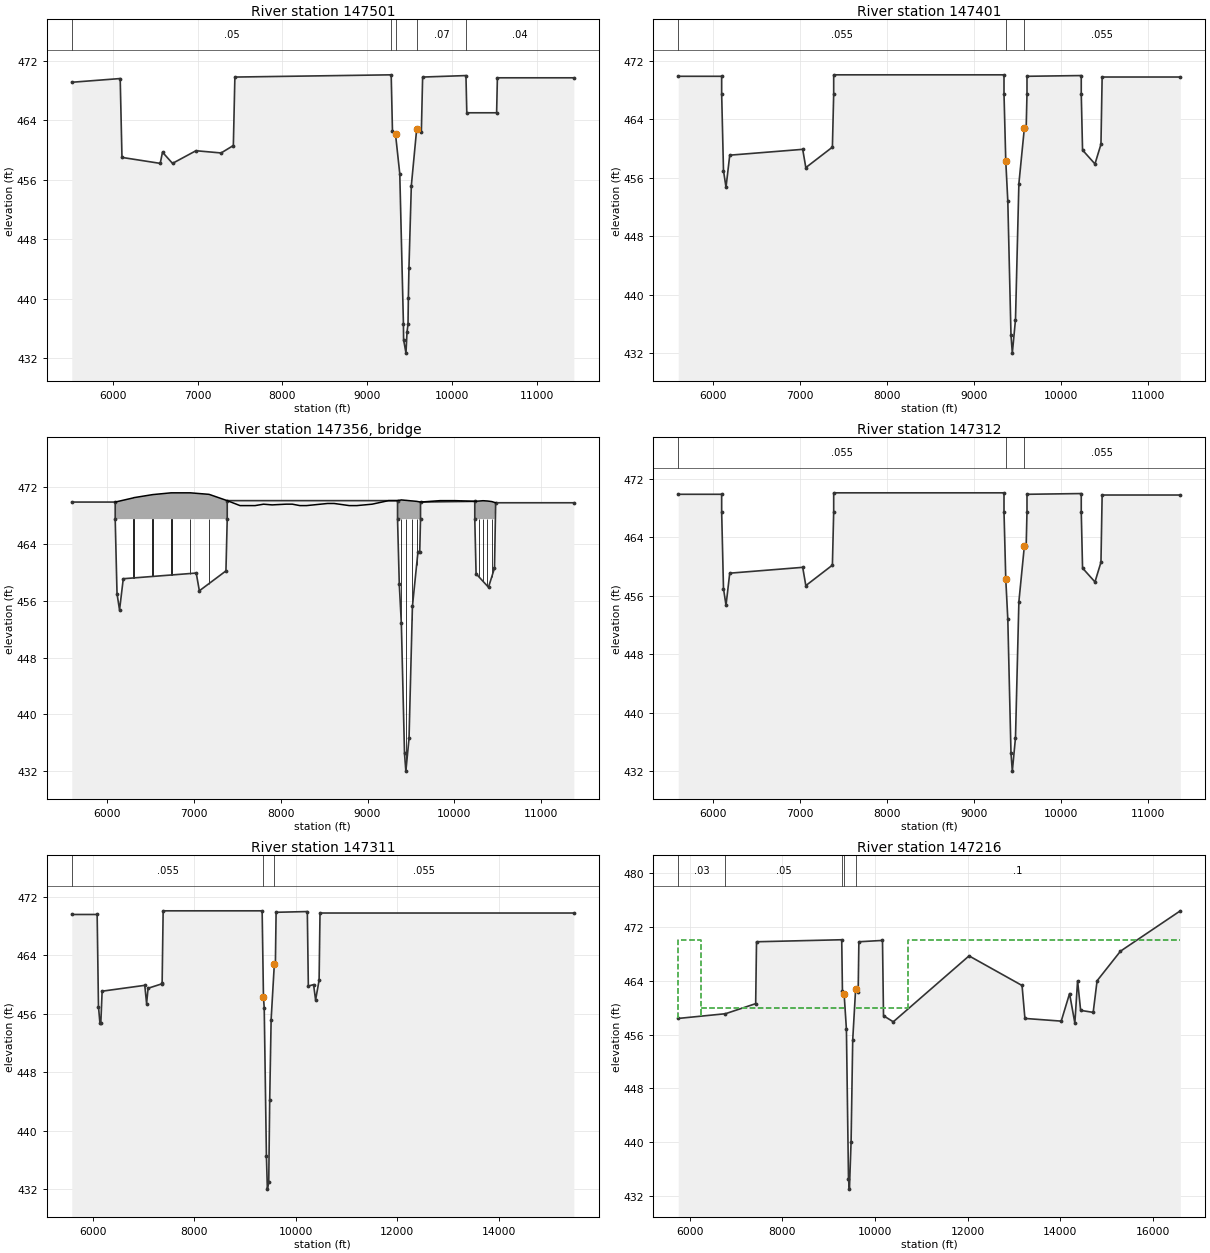
Type RM Length L Ch R = 1 ,147501  ,100,100,100
BEGIN DESCRIPTION:
This cross section corresponds to cross section 147489 of the non-georeferenced CDC model which was the source of this model.
Cross-section EF173.  100 feet upstream of SH 121.  Effective flow limit set at sta 6020 in LOB, at sta 10530 in ROB.  Ineffective flow from sta 7440 - 9280, sta 9835 - 10160 due to bridge openings.  Approx. 50 feet  downstream of left bank of McWhorter Creek.
Channel data from NDM Elm Fork channel survey.
END DESCRIPTION:
XS GIS Cut Line= 5
2443660.585755317067576.688206852443166.565470937067499.59113413
2439376.452972417066908.104128142438710.714802597066802.82415497
2437821.761775897066662.24493773
#Sta/Elev= 30
    5520   469.1    6090   469.6    6111     459    6561   458.2    6588   459.7
    6706   458.2    6982   459.9    7278   459.6    7422   460.6    7440   469.8
    9280   470.1    9295   462.5    9331   462.1    9381   456.8    9424   436.6
    9426   434.5    9454   432.7    9466   435.5    9478   436.6    9482   440.1
    9489   444.2    9517   455.2    9580   462.8    9635   462.4    9650   469.8
   10160     470   10170     465   10521     465   10530   469.7   11430   469.7
#Mann= 5 ,-1,0
    5520     .05       0    9280     .09       0    9331     .05       0
    9580     .07       0   10160     .04       0
Bank Sta=9331,9580
XS Rating Curve= 0 ,0
Exp/Cntr=0.3,0.1

Type RM Length L Ch R = 1 ,147401  ,89,89,89
BEGIN DESCRIPTION:
This cross section corresponds to cross section 147390 of the non-georeferenced CDC model which was the source of this model.
END DESCRIPTION:
XS GIS Cut Line= 4
2443619.449423847067476.809938342443125.501576667067399.25012746
2438797.923617667066719.732785722437908.817492737066580.12512613
#Sta/Elev= 30
    5595   469.9    6095   469.9    6095  467.49    6116     457    6145   454.7
    6188   459.1    7028   459.9    7064   457.4    7370   460.2  7384.8   467.5
  7384.8   470.1  9345.7   470.1  9345.7   467.5    9366   458.3  9389.5  452.81
    9426   434.5  9441.5     432    9478   436.6    9517   455.2    9580   462.8
    9601   462.8  9610.3   467.5  9610.3   469.9 10235.1     470 10235.1  467.49
   10250   459.8   10393   457.9   10462   460.6 10475.6   469.8 11375.6   469.8
#Mann= 3 ,0,0
    5595    .055       0    9366     .05       0    9580    .055       0
Bank Sta=9366,9580
XS Rating Curve= 0 ,0
Exp/Cntr=0.5,0.3

Type RM Length L Ch R = 3 ,147356  ,,,
BEGIN DESCRIPTION:
SH 121
END DESCRIPTION:
Node Name=SH 121
Bridge Culvert--1,0,-1,-1, 0
Deck Dist Width WeirC Skew NumUp NumDn MinLoCord MaxHiCord MaxSubmerge Is_Ogee
2,86,2.6,0, 54, 54, , , 0.95, 0, ,,,
    6095    6095  6304.5  6309.5  6521.5  6526.5  6738.5  6743.5  6955.5  6960.5
  7172.5  7177.5  7384.8  7384.8    7532    7705    7803    7901    8061    8135
    8221    8298    8540    8616    8790    8876    9053    9242  9345.7  9345.7
  9389.5  9390.5  9441.5  9444.5    9478  9511.5  9514.5  9564.5  9565.5  9610.3
  9610.3    9835   10010 10235.1 10279.5 10280.5 10329.5 10330.5 10379.5 10380.5
 10429.5 10430.5 10475.6 10475.6
   469.9   469.9  470.49  470.52  470.94  470.95   471.2   471.2   471.2   471.2
  470.99  470.98   470.1   470.1   469.4   469.4   469.6   469.5   469.6   469.6
   469.4   469.4   469.7   469.7   469.4   469.4   469.6   470.1   470.1   470.1
   470.2   470.2  470.14  470.14   470.1  470.06  470.06     470     470   469.9
   469.9   470.1   470.1     470  470.04  470.04  470.09  470.09  470.05  470.05
  469.97  469.97   469.8   469.8
   469.9  467.49   467.5   467.5   467.5   467.5   467.5   467.5   467.5   467.5
   467.5   467.5   467.5   470.1   469.4   469.4   469.6   469.5   469.6   469.6
   469.4   469.4   469.7   469.7   469.4   469.4   469.6   470.1   470.1   467.5
   467.5   467.5   467.5   467.5   467.5   467.5   467.5   467.5   467.5   467.5
   469.9   470.1   470.1  467.49   467.5   467.5   467.5   467.5   467.5   467.5
   467.5   467.5   467.5   469.8
    6095    6095  6304.5  6309.5  6521.5  6526.5  6738.5  6743.5  6955.5  6960.5
  7172.5  7177.5  7384.8  7384.8    7532    7705    7803    7901    8061    8135
    8221    8298    8540    8616    8790    8876    9053    9242  9345.7  9345.7
  9389.5  9390.5  9441.5  9444.5    9478  9511.5  9514.5  9564.5  9565.5  9610.3
  9610.3    9835   10010 10235.1 10279.5 10280.5 10329.5 10330.5 10379.5 10380.5
 10429.5 10430.5 10475.6 10475.6
   469.9   469.9  470.49  470.52  470.94  470.95   471.2   471.2   471.2   471.2
  470.99  470.98   470.1   470.1   469.4   469.4   469.6   469.5   469.6   469.6
   469.4   469.4   469.7   469.7   469.4   469.4   469.6   470.1   470.1   470.1
   470.2   470.2  470.14  470.14   470.1  470.06  470.06     470     470   469.9
   469.9   470.1   470.1     470  470.04  470.04  470.09  470.09  470.05  470.05
  469.97  469.97   469.8   469.8
   469.9  467.49   467.5   467.5   467.5   467.5   467.5   467.5   467.5   467.5
   467.5   467.5   467.5   470.1   469.4   469.4   469.6   469.5   469.6   469.6
   469.4   469.4   469.7   469.7   469.4   469.4   469.6   470.1   470.1   467.5
   467.5   467.5   467.5   467.5   467.5   467.5   467.5   467.5   467.5   467.5
   469.9   470.1   470.1  467.49   467.5   467.5   467.5   467.5   467.5   467.5
   467.5   467.5   467.5   469.8
Pier Skew, UpSta & Num, DnSta & Num=  ,6307, 2 ,6307, 2 , 0 , 0 , 0 ,,
       5       5
     455     468
       5       5
     455     468
Pier Skew, UpSta & Num, DnSta & Num=  ,6524, 2 ,6524, 2 , 0 , 0 , 0 ,,
       5       5
     455     468
       5       5
     455     468
Pier Skew, UpSta & Num, DnSta & Num=  ,6741, 2 ,6741, 2 , 0 , 0 , 0 ,,
       5       5
     455     468
       5       5
     455     468
Pier Skew, UpSta & Num, DnSta & Num=  ,6958, 2 ,6958, 2 , 0 , 0 , 0 ,,
       5       5
     455     468
       5       5
     455     468
Pier Skew, UpSta & Num, DnSta & Num=  ,7175, 2 ,7175, 2 , 0 , 0 , 0 ,,
       5       5
     455     468
       5       5
     455     468
Pier Skew, UpSta & Num, DnSta & Num=  ,9390, 2 ,9390, 2 , 0 , 0 , 0 ,,
       1       1
     430     469
       1       1
     430     469
Pier Skew, UpSta & Num, DnSta & Num=  ,9440, 2 ,9440, 2 , 0 , 0 , 0 ,,
       3       3
     430     469
       3       3
     430     469
Pier Skew, UpSta & Num, DnSta & Num=  ,9513, 2 ,9513, 2 , 0 , 0 , 0 ,,
       3       3
     430     469
       3       3
     430     469
Pier Skew, UpSta & Num, DnSta & Num=  ,9565, 2 ,9565, 2 , 0 , 0 , 0 ,,
       1       1
     430     469
       1       1
     430     469
Pier Skew, UpSta & Num, DnSta & Num=  ,10280, 2 ,10280, 2 , 0 , 0 , 0 ,,
       1       1
     430     469
       1       1
     430     469
Pier Skew, UpSta & Num, DnSta & Num=  ,10330, 2 ,10330, 2 , 0 , 0 , 0 ,,
       1       1
     430     469
       1       1
     430     469
Pier Skew, UpSta & Num, DnSta & Num=  ,10380, 2 ,10380, 2 , 0 , 0 , 0 ,,
       1       1
     430     469
       1       1
     430     469
Pier Skew, UpSta & Num, DnSta & Num=  ,10430, 2 ,10430, 2 , 0 , 0 , 0 ,,
       1       1
     430     469
       1       1
     430     469
BR Coef= 1 , 0 , 0 ,1.05, 0 ,,,0.8,-1,0.5,1,
WSPro=,,,, 1 ,,,, 0 ,,,, 0 ,,,,-1 ,-1 ,-1 , 0 , 0 , 0 , 0 , 0
BC Design=,, 0 ,, 0 ,,,,,,
BC HTab HWMax=470.1
BC Use User HTab Curves=0
BC User HTab FreeFlow(D)= 0

Type RM Length L Ch R = 1 ,147312  ,1,1,1
BEGIN DESCRIPTION:
This cross section corresponds to cross section 147301 of the non-georeferenced CDC model which was the source of this model.
One-foot upstream of SH 121.  Duplication of previous bridge cross-section (147301) without bridge piers.
Channel data from SH 121 bridge plans.
END DESCRIPTION:
XS GIS Cut Line= 4
2443660.98029071 7067399.15611012443167.06776652 7067321.3716743
2438839.800174337066639.88648872 2437950.75763087066499.87450428
#Sta/Elev= 30
    5595   469.9    6095   469.9    6095  467.49    6116     457    6145   454.7
    6188   459.1    7028   459.9    7064   457.4    7370   460.2  7384.8   467.5
  7384.8   470.1  9345.7   470.1  9345.7   467.5    9366   458.3  9389.5  452.81
    9426   434.5  9441.5     432    9478   436.6    9517   455.2    9580   462.8
    9601   462.8  9610.3   467.5  9610.3   469.9 10235.1     470 10235.1  467.49
   10250   459.8   10393   457.9   10462   460.6 10475.6   469.8 11375.6   469.8
#Mann= 3 ,0,0
    5595    .055       0    9366     .05       0    9580    .055       0
Bank Sta=9366,9580
XS Rating Curve= 0 ,0
Exp/Cntr=0.5,0.3

Type RM Length L Ch R = 1 ,147311  ,95,95,95
BEGIN DESCRIPTION:
This cross section corresponds to cross section 147300 of the non-georeferenced CDC model which was the source of this model.
One-foot downstream of SH 121.  Duplication of following bridge cross-section (147301) without bridge piers.
Channel data from NDM Elm Fork channel survey.
END DESCRIPTION:
XS GIS Cut Line= 4
2443675.931390817067400.564594352443182.019180187067322.77816755
2438845.474047517066639.813982292433906.351941257065861.94971431
#Sta/Elev= 30
    5590   469.6    6090   469.6    6116     457    6145   454.7    6162   454.7
    6188   459.1    7028   459.9    7064   457.4    7093   459.5    7362   460.1
    7370   460.2    7390   470.1    9340   470.1    9366   458.3    9381   456.8
    9424   436.6    9443     432    9470     433    9489   444.2    9517   455.2
    9580   462.8    9601   462.8    9615   469.9   10230     470   10250   459.8
   10353     460   10393   457.9   10462   460.6   10480   469.8   15480   469.8
#Mann= 3 ,0,0
    5590    .055       0    9366     .05       0    9580    .055       0
Bank Sta=9366,9580
XS Rating Curve= 0 ,0
Exp/Cntr=0.5,0.3

Type RM Length L Ch R = 1 ,147216  ,901,832,801
BEGIN DESCRIPTION:
This cross section corresponds to cross section 147204 of the non-georeferenced CDC model which was the source of this model.
Cross-section EF171.  97 feet downstream of SH 121.  Effective flow limit set at sta 6250 in LOB, at sta 10700 in ROB.  Connell project in LOB. Channel data from NDM Elm Fork channel survey - cross-section EF#171 surveyed
January 1994
END DESCRIPTION:
XS GIS Cut Line= 6
2443540.606116427067288.328175862435154.239960167065964.90293054
2434638.254115497065848.390040222434088.977983097065665.29821479
2433639.570089257065426.723232632433014.50375408 7065043.7089068
#Sta/Elev= 30
    5750   458.4    6769   459.1    7422   460.6    7440   469.8    9280   470.1
    9295   462.5    9331   462.1    9381   456.8    9426   434.5    9446  433.02
    9482   440.1    9517   455.2    9580   462.8    9635   462.4    9650   469.8
   10160     470   10182   458.8   10393   457.9   12029   467.7   13173   463.3
   13235   458.4   14019     458   14199   462.1   14313   457.7   14372     464
   14438   459.6   14709   459.3   14793     464   15298   468.4   16590   474.4
#Mann= 5 ,-1,0
    5750     .03       0    6769     .05       0    9280     .08       0
    9331     .05       0    9580      .1       0
#XS Ineff= 4 ,-1
    6250    9331     460    9580   10700     460   10700   16590     470
    5750    6250     470
Permanent Ineff=
       F       F       F       F
Bank Sta=9331,9580
XS Rating Curve= 0 ,0
Exp/Cntr=0.3,0.1