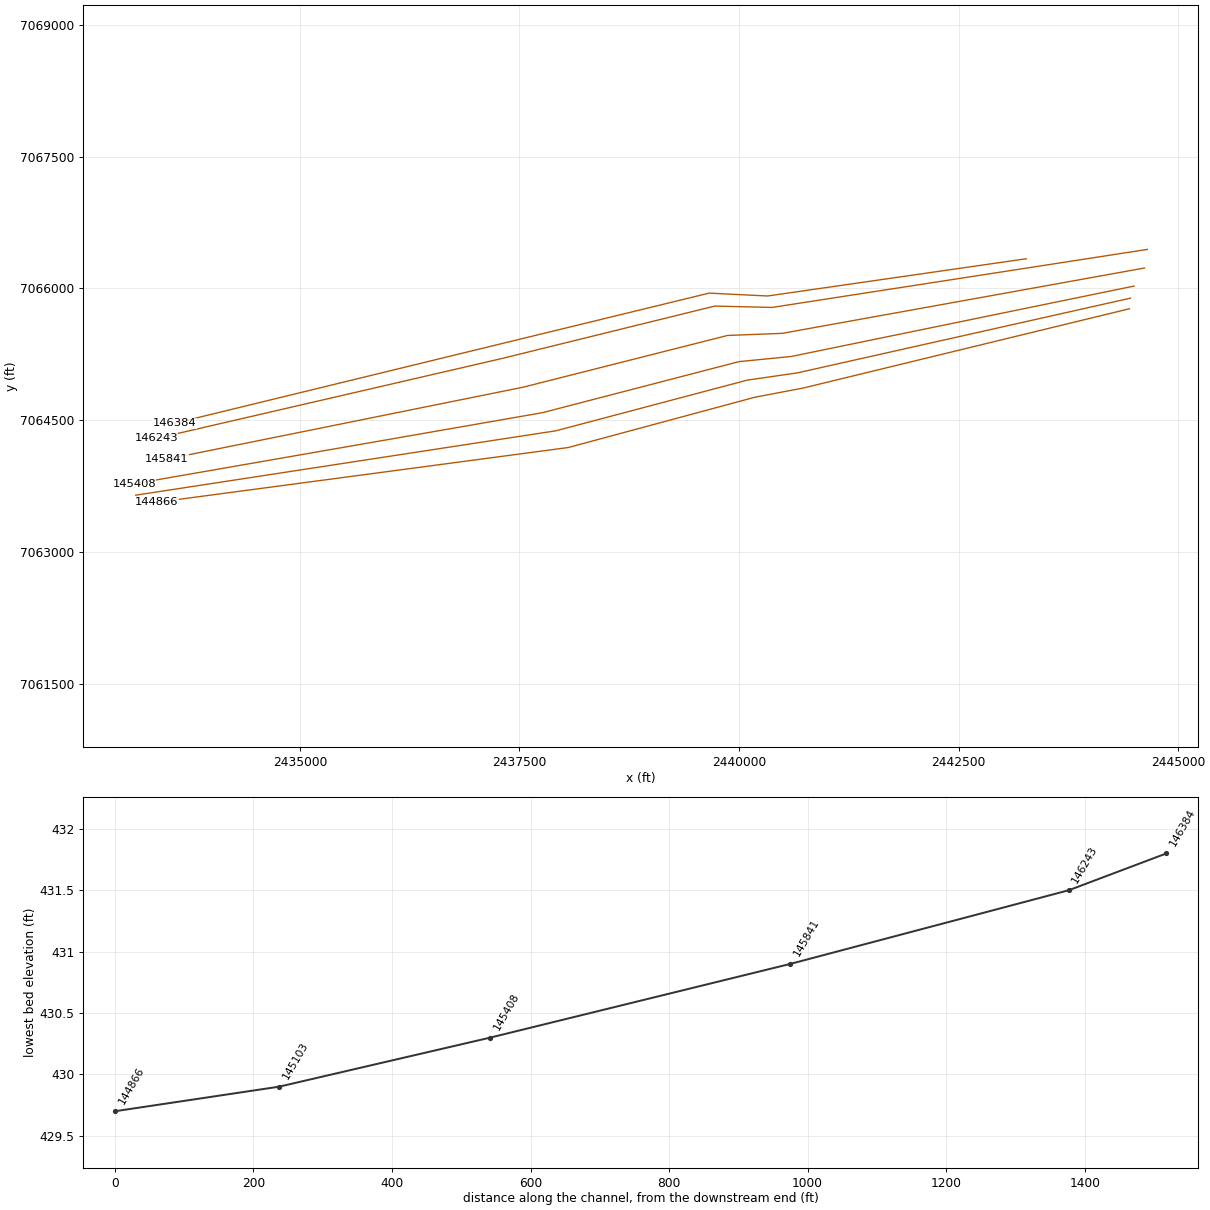
HEC-RAS study CDC_Consolidated_Model.prj: Upper Trinity CDC Consolidated Model

--- CDC_Consolidated_Model.g01 (geometry) --- (continued)

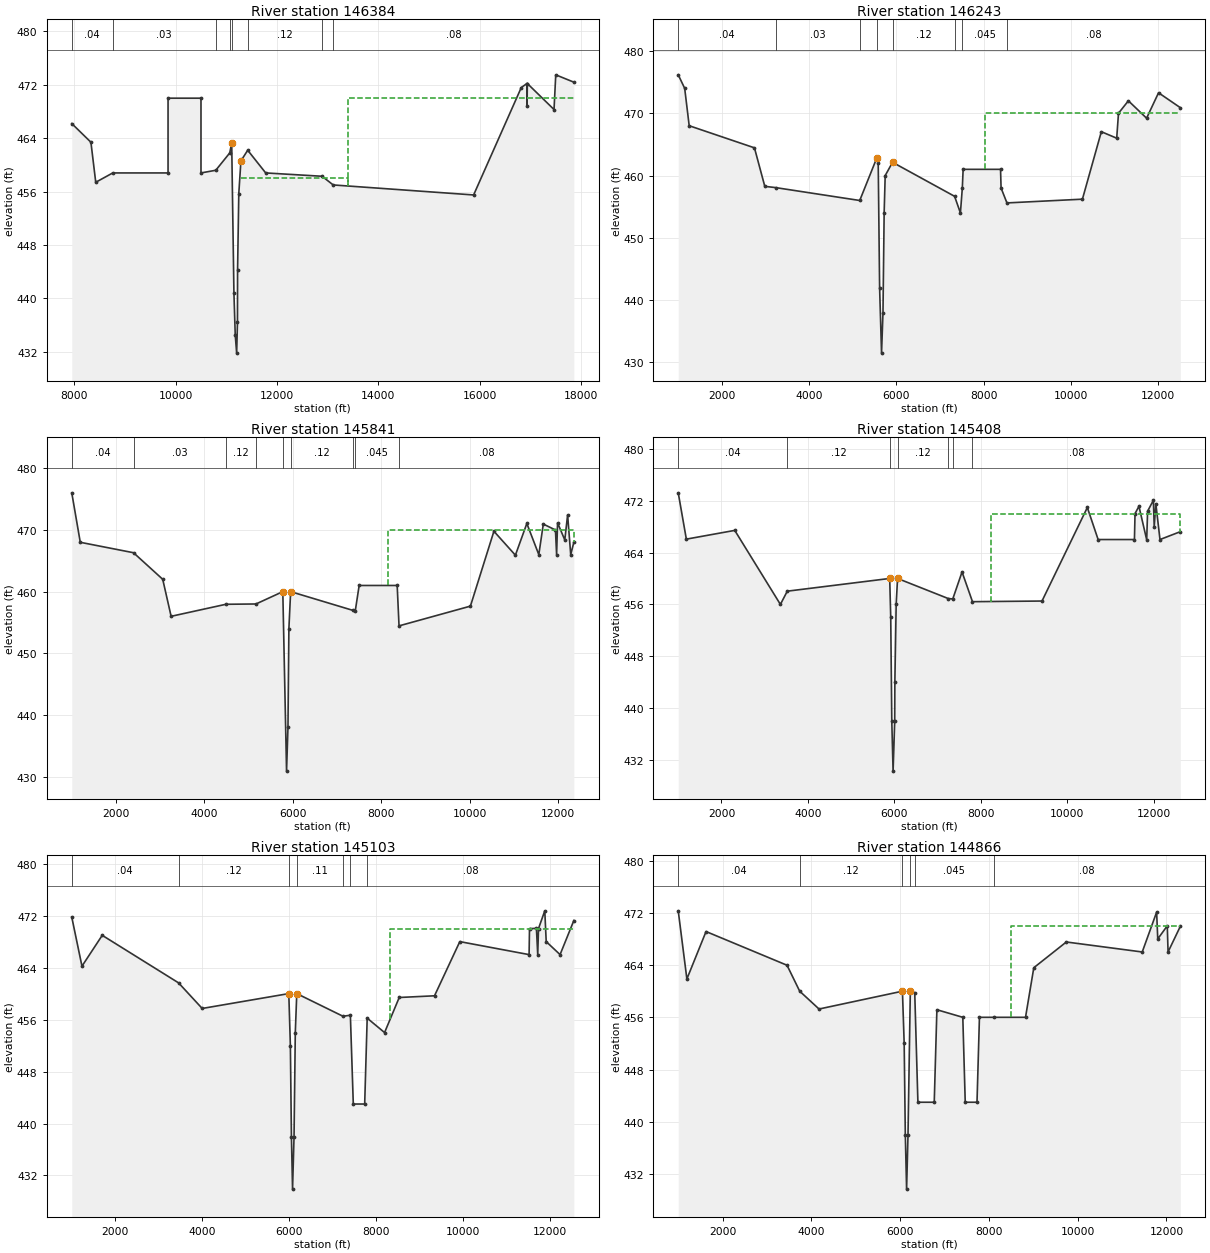
Type RM Length L Ch R = 1 ,146384  ,141,141,177
BEGIN DESCRIPTION:
This cross section corresponds to cross section 146373 of the non-georeferenced CDC model which was the source of this model.
Cross Section Truncated due to Ineffective Flow Areas
- End Lewisville CLOMR.
Proposed Park Improvements - 13863.99-14110 (not shown)
END DESCRIPTION:
XS GIS Cut Line= 4
2443270.27720577 7066336.75159632440325.592150247065912.75014772
  2439659.4350187065945.512221312433571.254609087064463.41577604
#Sta/Elev= 30
    7950   466.2    8328   463.4    8423   457.4    8759   458.8    9850   458.8
    9850     470   10500     470   10500   458.8   10792   459.2   11068   461.8
   11106   463.3   11150   440.8   11176   434.5   11204   431.8   11220   436.5
   11222   444.2   11246   455.7   11288   460.6   11422   462.2   11777   458.8
   12890   458.3   13109     457   15880   455.5   16821   471.6   16933   472.2
   16935   468.8   16940   472.2   17467   468.3   17501   473.5   17858   472.4
#Mann= 8 ,-1,0
    7950     .04       0    8759     .03       0   10792     .04       0
   11068     .09       0   11106     .05       0   11422     .12       0
   12890     .05       0   13109     .08       0
#XS Ineff= 3 ,-1
    7950   11106     458   11288   13400     458   13400   17858     470
Permanent Ineff=
       F       F       F
Bank Sta=11106,11288
XS Rating Curve= 0 ,0
Exp/Cntr=0.3,0.1

Type RM Length L Ch R = 1 ,146243  ,237,402,298
BEGIN DESCRIPTION:
This cross section corresponds to cross section 146190  of the non-georeferenced CDC model which was the source of this model.
Added XS for Lewisville Atheltic Complex CLOMR.
Geopak data, interpolated flowline.
Proposed Park Improvements - 7514.39-8537.5
END DESCRIPTION:
XS GIS Cut Line= 5
2444648.866312097066443.213981792440376.618951087065782.63787514
2439723.594010417065798.005298472437299.62543318 7065201.0393008
2433363.086718357064290.98534663
#Sta/Elev= 30
    1000  476.17 1147.93     474 1251.16     468 2747.63  464.45  2984.9  458.27
 3232.16  458.07  5161.9     456 5556.94   462.9 5585.76     462 5617.74     442
    5662   431.5 5695.12  438.01 5721.77     454 5745.64     460 5914.86  462.13
 7337.32  456.67 7470.52     454 7514.39     458 7532.93     461  8390.6     461
 8402.96     458  8537.5  455.6110268.12  456.2110702.09  467.0411054.48     466
11095.36     47011322.03     472 11739.9  469.2112013.82  473.2912512.98   470.9
#Mann= 8 ,-1,0
    1000     .04       0 3232.16     .03       0  5161.9     .04       0
 5556.94     .05       0 5914.86     .12       0 7337.32     .05       0
 7514.39    .045       0  8537.5     .08       0
#XS Ineff= 2 , 0
       0    5590     458    8030       0     470
Permanent Ineff=
       F       F
Bank Sta=5556.94,5914.86
XS Rating Curve= 0 ,0
Exp/Cntr=0.3,0.1

Type RM Length L Ch R = 1 ,145841  ,314,433,239
BEGIN DESCRIPTION:
This cross section corresponds to cross section 145774  of the non-georeferenced CDC model which was the source of this model.
Added XS for Lewisville Atheltic Complex CLOMR.
Geopak data, interpolated flowline.
Proposed Park Improvements - 7415.65-8405.03
END DESCRIPTION:
XS GIS Cut Line= 5
2444617.051415097066231.377135132440492.26471716 7065487.5544758
2439869.413600687065463.58437939 2437543.50650717064874.87886389
2433478.885043177064053.98713297
#Sta/Elev= 30
    1000  476.02 1192.47     468    2397 466.309 3058.11     462 3247.94     456
  4487.9  457.95 5168.07     458  5775.2     460    5860   430.9 5892.08     438
 5912.78     454 5952.43     460 7357.92  456.97 7415.65  456.92 7502.95     461
 8363.24     461 8405.03  454.4510020.19  457.6510551.82  469.79   11038  465.91
11296.87  471.0511567.86     466 11669.6  470.9511944.33     47011970.66     466
11992.25  471.16 12155.6  468.3812219.71  472.44 12289.8     46612360.57     468
#Mann= 9 ,-1,0
    1000     .04       0    2397     .03       0  4487.9     .12       0
 5168.07     .04       0  5775.2     .05       0 5952.43     .12       0
 7357.92     .05       0 7415.65    .045       0 8405.03     .08       0
#XS Ineff= 2 , 0
       0    5774     457    8160       0     470
Permanent Ineff=
       F       F
Bank Sta=5775.2,5952.43
XS Rating Curve= 0 ,0
Exp/Cntr=0.3,0.1

Type RM Length L Ch R = 1 ,145408  ,222,305,244
BEGIN DESCRIPTION:
This cross section corresponds to cross section 145400  of the non-georeferenced CDC model which was the source of this model.
Added XS for Lewisville Atheltic Complex CLOMR
END DESCRIPTION:
XS GIS Cut Line= 5
2444497.827572177066025.763701222440595.212017837065224.42376846
2440000.141029517065165.626641962437760.809878267064584.05956364
2433112.307036167063774.77279638
#Sta/Elev= 30
    1000   473.2 1187.62  466.06 2307.28  467.41  3363.1     456 3522.78  458.04
 5891.45     460 5915.47     454  5939.9     438    5970   430.3 6007.61     438
 6010.92     444 6041.31     456 6073.27     460    7247 456.901 7350.71  456.84
 7564.92     461 7806.49  456.42 9414.81  456.5210463.22  470.9410712.89     466
11552.91     46611566.71     47011657.19  471.1311836.79  465.9511857.19  470.36
11991.42  472.0612010.32     46812048.15  471.5112143.83     46612614.05  467.21
#Mann= 7 ,-1,0
    1000     .04       0 3522.78     .12       0 5891.45     .05       0
 6073.27     .12       0    7247     .05       0 7350.71    .045       0
 7806.49     .08       0
#XS Ineff= 2 , 0
       0    5887     457    8240       0     470
Permanent Ineff=
       F       F
Bank Sta=5891.45,6073.27
XS Rating Curve= 0 ,0
Exp/Cntr=0.3,0.1

Type RM Length L Ch R = 1 ,145103  ,237,237,237
BEGIN DESCRIPTION:
This cross section corresponds to cross section 145140  of the non-georeferenced CDC model which was the source of this model.
Added XS for Lewisville Atheltic Complex CLOMR.
END DESCRIPTION:
XS GIS Cut Line= 5
2444456.547142927065888.113057882440667.99763343 7065038.0671858
2440093.219255427064954.782575472437914.820068937064378.15544789
2433130.851290437063645.08243896
#Sta/Elev= 30
    1000  471.77 1234.62  464.22 1701.25  468.97 3458.56  461.65 4002.06  457.71
 5995.61     460 6031.76     452 6055.88     438    6082   429.9 6116.27     438
 6145.24     454 6179.15     460    7243  456.51 7412.84  456.67  7480.2     443
 7742.35     443    7800  456.22 8200.17     454 8537.47   459.4 9349.61  459.66
 9932.04     46811526.57     46611536.24     47011695.48  470.0411725.67     466
11743.38  470.0111887.82  472.7411920.65     46812239.67     46612556.76  471.25
#Mann= 7 ,-1,0
    1000     .04       0 3458.56     .12       0 5995.61     .05       0
 6179.15     .11       0    7243     .05       0 7412.84    .045       0
    7800     .08       0
#XS Ineff= 2 , 0
       0    5992     458    8330       0     470
Permanent Ineff=
       F       F
Bank Sta=5995.61,6179.15
XS Rating Curve= 0 ,0
Exp/Cntr=0.3,0.1

Type RM Length L Ch R = 1 ,144866  ,89,201,293
BEGIN DESCRIPTION:
This cross section corresponds to cross section 145000  of the non-georeferenced CDC model which was the source of this model.
Added XS for Lewisville Atheltic Complex CLOMR.
END DESCRIPTION:
XS GIS Cut Line= 5
2444444.939226517065767.548994562440735.146777337064865.91431488
2440179.557009257064760.134998892438057.010401347064187.95372856
2433368.266826097063564.04487139
#Sta/Elev= 30
    1000   472.3 1194.76  461.87 1626.44  469.13 3451.02  463.97 3736.34     460
 4172.12  457.27 6051.28     460 6090.49     452 6116.02     438    6145   429.7
 6176.63     438 6228.97     460 6328.36  459.78 6399.85     443 6767.83     443
 6827.46  457.16 7411.33     456 7466.17     443 7731.18     443 7786.18     456
 8108.31     456 8824.15     456 9010.82  463.59 9743.44  467.53 11453.9     466
11778.31   472.111803.53     46812018.14     47012035.55     46612311.75  469.92
#Mann= 6 ,-1,0
    1000     .04       0 3736.34     .12       0 6051.28     .05       0
 6228.97     .05       0 6328.36    .045       0 8108.31     .08       0
#XS Ineff= 2 , 0
       0    6029     458    8495       0     470
Permanent Ineff=
       F       F
Bank Sta=6051.28,6228.97
XS Rating Curve= 0 ,0
Exp/Cntr=0.3,0.1