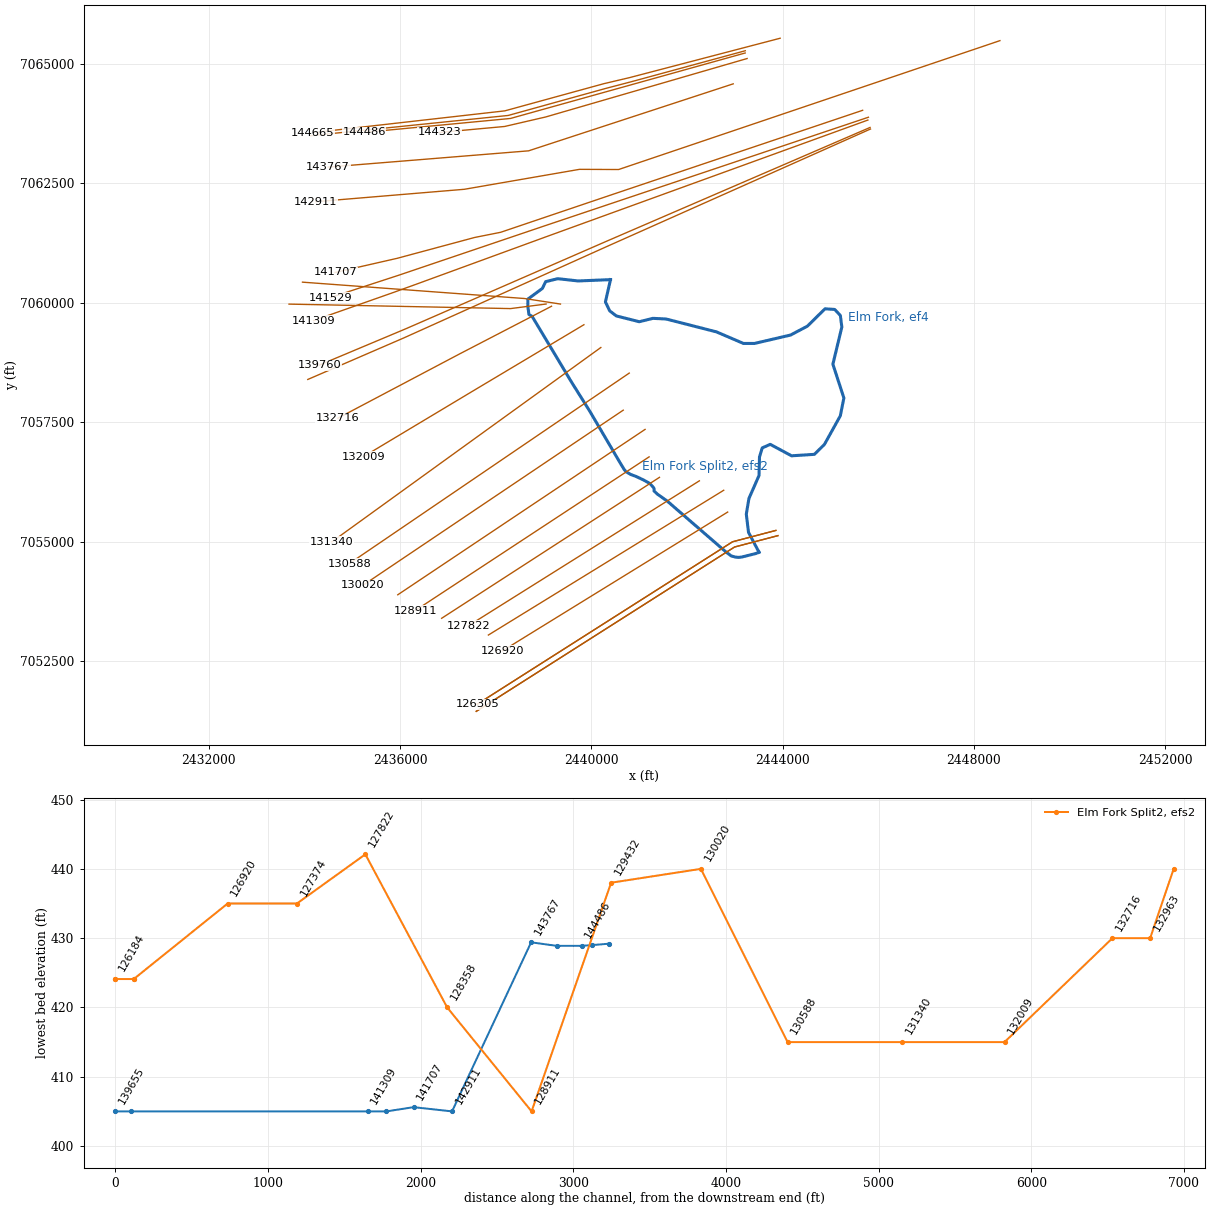
HEC-RAS study CDC_Consolidated_Model.prj: Upper Trinity CDC Consolidated Model

--- CDC_Consolidated_Model.g01 (geometry) --- (continued)

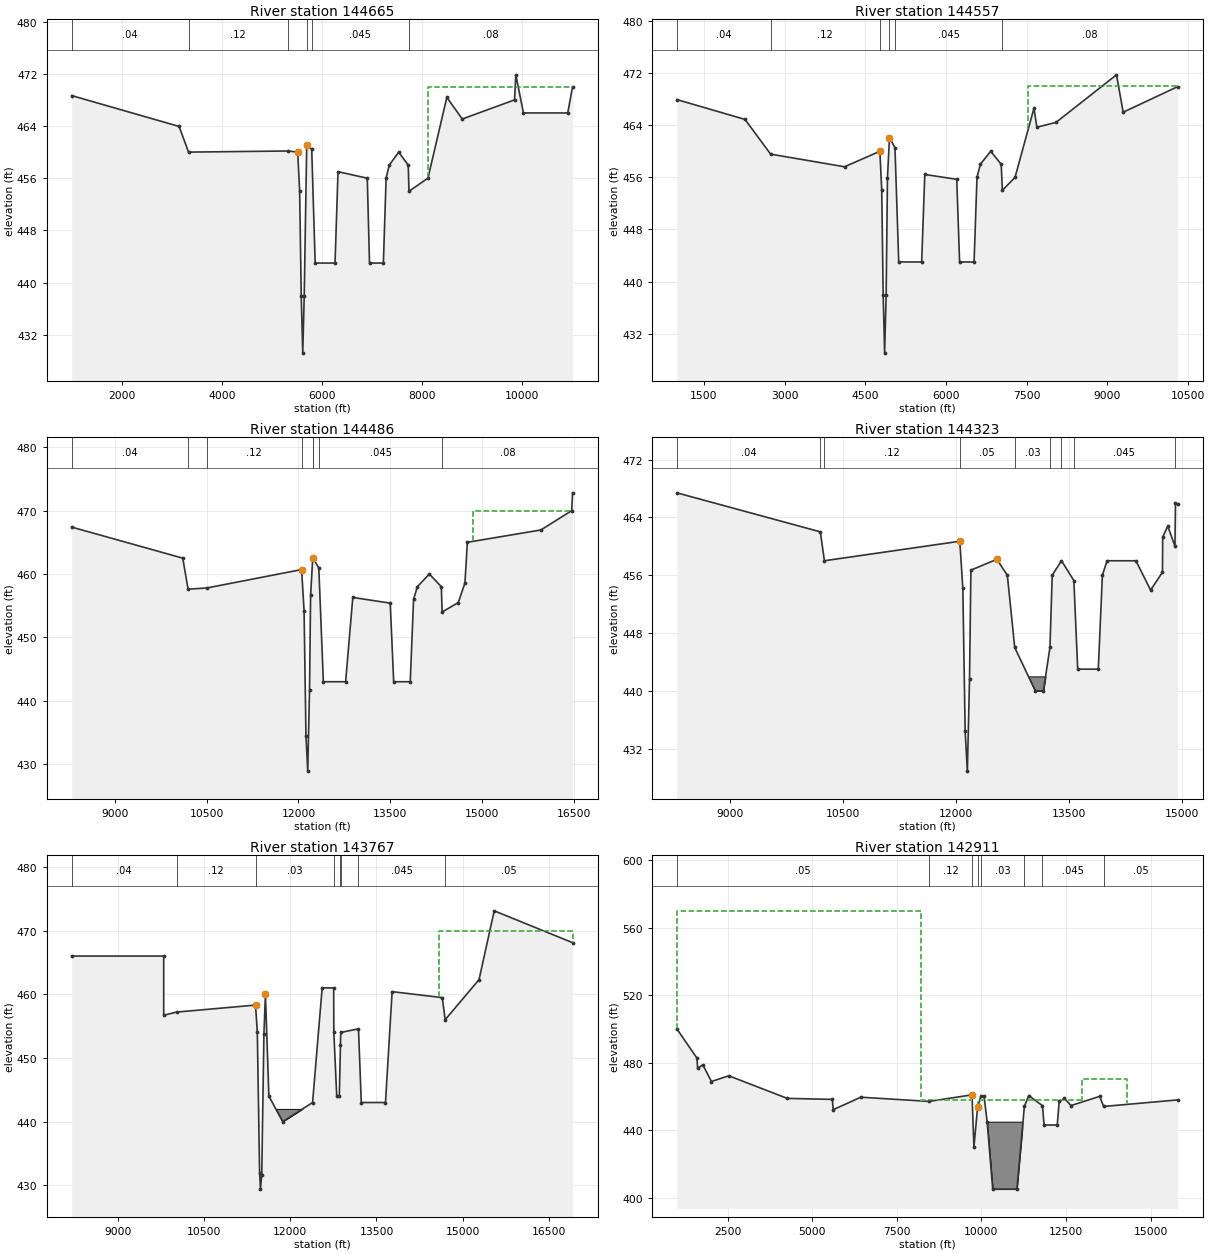
Type RM Length L Ch R = 1 ,144665  ,108,108,162
BEGIN DESCRIPTION:
This cross section corresponds to cross section 144646  of the non-georeferenced CDC model which was the source of this model.
Added XS for Lewisville Atheltic Complex CLOMR.
END DESCRIPTION:
XS GIS Cut Line= 5
2443949.803405767065529.901503972440797.504592277064705.83392638
2440260.166756187064579.254783212438189.185661917064011.10434471
2434167.64514858 7063554.7335383
#Sta/Elev= 30
    1000  468.66 3144.94  463.93 3333.97     460 5314.63  460.17 5514.24     460
 5552.99     454 5584.77     438    5615   429.2 5644.71     438 5694.29  461.08
 5794.43  460.45 5863.14     443  6260.1     443 6319.53     457 6904.17     456
 6948.46     443 7225.61     443 7280.07     456 7343.04     458 7531.96     460
 7722.58     458 7736.29     454 8115.92     456 8493.25  468.39 8801.11  465.07
 9845.37     468 9871.13  471.8410023.42     46610908.52     46611005.13  470.02
#Mann= 6 ,-1,0
    1000     .04       0 3333.97     .12       0 5314.63     .05       0
 5694.29     .05       0 5794.43    .045       0 7736.29     .08       0
#XS Ineff= 2 , 0
       0 5514.24     458    8110       0     470
Permanent Ineff=
       F       F
Bank Sta=5514.24,5694.29
XS Rating Curve= 0 ,0
Exp/Cntr=0.3,0.1

Type RM Length L Ch R = 1 ,144557  ,71,71,71
BEGIN DESCRIPTION:
This cross section corresponds to cross section 144554 of the non-georeferenced CDC model which was the source of this model.
Added XS for Lewisville Atheltic Complex CLOMR.
END DESCRIPTION:
XS GIS Cut Line= 5
2443220.874417427065268.569677552440831.276506337064619.02373254
 2440304.05807267064481.228732562438260.802316587063915.20099321
2434118.101284417063490.54173756
#Sta/Elev= 30
    1000  467.94 2266.35  464.89 2742.04  459.56  4115.2  457.62 4771.73     460
 4806.33     454  4833.1     438    4860     429 4888.67     438 4912.92  455.94
 4949.96  462.08  5052.5  460.55 5121.92     443 5548.33     443 5606.34  456.44
 6200.02  455.69 6252.98     443 6522.04     443 6576.31     456 6638.77     458
 6831.33     460 7026.35     458 7047.53     454 7283.14     456 7634.76  466.61
  7689.1   463.7 8043.26  464.43 9167.73  471.74 9292.68     46610305.85  469.93
#Mann= 6 ,-1,0
    1000     .04       0 2742.04     .12       0 4771.73     .05       0
 4949.96     .05       0  5052.5    .045       0 7047.53     .08       0
#XS Ineff= 2 , 0
       0    4781     458    7530       0     470
Permanent Ineff=
       F       F
Bank Sta=4771.73,4949.96
XS Rating Curve= 0 ,0
Exp/Cntr=0.3,0.1

Type RM Length L Ch R = 1 ,144486  ,155,163,155
BEGIN DESCRIPTION:
This cross section corresponds to cross section 144474 of the non-georeferenced CDC model which was the source of this model.
END DESCRIPTION:
XS GIS Cut Line= 3
2443218.701849587065221.590768892438307.751041597063852.31004289
2435247.728946427063561.08523163
#Sta/Elev= 30
    8300   467.4   10112   462.5   10199   457.6   10508   457.8   12051   460.7
   12091   454.2   12122   434.4   12151  428.89   12180   441.7   12198   456.7
   12233   462.6   12240   462.5 12331.7  460.9412405.75     44312768.79     443
12886.31   456.313497.03   455.413553.14     443 13823.4     44313877.68     456
13939.99     45814134.51     46014330.39     45814343.79     454   14608   455.5
   14716   458.6   14755     46515955.06  466.9516457.94     47016472.12  472.81
#Mann= 8 ,-1,0
    8300     .04       0   10199     .09       0   10508     .12       0
   12051     .05       0   12233      .1       0   12240     .05       0
 12331.7    .045       014343.79     .08       0
#XS Ineff= 2 , 0
       0   12051     458   14850       0     470
Permanent Ineff=
       F       F
Bank Sta=12051,12233
XS Rating Curve= 0 ,0
Exp/Cntr=0.3,0.1

Type RM Length L Ch R = 1 ,144323  ,111,167,261
BEGIN DESCRIPTION:
This cross section corresponds to cross section 144314 of the non-georeferenced CDC model which was the source of this model.
Added cross-section
END DESCRIPTION:
XS GIS Cut Line= 4
2443258.935036847065105.671053222439044.389332097063883.30243497
2438185.70568201 7063684.66438082436821.044041257063559.26732188
#Sta/Elev= 30
    8300   467.4   10202     462   10256     458   12051   460.7   12091   454.2
   12122   434.4   12151  428.89   12180   441.7   12198   456.7   12542   458.2
   12681     456   12779     446   13051     440   13159     440   13246     446
   13276     456   13399     45813562.81  455.2613614.04     44313886.99     443
13941.31     45614003.39     45814385.64     45814580.24  453.9414737.65  456.41
 14740.7  461.29 14808.5  462.7914903.27     460   14910     466   14940   465.8
#Mann= 9 ,-1,0
    8300     .04       0   10202     .09       0   10256     .12       0
   12051     .05       0   12779     .03       0   13246     .05       0
   13399     .08       013562.81    .045       014903.27     .08       0
#Block Obstruct= 1 ,-1
   12961   13201     442
Bank Sta=12051,12542
XS Rating Curve= 0 ,0
Exp/Cntr=0.3,0.1

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
Type RM Length L Ch R = 1 ,143767  ,622,518,306
BEGIN DESCRIPTION:
This cross section corresponds to cross section 143756 of the non-georeferenced CDC model which was the source of this model.
Proposed Park Improvements - 13187.64-14694.95
END DESCRIPTION:
XS GIS Cut Line= 3
2442968.259765187064576.398817792438685.958946597063175.14899564
2434494.472250857062834.95020096
#Sta/Elev= 30
    8200     466    9800     466    9800   456.7   10024   457.2   11397   458.3
   11428     454   11468   431.9   11483   429.4   11505   431.6   11543   453.8
   11569     460   11629     444   11869     440   12389     443   12556     461
   12756     461   12759     454   12809     444   12854     444   12874     452
   12879     45413187.64  454.5713236.01     44313656.82     44313772.62  460.41
14644.48  459.4714694.95     456   15284   462.3   15548   473.1   16911   468.1
#Mann= 8 ,-1,0
    8200     .04       0   10024     .12       0   11397     .03       0
   12756     .04       0   12874     .12       0   12879     .05       0
13187.64    .045       014694.95     .05       0
#XS Ineff= 2 , 0
       0   11358     458   14580       0     470
Permanent Ineff=
       F       F
#Block Obstruct= 1 ,-1
   11669   12269     442
Bank Sta=11397,11569
XS Rating Curve= 0 ,0
Exp/Cntr=0.3,0.1

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
Type RM Length L Ch R = 1 ,142911  ,185,252,195
BEGIN DESCRIPTION:
This cross section corresponds to cross section 142900 of the non-georeferenced CDC model which was the source of this model.
Proposed Park Improvements
END DESCRIPTION:
XS GIS Cut Line= 6
2448547.842109927065479.617155722440570.55885193 7062784.4890158
2439751.839032687062788.279034472437343.548901777062371.20014422
2435732.283423517062236.658090472434237.485531177062111.84118035
#Sta/Elev= 30
    1000     500    1593   482.7    1614   476.7    1767   478.7    2022   468.8
    2534   472.2    4261   458.8    5594   458.2    5620   452.1    6436   459.5
    8450     457    9721   460.9    9778  429.91    9887   453.8    9983     460
   10078     460   10168     445   10333     405   11048     405   11268     454
   11398   460.511802.65  454.4711851.17     44312239.32     44312298.18     457
12451.44  458.7512646.12  454.5513494.93     46013608.97  454.01   15800   457.9
#Mann= 8 ,-1,0
    1000     .05       0    8450     .12       0    9721     .05       0
    9887      .1       0    9983     .03       0   11268     .03       0
11802.65    .045       013608.97     .05       0
#XS Ineff= 4 ,-1
    1000    8200     570    8200    9721     458    9887   12978     458
   12978   14300     470
Permanent Ineff=
       F       F       F       F
#Block Obstruct= 1 ,-1
   10168   11208     445
Bank Sta=9721,9887
XS Rating Curve= 0 ,0
Exp/Cntr=0.3,0.1

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
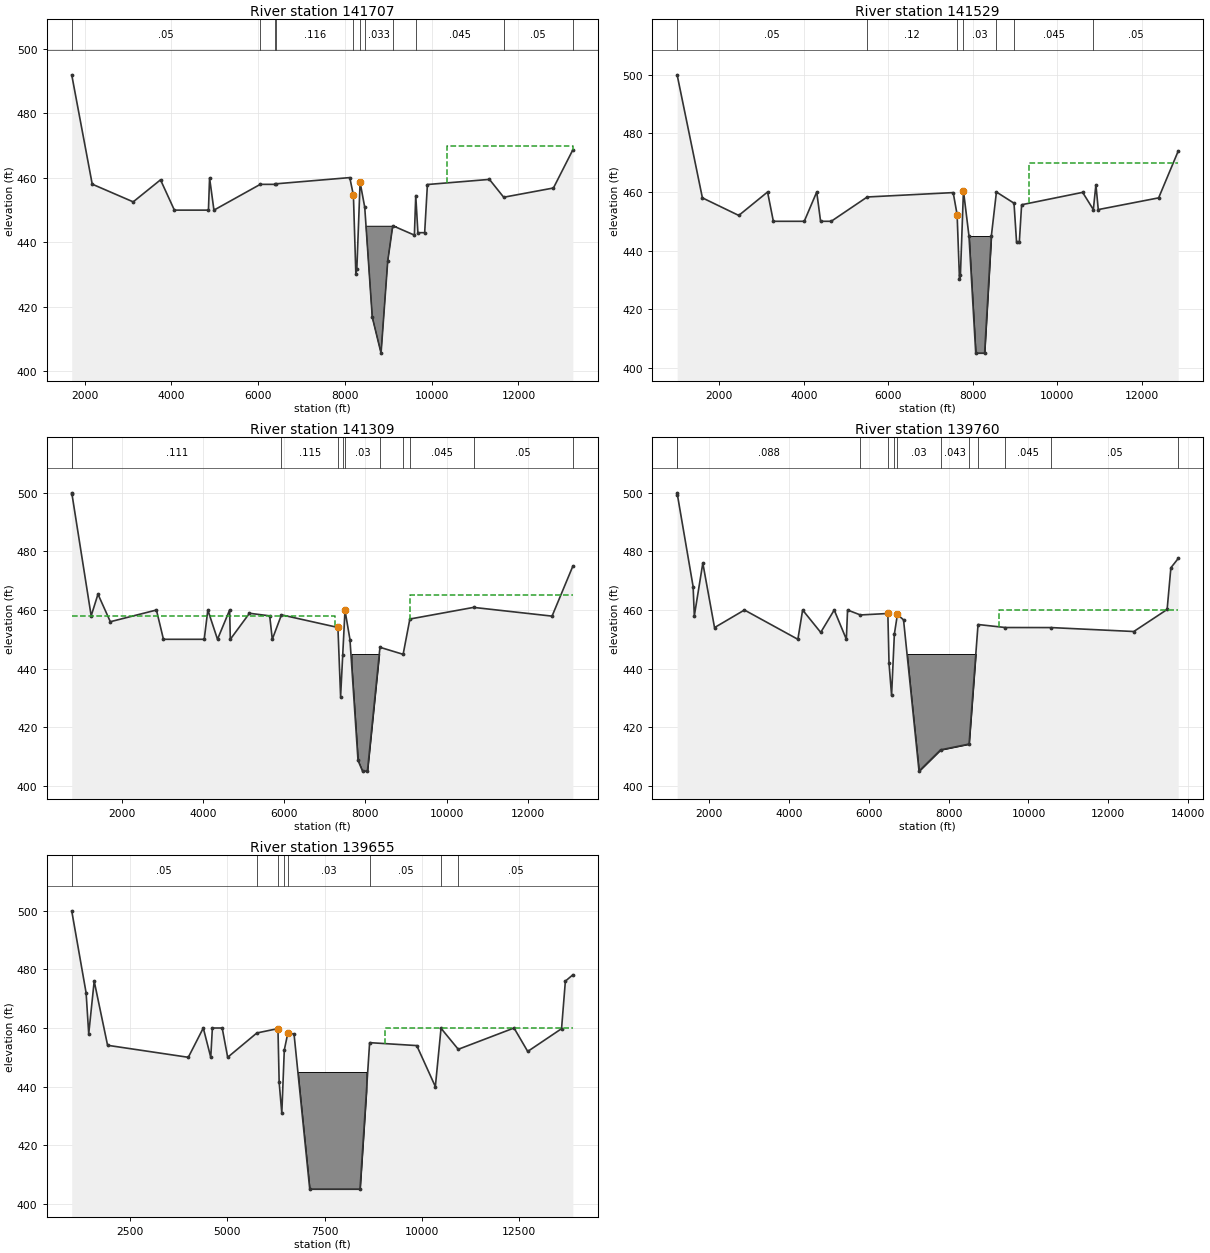
Type RM Length L Ch R = 1 ,141707  ,64,178,224
BEGIN DESCRIPTION:
This cross section corresponds to cross section 141891 of the non-georeferenced CDC model which was the source of this model.
Added XS for Lewisville Atheltic Complex CLOMR.
END DESCRIPTION:
XS GIS Cut Line= 6
   2445675.46499   7064022.81028 2440331.6065739 7062225.5521416
 2438102.0516498 7061471.7281899 2437558.2827243 7061363.5584587
 2435940.1183097 7060928.2164816 2434640.6839007 7060631.7269171
#Sta/Elev= 30
    1700     4922172.853458.05993117.467452.56643747.429459.40784067.159     450
4852.577     4504878.554     4604979.249     4506047.372     4586394.861     458
 6405.51  458.16 8111.09   460.1 8195.09  454.62 8251.36  430.19 8274.31  431.78
 8349.41  458.62 8456.11   450.9    8630  416.76 8832.49  405.61 8986.77   434.2
 9102.48  445.16 9601.18  442.24 9632.55  454.53  9681.8     443 9838.17     443
 9901.32  457.9511331.01  459.5411660.27     45412807.09  456.87 13254.5  468.71
#Mann= 11 ,-1,0
    1700     .05       06047.372     .05       06394.861    .113       0
 6405.51    .116       0 8195.09     .05       0 8349.41    .049       0
 8456.11    .033       0 9102.48    .052       0 9632.55    .045       0
11660.27     .05       0 13254.5    .045       0
#XS Ineff= 2 , 0
       0    8105     458   10350       0     470
Permanent Ineff=
       F       F
#Block Obstruct= 1 ,-1
    8480 9188.54     445
Bank Sta=8195.09,8349.41
XS Rating Curve= 0 ,0
Exp/Cntr=0.3,0.1

Type RM Length L Ch R = 1 ,141529  ,71,122,150
BEGIN DESCRIPTION:
This cross section corresponds to cross section 141518 of the non-georeferenced CDC model which was the source of this model.
Proposed Park Improvements
END DESCRIPTION:
XS GIS Cut Line= 5
    2445796.5051   7063878.11306  2441757.547291 7062523.7054166
 2439044.7587539 7061614.0100576 2435962.6251544 7060571.4169984
 2434543.2283869 7060108.2647095
#Sta/Elev= 30
    1000     5001598.488     4582459.837     4523141.728     4603279.137     450
4010.772     4504306.086     4604397.665     4504648.871     450    5502   458.3
    7538   459.8    7631   452.3    7687   430.3    7709   431.6    7781   460.4
    7912     445    8072     405    8282     405    8442     445    8562     460
 8978.41  456.18 9038.35     443 9104.72     443 9158.59  455.6510603.44  459.88
10857.37     454   10918   462.5   10974     454   12404     458   12868     474
#Mann= 7 ,-1,0
    1000     .05       0    5502     .12       0    7631     .05       0
    7781     .03       0    8562     .06       0 8978.41    .045       0
10857.37     .05       0
#XS Ineff= 2 , 0
       0    7538     458    9337       0     470
Permanent Ineff=
       F       F
#Block Obstruct= 1 ,-1
    7912    8442     445
Bank Sta=7631,7781
XS Rating Curve= 0 ,0
Exp/Cntr=0.3,0.1

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
Type RM Length L Ch R = 1 ,141309  ,422,1549,279
BEGIN DESCRIPTION:
This cross section corresponds to cross section 141084 of the non-georeferenced CDC model which was the source of this model.
Added XS for Lewisville Atheltic Complex CLOMR.
Swale normal pool elevation 453.5
END DESCRIPTION:
XS GIS Cut Line= 6
   2445785.53104    7063818.9137  2441511.608807 7062269.2869622
 2438997.3858172 7061357.6870794 2436348.4878998 7060390.0741852
 2435872.7778932 7060218.2661299 2434190.9876216 7059626.2236788
#Sta/Elev= 30
     774     500778.8699 499.6711252.676     4581419.875465.40811723.919     456
 2858.42     4603030.919     4504033.788     4504122.915     4604360.842     450
4659.301     4604676.231     4505146.837458.88725645.255     458 5708.92     450
 5934.26  458.35 7323.61  454.04 7389.57  430.44 7441.21  444.54 7497.45  459.89
 7619.84  449.93 7818.14  408.64 7928.86     405 8049.56     405 8358.13  447.27
 8928.09  444.87 9093.79  456.9210660.47  460.8912592.07  457.91 13103.4  474.96
#Mann= 11 ,-1,0
     774     .05       0778.8699    .111       0 5934.26    .115       0
 7323.61    .048       0 7441.21    .052       0 7497.45     .03       0
 8358.13    .055       0 8928.09    .049       0 9093.79    .045       0
10660.47     .05       0 13103.4     .05       0
#XS Ineff= 2 , 0
       0 7245.05     458    9090       0     465
Permanent Ineff=
       F       F
#Block Obstruct= 1 ,-1
7659.0078473.479     445
Bank Sta=7323.61,7497.45
XS Rating Curve= 0 ,0
Exp/Cntr=0.3,0.1

Type RM Length L Ch R = 1 ,139760  ,103,105,103
BEGIN DESCRIPTION:
This cross section corresponds to cross section 139890 of the non-georeferenced CDC model which was the source of this model.
Added XS for Lewisville Atheltic Complex CLOMR.
Swale normal pool elevation 453.5
END DESCRIPTION:
XS GIS Cut Line= 5
   2445830.53784   7063664.34774  2441895.766503 7061965.7518081
 2440327.8103217 7061288.8830831 2436120.7544313 7059455.0340606
  2434305.973284  7058693.486043
#Sta/Elev= 30
    1200     5001207.549499.29291600.411     468 1630.78     4581843.391     476
2136.795     4542885.903     4604224.158     4504343.372     4604796.403452.3515
5134.408     4605438.438     450 5468.72     460 5789.87  458.31 6477.94  458.81
 6507.17  441.81 6571.28  430.82 6641.22   451.8 6717.37  458.49 6870.93  456.62
 7258.65     405 7797.24  412.25 8512.36  414.24 8736.59  455.05    9421  454.02
   10571     45412637.77  452.6613472.71  460.1813566.76  474.4213751.03   477.6
#Mann= 12 ,-1,0
    1200     .05       01207.549    .088       0 5789.87    .144       0
 6477.94    .041       0 6641.22    .092       0 6717.37     .03       0
 7797.24    .043       0 8512.36    .048       0 8736.59     .05       0
    9421    .045       0   10571     .05       013751.03     .05       0
#XS Ineff= 2 , 0
       0 6439.02     458    9270       0     460
Permanent Ineff=
       F       F
#Block Obstruct= 1 ,-1
6962.984    9000     445
Bank Sta=6477.94,6717.37
XS Rating Curve= 0 ,0
Exp/Cntr=0.3,0.1

Type RM Length L Ch R = 1 ,139655  ,0,0,0
BEGIN DESCRIPTION:
This cross section corresponds to cross section 139643 of the non-georeferenced CDC model which was the source of this model.
---------------------------------------------------------------------
CDC LEW110305-1 Lewisville Athletic Complex
Cross-section 139643 - 146373
Project located in ROB.
---------------------------------------------------------------------
END DESCRIPTION:
XS GIS Cut Line= 5
   2445840.16414   7063631.77366  2441711.337082 7061792.4299763
 2440311.3900789 7061168.7701344 2436073.6820189 7059261.6181088
 2434067.9042063 7058394.1267336
#Sta/Elev= 30
    1000     5001369.871     4721437.134     4581577.627     4761922.011454.0978
3998.008     4504382.987     4604575.025     4504616.718     4604869.331     460
5010.003     450    5760   458.3    6303   459.8    6334   441.4    6402   430.9
    6466   452.5    6556   458.2    6716     458    7120     405    8413     405
    8660     455    9872     454   10350     440   10496   459.9   10939  452.73
   12373     460   12725     452   13595  459.77   13693     476   13885  478.15
#Mann= 8 ,-1,0
    1000     .05       0    5760     .15       0    6303     .04       0
    6466      .1       0    6556     .03       0    8660     .05       0
   10496     .03       0   10939     .05       0
#XS Ineff= 2 , 0
       0    6303     458    9044       0     460
Permanent Ineff=
       F       F
#Block Obstruct= 1 ,-1
    6819    8578     445
Bank Sta=6303,6556
XS Rating Curve= 0 ,0
Exp/Cntr=0.3,0.1

River Reach=Elm Fork Split2 ,efs2
Reach XY= 30
      2440400.92      7060482.14       2439724.1      7060454.22
      2439297.21      7060501.84      2439044.88      7060439.71
      2438975.07      7060297.12      2438672.06      7060074.32
      2438672.06      7059921.33      2438694.34      7059753.48
      2438761.18      7059713.38      2439574.71      7058356.55
      2439972.31      7057721.91      2440604.42      7056646.97
      2440688.53      7056509.34      2440730.74      7056461.97
      2440822.83       7056408.5      2440939.57      7056364.69
      2441092.49      7056292.05       2441226.1      7056217.92
      2441302.25       7056131.3      2441314.62      7056100.84
      2441310.81      7056063.72       2441382.2      7055996.14
      2441589.26      7055850.01      2442820.61      7054783.54
      2442930.53      7054701.84      2443016.68      7054679.56
      2443082.03      7054673.62      2443154.81      7054682.53
      2443443.72      7054755.15      2443507.86      7054781.77

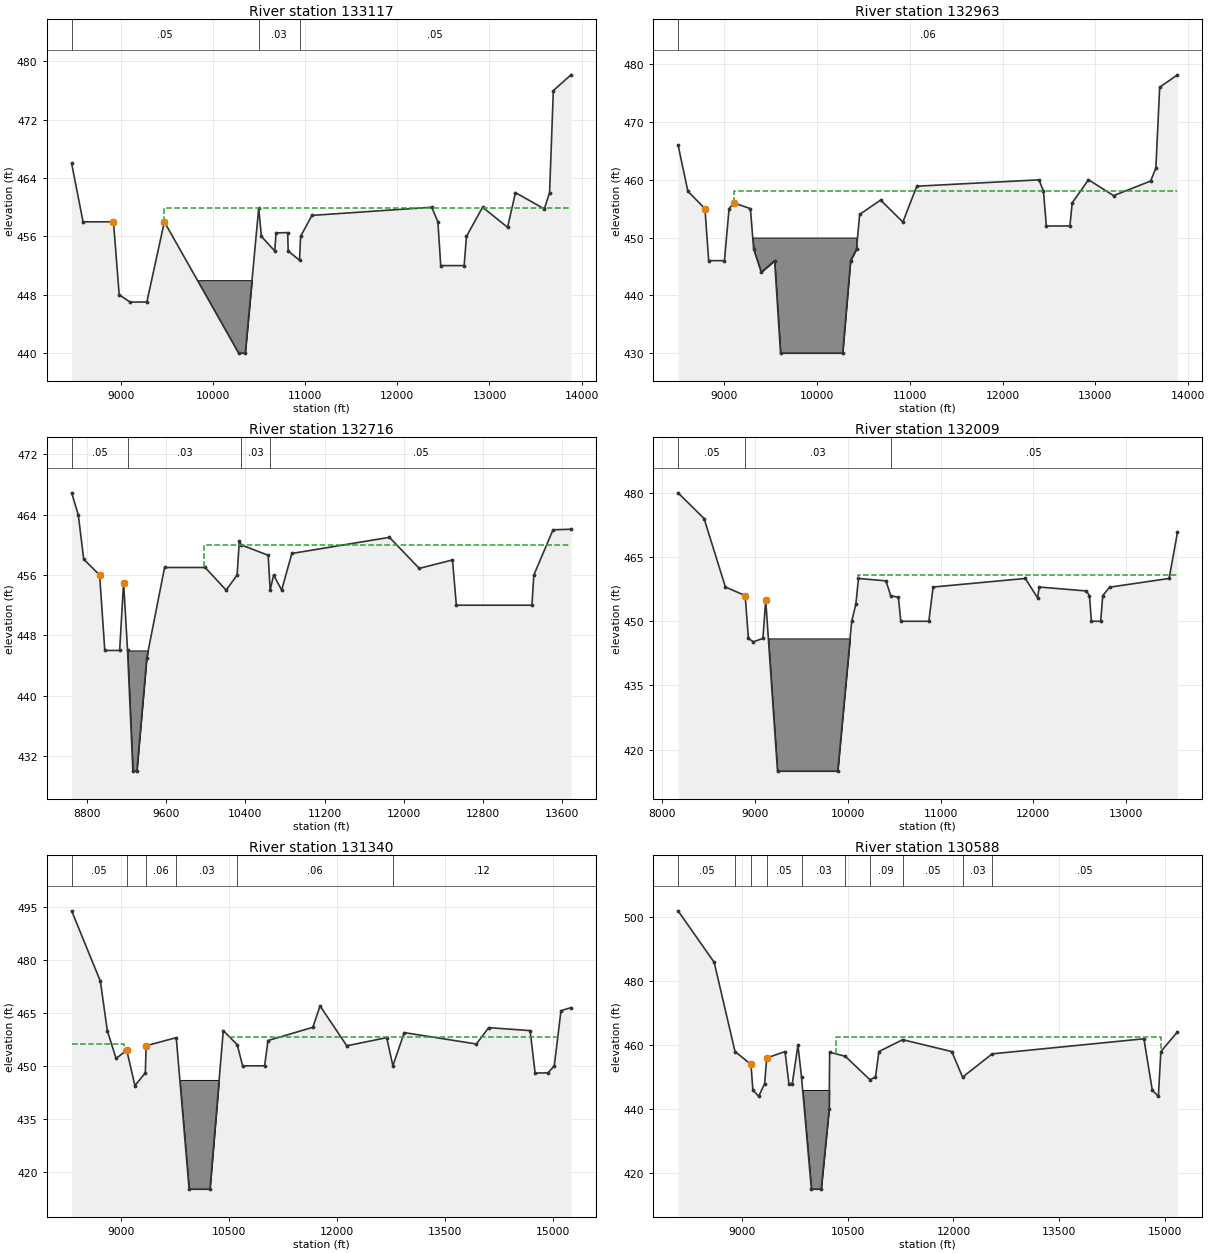
Type RM Length L Ch R = 1 ,133117  ,91,154,154
BEGIN DESCRIPTION:
This cross section corresponds to cross section 132950 of the non-georeferenced CDC model which was the source of this model.
This section is lined with rock rap rip in the graded portion.
END DESCRIPTION:
XS GIS Cut Line= 5
 2439354.4418616 7059971.0153121 2438603.4249909 7060086.8211828
 2434066.7660853 7060421.0186771 2434019.7382922 7060424.4829091
     2433956.908     7060429.111
#Sta/Elev= 30
    8466     466    8590     458    8920     458    8982     448    9100     447
    9282     447    9472     458   10278     440   10350     440   10496   459.9
   10525     456   10670     454   10684  456.48   10810  456.52   10816     454
   10939  452.73   10950     456   11074  458.88   12373     460   12440     458
   12471     452   12725     452   12750     456   12925     460   13196  457.25
   13282     462   13595  459.77   13652     462   13693     476   13885  478.15
#Mann= 3 ,-1,0
    8466     .05       0   10496     .03       0   10939     .05       0
#XS Ineff= 1 ,-1
    9472   13885   459.9
Permanent Ineff=
       T
#Block Obstruct= 1 ,-1
    9646   10439     450
Bank Sta=8920,9472
XS Rating Curve= 0 ,0
Exp/Cntr=0.5,0.3

Type RM Length L Ch R = 1 ,132963  ,174,247,306
BEGIN DESCRIPTION:
This cross section corresponds to cross section 132780 of the non-georeferenced CDC model which was the source of this model.
NOTE: topo east of railroad tracks updated Feb 2002 by Freese & Nichols, Inc.
END DESCRIPTION:
XS GIS Cut Line= 5
 2439053.5100488 7059971.8945754 2438310.2169159 7059876.3740971
 2437042.7821148 7059901.9682061 2433738.5547994 7059968.6928101
     2433675.567     7059969.965
#Sta/Elev= 30
    8500     466    8606     458    8790     455    8830     446    9000     446
    9050     455    9101     456    9280     455    9315     448    9397     444
    9541     446    9605     430   10275     430   10360     446   10424     448
   10458     454   10684  456.48   10924  452.68   11074  458.88   12392  459.98
   12440     458   12471     452   12725     452   12750     456   12925     460
   13196  457.25   13595  459.77   13652     462   13693     476   13885  478.15
#Mann= 1 ,-1,0
    8500     .06       0
#XS Ineff= 1 ,-1
    9101   13885     458
Permanent Ineff=
       T
#Block Obstruct= 1 ,-1
    9307   10425     450
Bank Sta=8790,9101
XS Rating Curve= 0 ,0
Exp/Cntr=0.3,0.1

Type RM Length L Ch R = 1 ,132716  ,697,707,737
BEGIN DESCRIPTION:
This cross section corresponds to cross section 132538 of the non-georeferenced CDC model which was the source of this model.
NOTE: topo east of railroad tracks updated Feb 2002 by Freese & Nichols, Inc.
END DESCRIPTION:
XS GIS Cut Line= 4
 2439167.4944008 7059925.5442744 2437240.0199094  7058926.387152
   2434702.85438 7057587.1165365     2434697.548     7057584.316
#Sta/Elev= 30
    8645   466.9    8712     464    8767   458.1    8928     456    8980     446
    9130     446    9170     455    9210     446    9264     430    9304     430
    9404     445    9584     457    9994     457   10206     454   10317     456
   10339   460.5   10357     460   10631  458.62   10651     454   10686     456
   10767     454   10870  458.86   11856     461   12157  456.88   12493     458
   12532     452   13296     452   13315     456   13509     462   13691  462.07
#Mann= 4 ,-1,0
    8645     .05       0    9210     .03       0   10357     .03       0
   10651     .05       0
#XS Ineff= 1 ,-1
    9984   13671     460
Permanent Ineff=
       F
#Block Obstruct= 1 ,-1
    9184    9444     446
Bank Sta=8928,9170
XS Rating Curve= 0 ,0
Exp/Cntr=0.5,0.3

Type RM Length L Ch R = 1 ,132009  ,649,669,709
BEGIN DESCRIPTION:
This cross section corresponds to cross section 131838 of the non-georeferenced CDC model which was the source of this model.
NOTE: topo east of railroad tracks updated Feb 2002 by Freese & Nichols, Inc.
END DESCRIPTION:
XS GIS Cut Line= 4
 2439844.8690303 7059539.1834986  2437484.033857 7058129.9071176
 2435233.0649338 7056780.3592918     2435228.776     7056777.788
#Sta/Elev= 30
    8173     480    8453     474    8683     458    8896     456    8930     446
    8984   445.2    9087     446    9117   454.9    9244     415    9893     415
   10043     450   10088     454   10116     460   10412  459.44   10463     456
   10546  455.59   10572     450   10874     450   10920     458   11913     460
   12045  455.46   12063     458   12570  457.08   12604     456   12625     450
   12725     450   12747     456   12821  457.96   13462     460   13552  470.79
#Mann= 3 ,-1,0
    8173     .05       0    8896     .03       0   10463     .05       0
#XS Ineff= 1 ,-1
   10116   13551  460.72
Permanent Ineff=
       F
#Block Obstruct= 1 ,-1
 9145.3310025.86     446
Bank Sta=8896,9117
XS Rating Curve= 0 ,0
Exp/Cntr=0.3,0.1

Type RM Length L Ch R = 1 ,131340  ,762,752,742
BEGIN DESCRIPTION:
This cross section corresponds to cross section 131168 of the non-georeferenced CDC model which was the source of this model.
NOTE: topo east of railroad tracks updated Feb 2002 by Freese & Nichols, Inc.
END DESCRIPTION:
XS GIS Cut Line= 3
  2440198.752837  7059062.434124 2434577.1545002 7055003.1249854
     2434567.426       7054996.1
#Sta/Elev= 30
    8311     494    8711     474    8807     460    8929   452.1    9078   454.4
    9191   444.4    9336     448    9347   455.7    9766     458    9945     415
   10235     415   10420     460   10614     456   10689     450   10995     450
   11042  457.18   11666  460.94   11766     467   12138  455.69   12693     458
   12779     450   12937  459.43   13940   456.2   14112  460.84   14688     460
   14757  447.95   14936     448   15024     450   15117  465.66   15257  466.53
#Mann= 6 ,-1,0
    8311     .05       0    9078     .03       0    9347     .06       0
    9766     .03       0   10614     .06       0   12779     .12       0
#XS Ineff= 3 ,-1
    8311    9034   456.2                           10496   15070  458.29
Permanent Ineff=
       F       F       F
#Block Obstruct= 1 ,-1
 9820.11   10359     446
Bank Sta=9078,9347
XS Rating Curve= 0 ,0
Exp/Cntr=0.3,0.1

Type RM Length L Ch R = 1 ,130588  ,568,568,558
BEGIN DESCRIPTION:
This cross section corresponds to cross section 130418  of the non-georeferenced CDC model which was the source of this model.
NOTE: topo east of railroad tracks updated Feb 2002 by Freese & Nichols, Inc.
END DESCRIPTION:
XS GIS Cut Line= 3
 2440793.1919369 7058527.5913616  2434941.865713 7054546.8991918
     2434936.905     7054543.524
#Sta/Elev= 30
    8094     502    8606   485.9    8902     458    9128     454    9155     446
    9237     444    9322     448    9351     456    9611     458    9666     448
    9714     448    9794     460    9845     450    9985     415   10124     415
   10237     440   10244   457.8   10466  456.52   10815   449.2   10894     450
   10942     458   11279  461.72   11976     458   12129     450   12549  457.29
   14701     462   14820  445.91   14906     444   14941     458   15177  464.15
#Mann= 10 ,-1,0
    8094     .05       0    8902     .06       0    9128     .03       0
    9351     .05       0    9845     .03       0   10466     .05       0
   10815     .09       0   11279     .05       0   12129     .03       0
   12549     .05       0
#XS Ineff= 1 ,-1
   10339   14943  462.47
Permanent Ineff=
       F
#Block Obstruct= 1 ,-1
    9861 10263.2     446
Bank Sta=9128,9351
XS Rating Curve= 0 ,0
Exp/Cntr=0.3,0.1

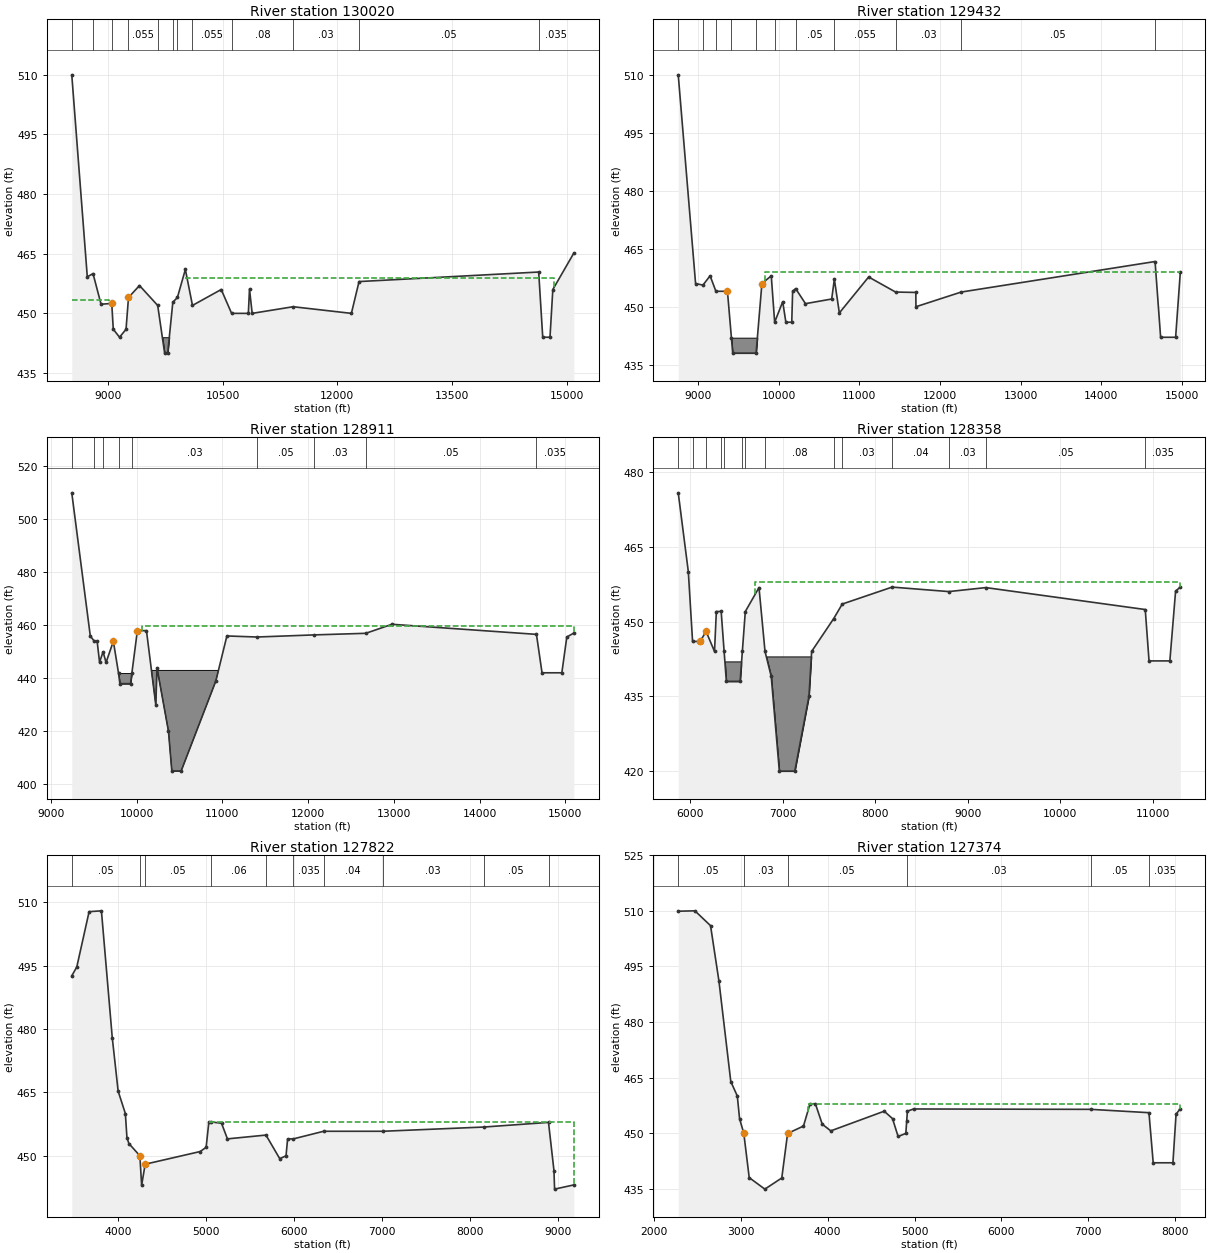
Type RM Length L Ch R = 1 ,130020  ,588,588,588
BEGIN DESCRIPTION:
This cross section corresponds to cross section 129848 of the non-georeferenced CDC model which was the source of this model.
NOTE: topo east of railroad tracks updated Feb 2002 by Freese & Nichols, Inc.
END DESCRIPTION:
XS GIS Cut Line= 3
 2440667.8014396 7057752.4360878 2435218.7135845 7054087.3397435
     2435217.884     7054086.782
#Sta/Elev= 30
    8528     510    8731   459.2    8806     460    8911   452.3    9051   452.5
    9071     446    9153     444    9238     446    9270     454    9414     457
 9651.96     452    9743     440    9783     440 9849.89   452.8    9910     454
   10014  461.05   10107     452   10483     456   10619     450   10838     450
   10853  456.12   10888     450   11424  451.67   12186     450   12286     458
   14636   460.4   14689     444   14784     444   14821     456   15096  465.17
#Mann= 12 ,-1,0
    8528     .05       0    8806     .06       0    9051     .03       0
    9270    .055       0 9651.96     .03       0 9849.89    .055       0
    9910     .03       0   10107    .055       0   10619     .08       0
   11424     .03       0   12286     .05       0   14636    .035       0
#XS Ineff= 3 ,-1
    8528    9021   453.3                           10014   14839  458.91
Permanent Ineff=
       F       F       F
#Block Obstruct= 1 ,-1
  9714.2  9803.8     444
Bank Sta=9051,9270
XS Rating Curve= 0 ,0
Exp/Cntr=0.3,0.1

Type RM Length L Ch R = 1 ,129432  ,531,521,511
BEGIN DESCRIPTION:
This cross section corresponds to cross section 129258  of the non-georeferenced CDC model which was the source of this model.
NOTE: topo east of railroad tracks updated Feb 2002 by Freese & Nichols, Inc.
END DESCRIPTION:
XS GIS Cut Line= 3
 2441124.2933088   7057349.98873 2435969.8190377 7053904.4992299
     2435950.698     7053891.718
#Sta/Elev= 30
    8755     510    8970     456    9061   455.6    9150     458    9222     454
    9365     454    9414     442    9430     438    9720     438    9792     456
    9908     458    9950     446   10050   451.3   10089     446   10162     446
   10173     454   10210   454.7   10332   450.8   10657     452   10690   457.1
   10752   448.4   11115   457.7   11449   453.8   11700   453.7   11701     450
   12262   453.8   14665   461.7   14734   442.1   14920   442.1   14978   458.9
#Mann= 11 ,-1,0
    8755     .05       0    9061     .06       0    9222     .03       0
    9414     .02       0    9720     .03       0    9950     .06       0
   10210     .05       0   10690    .055       0   11449     .03       0
   12262     .05       0   14665    .035       0
#XS Ineff= 3 ,-1
    8755    9150     458                            9827   14978  458.96
Permanent Ineff=
       F       F       F
#Block Obstruct= 1 ,-1
    9414    9735     442
Bank Sta=9365,9792
XS Rating Curve= 0 ,0
Exp/Cntr=0.5,0.3

Type RM Length L Ch R = 1 ,128911  ,482,553,472
BEGIN DESCRIPTION:
This cross section corresponds to cross section 128738  of the non-georeferenced CDC model which was the source of this model.
NOTE: topo east of railroad tracks updated Feb 2002 by Freese & Nichols, Inc.
END DESCRIPTION:
XS GIS Cut Line= 3
 2441208.8180741 7056775.9377127 2436317.0004299 7053562.2591007
     2436315.329     7053561.161
#Sta/Elev= 30
    9245     510    9461     456    9508     454    9541     454    9569   446.1
    9610     450    9645     446    9730     454    9790     442    9806     438
    9930     438    9946     442   10010     458   10116     458   10225     430
   10239     444   10373     420   10412     405   10520     405   10925     439
   11054     456   11404   455.6   12073   456.4   12674     457   12979   460.4
   14664   456.6   14729   442.1   14960   442.1   15018   455.6   15100   457.1
#Mann= 9 ,-1,0
    9245     .05       0    9508     .03       0    9610     .03       0
    9790     .02       0    9946     .03       0   11404     .05       0
   12073     .03       0   12674     .05       0   14664    .035       0
#XS Ineff= 1 ,-1
   10064   15100  459.93
Permanent Ineff=
       F
#Block Obstruct= 2 ,-1
    9788    9946     442   10178   10966     443
Bank Sta=9730,10010
XS Rating Curve= 0 ,0
Exp/Cntr=0.3,0.1

Type RM Length L Ch R = 1 ,128358  ,536,536,515
BEGIN DESCRIPTION:
This cross section corresponds to cross section 128188  of the non-georeferenced CDC model which was the source of this model.
NOTE: topo east of railroad tracks updated Feb 2002 by Freese & Nichols, Inc.
END DESCRIPTION:
XS GIS Cut Line= 3
  2441425.431486 7056347.4956562 2436882.8477234 7053409.2931993
     2436868.573      7053400.06
#Sta/Elev= 30
    5871   475.8    5980     460    6026     446    6107     446    6172     448
    6263     444    6283     452 6335.19  452.01    6367     444    6391     438
    6540     438    6564     444    6596     452    6744   456.8    6809     444
    6876     439    6964     420    7131     420    7284     435    7313     444
    7552   450.6    7644   453.5    8183   456.9    8796     456    9196   456.8
   10919   452.4   10960   442.1   11185   442.1   11247   456.1   11298   456.9
#Mann= 14 ,-1,0
    5871     .05       0    6026     .07       0    6172     .03       0
 6335.19     .03       0    6367     .02       0    6564     .03       0
    6596     .03       0    6809     .08       0    7552     .05       0
    7644     .03       0    8183     .04       0    8796     .03       0
    9196     .05       0   10919    .035       0
#XS Ineff= 1 ,-1
    6705   11300  457.94
Permanent Ineff=
       F
#Block Obstruct= 2 ,-1
    6809    7373     443    6373    6552     442
Bank Sta=6107,6172
XS Rating Curve= 0 ,0
Exp/Cntr=0.3,0.1

Type RM Length L Ch R = 1 ,127822  ,448,448,437
BEGIN DESCRIPTION:
This cross section corresponds to cross section 127678  of the non-georeferenced CDC model which was the source of this model.
NOTE: topo east of railroad tracks updated Feb 2002 by Freese & Nichols, Inc.
END DESCRIPTION:
XS GIS Cut Line= 3
 2442260.1929399 7056274.7110249 2437430.8216931 7053245.0947088
     2437426.586     7053242.438
#Sta/Elev= 30
    3473   492.6    3530   494.7    3670   507.8    3810     508    3933     478
    4000   465.3    4082     460    4100   454.3    4122   452.9    4247     450
    4267     443    4307     448    4932     451    5000     452    5031     458
    5060     458    5175   457.7    5242     454    5680   454.9    5837   449.3
    5908     450    5926     454    5992     454    6335   455.8    7006   455.8
    8154   456.8    8891   457.9    8953   446.5    8960   442.1    9179   443.1
#Mann= 10 ,-1,0
    3473     .05       0    4247     .03       0    4307     .05       0
    5060     .06       0    5680     .05       0    5992    .035       0
    6335     .04       0    7006     .03       0    8154     .05       0
    8891    .035       0
#XS Ineff= 2 , 0
       0                    5031       0     458
Permanent Ineff=
       F       F
Bank Sta=4247,4307
XS Rating Curve= 0 ,0
Exp/Cntr=0.3,0.1

Type RM Length L Ch R = 1 ,127374  ,454,454,454
BEGIN DESCRIPTION:
This cross section corresponds to cross section 127248 of the non-georeferenced CDC model which was the source of this model.
NOTE: topo east of railroad tracks updated Feb 2002 by Freese & Nichols, Inc.
END DESCRIPTION:
XS GIS Cut Line= 3
 2442769.5603594 7056077.4742146 2437860.5196526 7053058.6187038
     2437846.039     7053049.714
#Sta/Elev= 30
    2280   509.9    2472     510    2652     506    2749     491    2885     464
    2960   460.1    2986     454    3035     450    3097   438.1    3277     435
    3472     438    3539     450    3722     452    3797     458    3859     458
    3938   452.5    4036   450.7    4651     456    4747     454    4811   449.2
    4900     450    4910   453.3    4918     456    4989   456.6    7029   456.5
    7699   455.6    7748   442.1    7975   442.1    8011   455.2    8060   456.7
#Mann= 6 ,-1,0
    2280     .05       0    3035     .03       0    3539     .05       0
    4910     .03       0    7029     .05       0    7699    .035       0
#XS Ineff= 2 , 0
       0                    3771       0     458
Permanent Ineff=
       F       F
Bank Sta=3035,3539
XS Rating Curve= 0 ,0
Exp/Cntr=0.3,0.1

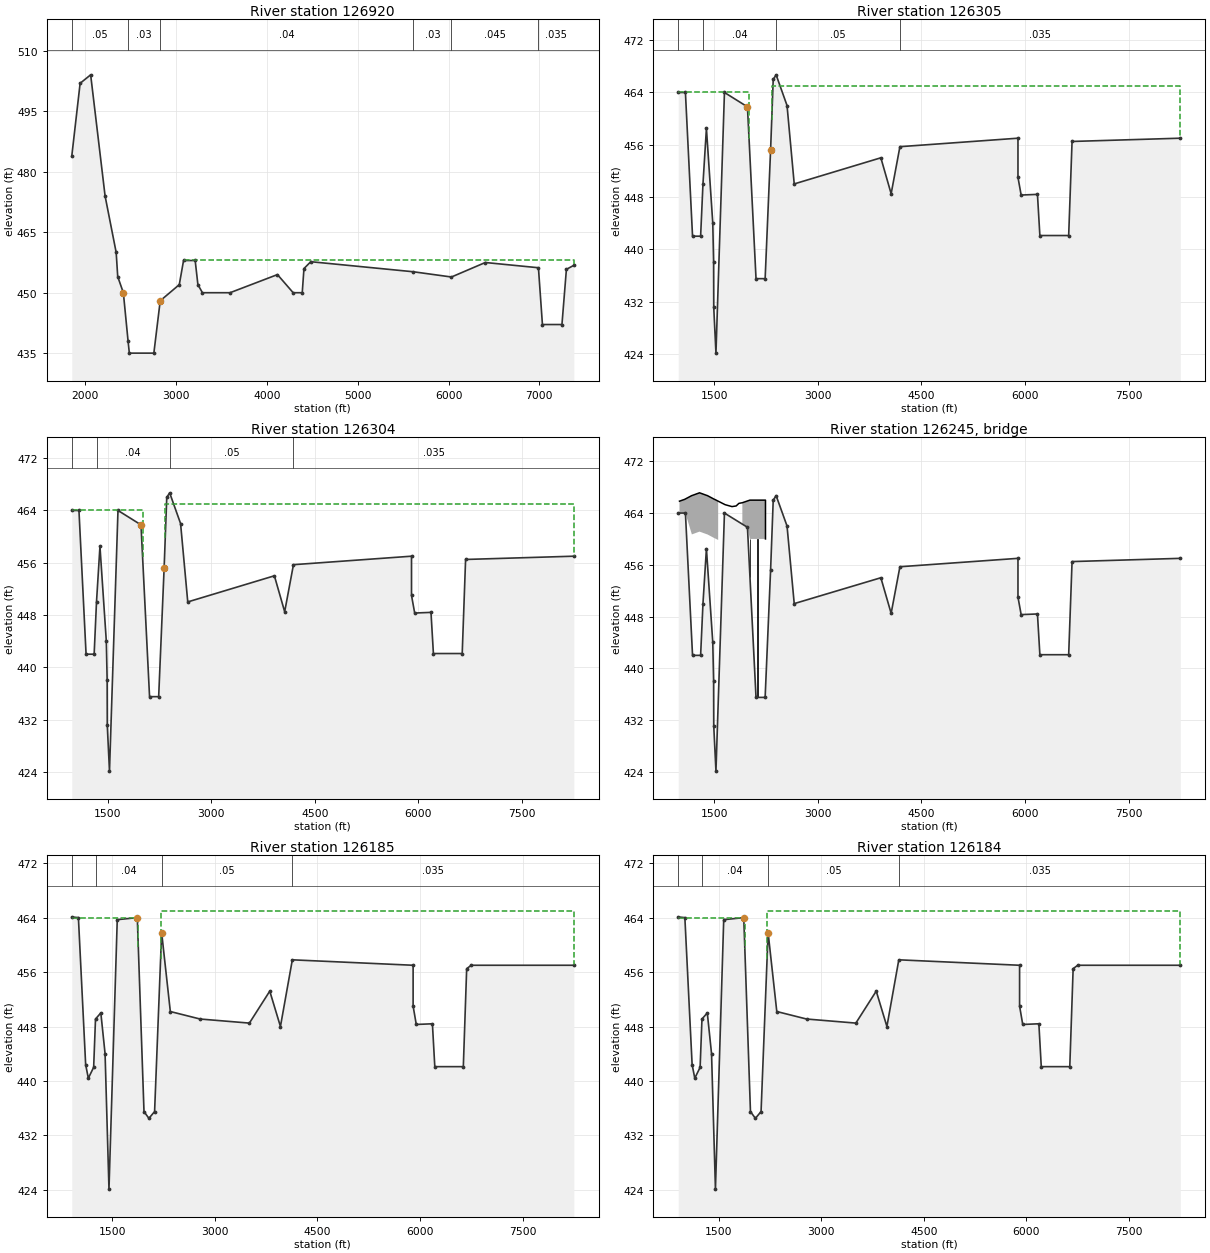
Type RM Length L Ch R = 1 ,126920  ,615,615,615
BEGIN DESCRIPTION:
This cross section corresponds to cross section 126818 of the non-georeferenced CDC model which was the source of this model.
NOTE: topo east of railroad tracks updated Feb 2002 by Freese & Nichols, Inc.
END DESCRIPTION:
XS GIS Cut Line= 3
 2442852.2229238 7055621.4702054 2438214.7194035  7052764.308925
     2438144.906     7052721.297
#Sta/Elev= 30
    1851   483.9    1943     502    2059   504.1    2218     474    2340     460
    2357     454    2419     450    2471     438    2485     435    2755     435
    2825     448    3035     452    3082     458    3210     458    3240     452
    3290     450    3594     450    4116   454.5    4289     450    4389     450
    4408     456    4483   457.7    5613   455.2    6032   453.9    6405   457.5
    6990   456.2    7034   442.1    7249   442.1    7298   455.8    7380   456.8
#Mann= 6 ,-1,0
    1851     .05       0    2471     .03       0    2825     .04       0
    5613     .03       0    6032    .045       0    6990    .035       0
#XS Ineff= 2 , 0
       0                    3082       0     458
Permanent Ineff=
       F       F
Bank Sta=2419,2825
XS Rating Curve= 0 ,0
Exp/Cntr=0.3,0.1

Type RM Length L Ch R = 1 ,126305  ,1,1,1
BEGIN DESCRIPTION:
This cross section corresponds to cross section 126293 of the non-georeferenced CDC model which was the source of this model.
NOTE: topo east of railroad tracks updated Feb 2002 by Freese & Nichols, Inc.
END DESCRIPTION:
XS GIS Cut Line= 4
     2443859.933     7055237.765     2442953.042     7054999.892
     2438876.956     7052407.8682437611.203780877051602.96345922
#Sta/Elev= 30
     982     464    1086     464    1189     442    1306     442    1340     450
    1390   458.5    1482     444    1494   438.1    1496   431.1    1528   424.1
    1651     464    1984   461.8    2108   435.5    2240   435.5    2319   455.2
    2357     466    2399   466.7    2557     462    2661     450    3915     454
    4064   448.5    4191   455.7    5900     457    5900     451    5946   448.3
    6182   448.4    6217   442.1    6634   442.1    6683   456.5    8250     457
#Mann= 4 ,-1,0
     982     .03       0    1340     .04       0    2399     .05       0
    4191    .035       0
#XS Ineff= 2 , 0
       0    2007     464    2335       0     465
Permanent Ineff=
       F       F
#Block Obstruct= 2 , 0
       0    1675                       0
Bank Sta=1984,2319
XS Rating Curve= 0 ,0
Exp/Cntr=0.5,0.3

Type RM Length L Ch R = 1 ,126304  ,119,119,119
BEGIN DESCRIPTION:
This cross section corresponds to cross section 126292 of the non-georeferenced CDC model which was the source of this model.
NOTE: topo east of railroad tracks updated Feb 2002 by Freese & Nichols, Inc.
END DESCRIPTION:
XS GIS Cut Line= 4
     2443860.681     7055237.114      2442953.79     7054999.241
     2438877.704     7052407.2172437611.951780877051602.31245922
#Sta/Elev= 30
     982     464    1086     464    1189     442    1306     442    1340     450
    1390   458.5    1482     444    1494   438.1    1496   431.1    1528   424.1
    1651     464    1984   461.8    2108   435.5    2240   435.5    2319   455.2
    2357     466    2399   466.7    2557     462    2661     450    3915     454
    4064   448.5    4191   455.7    5900     457    5900     451    5946   448.3
    6182   448.4    6217   442.1    6634   442.1    6683   456.5    8250     457
#Mann= 4 ,-1,0
     982     .03       0    1340     .04       0    2399     .05       0
    4191    .035       0
#XS Ineff= 2 , 0
       0    2007     464    2335       0     465
Permanent Ineff=
       F       F
#Block Obstruct= 2 , 0
       0    1675                       0
Bank Sta=1984,2319
XS Rating Curve= 0 ,0
Exp/Cntr=0.5,0.3

Type RM Length L Ch R = 3 ,126245  ,,,
BEGIN DESCRIPTION:
Hebron Parkway
END DESCRIPTION:
Node Name=Hebron Parkway
Bridge Culvert--1,0,-1,-1, 0
Deck Dist Width WeirC Skew NumUp NumDn MinLoCord MaxHiCord MaxSubmerge Is_Ogee
1,117,2.6,0, 25, 25, , , 0.95, 0, 0,0,,
    1000    1069  1071.5    1179  1181.5    1289  1291.5    1400  1402.5    1510
  1512.5    1560    1560    1660    1760    1820    1860    1910    1910    2019
  2021.5    2129  2131.5    2245    2245
  465.84   466.1   466.1  466.71  466.71  467.13  467.13  466.71  466.71   466.1
   466.1  465.84  465.84   465.3     465   465.1   465.5   465.6   465.6     466
     466     466     466     466     460
  459.84   460.1   460.1  460.71  460.71  461.13  461.13  460.71  460.71   460.1
   460.1  459.84  465.84   465.3     465   465.1   465.5   465.6     460     460
     460     460     460     460     460
    1000    1069  1071.5    1179  1181.5    1289  1291.5    1400  1402.5    1510
  1512.5    1560    1560    1660    1760    1820    1860    1910    1910    2019
  2021.5    2129  2131.5    2245    2245
  465.84   466.1   466.1  466.71  466.71  467.13  467.13  466.71  466.71   466.1
   466.1  465.84  465.84   465.3     465   465.1   465.5   465.6   465.6     466
     466     466     466     466     460
  459.84   460.1   460.1  460.71  460.71  461.13  461.13  460.71  460.71   460.1
   460.1  459.84  465.84   465.3     465   465.1   465.5   465.6     460     460
     460     460     460     460     460
Pier Skew, UpSta & Num, DnSta & Num=  ,2020.25, 2 ,2020.25, 2 , 0 , 0 , 0 ,,
     2.5     2.5
       0     461
     2.5     2.5
       0     461
Pier Skew, UpSta & Num, DnSta & Num=  ,2130.25, 2 ,2130.25, 2 , 0 , 0 , 0 ,,
     2.5     2.5
       0     461
     2.5     2.5
       0     461
BR Coef=-1 , 0 , 0 ,, 0 ,,,0.8,-1,,1,
WSPro=,,,, 1 ,,,, 0 ,,,, 0 ,,,,-1 ,-1 ,-1 , 0 , 0 , 0 , 0 , 0
BC Design=,, 0 ,, 0 ,,,,,,
BC HTab HWMax=465.84
BC Use User HTab Curves=0
BC User HTab FreeFlow(D)= 0

Type RM Length L Ch R = 1 ,126185  ,1,1,1
BEGIN DESCRIPTION:
This cross section corresponds to cross section 126172 of the non-georeferenced CDC model which was the source of this model.
NOTE: topo east of railroad tracks updated Feb 2002 by Freese & Nichols, Inc.
END DESCRIPTION:
XS GIS Cut Line= 5
   2443902.55369   7055128.60608   2442995.66312    7054890.7332
   2438885.82357   7052277.24433   2438857.97691   7052259.53635
2437592.224884417051454.63150487
#Sta/Elev= 30
     909   464.1    1006     464    1112   442.4    1151   440.4    1229     442
    1256   449.1    1334     450    1396     444    1453   424.1    1574   463.7
    1867     464    1965   435.5    2037   434.5    2120   435.5    2223   461.8
    2350   450.2    2785   449.1    3506   448.5    3804   453.2    3960     448
    4134   457.8    5900     457    5900     451    5946   448.3    6182   448.4
    6217   442.1    6634   442.1    6683   456.5    6750     457    8250     457
#Mann= 4 ,-1,0
     909     .03       0    1256     .04       0    2223     .05       0
    4134    .035       0
#XS Ineff= 2 , 0
       0    1883     464    2208       0     465
Permanent Ineff=
       F       F
#Block Obstruct= 2 , 0
       0    1676                       0
Bank Sta=1867,2223
XS Rating Curve= 0 ,0
Exp/Cntr=0.5,0.3

Type RM Length L Ch R = 1 ,126184  ,0,0,0
BEGIN DESCRIPTION:
This cross section corresponds to cross section 126171 of the non-georeferenced CDC model which was the source of this model.
NOTE: topo east of railroad tracks updated Feb 2002 by Freese & Nichols, Inc.
END DESCRIPTION:
XS GIS Cut Line= 5
  2443903.383551 7055127.9469142 2442996.4929764 7054890.0740304
 2438886.6534271 7052276.5851629     2438858.807     7052258.877
2437593.061787167051453.96144158
#Sta/Elev= 30
     909   464.1    1006     464    1112   442.4    1151   440.4    1229     442
    1256   449.1    1334     450    1396     444    1453   424.1    1574   463.7
    1867     464    1965   435.5    2037   434.5    2120   435.5    2223   461.8
    2350   450.2    2785   449.1    3506   448.5    3804   453.2    3960     448
    4134   457.8    5900     457    5900     451    5946   448.3    6182   448.4
    6217   442.1    6634   442.1    6683   456.5    6750     457    8250     457
#Mann= 4 ,-1,0
     909     .03       0    1256     .04       0    2223     .05       0
    4134    .035       0
#XS Ineff= 2 , 0
       0    1883     464    2208       0     465
Permanent Ineff=
       F       F
#Block Obstruct= 2 , 0
       0    1676                       0
Bank Sta=1867,2223
XS Rating Curve= 0 ,0
Exp/Cntr=0.5,0.3

River Reach=Elm Fork        ,ef4
Reach XY= 30
      2440400.92      7060482.14      2440294.34      7060015.81
      2440383.31      7059829.47      2440522.78      7059722.76
       2441002.8      7059601.84      2441288.86      7059672.27
      2441563.46      7059658.68      2442618.16      7059389.23
      2443182.24      7059147.58      2443412.14      7059147.38
      2444167.74      7059322.94       2444519.5      7059508.74
      2444888.28      7059871.88      2445091.58       7059858.5
      2445209.51      7059732.61      2445240.46      7059490.37
      2445053.22      7058713.77      2445282.96      7058007.48
      2445208.63      7057633.68      2444876.01      7057035.28
      2444665.63      7056828.23      2444188.86      7056797.96
      2443742.29      7057037.22        2443575.       7056962.7
      2443517.68      7056772.63      2443507.66      7056384.86
      2443297.03      7055905.67      2443242.05      7055579.44
      2443287.84      7055196.61      2443507.86      7054781.77