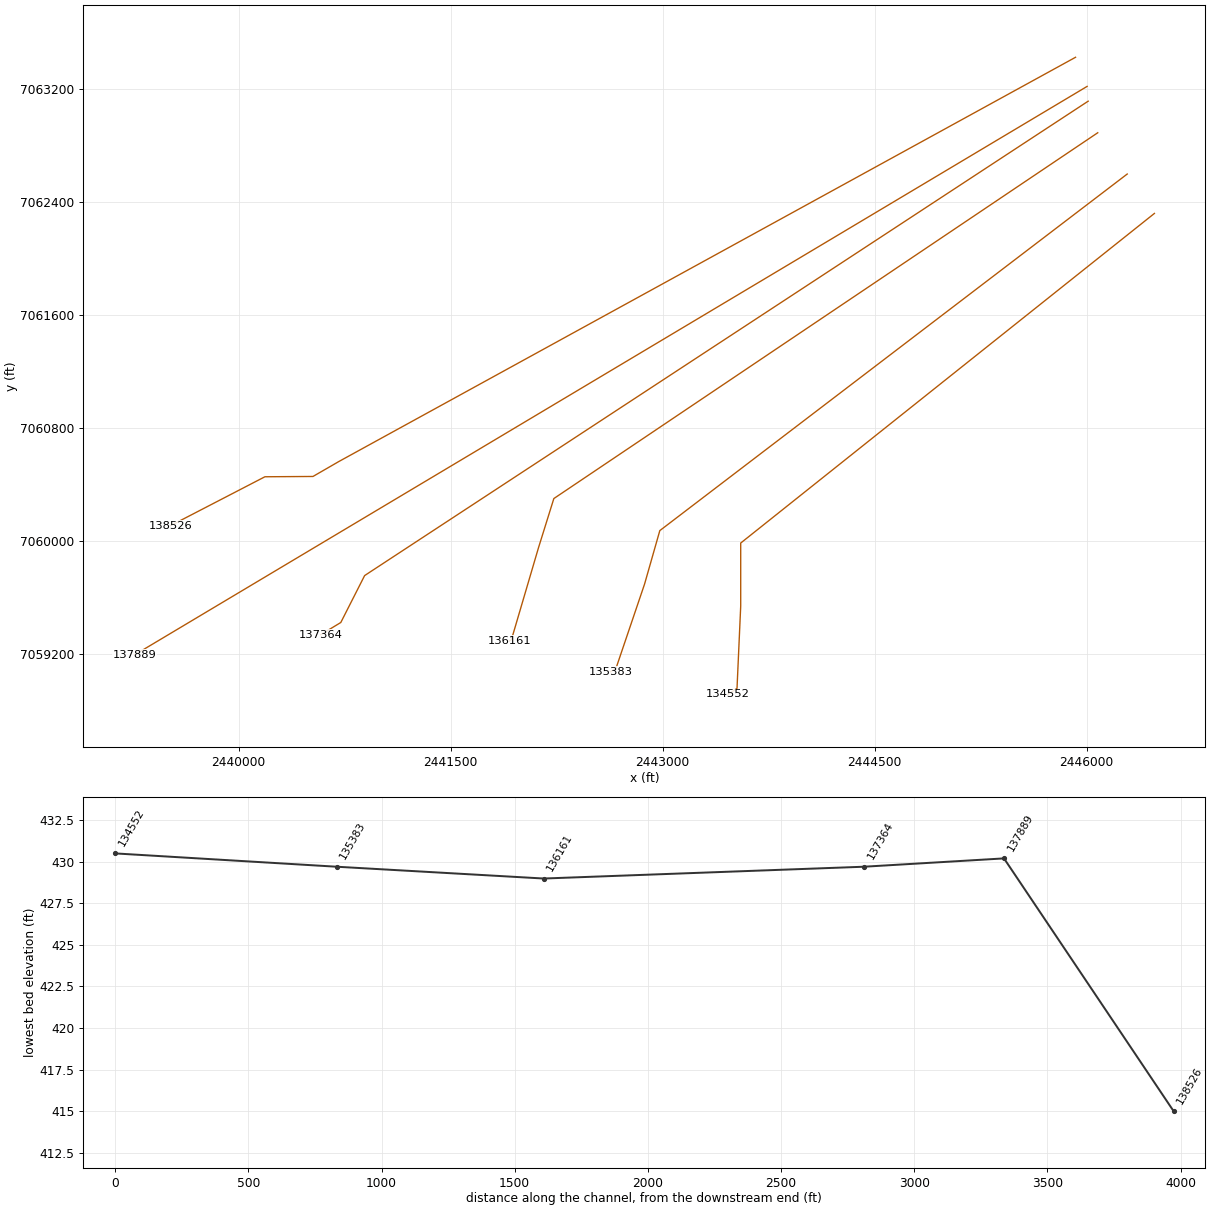
HEC-RAS study CDC_Consolidated_Model.prj: Upper Trinity CDC Consolidated Model

--- CDC_Consolidated_Model.g01 (geometry) --- (continued)

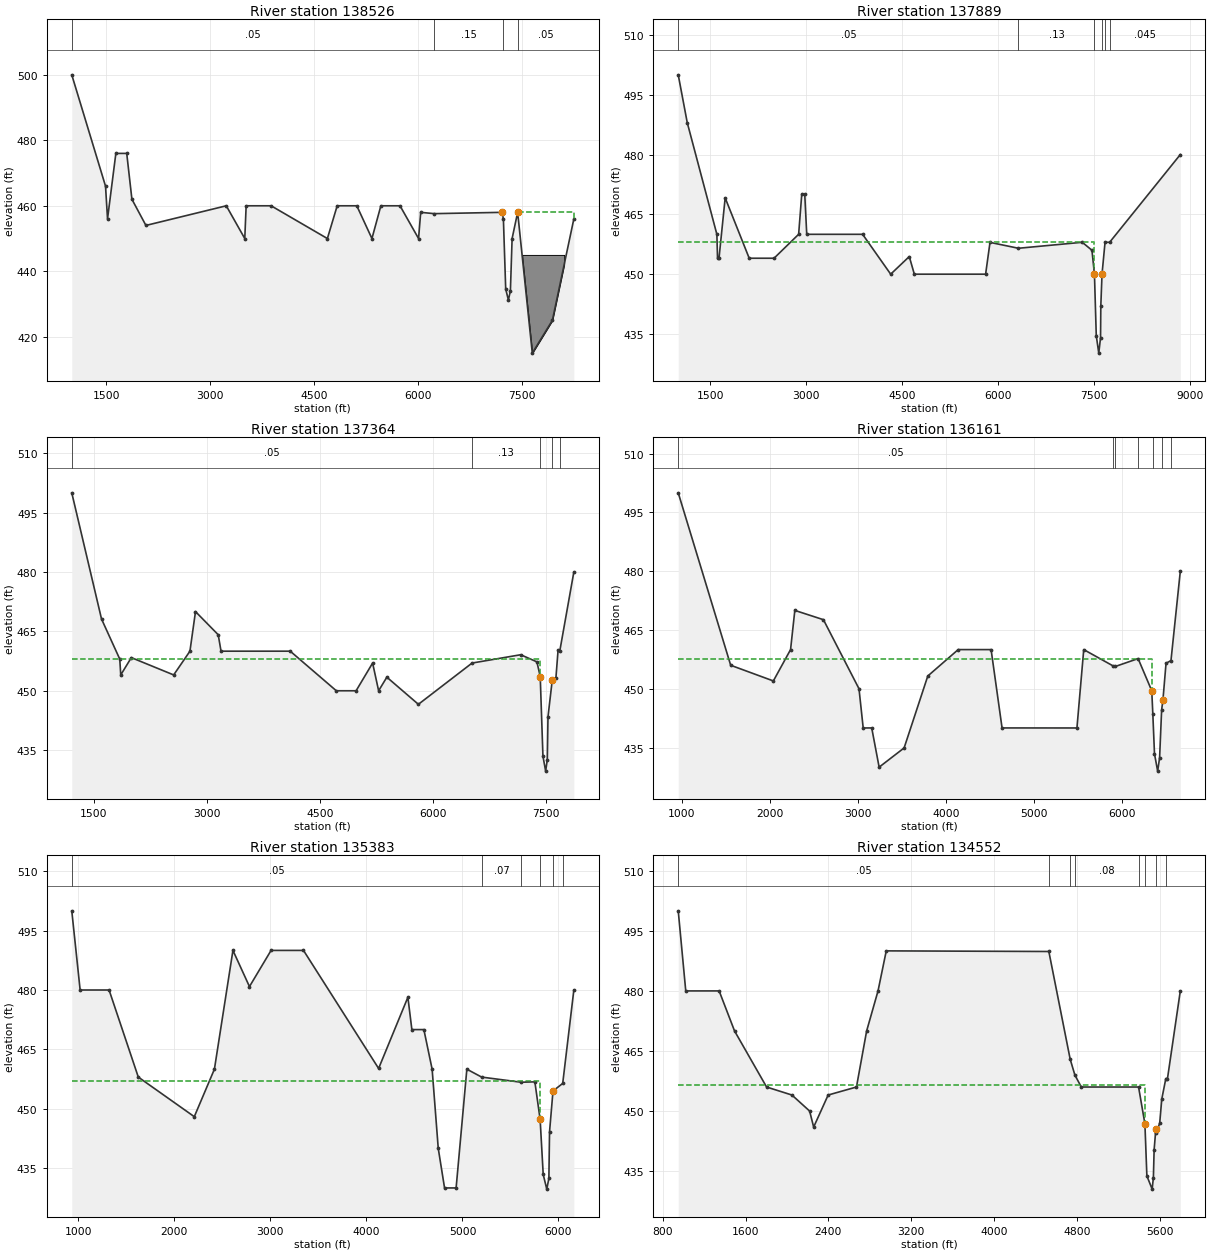
Type RM Length L Ch R = 1 ,138526  ,421,637,701
BEGIN DESCRIPTION:
This cross section corresponds to cross section 138514 of the non-georeferenced CDC model which was the source of this model.
ROCK RIP RAP PORTION OF POND
END DESCRIPTION:
XS GIS Cut Line= 6
   2445920.99665   7063424.07033  2441687.507077 7061098.8896967
 2440710.5710391 7060562.3222003 2440526.5969976 7060455.9730036
 2440186.7151314  7060453.884097 2439518.1777546 7060107.3303281
#Sta/Elev= 30
    1000     5001487.401     4661516.302     4561636.653     4761793.639     476
1868.329     4622070.719     4543231.114     4603498.249     4503518.073     460
3878.572     4604691.068     4504832.649     460 5115.82     4605334.396     450
5463.418     4605739.785     4606007.649     4506038.542     458    6235   457.6
  7212.6     458  7232.7     456    7266   434.6    7305  431.19    7334   434.1
  7358.5     450  7438.6     458    7650     415    7940     425    8250     456
#Mann= 4 ,-1,0
    1000     .05       0    6235     .15       0  7232.7     .04       0
  7438.6     .05       0
#XS Ineff= 2 , 0
       0  7212.6     458  7438.6       0     458
Permanent Ineff=
       F       F
#Block Obstruct= 1 ,-1
    7505    8110     445
Bank Sta=7212.6,7438.6
XS Rating Curve= 0 ,0
Exp/Cntr=0.3,0.1

Type RM Length L Ch R = 1 ,137889  ,319,525,669
BEGIN DESCRIPTION:
This cross section corresponds to cross section 137878 of the non-georeferenced CDC model which was the source of this model.
END DESCRIPTION:
XS GIS Cut Line= 3
     2446002.735   7063217.85355  2441817.580308 7060717.8327161
 2439263.5631063 7059192.1792713
#Sta/Elev= 30
    1000     5001140.983     4881604.058     4601614.375     4541637.325     454
1733.895469.13912109.635     4542497.949     4542882.506     4602931.008     470
2978.196     4703009.224     4603882.662     4604321.727     4504612.306454.4227
4691.324     4505805.794     450 5874.59 457.977    6319   456.5  7316.8     458
  7468.5     456  7507.5     450    7536   434.6    7575   430.2    7603   434.1
    7607     442  7625.8     450  7673.2     458    7745     458    8850     480
#Mann= 6 ,-1,0
    1000     .05       0    6319     .13       0  7507.5     .04       0
  7625.8      .1       0  7673.2     .07       0    7745    .045       0
#XS Ineff= 2 , 0
       0  7507.5     458  7625.8       0     450
Permanent Ineff=
       F       F
Bank Sta=7507.5,7625.8
XS Rating Curve= 0 ,0
Exp/Cntr=0.3,0.1

Type RM Length L Ch R = 1 ,137364  ,1233,1203,1183
BEGIN DESCRIPTION:
This cross section corresponds to cross section 137352 of the non-georeferenced CDC model which was the source of this model.
END DESCRIPTION:
XS GIS Cut Line= 5
   2446010.16478   7063113.17693  2441821.632137  7060364.305536
 2440892.0168704 7059754.2129241 2440723.4860395 7059421.9852421
 2440581.9295641 7059336.1704531
#Sta/Elev= 30
    1210     5001604.655468.13281846.536     4581859.607     4542000.286458.3746
2561.672     4542777.542     460 2851.19     4703152.595464.15243189.918     460
4108.099     4604719.196     4504981.615     450 5200.63457.0022 5280.35     450
5389.495453.43115807.923446.5769    6520     457    7165   459.1    7380   457.3
    7424   453.6    7460   433.5    7496   429.7    7518   432.6    7527   443.4
    7583   452.6    7632   453.2    7661   460.3    7684   460.1    7870     480
#Mann= 5 ,-1,0
    1210     .05       0    6520     .13       0    7424     .05       0
    7583      .1       0    7684    .045       0
#XS Ineff= 2 , 0
       0    7424     458    7583       0   452.6
Permanent Ineff=
       F       F
Bank Sta=7424,7583
XS Rating Curve= 0 ,0
Exp/Cntr=0.3,0.1

Type RM Length L Ch R = 1 ,136161  ,789,778,759
BEGIN DESCRIPTION:
This cross section corresponds to cross section 136149 of the non-georeferenced CDC model which was the source of this model.
END DESCRIPTION:
XS GIS Cut Line= 5
   2446077.87363   7062889.65277  2442230.476463 7060299.5599306
 2442123.0035817 7059955.0340448 2441930.7880868 7059301.5041839
 2441915.9967778 7059291.4418681
#Sta/Elev= 30
     962     5001557.286     4562041.457     4522236.795     4602285.182     470
2609.802467.62933013.416 450.0123061.105     440 3157.84 440.0123241.932     430
  3525.5 434.9083794.254453.26014139.198     4604512.671     4604637.029440.0103
5486.837     4405563.988     460    5900   455.8    5923   455.7    6181   457.7
    6336   449.5    6348   443.6    6367   433.4    6403  428.99    6425   432.4
    6448   444.6    6463   447.2    6498   456.5    6554   457.2    6660     480
#Mann= 7 ,-1,0
     962     .05       0    5900      .1       0    5923     .07       0
    6181      .1       0    6348     .05       0    6448      .1       0
    6554    .045       0
#XS Ineff= 2 , 0
       0    6336   457.5    6463       0   447.2
Permanent Ineff=
       F       F
Bank Sta=6336,6463
XS Rating Curve= 0 ,0
Exp/Cntr=0.3,0.1

Type RM Length L Ch R = 1 ,135383  ,729,831,849
BEGIN DESCRIPTION:
This cross section corresponds to cross section 135370 of the non-georeferenced CDC model which was the source of this model.
END DESCRIPTION:
XS GIS Cut Line= 6
   2446286.48378   7062597.42238  2443061.265156 7060134.6337512
 2442980.1465524 7060072.6912898 2442872.0201283 7059693.3967728
 2442670.8151501  7059099.678144 2442632.0845845 7059073.6201252
#Sta/Elev= 30
     932     5001019.138     4801320.523     480 1624.75     4582207.872     448
2417.369     4602610.204     4902782.302480.86223007.138     4903344.886     490
4127.077460.18314431.959478.16654473.341     4704598.328     4704684.343     460
4748.019     4404813.729     4304934.143     4305045.907     460    5200     458
    5611   456.7    5754   456.8    5809   447.3    5841   433.4    5878   429.7
    5900   432.4    5907   444.2    5943   454.5    6044   456.4    6160     480
#Mann= 6 ,-1,0
     932     .05       0    5200     .07       0    5611      .1       0
    5809     .05       0    5943     .08       0    6044    .045       0
#XS Ineff= 2 , 0
       0    5809     457    5943       0   454.5
Permanent Ineff=
       F       F
Bank Sta=5809,5943
XS Rating Curve= 0 ,0
Exp/Cntr=0.3,0.1

Type RM Length L Ch R = 1 ,134552  ,821,905,921
BEGIN DESCRIPTION:
This cross section corresponds to cross section 134538 of the non-georeferenced CDC model which was the source of this model.
END DESCRIPTION:
XS GIS Cut Line= 6
2446478.774475797062318.488174322443679.896793347060086.29559331
2443552.315027517059984.545140642443552.315027517059537.52208455
2443526.172035167058955.517014972443461.993029687058912.61683831
#Sta/Elev= 30
     950     5001022.603     4801345.108     4801493.955     4701803.493     456
2048.101     4542219.146     4502258.179     4462398.165     4542671.638     456
2769.915     470 2879.97     4802959.483     490    4530489.8436 4736.19462.9355
4781.939458.95964843.612     4565396.818     456    5458   446.8    5477   433.8
    5528   430.5    5540   433.4    5547   440.3    5564   445.6    5568   444.5
    5601     447    5621     453    5660   458.1    5676   458.1    5800     480
#Mann= 8 ,-1,0
     950     .05       0    4530     .05       0 4736.19     .03       0
4781.939     .08       05396.818      .1       0    5458     .05       0
    5568     .09       0    5660    .045       0
#XS Ineff= 2 , 0
       0    5458   456.5    5564       0   445.6
Permanent Ineff=
       F       F
Bank Sta=5458,5564
XS Rating Curve= 0 ,0
Exp/Cntr=0.3,0.1