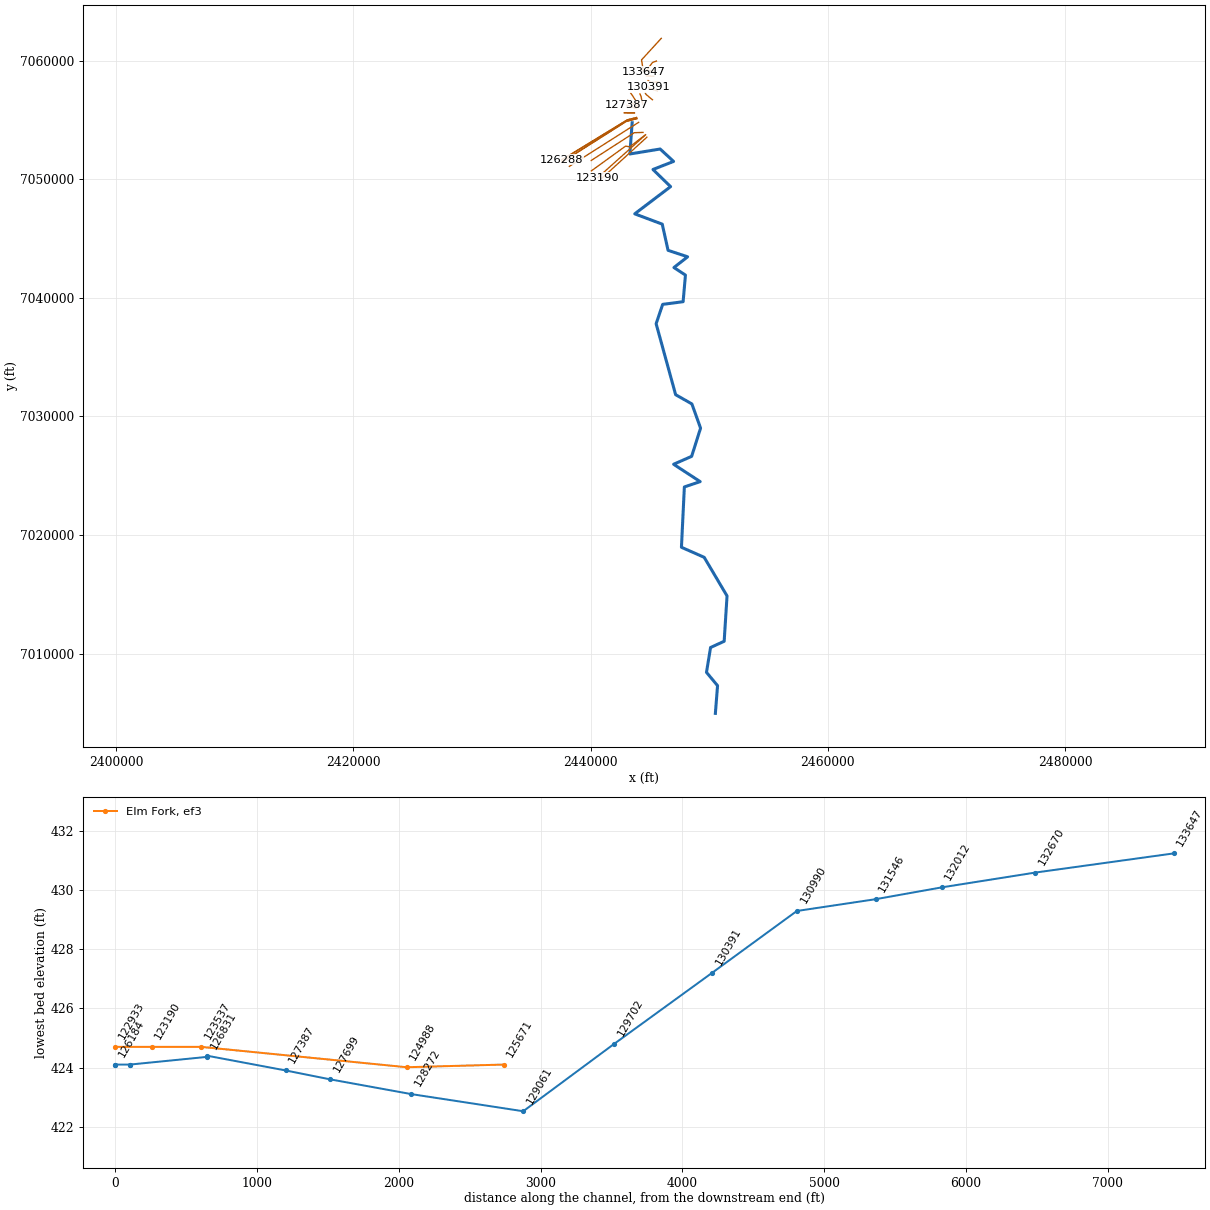
HEC-RAS study CDC_Consolidated_Model.prj: Upper Trinity CDC Consolidated Model

--- CDC_Consolidated_Model.g01 (geometry) --- (continued)

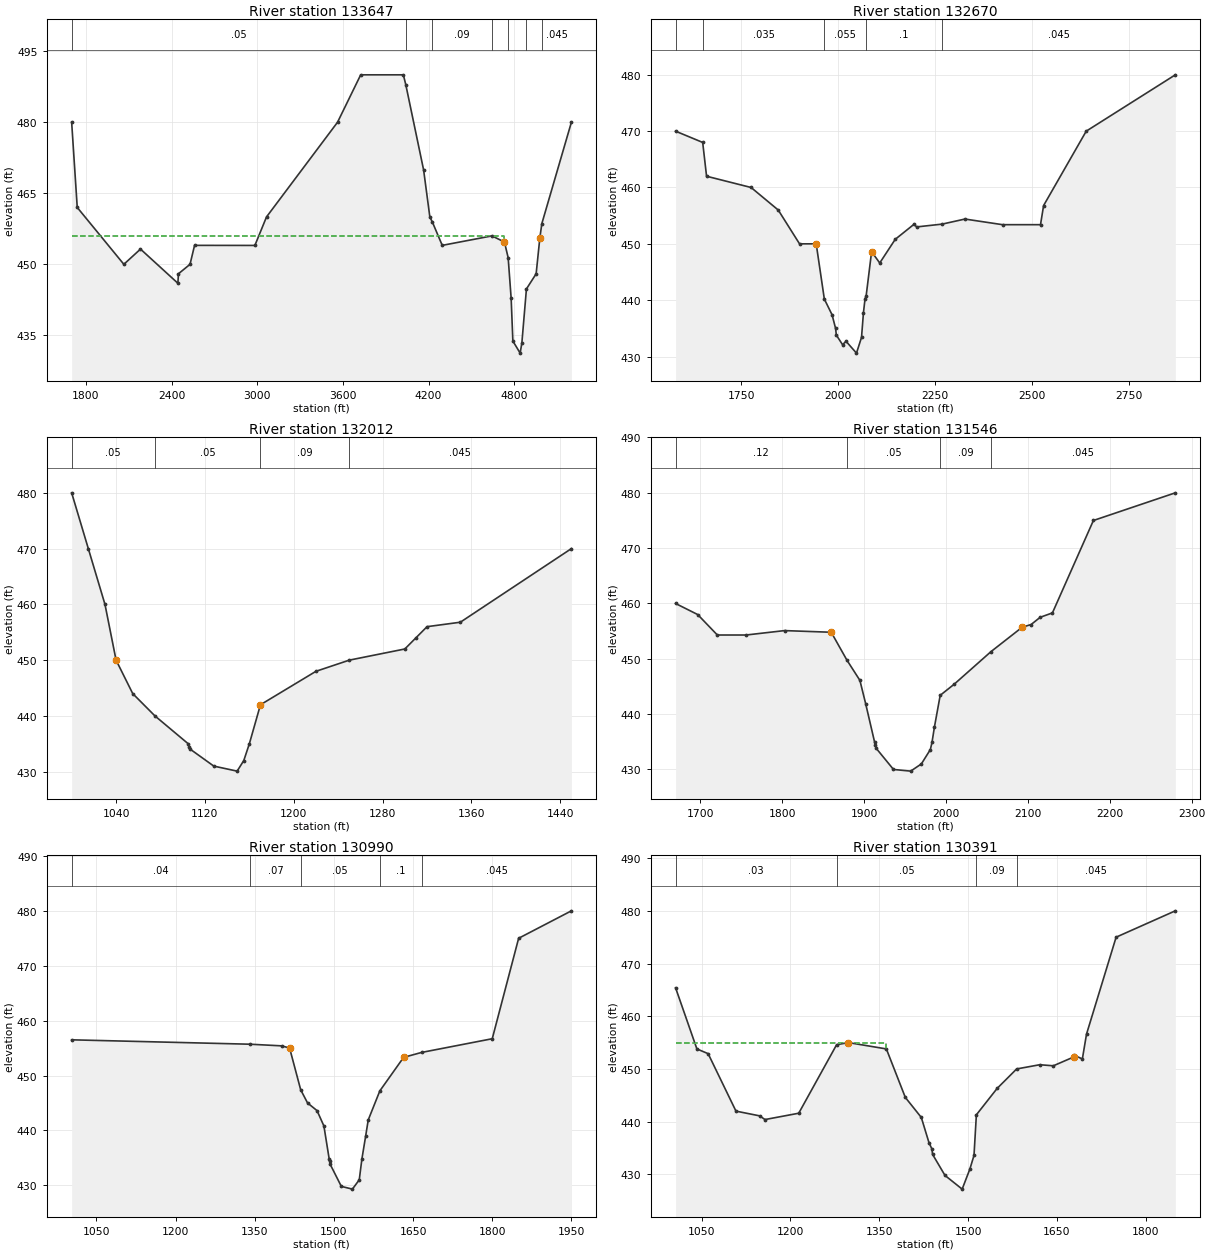
Type RM Length L Ch R = 1 ,133647  ,999,977,649
BEGIN DESCRIPTION:
This cross section corresponds to cross section 133634 of the non-georeferenced CDC model which was the source of this model.
---------------------------------------------------------------------
CDC LEW063011-1 Camelot Landfill
Cross-section 133634 - 134538
Located in LOB.
---------------------------------------------------------------------
END DESCRIPTION:
XS GIS Cut Line= 5
2445960.838502867061901.407539022444382.196241777060174.12973522
2444297.873903847060081.868108722444362.306845847059695.54407822
2444448.880491587059058.04600938
#Sta/Elev= 30
    1700     4801739.155     462 2065.52     4502182.107453.21262444.073     446
2447.858     4482529.027     4502560.779     4542983.234453.98473064.632     460
3562.264     4803724.297     490 4023.01     490    4040487.9333 4164.99469.9083
4208.559     4604226.869458.8767 4295.42     4544643.583     456    4731   454.7
    4757   451.4    4778   442.8    4790   433.8    4841  431.25    4853   433.4
    4885   444.8    4953     448    4979   455.6    4993   458.6    5200     480
#Mann= 7 ,-1,0
    1700     .05       0    4040     .05       04226.869     .09       0
4643.583     .11       0    4757     .04       0    4885     .12       0
    4993    .045       0
#XS Ineff= 2 , 0
       0    4731     456    4979       0   455.6
Permanent Ineff=
       F       F
Bank Sta=4731,4979
XS Rating Curve= 0 ,0
Exp/Cntr=0.3,0.1

Type RM Length L Ch R = 1 ,132670  ,730,658,430
BEGIN DESCRIPTION:
This cross section corresponds to cross section 132656 of the non-georeferenced CDC model which was the source of this model.
---------------------------------------------------------------------
CDC CAR110497-1 Coyote Ridge Golf Club
Cross-section 132656
Project located in LOB.
---------------------------------------------------------------------
END DESCRIPTION:
XS GIS Cut Line= 3
2445552.465554747059984.042845062445224.724740427059868.39478238
 2444662.00178457059112.37824979
#Sta/Elev= 30
    1580     470    1650     468    1660     462    1775     460    1845     456
    1900     450    1943     450    1964   440.2    1984   437.4    1993     435
    1995   433.8    2011   432.1    2020   432.7    2047   430.6    2060   433.4
    2065   437.8    2069   440.2    2072   440.8    2086   448.6    2107   446.6
    2147   450.8    2196   453.5    2202     453    2268   453.5    2327   454.4
    2424   453.4    2522   453.4    2530   456.8    2640     470    2870     480
#Mann= 5 ,-1,0
    1580     .05       0    1650    .035       0    1964    .055       0
    2072      .1       0    2268    .045       0
#XS Ineff= 2 , 0
       0    1943     450    2086       0   448.6
Permanent Ineff=
       F       F
Bank Sta=1943,2086
XS Rating Curve= 0 ,0
Exp/Cntr=0.3,0.1

Type RM Length L Ch R = 1 ,132012  ,460,466,450
BEGIN DESCRIPTION:
This cross section corresponds to cross section 131998 of the non-georeferenced CDC model which was the source of this model.
END DESCRIPTION:
XS GIS Cut Line= 2
2445280.482174847059168.430959212444830.489636517059165.79874663
#Sta/Elev= 21
    1000     480    1015     470    1030     460    1040     450    1055     444
    1075     440    1105     435    1106   434.4    1107     434    1128     431
    1149   430.1    1155     432    1160     435    1170     442    1220     448
    1250     450    1300     452    1310     454    1320     456    1350   456.8
    1450     470
#Mann= 4 ,-1,0
    1000     .05       0    1075     .05       0    1170     .09       0
    1250    .045       0
#XS Ineff= 2 , 0
       0    1040     450    1170       0     442
Permanent Ineff=
       F       F
Bank Sta=1040,1170
XS Rating Curve= 0 ,0
Exp/Cntr=0.3,0.1

Type RM Length L Ch R = 1 ,131546  ,541,556,451
BEGIN DESCRIPTION:
This cross section corresponds to cross section 131532 of the non-georeferenced CDC model which was the source of this model.
END DESCRIPTION:
XS GIS Cut Line= 2
2445331.159238857058704.210430962444721.515773097058725.04995622
#Sta/Elev= 27
    1670     460    1697     458    1721   454.3    1756   454.3    1803   455.1
    1860   454.8    1879   449.8    1895   446.1    1902   441.9    1913   434.9
    1914   434.4    1915   433.8    1936     430    1957   429.7    1970     431
    1981   433.6    1983   434.9    1986   437.7    1993   443.4    2010   445.4
    2055   451.3    2093   455.7    2104   456.2    2115   457.5    2130   458.3
    2180     475    2280     480
#Mann= 4 ,-1,0
    1670     .12       0    1879     .05       0    1993     .09       0
    2055    .045       0
#XS Ineff= 2 , 0
       0    1860   454.8    2093       0   455.7
Permanent Ineff=
       F       F
Bank Sta=1860,2093
XS Rating Curve= 0 ,0
Exp/Cntr=0.3,0.1

Type RM Length L Ch R = 1 ,130990  ,729,599,449
BEGIN DESCRIPTION:
This cross section corresponds to cross section 130977 of the non-georeferenced CDC model which was the source of this model.
END DESCRIPTION:
XS GIS Cut Line= 3
2445752.870665767058224.918082462445075.839867597058183.76823038
2444852.991231927058333.93065971
#Sta/Elev= 23
    1003   456.5    1341   455.7    1401   455.4    1416     455    1437   447.4
    1450     445    1468   443.6    1481   440.8    1491   434.8    1492   434.4
    1493   433.8    1514   429.8    1535   429.3    1548     431    1553   434.8
    1560   438.9    1565   441.9    1587   447.2    1632   453.3    1666   454.2
    1800   456.7    1850     475    1950     480
#Mann= 5 ,-1,0
    1003     .04       0    1341     .07       0    1437     .05       0
    1587      .1       0    1666    .045       0
#XS Ineff= 2 , 0
       0    1416     455    1632       0   453.3
Permanent Ineff=
       F       F
Bank Sta=1416,1632
XS Rating Curve= 0 ,0
Exp/Cntr=0.3,0.1

Type RM Length L Ch R = 1 ,130391  ,821,689,501
BEGIN DESCRIPTION:
This cross section corresponds to cross section 130377 of the non-georeferenced CDC model which was the source of this model.
END DESCRIPTION:
XS GIS Cut Line= 3
2445633.120905257057454.420279642444989.106117167057689.21803838
2444867.026636937057790.33496213
#Sta/Elev= 30
    1006   465.4    1042   453.8    1061   452.9    1108     442    1148   441.1
    1157   440.4    1214   441.6    1278   454.6    1298     455    1362   453.8
    1394   444.6    1421   440.8    1434     436    1439   434.8    1440   433.8
    1461   429.8    1490   427.2    1503     431    1510   433.6    1514   441.3
    1549   446.3    1582     450    1621   450.8    1644   450.6    1679   452.3
    1679   452.6    1693   451.9    1700   456.6    1750     475    1850     480
#Mann= 4 ,-1,0
    1006     .03       0    1278     .05       0    1514     .09       0
    1582    .045       0
#XS Ineff= 2 , 0
       0    1362     455    1679       0   452.3
Permanent Ineff=
       F       F
Bank Sta=1298,1679
XS Rating Curve= 0 ,0
Exp/Cntr=0.3,0.1

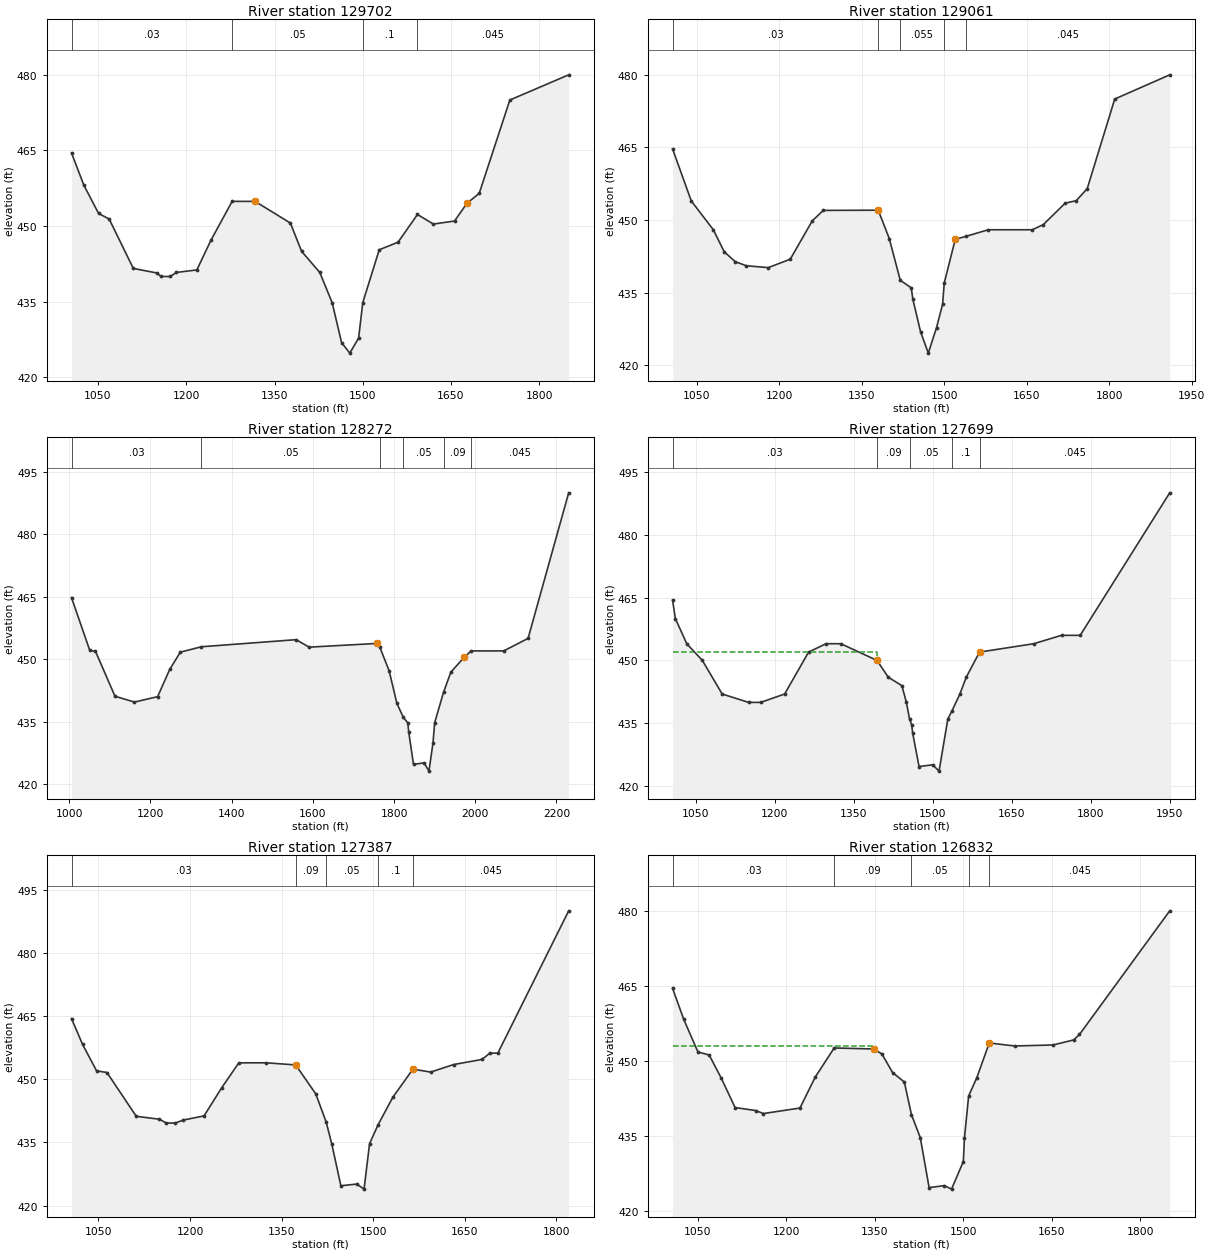
Type RM Length L Ch R = 1 ,129702  ,840,641,450
BEGIN DESCRIPTION:
This cross section corresponds to cross section 129689 of the non-georeferenced CDC model which was the source of this model.
END DESCRIPTION:
XS GIS Cut Line= 3
2445219.482624927056715.184881462444689.060129347057160.73910847
2444611.97891867 7057292.0649613
#Sta/Elev= 30
    1005   464.5    1026   458.1    1051   452.5    1069   451.4    1110   441.6
    1150   440.7    1157     440    1173     440    1183   440.8    1218   441.3
    1242   447.2    1278   454.9    1317   454.9    1377   450.6    1396     445
    1427   440.8    1448   434.8    1464   426.9    1478   424.8    1493   427.8
    1500   434.8    1528   445.3    1560   446.8    1593   452.3    1620   450.4
    1656     451    1677   454.5    1698   456.5    1750     475    1850     480
#Mann= 4 ,-1,0
    1005     .03       0    1278     .05       0    1500      .1       0
    1593    .045       0
#XS Ineff= 2 , 0
       0    1317   454.6    1677       0   454.5
Permanent Ineff=
       F       F
Bank Sta=1317,1677
XS Rating Curve= 0 ,0
Exp/Cntr=0.3,0.1

Type RM Length L Ch R = 1 ,129061  ,400,789,800
BEGIN DESCRIPTION:
This cross section corresponds to cross section 129048 of the non-georeferenced CDC model which was the source of this model.
END DESCRIPTION:
XS GIS Cut Line= 3
2444391.83697051 7056338.82474182444256.431073347057007.48022863
2444161.65501618 7057207.9804838
#Sta/Elev= 30
    1006   464.7    1040  453.95    1080  448.02    1100  443.44    1120  441.41
    1140  440.57    1180  440.18    1220  441.92    1260  449.84    1280     452
    1380  452.04    1400  446.19    1420  437.57    1440     436    1443   433.6
    1457   426.9    1471  422.52    1486   427.8    1497   432.6    1500     437
    1520  446.02    1540  446.66    1580     448    1660     448    1680  449.06
    1720   453.5    1740     454    1760   456.5    1810     475    1910     480
#Mann= 5 ,-1,0
    1006     .03       0    1380      .1       0    1420    .055       0
    1500      .1       0    1540    .045       0
#XS Ineff= 2 , 0
       0    1380  452.04    1520       0  446.02
Permanent Ineff=
       F       F
Bank Sta=1380,1520
XS Rating Curve= 0 ,0
Exp/Cntr=0.3,0.1

Type RM Length L Ch R = 1 ,128272  ,220,573,750
BEGIN DESCRIPTION:
This cross section corresponds to cross section 128259 of the non-georeferenced CDC model which was the source of this model.
END DESCRIPTION:
XS GIS Cut Line= 3
2444054.734626357056258.631988792443537.38789201 7057070.5280028
2443385.42690983 7057283.0767903
#Sta/Elev= 30
    1006   464.8    1051   452.1    1065   451.9    1113   441.1    1161   439.7
    1218     441    1248   447.6    1274   451.7    1326     453    1559   454.7
    1591   452.9    1759   453.8    1765   452.9    1788   447.2    1807   439.4
    1823     436    1834   434.7    1836   432.6    1848   424.7    1874   425.1
    1886   423.1    1896   429.9    1900   434.7    1922   442.1    1940   446.9
    1973   450.5    1990     452    2070     452    2130     455    2230     490
#Mann= 6 ,-1,0
    1006     .03       0    1326     .05       0    1765     .09       0
    1823     .05       0    1922     .09       0    1990    .045       0
#XS Ineff= 2 , 0
       0    1759   453.5    1973       0   450.5
Permanent Ineff=
       F       F
Bank Sta=1759,1973
XS Rating Curve= 0 ,0
Exp/Cntr=0.3,0.1

Type RM Length L Ch R = 1 ,127699  ,250,312,350
BEGIN DESCRIPTION:
This cross section corresponds to cross section 127686 of the non-georeferenced CDC model which was the source of this model.
END DESCRIPTION:
XS GIS Cut Line= 3
2443932.347403917056168.207957042443528.493880937056421.38592838
2443135.312252587056674.01764096
#Sta/Elev= 30
    1006   464.4  1011.3     460  1032.9     454  1062.6     450  1100.2     442
  1150.4     440  1173.4     440  1218.8     442  1264.3     452  1297.3     454
  1325.5     454  1394.4     450  1415.5     446  1441.4     444    1450     440
    1456     436    1460   434.7    1462   432.6    1474   424.7    1500   425.1
    1512   423.6  1528.6     436  1536.6     438  1551.6     442  1563.6     446
  1588.9     452  1691.8     454  1744.5     456    1780     456    1950     490
#Mann= 5 ,-1,0
    1006     .03       0  1394.4     .09       0    1456     .05       0
  1536.6      .1       0  1588.9    .045       0
#XS Ineff= 2 , 0
       0  1394.4     452  1588.9       0     452
Permanent Ineff=
       F       F
Bank Sta=1394.4,1588.9
XS Rating Curve= 0 ,0
Exp/Cntr=0.3,0.1

Type RM Length L Ch R = 1 ,127387  ,450,555,590
BEGIN DESCRIPTION:
This cross section corresponds to cross section 127374 of the non-georeferenced CDC model which was the source of this model.
END DESCRIPTION:
XS GIS Cut Line= 2
 2443829.11401467055991.458310542443060.813385847056260.36361264
#Sta/Elev= 30
    1006   464.4    1024   458.3    1047     452    1064   451.6    1112   441.2
    1150   440.5    1161   439.6    1176   439.6    1189   440.3    1223   441.3
    1252     448    1280   453.9    1325   453.9    1373   453.4    1406   446.5
    1423   439.8    1432   434.7    1447   424.7    1473   425.1    1485   423.9
    1494   434.7    1508   439.2    1532   445.7    1565   452.4    1594   451.7
    1632   453.5    1678   454.7    1691   456.2    1704   456.2    1820     490
#Mann= 5 ,-1,0
    1006     .03       0    1373     .09       0    1423     .05       0
    1508      .1       0    1565    .045       0
#XS Ineff= 2 , 0
       0    1373     453    1565       0   452.4
Permanent Ineff=
       F       F
Bank Sta=1373,1565
XS Rating Curve= 0 ,0
Exp/Cntr=0.3,0.1

Type RM Length L Ch R = 1 ,126832  ,1,1,1
BEGIN DESCRIPTION:
This cross section corresponds to cross section 126819 of the non-georeferenced CDC model which was the source of this model.
END DESCRIPTION:
XS GIS Cut Line= 2
     2443695.892     7055604.893     2442853.075     7055622.452
#Sta/Elev= 30
    1007   464.5    1026   458.3    1050   451.8    1069   451.2    1089   446.7
    1113   440.7    1148   440.1    1161   439.5    1223   440.6    1249   446.8
    1281   452.6    1348   452.4    1362   451.4    1380   447.7    1400   445.8
    1412   439.3    1427   434.7    1442   424.7    1468   425.1    1480   424.4
    1500   429.9    1502   434.7    1509     443    1523   446.7    1544   453.6
    1587     453    1652   453.2    1687   454.2    1697   455.3    1850     480
#Mann= 5 ,-1,0
    1007     .03       0    1281     .09       0    1412     .05       0
    1509     .08       0    1544    .045       0
#XS Ineff= 2 , 0
       0    1348     453    1544       0   453.6
Permanent Ineff=
       F       F
Bank Sta=1348,1544
XS Rating Curve= 0 ,0
Exp/Cntr=0.3,0.1

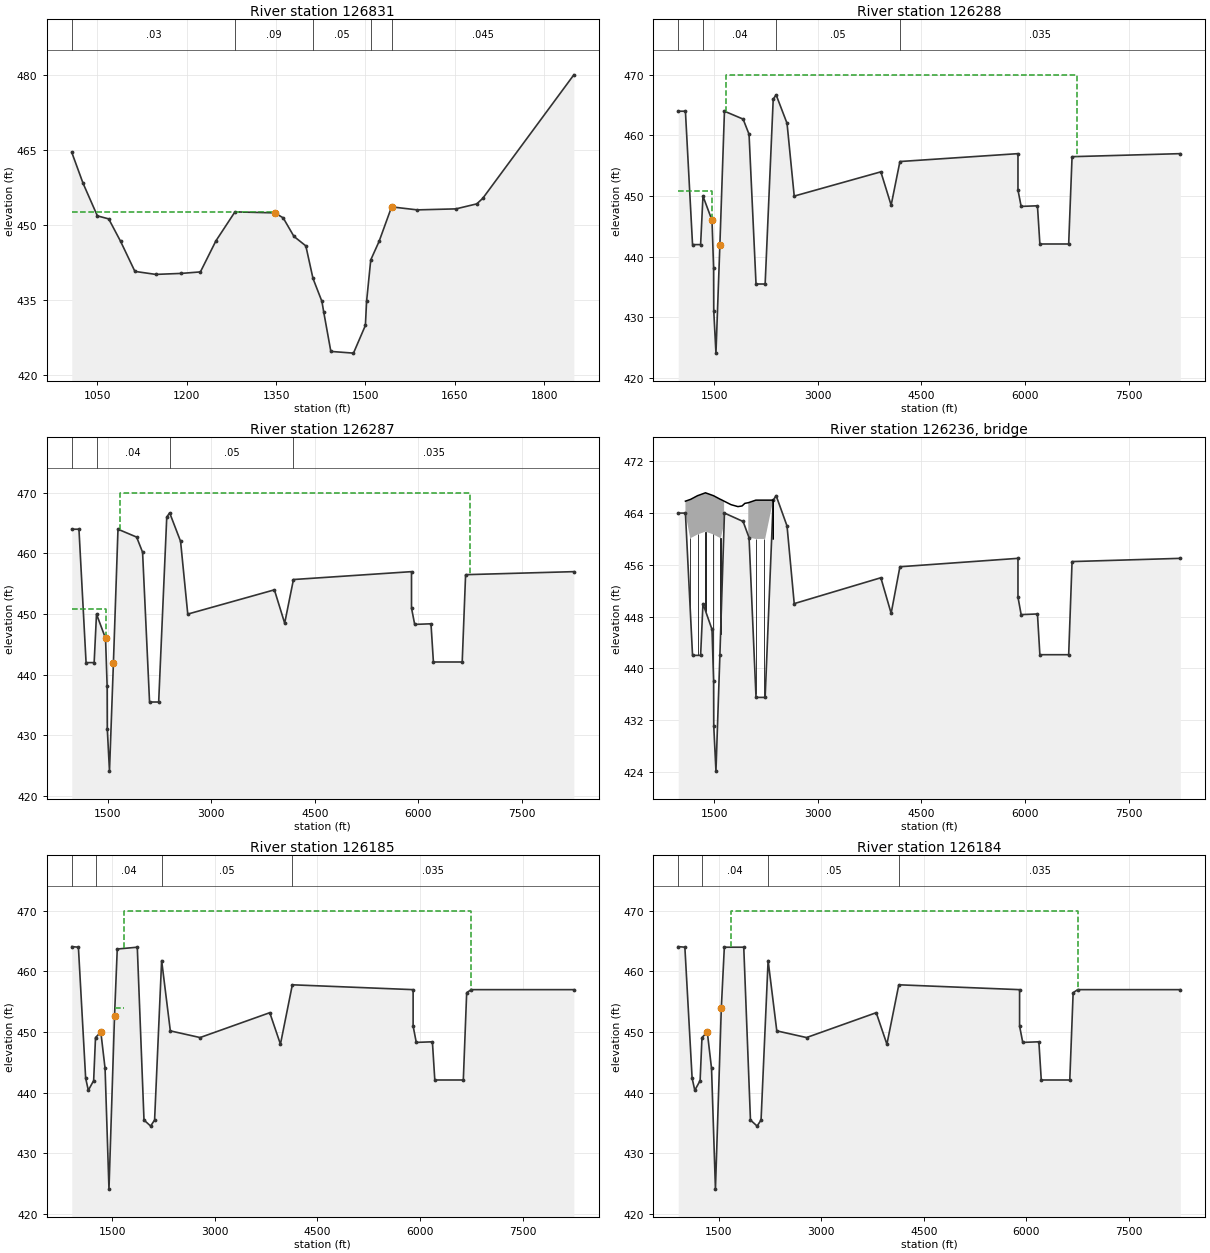
Type RM Length L Ch R = 1 ,126831  ,464,543,622
BEGIN DESCRIPTION:
This cross section corresponds to cross section 126818 of the non-georeferenced CDC model which was the source of this model.
END DESCRIPTION:
XS GIS Cut Line= 2
2443695.835737827055603.894781222442853.018853937055621.45347314
#Sta/Elev= 30
    1007   464.5    1026   458.3    1050   451.8    1069   451.2    1089   446.7
    1113   440.7    1148   440.1    1191   440.3    1223   440.6    1249   446.8
    1281   452.6    1348   452.4    1362   451.4    1380   447.7    1400   445.8
    1412   439.3    1427   434.7    1430   432.6    1442   424.7    1480  424.36
    1500   429.9    1502   434.7    1509     443    1523   446.7    1544   453.6
    1587     453    1652   453.2    1687   454.2    1697   455.3    1850     480
#Mann= 5 ,-1,0
    1007     .03       0    1281     .09       0    1412     .05       0
    1509     .08       0    1544    .045       0
#XS Ineff= 2 , 0
       0    1348   452.5    1544       0   453.6
Permanent Ineff=
       F       F
Bank Sta=1348,1544
XS Rating Curve= 0 ,0
Exp/Cntr=0.3,0.1

Type RM Length L Ch R = 1 ,126288  ,1,1,1
BEGIN DESCRIPTION:
This cross section corresponds to cross section 126293 of the non-georeferenced CDC model which was the source of this model.
END DESCRIPTION:
XS GIS Cut Line= 4
2443872.004020667055219.654079882443102.852999937055025.20564988
2438857.507488017052432.10224029 2437577.41378997051650.20702732
#Sta/Elev= 30
     982     464    1086     464    1189     442    1306     442    1340     450
    1471     446    1494   438.1    1496   431.1    1528   424.1    1585     442
    1651     464    1921   462.7    2007   460.2    2108   435.5    2240   435.5
    2357     466    2399   466.7    2557     462    2661     450    3915     454
    4064   448.5    4191   455.7    5900     457    5900     451    5946   448.3
    6182   448.4    6217   442.1    6634   442.1    6683   456.5    8250     457
#Mann= 4 ,-1,0
     982     .03       0    1340     .04       0    2399     .05       0
    4191    .035       0
#XS Ineff= 3 ,-1
     982    1471   450.9    1585    1675     442    1675    6750     470
Permanent Ineff=
       F       F       F
Bank Sta=1471,1585
XS Rating Curve= 0 ,0
Exp/Cntr=0.5,0.3

Type RM Length L Ch R = 1 ,126287  ,102,102,102
BEGIN DESCRIPTION:
This cross section corresponds to cross section 126292 of the non-georeferenced CDC model which was the source of this model.
END DESCRIPTION:
XS GIS Cut Line= 4
2443872.324230027055218.918517052443101.958972847055024.08360489
2438858.160373847052430.888331962437578.205792177051648.76540757
#Sta/Elev= 30
     982     464    1086     464    1189     442    1306     442    1340     450
    1471     446    1494   438.1    1496   431.1    1528   424.1    1585     442
    1651     464    1921   462.7    2007   460.2    2108   435.5    2240   435.5
    2357     466    2399   466.7    2557     462    2661     450    3915     454
    4064   448.5    4191   455.7    5900     457    5900     451    5946   448.3
    6182   448.4    6217   442.1    6634   442.1    6683   456.5    8250     457
#Mann= 4 ,-1,0
     982     .03       0    1340     .04       0    2399     .05       0
    4191    .035       0
#XS Ineff= 3 ,-1
     982    1471   450.9    1585    1675     442    1675    6750     470
Permanent Ineff=
       F       F       F
Bank Sta=1471,1585
XS Rating Curve= 0 ,0
Exp/Cntr=0.5,0.3

Type RM Length L Ch R = 3 ,126236  ,,,
BEGIN DESCRIPTION:
Hebron Parkway
END DESCRIPTION:
Node Name=Hebron Parkway
Bridge Culvert--1,0,-1,-1, 0
Deck Dist Width WeirC Skew NumUp NumDn MinLoCord MaxHiCord MaxSubmerge Is_Ogee
1,100,2.6,0, 25, 25, , , 0.95, 0, ,,,
    1086    1155  1157.5    1265  1267.5    1375  1377.5    1486  1488.5    1596
  1598.5    1646    1646    1746    1846    1906    1946    1996    1996    2105
  2107.5    2215  2217.5    2357    2357
  465.84   466.1   466.1  466.71  466.71  467.13  467.13  466.71  466.71   466.1
   466.1  465.84  465.84   465.3     465   465.1   465.5   465.6   465.6     466
     466     466     466     466     460
  459.84   460.1   460.1  460.71  460.71  461.13  461.13  460.71  460.71   460.1
   460.1  459.84  465.84   465.3     465   465.1   465.5   465.6     460     460
     460     460     460     460     460
    1000    1069  1071.5    1179  1181.5    1289  1291.5    1400  1402.5    1510
  1512.5    1560    1560    1660    1760    1820    1860    1880    1880    2019
  2021.5    2129  2131.5    2213    2213
  465.84   466.1   466.1  466.71  466.71  467.13  467.13  466.71  466.71   466.1
   466.1  465.84  465.84   465.3     465   465.1   465.5   465.6   465.6     466
     466     466     466     466     460
  459.84   460.1   460.1  460.71  460.71  461.13  461.13  460.71  460.71   460.1
   460.1  459.84  465.84   465.3     465   465.1   465.5   465.6     460     460
     460     460     460     460     460
Pier Skew, UpSta & Num, DnSta & Num=  ,1156, 2 ,1081, 2 , 0 , 0 , 0 ,,
     2.5     2.5
       0   460.5
     2.5     2.5
       0   460.5
Pier Skew, UpSta & Num, DnSta & Num=  ,1266, 2 ,1191, 2 , 0 , 0 , 0 ,,
     2.5     2.5
       0     461
     2.5     2.5
       0     461
Pier Skew, UpSta & Num, DnSta & Num=  ,1376, 2 ,1301, 2 , 0 , 0 , 0 ,,
     2.5     2.5
       0   461.5
     2.5     2.5
       0   461.5
Pier Skew, UpSta & Num, DnSta & Num=  ,1487, 2 ,1412, 2 , 0 , 0 , 0 ,,
     2.5     2.5
       0     461
     2.5     2.5
       0     461
Pier Skew, UpSta & Num, DnSta & Num=  ,1595, 2 ,1520, 2 , 0 , 0 , 0 ,,
     2.5     2.5
       0   460.5
     2.5     2.5
       0   460.5
Pier Skew, UpSta & Num, DnSta & Num=  ,2106, 2 ,1974, 2 , 0 , 0 , 0 ,,
     2.5     2.5
       0     461
     2.5     2.5
       0     461
Pier Skew, UpSta & Num, DnSta & Num=  ,2219, 2 ,2087, 2 , 0 , 0 , 0 ,,
     2.5     2.5
       0     461
     2.5     2.5
       0     461
BR Coef= 1 , 0 , 0 ,1.05, 0 ,,,0.8,-1,0.5,1,
WSPro=,,,, 1 ,,,, 0 ,,,, 0 ,,,,-1 ,-1 ,-1 , 0 , 0 , 0 , 0 , 0
BC Design=,, 0 ,, 0 ,,,,,,
BC HTab HWMax=465.84
BC Use User HTab Curves=0
BC User HTab FreeFlow(D)= 0

Type RM Length L Ch R = 1 ,126185  ,1,1,1
BEGIN DESCRIPTION:
This cross section corresponds to cross section 126172 of the non-georeferenced CDC model which was the source of this model.
END DESCRIPTION:
XS GIS Cut Line= 4
     2443902.915     7055128.836     2442996.024     7054890.963
     2438858.338     7052259.767 2437592.58577287051454.86247191
#Sta/Elev= 30
     909   464.1    1006     464    1112   442.4    1151   440.4    1229     442
    1256   449.1    1334     450    1396     444    1453   424.1    1534   452.6
    1574   463.7    1867     464    1965   435.5    2062   434.5    2120   435.5
    2223   461.8    2350   450.2    2785   449.1    3804   453.2    3960     448
    4134   457.8    5900     457    5900     451    5946   448.3    6182   448.4
    6217   442.1    6634   442.1    6683   456.5    6750     457    8250     457
#Mann= 4 ,-1,0
     909     .03       0    1256     .04       0    2223     .05       0
    4134    .035       0
#XS Ineff= 3 ,-1
     909    1334     450    1539    1676     454    1676    6750     470
Permanent Ineff=
       F       F       F
Bank Sta=1334,1534
XS Rating Curve= 0 ,0
Exp/Cntr=0.5,0.3

Type RM Length L Ch R = 1 ,126184  ,0,0,0
BEGIN DESCRIPTION:
This cross section corresponds to cross section 126171 of the non-georeferenced CDC model which was the source of this model.
END DESCRIPTION:
XS GIS Cut Line= 4
2443903.383879187055127.946258052442996.492976437054890.07403038
2438858.806697997052258.877193052437593.054562257051453.97252114
#Sta/Elev= 30
     909   464.1    1006     464    1112   442.4    1151   440.4    1229     442
    1256   449.1    1334     450    1396     444    1453   424.1    1539     454
    1583     464    1867     464    1965   435.5    2062   434.5    2120   435.5
    2223   461.8    2350   450.2    2785   449.1    3804   453.2    3960     448
    4134   457.8    5900     457    5900     451    5946   448.3    6182   448.4
    6217   442.1    6634   442.1    6683   456.5    6750     457    8250     457
#Mann= 4 ,-1,0
     909     .03       0    1256     .04       0    2223     .05       0
    4134    .035       0
#XS Ineff= 3 ,-1
     909    1334     450    1539    1676     454    1676    6750     470
Permanent Ineff=
       F       F       F
Bank Sta=1334,1539
XS Rating Curve= 0 ,0
Exp/Cntr=0.3,0.1

River Reach=Elm Fork        ,ef3
Reach XY= 30
      2443507.86      7054781.77      2443313.02       7052145.4
      2445868.22      7052564.08      2446998.56      7051517.39
      2445261.13      7050837.78      2446747.18      7049390.79
      2443724.81      7047095.96      2446042.79      7046227.23
      2446533.18      7044018.46      2448182.62      7043471.38
      2447028.23      7042565.46      2447998.71      7041928.89
      2447803.01      7039683.01      2446079.96      7039459.22
      2445527.69      7037824.95      2447171.93      7031838.88
      2448540.99      7031061.07      2449273.49       7029018.6
      2448521.48      7026637.83      2447000.53      7025969.64
       2449243.1      7024505.45      2447907.61      7024057.09
      2447661.34       7018966.6      2449579.68      7018119.64
      2451504.25      7014860.54      2451262.61      7011037.61
       2450116.3      7010513.16      2449772.04      7008416.84
       2450705.4      7007292.08      2450520.46       7004955.1

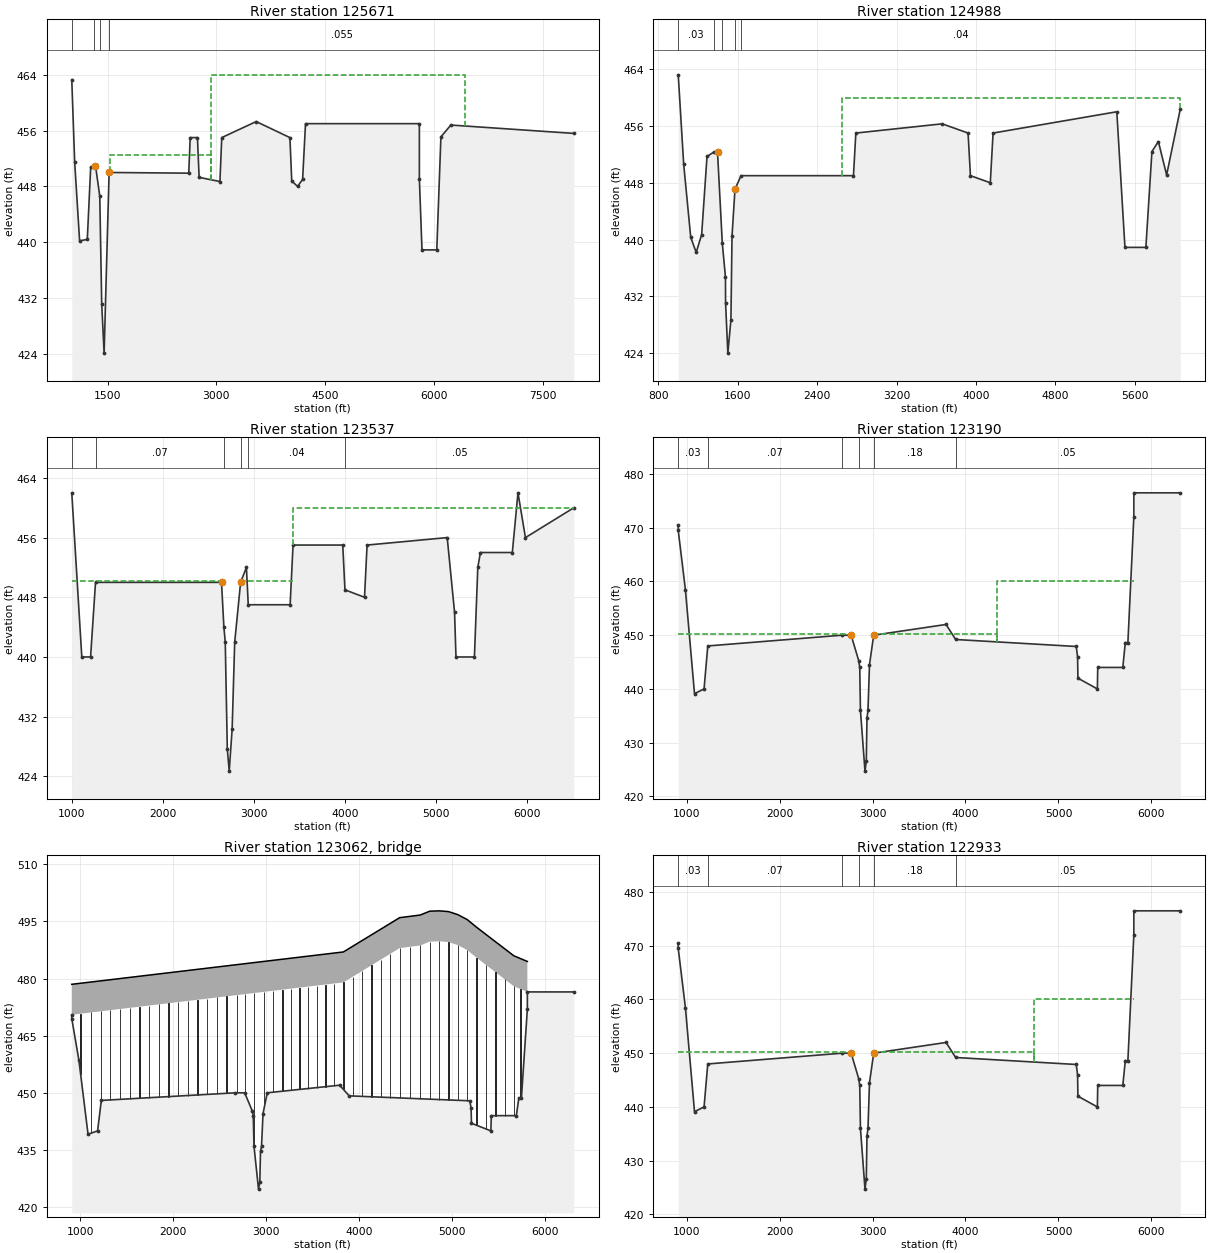
Type RM Length L Ch R = 1 ,125671  ,850,683,550
BEGIN DESCRIPTION:
This cross section corresponds to cross section 125658 of the non-georeferenced CDC model which was the source of this model.
ROB skewed 40 deg   start 1550   2 Proposed fills.
---------------------------------------------------------------------
CDC LEW121406-1 Waste Management Systems Landfill
Cross-section 125658 - 144474.  Includes split flow reach efs2.
This CDC incorporates CDC LEW102202-02
---------------------------------------------------------------------
END DESCRIPTION:
XS GIS Cut Line= 3
2444055.669007667054814.836976132439478.530524167051906.44712363
2438212.495522327051101.98744527
#Sta/Elev= 30
    1007   463.3    1047   451.5    1115   440.2    1221   440.4    1268   450.8
    1311   450.8    1334     451    1393   446.6    1420   431.1    1453   424.1
    1522     450    2620   449.9    2640     455    2740     455    2763   449.3
    3050   448.7    3075     455    3550   457.3    4015     455    4040   448.8
    4120     448    4190     449    4230     457    5800     457    5800   449.1
    5836   438.9    6040   438.9    6097   455.1    6234   456.8    7930   455.6
#Mann= 4 ,-1,0
    1007     .03       0    1311     .07       0    1393     .05       0
    1522    .055       0
#XS Ineff= 3 ,-1
    1007    1334   450.8    1533    2930   452.5    2930    6430     464
Permanent Ineff=
       F       F       F
Bank Sta=1334,1522
XS Rating Curve= 0 ,0
Exp/Cntr=0.3,0.1

Type RM Length L Ch R = 1 ,124988  ,500,1451,570
BEGIN DESCRIPTION:
This cross section corresponds to cross section 124975 of the non-georeferenced CDC model which was the source of this model.
ROB skewed 37 deg.start 1737   1 lake 2 fills.
END DESCRIPTION:
XS GIS Cut Line= 3
2444422.009154267053966.009933642443685.355115747053940.60808155
2440054.028060857051595.18724747
#Sta/Elev= 30
    1000   463.2    1055   450.6    1126   440.3    1181   438.2    1236   440.7
    1290   451.7    1356   452.3    1396   452.3    1444   439.5    1476   434.7
    1477   431.1    1500  424.01    1531   428.7    1542   440.5    1572   447.1
    1633     449    2766     449    2790     455    3660   456.3    3921     455
    3945     449    4145     448    4173     455    5420     458    5502   438.9
    5713   438.9    5774   452.4    5839   453.8    5922   449.1    6060   458.4
#Mann= 5 ,-1,0
    1000     .03       0    1356     .07       0    1444     .05       0
    1572    .055       0    1633     .04       0
#XS Ineff= 3 ,-1
    1000    1396     451    1572    2650   447.1    2650    6060     460
Permanent Ineff=
       F       F       F
Bank Sta=1396,1572
XS Rating Curve= 0 ,0
Exp/Cntr=0.3,0.1

Type RM Length L Ch R = 1 ,123537  ,36,347,534
BEGIN DESCRIPTION:
This cross section corresponds to cross section 123524 of the non-georeferenced CDC model which was the source of this model.
ROB skewed 48 deg.from original start 2970    Only 1 pond & 1 fill shown.
END DESCRIPTION:
XS GIS Cut Line= 4
   2444573.66683   7053727.27222 2443308.5848719 7052752.3411011
 2442949.3510104  7052807.722224 2440071.9335368 7050722.6827589
#Sta/Elev= 30
    1000     462 1110.15     440 1206.55     440 1260.84     450 2644.49     450
 2670.44     444  2685.5     442    2708   427.7    2729   424.7    2761   430.3
 2789.39     442 2854.18     450    2918     452    2938     447    3398     447
    3430     455    3976     455    4000     449    4215     448    4243     455
    5123     456 5203.66     446  5219.3     440 5421.82     440 5458.97     452
 5487.67     454    5838     454 5900.17     462 5982.19     456  6513.7     460
#Mann= 6 ,-1,0
    1000     .03       0 1260.84     .07       0 2670.44    .055       0
 2854.18     .07       0    2938     .04       0    4000     .05       0
#XS Ineff= 3 ,-1
    1000 2644.49   450.2 2854.18    3430   450.2    3430  6513.7     460
Permanent Ineff=
       F       F       F
Bank Sta=2644.49,2854.18
XS Rating Curve= 0 ,0
Exp/Cntr=0.3,0.1

Type RM Length L Ch R = 1 ,123190  ,257,257,257
BEGIN DESCRIPTION:
This cross section corresponds to cross section 123134 of the non-georeferenced CDC model which was the source of this model.
Upstream bounding cross section for S.H. 121 Lewisville Bypass Bridge.
END DESCRIPTION:
XS GIS Cut Line= 3
   2444641.21169   7053764.75067   2440996.06212   7050494.45151
2440623.890792167050160.55256911
#Sta/Elev= 30
     910   470.5     910   469.5     987   458.5    1085  439.12 1187.82     440
 1227.84     448    2670     450    2770     450 2851.71  445.24 2862.58     444
    2870     436    2919   424.7    2933   426.6 2940.33   434.6 2951.24     436
 2967.41  444.52 3012.64     450 3791.38     452  3894.3   449.2 5191.51   447.9
 5205.77     446 5209.59     442 5418.76     440 5422.75     444 5692.37     444
 5719.38  448.64 5746.79  448.52    5811     472    5811   476.5    6311   476.5
#Mann= 6 ,-1,0
     910     .03       0 1227.84     .07       0    2670     .06       0
 2851.71    .055       0 3012.64     .18       0  3894.3     .05       0
#XS Ineff= 3 ,-1
     910    2770   450.2 3012.64    4340   450.2    4340    5811     460
Permanent Ineff=
       F       F       F
Bank Sta=2770,3012.64
XS Rating Curve= 0 ,0
Exp/Cntr=0.3,0.1

Type RM Length L Ch R = 3 ,123062  ,,,
BEGIN DESCRIPTION:
State Highway 121 Lewisville Bypass
Note:  This bridge was modeled from plans dated Oct. 1995 and supplied by TXDOT Aug. 1999.
END DESCRIPTION:
Node Name=SH 121
Bridge Culvert--1,0,-1,-1, 0
Deck Dist Width WeirC Skew NumUp NumDn MinLoCord MaxHiCord MaxSubmerge Is_Ogee
10,237,2.6,0, 12, 12, , , 0.95, 0, 0,0,,
     910    3832    4437    4659    4760    4861    4962    5063    5164    5264
    5665    5811
   478.5     487     496   496.7   497.7   497.8   497.6   496.8   495.5   493.5
     486   484.5
   470.5     479     488   488.7   489.7   489.8   489.6   488.8   487.5   485.5
     478   476.5
     910    3832    4437    4659    4760    4861    4962    5063    5164    5264
    5665    5811
   478.5     487     496   496.7   497.7   497.8   497.6   496.8   495.5   493.5
     486   484.5
   470.5     479     488   488.7   489.7   489.8   489.6   488.8   487.5   485.5
     478   476.5
Pier Skew, UpSta & Num, DnSta & Num=  ,1005, 2 ,1005, 2 , 0 , 0 , 0 ,,
       3       3
     400     475
       3       3
     400     475
Pier Skew, UpSta & Num, DnSta & Num=  ,1115, 2 ,1115, 2 , 0 , 0 , 0 ,,
       3       3
     400     475
       3       3
     400     475
Pier Skew, UpSta & Num, DnSta & Num=  ,1225, 2 ,1225, 2 , 0 , 0 , 0 ,,
       3       3
     400     475
       3       3
     400     475
Pier Skew, UpSta & Num, DnSta & Num=  ,1325, 2 ,1325, 2 , 0 , 0 , 0 ,,
       3       3
     400     475
       3       3
     400     475
Pier Skew, UpSta & Num, DnSta & Num=  ,1430, 2 ,1430, 2 , 0 , 0 , 0 ,,
       3       3
     400     475
       3       3
     400     475
Pier Skew, UpSta & Num, DnSta & Num=  ,1534, 2 ,1534, 2 , 0 , 0 , 0 ,,
       3       3
     400     475
       3       3
     400     475
Pier Skew, UpSta & Num, DnSta & Num=  ,1638, 2 ,1638, 2 , 0 , 0 , 0 ,,
       3       3
     400     480
       3       3
     400     480
Pier Skew, UpSta & Num, DnSta & Num=  ,1742, 2 ,1742, 2 , 0 , 0 , 0 ,,
       3       3
     400     480
       3       3
     400     480
Pier Skew, UpSta & Num, DnSta & Num=  ,1846, 2 ,1846, 2 , 0 , 0 , 0 ,,
       3       3
     400     480
       3       3
     400     480
Pier Skew, UpSta & Num, DnSta & Num=  ,1950, 2 ,1950, 2 , 0 , 0 , 0 ,,
       3       3
     400     480
       3       3
     400     480
Pier Skew, UpSta & Num, DnSta & Num=  ,2054, 2 ,2054, 2 , 0 , 0 , 0 ,,
       3       3
     400     480
       3       3
     400     480
Pier Skew, UpSta & Num, DnSta & Num=  ,2158, 2 ,2158, 2 , 0 , 0 , 0 ,,
       3       3
     400     480
       3       3
     400     480
Pier Skew, UpSta & Num, DnSta & Num=  ,2262, 2 ,2262, 2 , 0 , 0 , 0 ,,
       3       3
     400     480
       3       3
     400     480
Pier Skew, UpSta & Num, DnSta & Num=  ,2366, 2 ,2366, 2 , 0 , 0 , 0 ,,
       3       3
     400     480
       3       3
     400     480
Pier Skew, UpSta & Num, DnSta & Num=  ,2470, 2 ,2470, 2 , 0 , 0 , 0 ,,
       3       3
     400     480
       3       3
     400     480
Pier Skew, UpSta & Num, DnSta & Num=  ,2574, 2 ,2574, 2 , 0 , 0 , 0 ,,
       3       3
     400     480
       3       3
     400     480
Pier Skew, UpSta & Num, DnSta & Num=  ,2684, 2 ,2684, 2 , 0 , 0 , 0 ,,
       3       3
     400     480
       3       3
     400     480
Pier Skew, UpSta & Num, DnSta & Num=  ,2777, 2 ,2777, 2 , 0 , 0 , 0 ,,
       3       3
     400     480
       3       3
     400     480
Pier Skew, UpSta & Num, DnSta & Num=  ,2870, 2 ,2870, 2 , 0 , 0 , 0 ,,
       3       3
     400     480
       3       3
     400     480
Pier Skew, UpSta & Num, DnSta & Num=  ,2980, 2 ,2980, 2 , 0 , 0 , 0 ,,
       3       3
     400     480
       3       3
     400     480
Pier Skew, UpSta & Num, DnSta & Num=  ,3076, 2 ,3076, 2 , 0 , 0 , 0 ,,
       3       3
     400     480
       3       3
     400     480
Pier Skew, UpSta & Num, DnSta & Num=  ,3176, 2 ,3176, 2 , 0 , 0 , 0 ,,
       3       3
     400     480
       3       3
     400     480
Pier Skew, UpSta & Num, DnSta & Num=  ,3265, 2 ,3265, 2 , 0 , 0 , 0 ,,
       3       3
     400     480
       3       3
     400     480
Pier Skew, UpSta & Num, DnSta & Num=  ,3359, 2 ,3359, 2 , 0 , 0 , 0 ,,
       3       3
     400     480
       3       3
     400     480
Pier Skew, UpSta & Num, DnSta & Num=  ,3452, 2 ,3452, 2 , 0 , 0 , 0 ,,
       3       3
     400     480
       3       3
     400     480
Pier Skew, UpSta & Num, DnSta & Num=  ,3546, 2 ,3546, 2 , 0 , 0 , 0 ,,
       3       3
     400     480
       3       3
     400     480
Pier Skew, UpSta & Num, DnSta & Num=  ,3639, 2 ,3639, 2 , 0 , 0 , 0 ,,
       3       3
     400     480
       3       3
     400     480
Pier Skew, UpSta & Num, DnSta & Num=  ,3732, 2 ,3732, 2 , 0 , 0 , 0 ,,
       3       3
     400     480
       3       3
     400     480
Pier Skew, UpSta & Num, DnSta & Num=  ,3832, 2 ,3832, 2 , 0 , 0 , 0 ,,
       3       3
     400     480
       3       3
     400     480
Pier Skew, UpSta & Num, DnSta & Num=  ,3932, 2 ,3932, 2 , 0 , 0 , 0 ,,
       3       3
     400     485
       3       3
     400     485
Pier Skew, UpSta & Num, DnSta & Num=  ,4033, 2 ,4033, 2 , 0 , 0 , 0 ,,
       3       3
     400     485
       3       3
     400     485
Pier Skew, UpSta & Num, DnSta & Num=  ,4133, 2 ,4133, 2 , 0 , 0 , 0 ,,
       3       3
     400     485
       3       3
     400     485
Pier Skew, UpSta & Num, DnSta & Num=  ,4233, 2 ,4233, 2 , 0 , 0 , 0 ,,
       3       3
     400     490
       3       3
     400     490
Pier Skew, UpSta & Num, DnSta & Num=  ,4334, 2 ,4334, 2 , 0 , 0 , 0 ,,
       3       3
     400     490
       3       3
     400     490
Pier Skew, UpSta & Num, DnSta & Num=  ,4437, 2 ,4437, 2 , 0 , 0 , 0 ,,
       3       3
     400     490
       3       3
     400     490
Pier Skew, UpSta & Num, DnSta & Num=  ,4547, 2 ,4547, 2 , 0 , 0 , 0 ,,
       3       3
     400     490
       3       3
     400     490
Pier Skew, UpSta & Num, DnSta & Num=  ,4659, 2 ,4659, 2 , 0 , 0 , 0 ,,
       3       3
     400     490
       3       3
     400     490
Pier Skew, UpSta & Num, DnSta & Num=  ,4760, 2 ,4760, 2 , 0 , 0 , 0 ,,
       3       3
     400     490
       3       3
     400     490
Pier Skew, UpSta & Num, DnSta & Num=  ,4861, 2 ,4861, 2 , 0 , 0 , 0 ,,
       3       3
     400     490
       3       3
     400     490
Pier Skew, UpSta & Num, DnSta & Num=  ,4962, 2 ,4962, 2 , 0 , 0 , 0 ,,
       3       3
     400     490
       3       3
     400     490
Pier Skew, UpSta & Num, DnSta & Num=  ,5063, 2 ,5063, 2 , 0 , 0 , 0 ,,
       3       3
     400     490
       3       3
     400     490
Pier Skew, UpSta & Num, DnSta & Num=  ,5164, 2 ,5164, 2 , 0 , 0 , 0 ,,
       3       3
     400     490
       3       3
     400     490
Pier Skew, UpSta & Num, DnSta & Num=  ,5265, 2 ,5265, 2 , 0 , 0 , 0 ,,
       3       3
     400     490
       3       3
     400     490
Pier Skew, UpSta & Num, DnSta & Num=  ,5366, 2 ,5366, 2 , 0 , 0 , 0 ,,
       3       3
     400     490
       3       3
     400     490
Pier Skew, UpSta & Num, DnSta & Num=  ,5467, 2 ,5467, 2 , 0 , 0 , 0 ,,
       3       3
     400     488
       3       3
     400     488
Pier Skew, UpSta & Num, DnSta & Num=  ,5568, 2 ,5568, 2 , 0 , 0 , 0 ,,
       3       3
     400     485
       3       3
     400     485
Pier Skew, UpSta & Num, DnSta & Num=  ,5665, 2 ,5665, 2 , 0 , 0 , 0 ,,
       3       3
     400     485
       3       3
     400     485
Pier Skew, UpSta & Num, DnSta & Num=  ,5736, 2 ,5736, 2 , 0 , 0 , 0 ,,
       3       3
     400     484
       3       3
     400     484
BR Coef=-1 , 0 , 0 ,, 0 ,,,0.8,-1,,0,
WSPro=,,,, 1 ,,,, 0 ,,,, 0 ,,,,-1 ,-1 ,-1 , 0 , 0 , 0 , 0 , 0
BC Design=,, 0 ,, 0 ,,,,,,
BC HTab HWMax=476.5
BC Use User HTab Curves=0
BC User HTab FreeFlow(D)= 0

Type RM Length L Ch R = 1 ,122933  ,904,2168,596
BEGIN DESCRIPTION:
This cross section corresponds to cross section 122934 of the non-georeferenced CDC model which was the source of this model.
Downstream bounding cross section for S.H. 121 Lewisville Bypass Bridge.
END DESCRIPTION:
XS GIS Cut Line= 3
   2444750.11247   7053563.61165   2441131.48579   7050257.81637
2440762.336105677049920.57979049
#Sta/Elev= 30
     910   470.5     910   469.5     987   458.5    1085  439.12 1187.82     440
 1227.84     448    2670     450    2770     450 2851.71  445.24 2862.58     444
    2870     436    2919   424.7    2933   426.6 2940.33   434.6 2951.24     436
 2967.41  444.52 3012.64     450 3791.38     452  3894.3   449.2 5191.51   447.9
 5205.77     446 5209.59     442 5418.76     440 5422.75     444 5692.37     444
 5719.38  448.64 5746.79  448.52    5811     472    5811   476.5    6311   476.5
#Mann= 6 ,-1,0
     910     .03       0 1227.84     .07       0    2670     .06       0
 2851.71    .055       0 3012.64     .18       0  3894.3     .05       0
#XS Ineff= 3 ,-1
     910    2770   450.2 3012.64    4740   450.2    4740    5811     460
Permanent Ineff=
       F       F       F
Bank Sta=2770,3012.64
XS Rating Curve= 0 ,0
Exp/Cntr=0.3,0.1