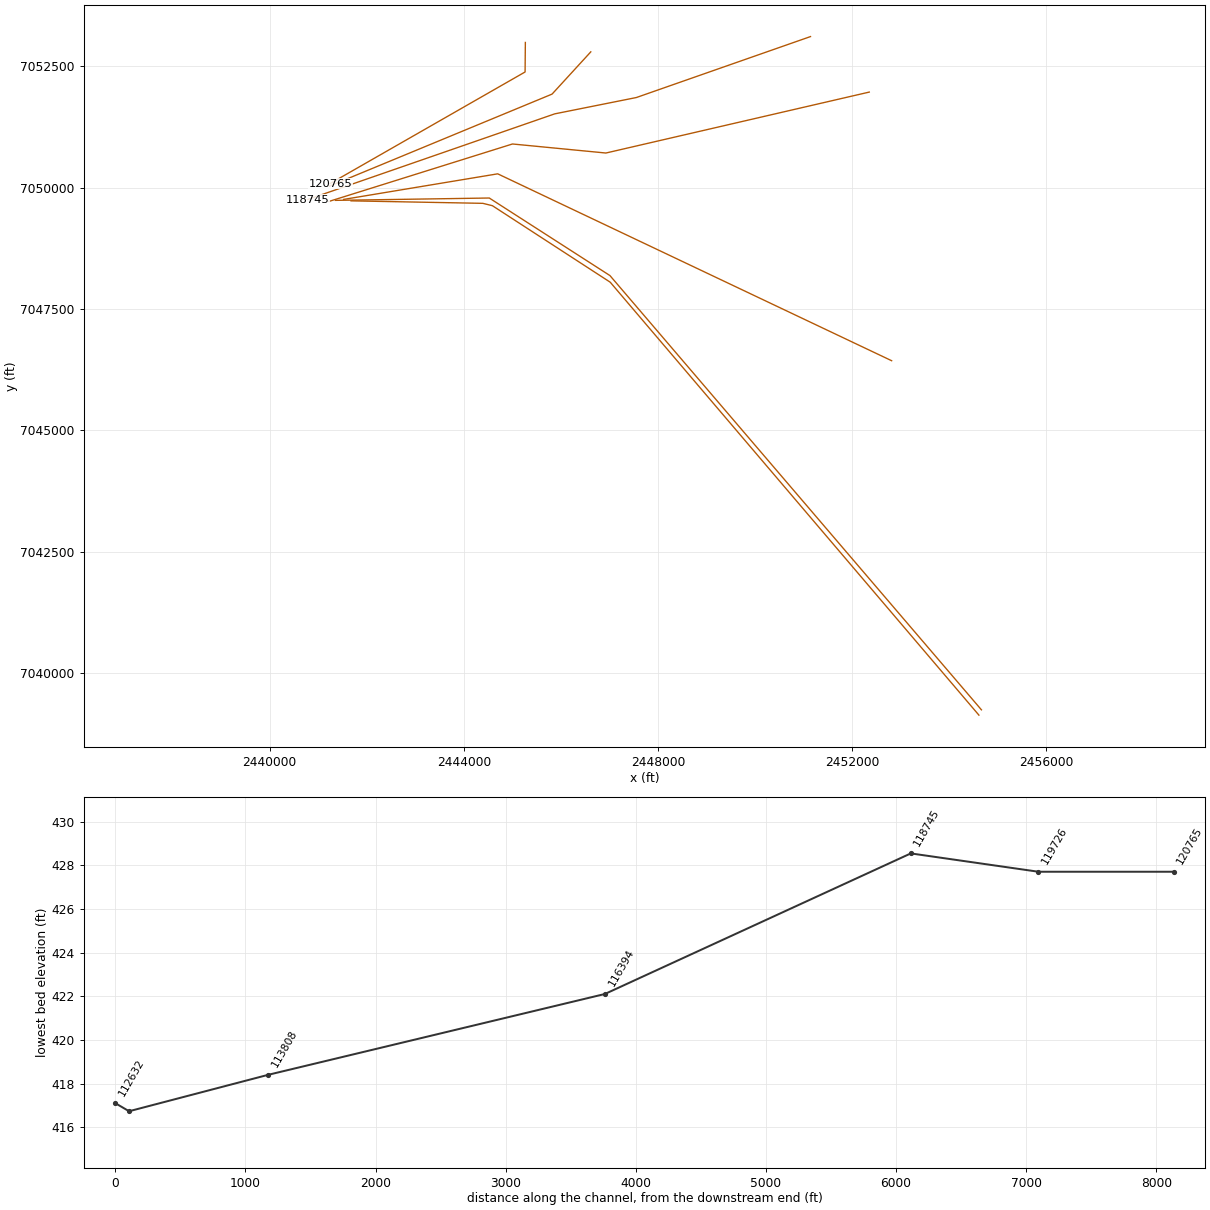
HEC-RAS study CDC_Consolidated_Model.prj: Upper Trinity CDC Consolidated Model

--- CDC_Consolidated_Model.g01 (geometry) --- (continued)

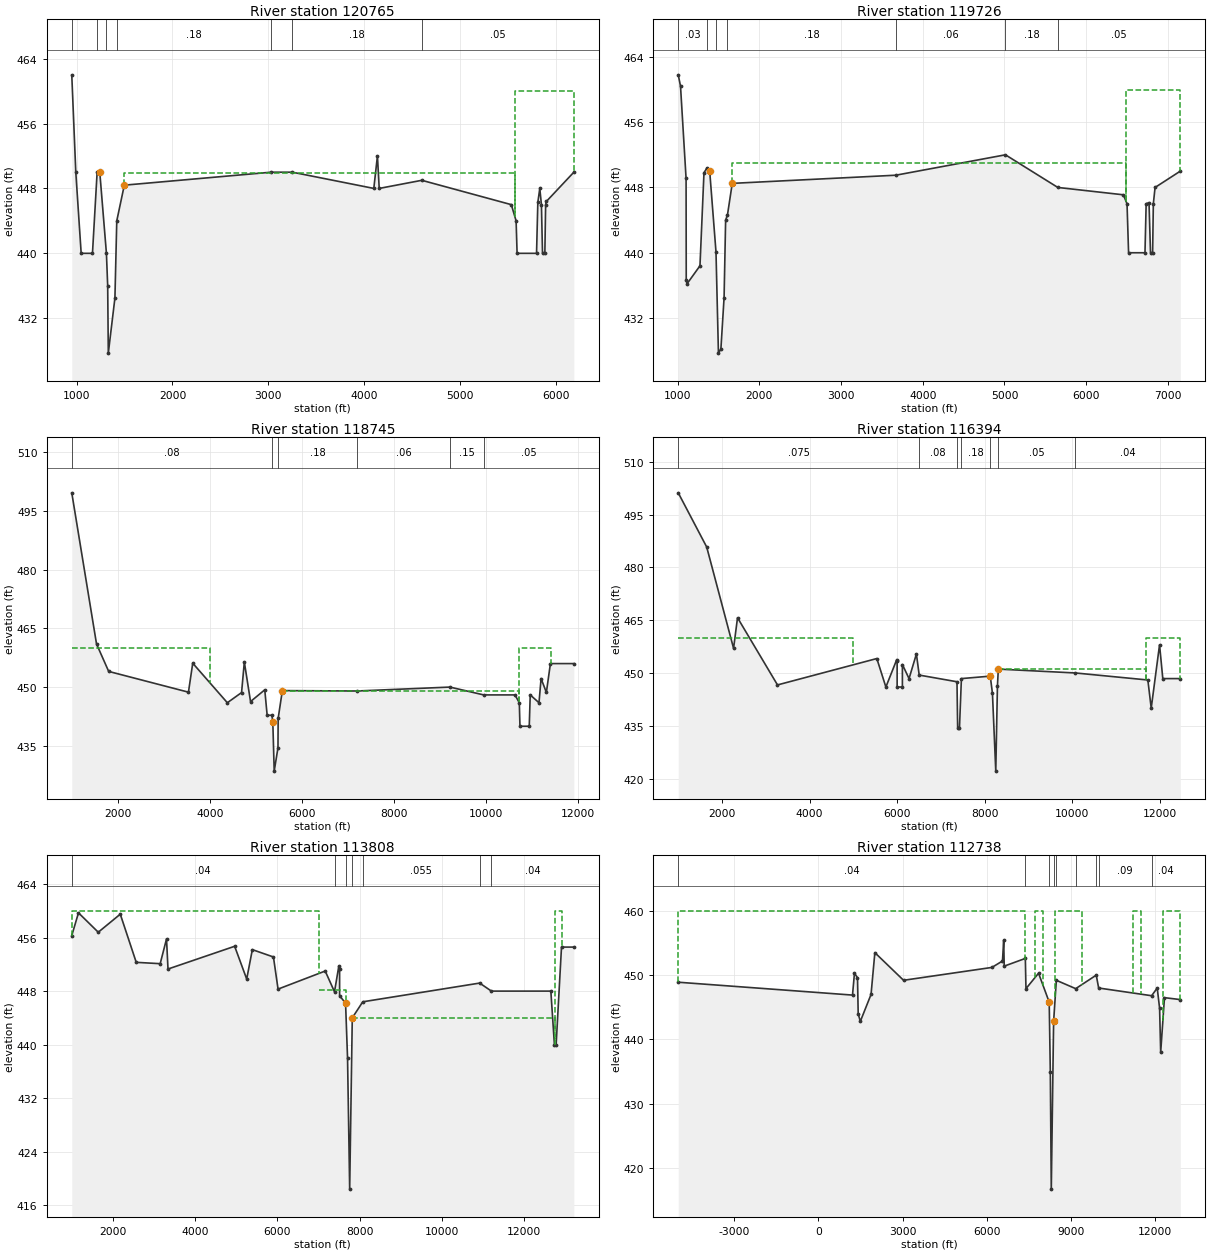
Type RM Length L Ch R = 1 ,120765  ,1201,1039,400
BEGIN DESCRIPTION:
This cross section corresponds to cross section 120752 of the non-georeferenced CDC model which was the source of this model.
Cut area
END DESCRIPTION:
XS GIS Cut Line= 3
2445267.590468357052991.55617388 2445262.22893057052383.13809939
2441246.677906517050084.84774847
#Sta/Elev= 30
     950     462     992     450    1048     440 1165.82     440 1214.47     450
 1241.98     450 1311.33     440 1324.46     436    1331   427.7    1400   434.5
 1419.24     444 1497.77   448.4    3030     450    3250     450 4099.42     448
  4137.1     452 4155.74     448    4600     449 5533.18     446 5583.16     444
 5593.37     440 5796.28     440 5809.64  446.27 5830.12     448 5847.11     446
 5858.49     440 5882.89     440 5891.04     446 5899.17   446.4 6185.19     450
#Mann= 7 ,-1,0
     950     .03       0 1214.47     .11       0 1311.33    .055       0
 1419.24     .18       0    3030     .06       0    3250     .18       0
    4600     .05       0
#XS Ineff= 3 ,-1
     950 1241.88   449.9  1497.7    5570   449.9    5570 6185.19     460
Permanent Ineff=
       F       F       F
Bank Sta=1241.98,1497.77
XS Rating Curve= 0 ,0
Exp/Cntr=0.3,0.1

Type RM Length L Ch R = 1 ,119726  ,1349,981,300
BEGIN DESCRIPTION:
This cross section corresponds to cross section 119714 of the non-georeferenced CDC model which was the source of this model.
---------------------------------------------------------------------
CDC LEW042104-02 Trinity Place
Cross-section 119714 - 125658
Project located in ROB.
---------------------------------------------------------------------
Cut area
END DESCRIPTION:
XS GIS Cut Line= 3
2446616.14813867 7052797.84363482445818.140876417051927.28992972
2441231.914812687050030.39149255
#Sta/Elev= 30
    1008   461.8    1036   460.4    1104   449.1    1106   436.6    1116   436.2
    1274   438.4    1323   449.8    1360   450.4    1393     450    1470   440.1
    1500   427.7    1530   428.2    1569   434.5    1588     444    1610   444.6
    1669   448.5 3670.52   449.5 5012.09     452 5653.17     448    6455   447.1
 6499.98     446 6518.95     440 6719.67     440 6733.98     446 6769.15  446.14
  6787.2     440 6813.14     440 6821.97     446 6843.15     448    7152     450
#Mann= 7 ,-1,0
    1008     .03       0    1360     .15       0    1470    .055       0
    1610     .18       0 3670.52     .06       0 5012.09     .18       0
 5653.17     .05       0
#XS Ineff= 3 ,-1
    1008    1393     450    1669    6490     451    6490    7152     460
Permanent Ineff=
       F       F       F
Bank Sta=1393,1669
XS Rating Curve= 0 ,0
Exp/Cntr=0.3,0.1

Type RM Length L Ch R = 1 ,118745  ,1000,2351,400
BEGIN DESCRIPTION:
This cross section corresponds to cross section 118732 of the non-georeferenced CDC model which was the source of this model.
END DESCRIPTION:
XS GIS Cut Line= 5
2451142.982917017053112.485065882447555.225984937051856.77005763
2445873.463928497051520.418040052441251.603749667049917.78541856
2440779.197917257049753.97842997
#Sta/Elev= 30
    1000   499.6    1538     461    1802     454    3535   448.7    3628   456.1
    4380     446    4689   448.6    4749   456.4    4884   446.3    5193   449.3
    5245   442.8    5348   442.8    5368   441.1    5398  428.54    5480   434.5
    5484     442    5575   449.1    7200     449 9215.07     450    9950     448
10629.15     44810723.16     44610737.34     44010939.21     44010960.53     448
11151.01     44611196.23  452.1811311.24  448.63   11399     45611908.06     456
#Mann= 6 ,-1,0
    1000     .08       0    5348    .055       0    5484     .18       0
    7200     .06       0 9215.07     .15       0    9950     .05       0
#XS Ineff= 4 ,-1
    1000    4000     460    4000    5368   441.1    5575   10720     449
   1072011408.06     460
Permanent Ineff=
       F       F       F       F
Bank Sta=5368,5575
XS Rating Curve= 0 ,0
Exp/Cntr=0.3,0.1

Type RM Length L Ch R = 1 ,116394  ,2363,2586,719
BEGIN DESCRIPTION:
This cross section corresponds to cross section 116381 of the non-georeferenced CDC model which was the source of this model.
END DESCRIPTION:
XS GIS Cut Line= 5
2452353.851886337051968.887943642446927.367988687050713.17195113
2445002.181878427050899.48096171 2441600.99248667049834.71439047
2441219.261091727049715.21065762
#Sta/Elev= 30
    1000   501.2    1650   485.8    2264     457    2354   465.7    3267   446.6
    5536   454.1    5743     446    5991   453.8    6000  453.35 6000.01     446
    6120     446 6120.01   452.4    6272   448.4    6440   455.4    6504   449.4
    7367   447.5    7382   434.5    7424   434.5    7468   448.4    8127   449.1
    8177   444.2    8253   422.1    8291   446.3    8311   451.110071.73     450
11726.56     44811803.53     44011993.71     45812068.02   448.412468.02   448.4
#Mann= 7 ,-1,0
    1000    .075       0    6504     .08       0    7367    .055       0
    7468     .18       0    8127     .05       0    8311     .05       0
10071.73     .04       0
#XS Ineff= 4 ,-1
    1000    5000     460    5000    8127   449.1    8311   11690   451.1
   1169012468.02     460
Permanent Ineff=
       F       F       F       F
Bank Sta=8127,8311
XS Rating Curve= 0 ,0
Exp/Cntr=0.3,0.1

Type RM Length L Ch R = 1 ,113808  ,945,1070,473
BEGIN DESCRIPTION:
This cross section corresponds to cross section 113864 of the non-georeferenced CDC model which was the source of this model.
---------------------------------------------------------------------
CDC CAR040202-1 Indian Creek Golf Course
Cross-section 113864 - 118732
Located in LOB.
---------------------------------------------------------------------
END DESCRIPTION:
XS GIS Cut Line= 4
2452814.946108527046433.737924712444698.272053187050284.53993438
2441818.028141777049806.243646892441522.080950917049757.09834981
#Sta/Elev= 30
    1000   456.3    1163   459.7    1644   456.8    2179   459.5    2567   452.3
    3149   452.1    3303   455.8    3339   451.3    4959   454.7    5252   449.8
    5389   454.2    5902   453.1    6014   448.3 7160.01     451    7386   447.9
    7490   451.7    7510   451.3 7510.01   447.3    7655   446.2    7703     438
    7755   418.4    7818     444    8073   446.4 10914.3   449.2   11200     448
12644.47     44812731.22     44012773.04     44012903.51  454.5813203.51  454.58
#Mann= 7 ,-1,0
    1000     .04       0    7386     .06       0    7655    .055       0
    7818     .15       0    8073    .055       0 10914.3     .15       0
   11200     .04       0
#XS Ineff= 4 ,-1
    1000    7000     460    7000    7655   448.2    7818   12740     444
   1274012903.51     460
Permanent Ineff=
       F       F       F       F
Bank Sta=7655,7818
XS Rating Curve= 0 ,0
Exp/Cntr=0.3,0.1

Type RM Length L Ch R = 1 ,112738  ,106,106,101
BEGIN DESCRIPTION:
This cross section corresponds to cross section 112732 of the non-georeferenced CDC model which was the source of this model.
END DESCRIPTION:
XS GIS Cut Line= 6
2454665.088166817039240.349443072450764.779933247043799.69102746
2447010.445906527048188.393208062444524.075879257049786.25516979
2441752.901631597049743.814309812441355.426507187049737.72671316
#Sta/Elev= 30
   -5000   448.9    1213   446.9    1283   450.3    1391   449.6    1416     444
    1491   442.8    1874     447    2010   453.5    3033   449.2    6183   451.2
    6560   452.2    6603   455.4    6622   451.4    7375   452.6    7397   447.9
    7846   450.3    8226   445.8    8265     435    8300  416.73    8383   442.8
    8480   449.2    9170   447.9 9903.24     450 9988.57     44811877.94   446.8
12076.83     448 12161.5  444.86 12200.3     438   12335   446.5   12900   446.2
#Mann= 9 ,-1,0
   -5000     .04       0    7375     .07       0    8226     .05       0
    8383      .1       0    8480     .04       0    9170     .09       0
 9903.24     .04       0 9988.57     .09       011877.94     .04       0
#XS Ineff= 10 ,-1
   -5000    7377     460                            7710    8020     460
    8020    8226   445.8    8383    8440   442.8    8440    9380     460
                           11200   11500     460   1150012277.01   442.8
12277.01   12900     460
Permanent Ineff=
       F       F       F       F       F       F       F       F       F       F
Bank Sta=8226,8383
XS Rating Curve= 0 ,0
Exp/Cntr=0.3,0.1

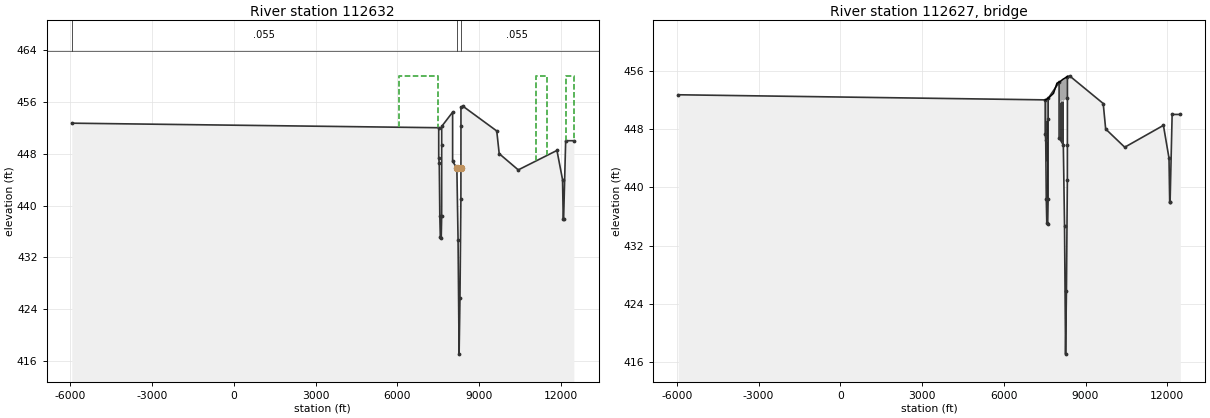
Type RM Length L Ch R = 1 ,112632  ,10,10,10
BEGIN DESCRIPTION:
This cross section corresponds to cross section 112627 of the non-georeferenced CDC model which was the source of this model.
END DESCRIPTION:
XS GIS Cut Line= 6
  2454613.080887 7039131.2886082 2447018.3894602 7048049.0450615
 2447012.7720173 7048053.7651965 2444588.3326405 7049628.1770739
 2444391.2818535 7049676.4939064 2441676.2664943 7049727.6802208
#Sta/Elev= 30
   -5950   452.7    7520     452    7520   447.3    7540   446.5    7560   438.4
    7579   435.1    7612     435    7628   438.4    7629   449.4    7629   452.2
    8030   454.4    8030   446.8    8186   445.8    8230   434.7    8268   417.1
    8300   425.7    8334     441    8335   445.8    8336   452.2    8336   455.2
    8414   455.3    9650   451.5    9740     448   10440   445.5   11860   448.5
   12065     444   12090     438   12105     438   12180     450   12480     450
#Mann= 3 ,0,0
   -5950    .055       0    8186     .05       0    8335    .055       0
#XS Ineff= 6 ,-1
    6050    7510     460    7510    8186   445.8    8338   11100   445.8
   11100   11480     460   11480   12180   445.8   12180   12480     460
Permanent Ineff=
       F       F       F       F       F       F
Bank Sta=8186,8335
XS Rating Curve= 0 ,0
Exp/Cntr=0.5,0.3

Type RM Length L Ch R = 3 ,112627  ,,,
BEGIN DESCRIPTION:
Union Pacific Railroad
END DESCRIPTION:
Node Name=UP Railroad
Bridge Culvert--1,0,-1,-1, 0
Deck Dist Width WeirC Skew NumUp NumDn MinLoCord MaxHiCord MaxSubmerge Is_Ogee
1,8,2.6,0, 22, 22, , , 0.95, 0, ,,,
    7520  7545.2  7548.8  7572.2  7575.8  7599.2  7602.8    7629    7629    7826
    7952    8030    8030  8060.3  8065.7  8093.3  8098.7  8126.3  8131.7    8158
    8164    8336
     452  452.05  452.05   452.1   452.1  452.15  452.15   452.2   452.2   452.9
   454.3   454.4   454.4  454.49  454.51  454.59  454.61  454.69  454.71  454.79
  454.81   455.2
   449.2  449.25  449.25   449.3   449.3  449.35  449.35   449.4   452.2   452.9
   454.3   454.4   451.6  451.69  451.71  451.79  451.81  451.89  451.91  451.99
  451.81   452.2
    7520  7545.2  7548.8  7572.2  7575.8  7599.2  7602.8    7629    7629    7826
    7952    8030    8030  8060.3  8065.7  8093.3  8098.7  8126.3  8131.7    8158
    8164    8336
     452  452.05  452.05   452.1   452.1  452.15  452.15   452.2   452.2   452.9
   454.3   454.4   454.4  454.49  454.51  454.59  454.61  454.69  454.71  454.79
  454.81   455.2
   449.2  449.25  449.25   449.3   449.3  449.35  449.35   449.4   452.2   452.9
   454.3   454.4   451.6  451.69  451.71  451.79  451.81  451.89  451.91  451.99
  451.81   452.2
Pier Skew, UpSta & Num, DnSta & Num=  ,7547, 2 ,7547, 2 , 0 , 0 , 0 ,,
     3.6     3.6
     430     450
     3.6     3.6
     430     450
Pier Skew, UpSta & Num, DnSta & Num=  ,7574, 2 ,7574, 2 , 0 , 0 , 0 ,,
     3.6     3.6
     430     450
     3.6     3.6
     430     450
Pier Skew, UpSta & Num, DnSta & Num=  ,7601, 2 ,7601, 2 , 0 , 0 , 0 ,,
     3.6     3.6
     430     450
     3.6     3.6
     430     450
Pier Skew, UpSta & Num, DnSta & Num=  ,8063, 2 ,8063, 2 , 0 , 0 , 0 ,,
     5.4     5.4
     430     454
     5.4     5.4
     430     454
Pier Skew, UpSta & Num, DnSta & Num=  ,8096, 2 ,8096, 2 , 0 , 0 , 0 ,,
     5.4     5.4
     430     454
     5.4     5.4
     430     454
Pier Skew, UpSta & Num, DnSta & Num=  ,8129, 2 ,8129, 2 , 0 , 0 , 0 ,,
     5.4     5.4
     430     454
     5.4     5.4
     430     454
Pier Skew, UpSta & Num, DnSta & Num=  ,8161, 2 ,8161, 2 , 0 , 0 , 0 ,,
       6       6
     430     454
       6       6
     430     454
BR Coef= 1 , 0 , 0 ,1.05, 0 ,,,0.8,-1,0.5,1,
WSPro=,,,, 1 ,,,, 0 ,,,, 0 ,,,,-1 ,-1 ,-1 , 0 , 0 , 0 , 0 , 0
BC Design=,, 0 ,, 0 ,,,,,,
BC HTab HWMax=455.3
BC Use User HTab Curves=0
BC User HTab FreeFlow(D)= 0