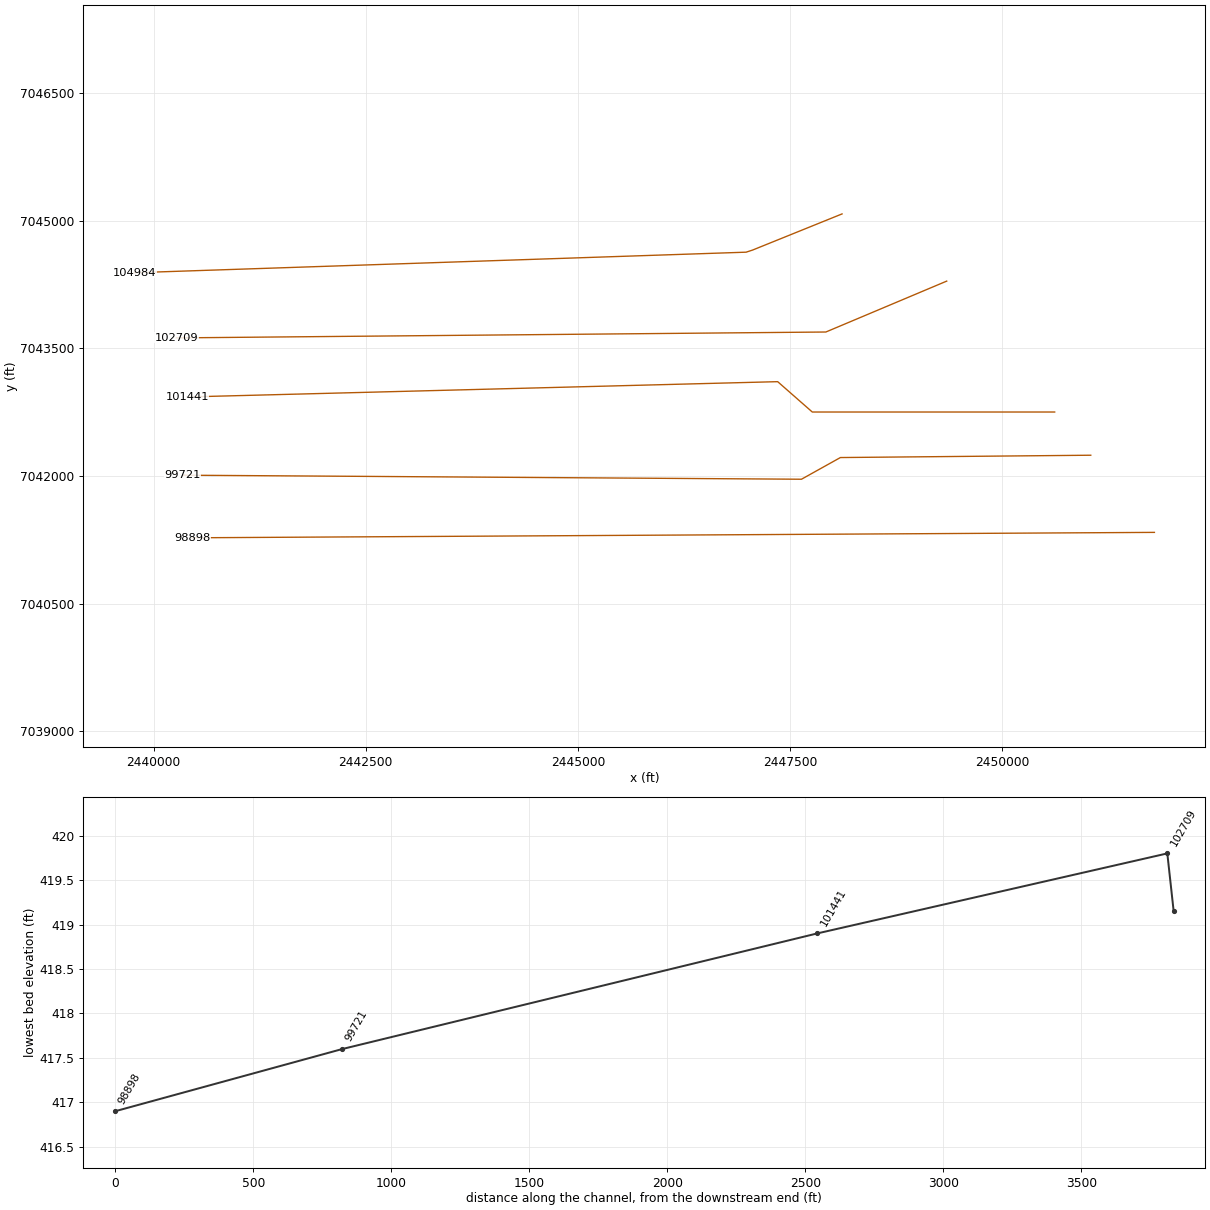
HEC-RAS study CDC_Consolidated_Model.prj: Upper Trinity CDC Consolidated Model

--- CDC_Consolidated_Model.g01 (geometry) --- (continued)

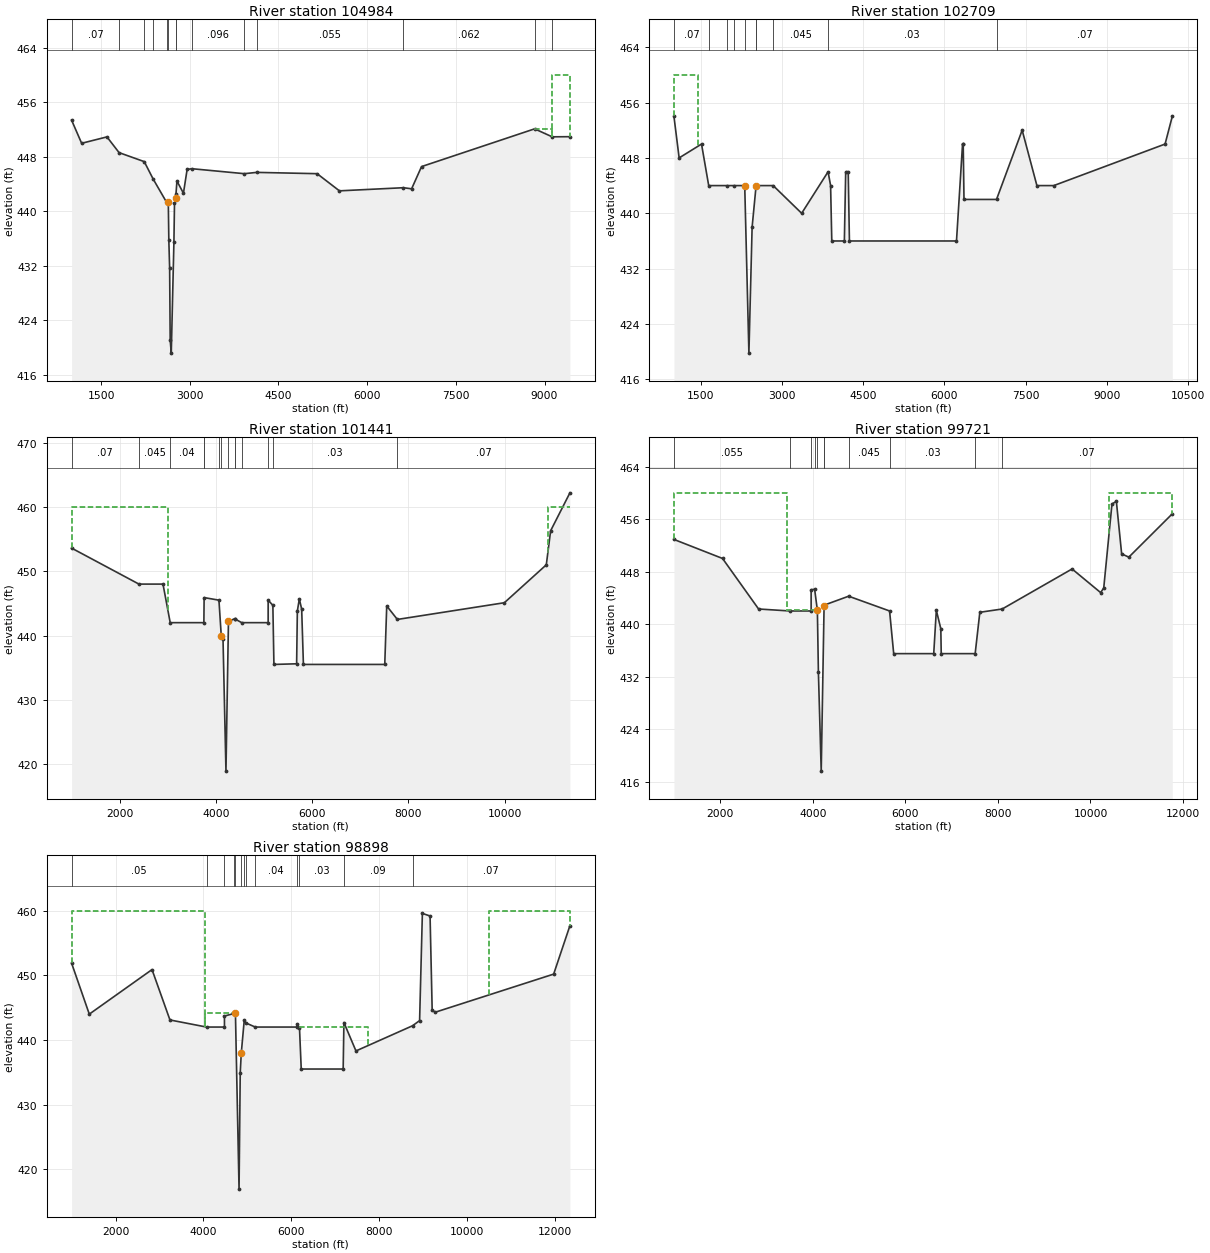
Type RM Length L Ch R = 1 ,104984  ,23,23,23
BEGIN DESCRIPTION:
This cross section corresponds to cross section 104750 of the non-georeferenced CDC model which was the source of this model.
Copy of cross-section 104700.
---------------------------------------------------------------------
CDC COP070199-01 Windsor Estates
Cross-section 104750 - 105600
Located in ROB west of Denton Creek.
---------------------------------------------------------------------
END DESCRIPTION:
XS GIS Cut Line= 4
2448113.084121177045078.379086882447057.470746857044653.08531804
2446982.141501167044628.758923132439775.045022997044387.18558738
#Sta/Elev= 30
 1001.58  453.35 1171.64  449.95 1599.66  450.89 1804.88  448.58 2230.58  447.26
 2380.82  444.71 2617.17  441.16 2637.23   441.4 2646.37   435.7 2660.08  431.59
 2669.21  421.07 2687.48  419.15 2732.44  435.47 2742.16  441.12 2762.81  441.97
 2767.32   442.5 2783.54  444.41 2893.42  442.62 2955.61  446.11  3036.4  446.22
 3923.04  445.49 4133.14  445.68 5154.15  445.49 5531.46  442.97 6614.39  443.43
 6752.52  443.27 6920.44  446.53 8832.78  452.07    9130   450.9 9429.95  450.92
#Mann= 14 ,-1,0
 1001.58     .07       0 1804.88    .076       0 2230.58    .089       0
 2380.82    .096       0 2617.17    .091       0 2637.23     .05       0
 2762.81    .106       0 2767.32    .116       0  3036.4    .096       0
 3923.04    .062       0 4133.14    .055       0 6614.39    .062       0
 8832.78    .025       0    9130     .15       0
#XS Ineff= 4 ,-1
 1001.58 2637.23   441.4 2762.81    8830  441.97    8830    9130     452
    9130  9429.5     460
Permanent Ineff=
       F       F       F       F
Bank Sta=2637.23,2762.81
XS Rating Curve= 0 ,0
Exp/Cntr=0.3,0.1

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
Type RM Length L Ch R = 1 ,102709  ,907,1268,605
BEGIN DESCRIPTION:
This cross section corresponds to cross section 102686 of the non-georeferenced CDC model.
Cross-section generated from topographic file.  Effective flow limit set at IH 35E in LOB.  Denton Creek removed from conveyance in ROB.  Conveyance removed from lake in ROB.  Approx. 300 feet downstream of right bank of Furneaux Creek.
Channel data from NDM Elm Fork channel survey - cross-section EF#125 surveyed  January 1994.
XS 102709 to 97192 retored to 1991 topo  to remove project CAR 062309-01.
END DESCRIPTION:
XS GIS Cut Line= 3
 2449346.20501457044288.79208338 2447922.35189117043690.69715096
2440269.43379802 7043621.4781293
#Sta/Elev= 30
  1008.4     454  1104.3     448  1517.4     450    1650     444    1990     444
    2110     444  2314.8     444    2392   419.8  2451.2     438  2524.8     444
    2530     444    2840     444  3365.7     440  3853.3     446  3899.7     444
  3921.7     436  4153.8     436  4178.4     446  4224.8     446  4247.2     436
  6223.3     436  6335.2     450  6347.4     450  6361.7     442  6962.2     442
  7435.4     452  7707.4     444  8018.6     444   10073     450   10206     454
#Mann= 10 ,-1,0
  1008.4     .07       0    1650     .04       0    1990     .07       0
    2110      .1       0  2314.8     .05       0  2524.8    .045       0
    2530      .1       0    2840    .045       0  3853.3     .03       0
  6962.2     .07       0
#XS Ineff= 3 ,-1
  1008.4    1450     460    1450  2314.8     444  2524.8   10206     444
Permanent Ineff=
       F       F       F
Bank Sta=2314.8,2524.8
XS Rating Curve= 0 ,0
Exp/Cntr=0.3,0.1

Type RM Length L Ch R = 1 ,101441  ,930,1720,870
BEGIN DESCRIPTION:
This cross section corresponds to cross section 101428 of the non-georeferenced CDC model which was the source of this model.
END DESCRIPTION:
XS GIS Cut Line= 4
2450618.600107497042750.521209812447762.271830687042750.52120981
2447354.618118447043107.218002962440395.945027927042927.45786379
#Sta/Elev= 30
    1000   453.6    2400     448    2900     448    3050     442    3750     442
    3755   445.9    4063   445.5    4111     440    4148   439.4    4209   418.9
    4261   442.2    4387   442.6    4390   442.6    4537     442    5086     442
    5086   445.5    5184   444.7    5206   435.5    5678   435.6    5693   443.8
    5734   445.7    5783   444.1    5819   435.5    7510   435.5    7551   444.6
    7772   442.5    9996   445.1   10868     451   10958   456.3   11359   462.2
#Mann= 14 ,-1,0
    1000     .07       0    2400    .045       0    3050     .04       0
    3750      .1       0    3755      .1       0    4063      .1       0
    4111     .05       0    4261      .1       0    4387    .045       0
    4390      .1       0    4537     .04       0    5086    .045       0
    5184     .03       0    7772     .07       0
#XS Ineff= 6 ,-1
    1000    3008     460    3008    4111     440    4261    5130   442.2
   10900   11359     460    5130    7551     442    7551   10900   442.2
Permanent Ineff=
       F       F       F       F       T       F
Bank Sta=4111,4261
XS Rating Curve= 0 ,0
Exp/Cntr=0.3,0.1

Type RM Length L Ch R = 1 ,99721   ,899,823,899
BEGIN DESCRIPTION:
This cross section corresponds to cross section 99708 of the non-georeferenced CDC model which was the source of this model.
END DESCRIPTION:
XS GIS Cut Line= 4
2451043.622879517042242.79223838 2448093.4909845 7042215.4750358
2447634.88002509 7041960.69208082440342.924792777042008.16147405
#Sta/Elev= 30
    1000   452.9    2050     450    2829   442.3    3505     442    3964     442
    3964  445.23    4040   445.3    4099   442.1    4121   432.7    4182   417.6
    4244   442.8    4250   442.9    4775  444.25    5659     442    5748   435.5
    6613   435.5    6669   442.1    6766   439.3    6775   435.5    7508   435.5
    7609   441.8    8092   442.3    9602   448.4   10219   444.8   10286   445.5
   10464   458.3   10559   458.7   10673   450.7   10828   450.2   11767   456.8
#Mann= 11 ,-1,0
    1000    .055       0    3505     .04       0    3964      .1       0
    4040    .055       0    4099     .05       0    4244    .045       0
    4250      .1       0    4775    .045       0    5659     .03       0
    7508     .09       0    8092     .07       0
#XS Ineff= 4 ,-1
    1000    3453     460    3453    4099   442.1    5511    7827     442
   10400   11767     460
Permanent Ineff=
       F       F       T       F
Bank Sta=4099,4244
XS Rating Curve= 0 ,0
Exp/Cntr=0.3,0.1

Type RM Length L Ch R = 1 ,98898   ,920,965,900
BEGIN DESCRIPTION:
This cross section corresponds to cross section 98884 of the non-georeferenced CDC model which was the source of this model.
Cross-section EF123.  Effective flow limit set at sta 4030 in LOB, at sta 10500 in ROB.  Denton Creek removed from conveyance in ROB.
Conveyance removed from lake in ROB.
Channel data from NDM Elm Fork channel survey.
END DESCRIPTION:
XS GIS Cut Line= 2
2451793.58496225 7041336.08112532440455.763149777041272.52350964
#Sta/Elev= 30
    1000   451.9    1403     444    2830   450.9    3238   443.1    4070     442
    4478     442    4478  443.71    4700   444.1    4728   444.1    4810   416.9
    4837   434.9    4861     438    4929   443.1    4960  442.65    5179     442
    6130     442    6130   442.4    6185   441.9    6225   435.5    7179   435.5
    7196   442.7    7470   438.3    8757   442.2    8918     443    8981   459.6
    9156   459.2    9204   444.6    9275   444.3   11968   450.2   12338   457.7
#Mann= 13 ,-1,0
    1000     .05       0    4070     .04       0    4478      .1       0
    4700     .05       0    4728    .045       0    4861      .1       0
    4929    .045       0    4960      .1       0    5179     .04       0
    6130    .045       0    6185     .03       0    7196     .09       0
    8757     .07       0
#XS Ineff= 4 ,-1
    1000    4030     460    4030    4728   444.1    6164    7753     442
   10500   12338     460
Permanent Ineff=
       F       F       T       F
Bank Sta=4728,4861
XS Rating Curve= 0 ,0
Exp/Cntr=0.3,0.1