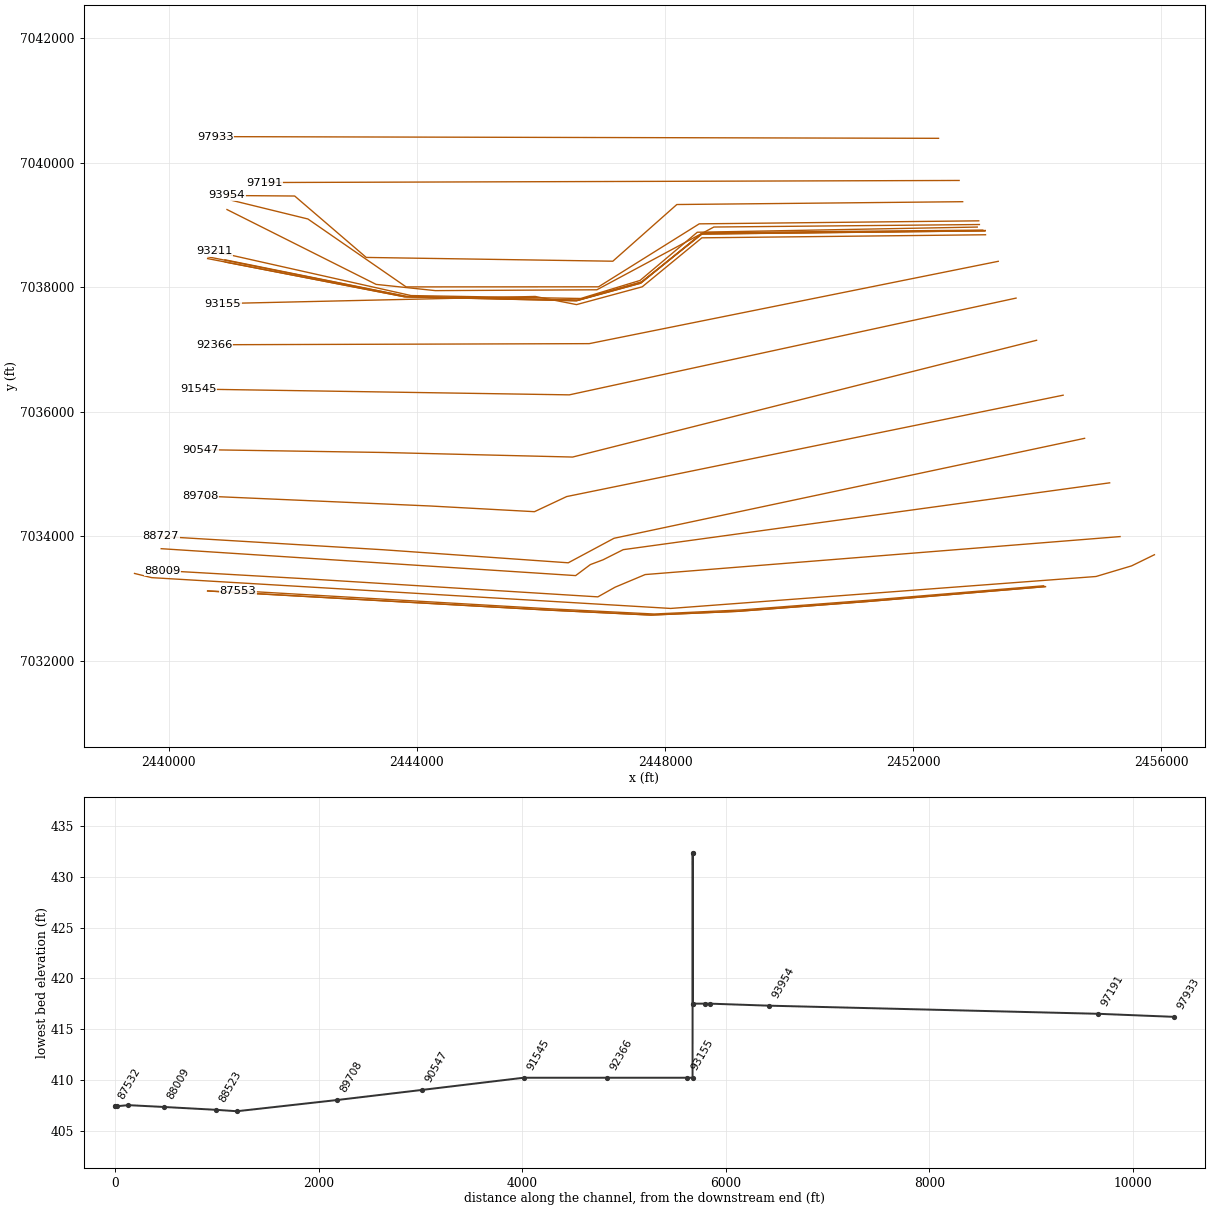
HEC-RAS study CDC_Consolidated_Model.prj: Upper Trinity CDC Consolidated Model

--- CDC_Consolidated_Model.g01 (geometry) --- (continued)

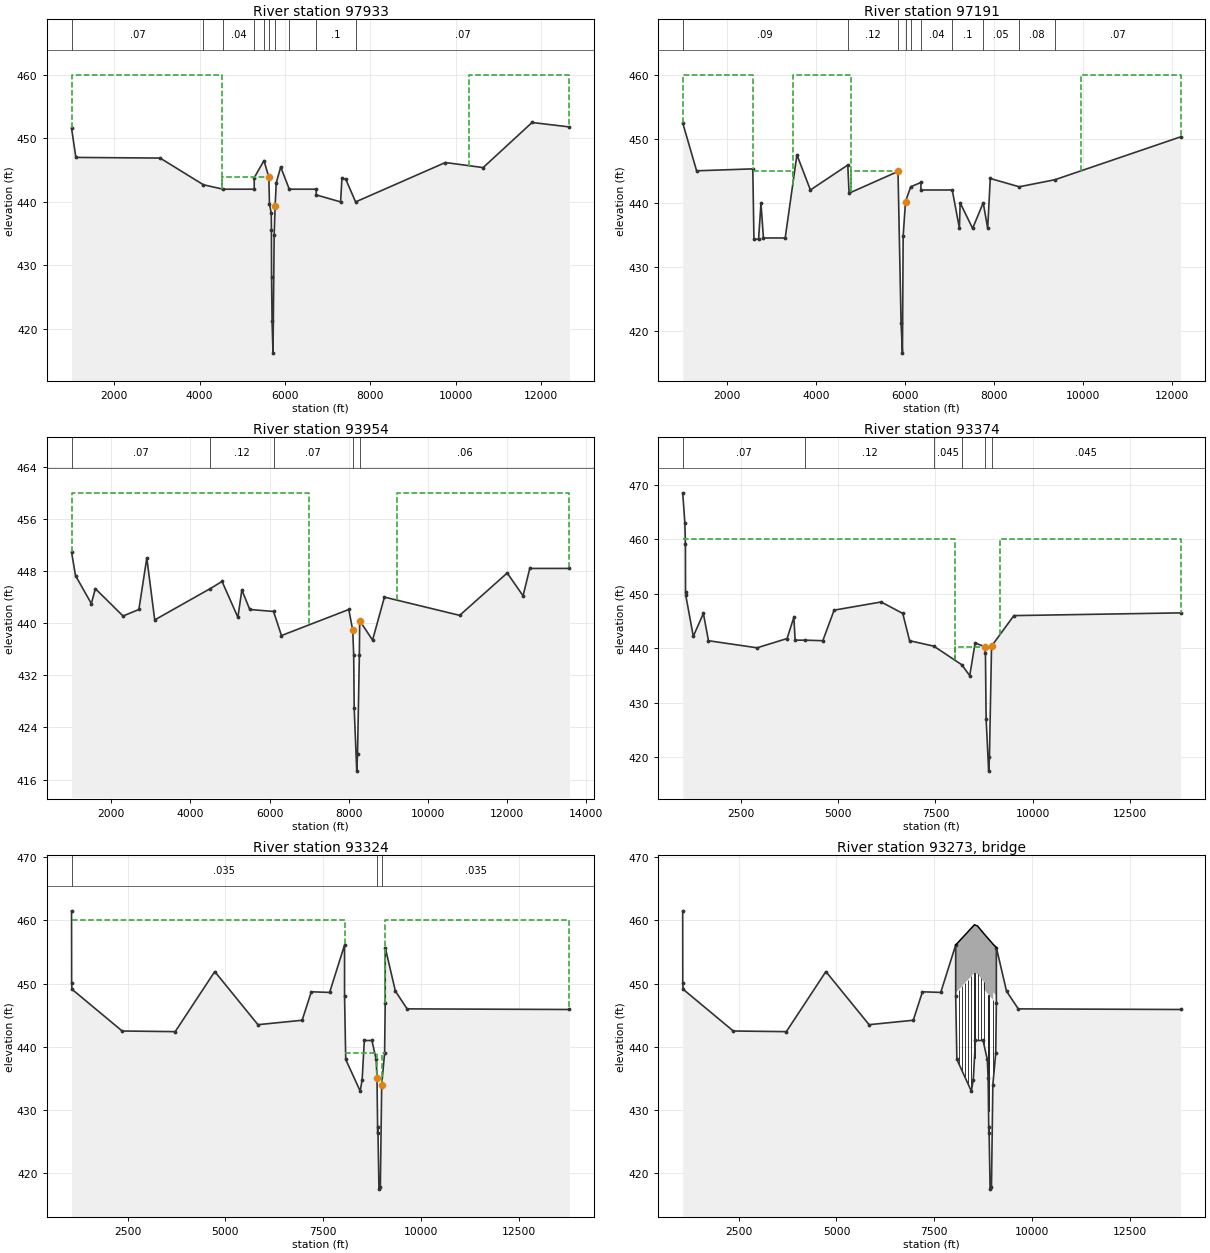
Type RM Length L Ch R = 1 ,97933   ,701,742,701
BEGIN DESCRIPTION:
This cross section corresponds to cross section 97919 of the non-georeferenced CDC model which was the source of this model.
Cross-section EF122.  Effective flow limit set at sta 4517 in LOB, at sta 10300 in ROB.  Denton Creek removed from conveyance in ROB.
Channel data from NDM Elm Fork channel survey - cross-section EF#122 surveyed December 1993.
END DESCRIPTION:
XS GIS Cut Line= 2
2452408.071922247040392.980977392440749.103770437040420.18794397
#Sta/Elev= 30
    1000   451.6    1101     447    3074   446.9    4087   442.7    4547     442
    5278     442    5278  443.81    5506   446.5    5620   443.9    5635   439.7
    5677   438.2    5681   435.5    5684   428.2    5696   421.2    5718   416.2
    5745   434.8    5767   439.3    5794     443    5898   445.5    6099     442
    6730     442    6730   441.1    7301     440    7332   443.7    7420   443.6
    7652     440    9755   446.2   10639   445.4   11785   452.5   12659   451.8
#Mann= 10 ,-1,0
    1000     .07       0    4087     .05       0    4547     .04       0
    5278      .1       0    5506      .1       0    5620     .05       0
    5767      .1       0    6099     .04       0    6730      .1       0
    7652     .07       0
#XS Ineff= 4 ,-1
    1000    4517     460    4517    5620   443.9    5767   10300   439.3
   10300   12659     460
Permanent Ineff=
       F       F       F       F
Bank Sta=5620,5767
XS Rating Curve= 0 ,0
Exp/Cntr=0.3,0.1

Type RM Length L Ch R = 1 ,97191   ,2199,3237,1350
BEGIN DESCRIPTION:
This cross section corresponds to cross section 97178 of the non-georeferenced CDC model which was the source of this model.
Cross-section EF121.  Effective flow limit set at sta 4780 in LOB, at sta 9950 in ROB.  Denton Creek removed from conveyance in ROB.
Channel data from NDM Elm Fork channel survey.
END DESCRIPTION:
XS GIS Cut Line= 2
2452739.651967767039715.766124472441539.700942527039682.66481271
#Sta/Elev= 30
    1000   452.5    1313     445    2577   445.3    2603   434.3    2707   434.3
    2761   439.9    2817   434.5    3306   434.5    3570   447.5    3873     442
    4714   445.9    4743   441.5    5844   444.9    5913   421.2    5944   416.5
    5960   434.8    6013   440.2    6130   442.5    6360  443.18    6360     442
 7064.45     442  7225.9     436  7241.9     440  7522.7     436  7761.2     440
  7861.8     436  7919.6   443.8    8571   442.5    9372   443.6   12200   450.3
#Mann= 10 ,-1,0
    1000     .09       0    4714     .12       0    5844     .05       0
    6013    .045       0    6130      .1       0    6360     .04       0
 7064.45      .1       0  7761.2     .05       0    8571     .08       0
    9372     .07       0
#XS Ineff= 6 ,-1
    1000    2577     460    4780    5844   444.9    6013    9950   440.2
    9950   12200     460    2577    3475     445    3475    4780     460
Permanent Ineff=
       F       F       F       F       T       F
Bank Sta=5844,6013
XS Rating Curve= 0 ,0
Exp/Cntr=0.3,0.1

Type RM Length L Ch R = 1 ,93954   ,649,580,459
BEGIN DESCRIPTION:
This cross section corresponds to cross section 93940 of the non-georeferenced CDC model which was the source of this model.
--------------------------------------------
CDC CAR062309-1 WTP Pre-Sedimentation Basins
Cross-section 93940 - 105167
--------------------------------------------
Bridge blocked ROB as part of the project for SPF only.
No other impacts to 100-year or SPF conveyance models.
Cross-section generated from topographic file.  Effective flow limit set at sta 7000 in LOB, at sta 9220 in ROB.
Channel data from NDM channel survey.
END DESCRIPTION:
XS GIS Cut Line= 6
2452796.764058267039374.541085142448190.277864437039329.19406296
2447158.79895625 7038418.3231813 2443184.57199667038479.04812546
2442031.742937427039465.825023292440936.748789827039474.25203951
#Sta/Elev= 30
    1000   450.9    1100   447.3    1500     443    1600   445.3    2300   441.1
    2700   442.1    2900     450    3100   440.5    4500   445.3    4800   446.4
    5200   440.9    5300   445.1    5500   442.1    6100   441.8    6300   438.1
    8000   442.1    8100   438.9    8124   435.1    8136     427    8201   417.3
    8221     420    8267   435.1    8275   440.4    8600   437.4    8900     444
   10800   441.2   12000   447.7   12400   444.2   12570   448.4   13570   448.4
#Mann= 5 ,-1,0
    1000     .07       0    4500     .12       0    6100     .07       0
    8100     .05       0    8275     .06       0
#XS Ineff= 4 ,-1
    1000    7000     460    7000    8100   438.9    8275    9220   440.4
    9220   13570     460
Permanent Ineff=
       F       F       F       F
Bank Sta=8100,8275
XS Rating Curve= 0 ,0
Exp/Cntr=0.3,0.1

Type RM Length L Ch R = 1 ,93374   ,50,50,50
BEGIN DESCRIPTION:
This cross section corresponds to cross section 93359 of the non-georeferenced CDC model which was the source of this model.
Cross-section EF120.  62 feet upstream of Sandy Lake Road.  Effective flow limit set at sta 8000 in LOB, at sta 9150 in ROB.
Channel data from NDM Elm Fork channel survey - cross-section EF#120 surveyed January 1994.
END DESCRIPTION:
XS GIS Cut Line= 6
2453055.818986337039066.976083472448551.367037277039018.65006463
2446928.598957337038007.054974972443827.059884857038005.64520088
2442244.274008427039096.973070712441008.350427037039398.64766707
#Sta/Elev= 30
    1000   468.5    1056     463    1070   459.2    1073   450.4    1080   449.7
    1272   442.2    1532   446.4    1663   441.4    2912   440.1    3684   441.8
    3859   445.7    3891   441.5    4146   441.5    4603   441.4    4893     447
    6103   448.5    6658   446.4    6834   441.4    7457   440.4    8174     437
    8380     435    8519     441    8766   440.3    8784   439.1    8802     427
    8867   417.5    8887     420    8941   440.4    9515     446   13800   446.5
#Mann= 6 ,-1,0
    1000     .07       0    4146     .12       0    7457    .045       0
    8174    .035       0    8766     .05       0    8941    .045       0
#XS Ineff= 4 ,-1
    1000    8000     460    8000    8766   440.3    8941    9150   440.4
    9150   13800     460
Permanent Ineff=
       F       F       F       F
Bank Sta=8766,8941
XS Rating Curve= 0 ,0
Exp/Cntr=0.3,0.1

Type RM Length L Ch R = 1 ,93324   ,113,113,113
BEGIN DESCRIPTION:
This cross section corresponds to cross section 93297 of the non-georeferenced CDC model which was the source of this model.
Upstream bounding cross-section for Sandy Lake Road bridge
END DESCRIPTION:
XS GIS Cut Line= 6
2453066.561747017039007.696674472448786.985660497038967.59209588
2446901.668565017037959.034729792444298.008746097037945.72931021
2443344.115968857038045.839674292440940.747899967039248.27824411
#Sta/Elev= 30
    1068   461.5    1070   450.1    1079   449.1    2362   442.5    3719   442.4
    4730   451.9    5835   443.5    6965   444.2    7200   448.7    7668   448.6
    8050   456.1    8050     448    8080     438    8450     433    8500   434.8
    8555     441    8750     441    8858     438    8880     435    8897   426.3
    8902   427.4    8930   417.5    8965   417.8    9000     434    9074     439
    9090     447    9090   455.7    9350   448.8    9650     446   13800   445.9
#Mann= 3 ,0,0
    1068    .035       0    8880     .03       0    9000    .035       0
#XS Ineff= 4 ,-1
    1068    8050     460    8050    8880     439    9000    9090     439
    9090   13800     460
Permanent Ineff=
       F       F       F       F
Bank Sta=8880,9000
XS Rating Curve= 0 ,0
Exp/Cntr=0.3,0.1

Type RM Length L Ch R = 3 ,93273   ,,,
BEGIN DESCRIPTION:
Sandy Lake Road
Note:  Bridge and roadway modeled from plans dated Dec. 1996 and stamped Dec. 1997.
END DESCRIPTION:
Node Name=Sandy Lake Road
Bridge Culvert--1,0,-1,-1, 0
Deck Dist Width WeirC Skew NumUp NumDn MinLoCord MaxHiCord MaxSubmerge Is_Ogee
10,83,2.6,0, 8, 8, , , 0.95, 0, ,,,
    8050    8530    8610    8770    8770    9010    9010    9090
   456.1   459.3   459.1   457.9   457.9   456.2   456.2   455.7
   448.5   451.7   451.5   450.3   449.1   447.4   448.6   448.1
    8050    8530    8610    8770    8770    9010    9010    9090
   456.1   459.3   459.1   457.9   457.9   456.2   456.2   455.7
   448.5   451.7   451.5   450.3   449.1   447.4   448.6   448.1
Pier Skew, UpSta & Num, DnSta & Num=  ,8130, 2 ,8130, 2 , 0 , 0 , 0 ,,
     2.5     2.5
     425     452
     2.5     2.5
     425     452
Pier Skew, UpSta & Num, DnSta & Num=  ,8210, 2 ,8210, 2 , 0 , 0 , 0 ,,
     2.5     2.5
     425     452
     2.5     2.5
     425     452
Pier Skew, UpSta & Num, DnSta & Num=  ,8290, 2 ,8290, 2 , 0 , 0 , 0 ,,
     2.5     2.5
     425     452
     2.5     2.5
     425     452
Pier Skew, UpSta & Num, DnSta & Num=  ,8370, 2 ,8370, 2 , 0 , 0 , 0 ,,
     2.5     2.5
     425     452
     2.5     2.5
     425     452
Pier Skew, UpSta & Num, DnSta & Num=  ,8450, 2 ,8450, 2 , 0 , 0 , 0 ,,
     2.5     2.5
     425     452
     2.5     2.5
     425     452
Pier Skew, UpSta & Num, DnSta & Num=  ,8530, 2 ,8530, 2 , 0 , 0 , 0 ,,
     2.5     2.5
     425     453
     2.5     2.5
     425     453
Pier Skew, UpSta & Num, DnSta & Num=  ,8610, 2 ,8610, 2 , 0 , 0 , 0 ,,
     2.5     2.5
     425     453
     2.5     2.5
     425     453
Pier Skew, UpSta & Num, DnSta & Num=  ,8690, 2 ,8690, 2 , 0 , 0 , 0 ,,
     2.5     2.5
     425     452
     2.5     2.5
     425     452
Pier Skew, UpSta & Num, DnSta & Num=  ,8770, 2 ,8770, 2 , 0 , 0 , 0 ,,
       3       3
     425     452
       3       3
     425     452
Pier Skew, UpSta & Num, DnSta & Num=  ,8890, 2 ,8890, 2 , 0 , 0 , 0 ,,
       3       3
     425     452
       3       3
     425     452
Pier Skew, UpSta & Num, DnSta & Num=  ,9010, 2 ,9010, 2 , 0 , 0 , 0 ,,
       3       3
     425     452
       3       3
     425     452
BR Coef= 1 , 0 , 0 ,1.05, 0 ,,,0.8,-1,0.5,1,
WSPro=,,,, 1 ,,,, 0 ,,,, 0 ,,,,-1 ,-1 ,-1 , 0 , 0 , 0 , 0 , 0
BC Design=,, 0 ,, 0 ,,,,,,
BC Use User HTab Curves=0
BC User HTab FreeFlow(D)= 0

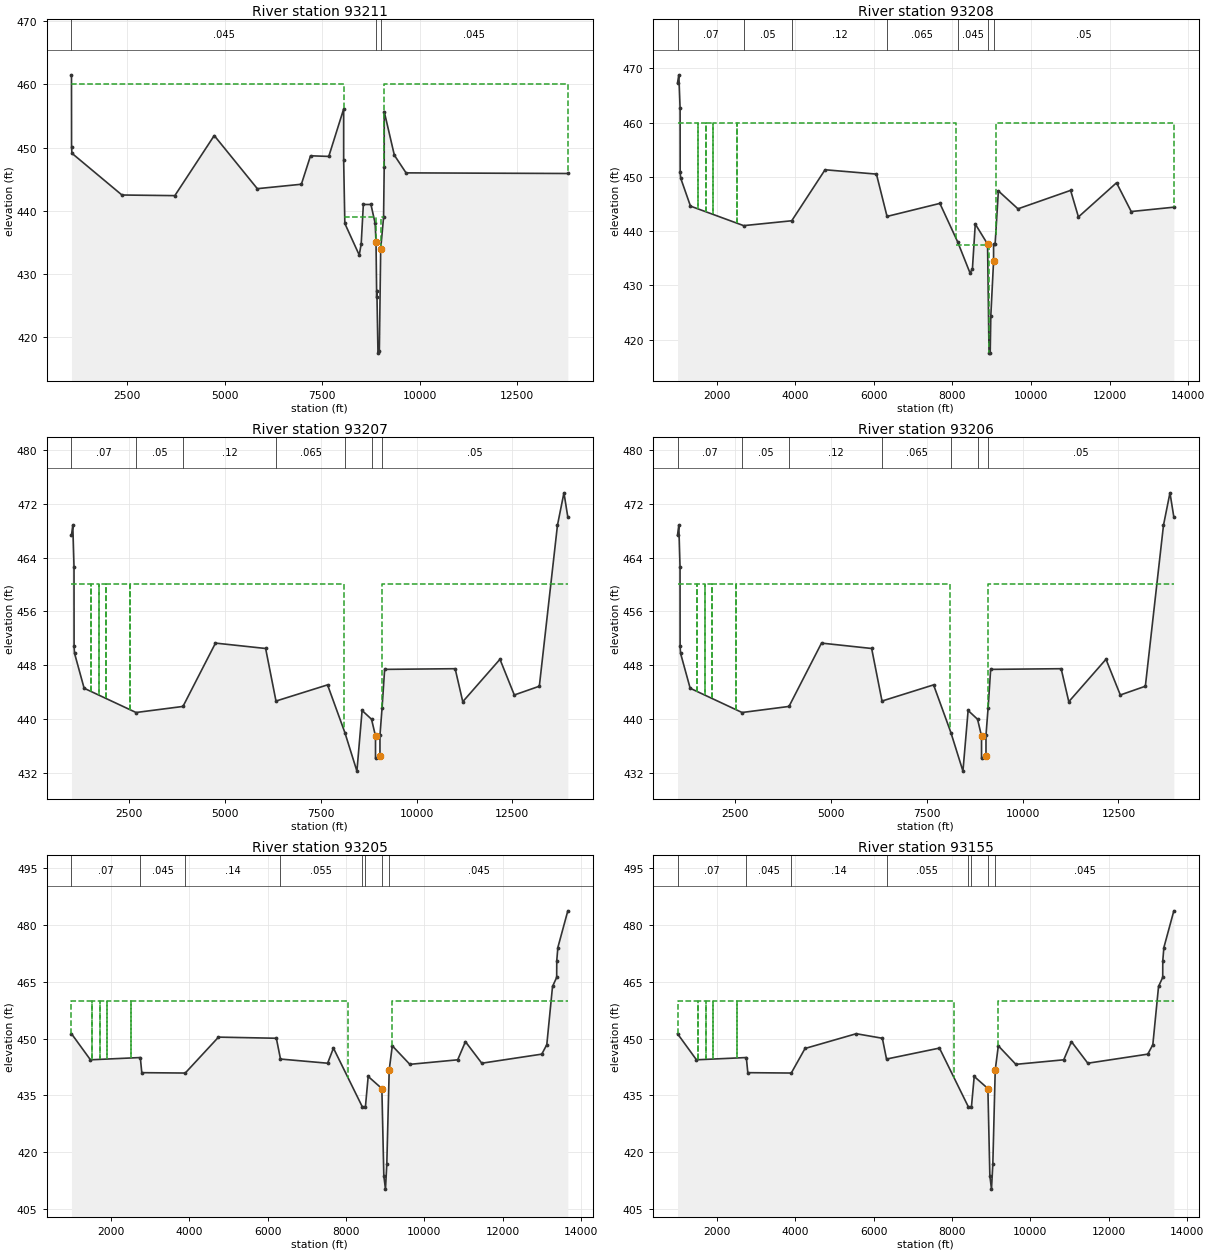
Type RM Length L Ch R = 1 ,93211   ,2,3,4
BEGIN DESCRIPTION:
This cross section corresponds to cross section 93212 of the non-georeferenced CDC model which was the source of this model.
Downstream bounding cross-section for Sandy Lake Road bridge
END DESCRIPTION:
XS GIS Cut Line= 6
2453032.140556017038966.992687632448520.069527697038883.64377296
2447597.799390587038109.242434642446642.141196947037819.29157096
2443907.252637837037866.266214552440736.861069247038575.79107872
#Sta/Elev= 30
    1068   461.5    1070   450.1    1079   449.1    2362   442.5    3719   442.4
    4730   451.9    5835   443.5    6965   444.2    7200   448.7    7668   448.6
    8050   456.1    8050     448    8080     438    8450     433    8500   434.8
    8555     441    8750     441    8858     438    8880     435    8897   426.3
    8902   427.4    8930   417.5    8965   417.8    9000     434    9074     439
    9090     447    9090   455.7    9350   448.8    9650     446   13800   445.9
#Mann= 3 ,0,0
    1068    .045       0    8880     .05       0    9000    .045       0
#XS Ineff= 4 ,-1
    1068    8050     460    8050    8880     439    9000    9090     439
    9090   13800     460
Permanent Ineff=
       F       F       F       F
Bank Sta=8880,9000
XS Rating Curve= 0 ,0
Exp/Cntr=0.3,0.1

Type RM Length L Ch R = 1 ,93208   ,1,1,1
BEGIN DESCRIPTION:
This cross section corresponds to cross section 93197 of the non-georeferenced CDC model which was the source of this model.
One-foot upstream of Carrollton Dam.  Duplication of previous cross-section (93191) with existing channel.
Channel data from NDM Elm Fork channel survey.
END DESCRIPTION:
XS GIS Cut Line= 6
2453120.484211337038918.043638542448624.117547937038876.03912938
2447622.075260677038085.549240542446594.051726167037793.92941697
2443835.875484027037852.248854132440907.53535428 7038441.0544172
#Sta/Elev= 30
    1000   467.3    1034   468.8    1066   462.6    1068   450.8    1079   449.8
    1330   444.6    2684     441    3908   441.9    4756   451.3    6064   450.5
    6334   442.7    7679   445.1    8132     438    8445   432.3    8507     433
    8580   441.3    8893   437.6    8930   417.5    8960   417.5    8976   424.4
    9046   434.5    9046   437.6    9086   437.7    9168   447.4    9667   444.1
   11007   447.5   11206   442.6   12176   448.9   12550   443.6   13635   444.4
#Mann= 7 ,-1,0
    1000     .07       0    2684     .05       0    3908     .12       0
    6334    .065       0    8132    .045       0    8893     .05       0
    9046     .05       0
#XS Ineff= 8 ,-1
    1000    1520     460    8100    8930   437.5    9046    9100   434.5
    9100   13635     460    1520    1730     460    1730    1900     460
    1900    2520     460    2520    8100     460
Permanent Ineff=
       F       F       F       F       T       F       T       F
Bank Sta=8893,9046
XS Rating Curve= 0 ,0
Exp/Cntr=0.3,0.1

Type RM Length L Ch R = 1 ,93207   ,1,1,1
BEGIN DESCRIPTION:
This cross section corresponds to cross section 93196 of the non-georeferenced CDC model which was the source of this model.
Carrollton Dam
Upstream face of dam.
END DESCRIPTION:
XS GIS Cut Line= 6
2453161.383407747038911.607299722448592.968660097038861.20648189
2447619.803611677038082.320244392446590.514987837037792.19451229
2443830.769195027037851.319065972440636.833981847038488.36241131
#Sta/Elev= 30
    1000   467.3    1034   468.8    1066   462.6    1068   450.8    1079   449.8
    1330   444.6    2684     441    3908   441.9    4756   451.3    6064   450.5
    6334   442.7    7679   445.1    8132     438    8445   432.3    8580   441.3
    8826     440    8930   437.5    8930   434.2    9046   434.5    9046   437.6
    9100   441.6    9168   447.4   11007   447.5   11206   442.6   12176   448.9
   12550   443.6   13203   444.9   13676   468.8   13845   473.6   13946     470
#Mann= 7 ,-1,0
    1000     .07       0    2684     .05       0    3908     .12       0
    6334    .065       0    8132    .045       0    8826     .02       0
    9100     .05       0
#XS Ineff= 8 ,-1
    1000    1520     460    8100    8930   437.5    9046    9100   434.5
    9100   13946     460    1520    1730     460    1730    1900     460
    1900    2520     460    2520    8100     460
Permanent Ineff=
       F       F       F       F       T       F       T       F
Bank Sta=8930,9046
XS Rating Curve= 0 ,0
Exp/Cntr=0.3,0.1

Type RM Length L Ch R = 1 ,93206   ,1,1,1
BEGIN DESCRIPTION:
This cross section corresponds to cross section 93191 of the non-georeferenced CDC model which was the source of this model.
Carrollton Dam
Weir crest length approx. 106 feet, minimum weir crest elev. 433.70.  Weir data from surveyed cross-section of structure.  Ground points from cross-section EF118.  Effective flow limit set at sta 8100 in LOB at sta 9100 in ROB. Carrollton Landfill in LOB, Riverchase project in ROB.
END DESCRIPTION:
XS GIS Cut Line= 6
2453153.701992667038906.782834312448582.513956587038855.67696539
2447608.631061857038066.236943222446572.952030847037783.50916222
2443805.37685734 7037846.64322232440628.477043187038460.56751938
#Sta/Elev= 30
    1000   467.3    1034   468.8    1066   462.6    1068   450.8    1079   449.8
    1330   444.6    2684     441    3908   441.9    4756   451.3    6064   450.5
    6334   442.7    7679   445.1    8132     438    8445   432.3    8580   441.3
    8826     440    8930   437.5    8930   434.2    9046   434.5    9046   437.6
    9100   441.6    9168   447.4   11007   447.5   11206   442.6   12176   448.9
   12550   443.6   13203   444.9   13676   468.8   13845   473.6   13946     470
#Mann= 7 ,-1,0
    1000     .07       0    2684     .05       0    3908     .12       0
    6334    .065       0    8132    .045       0    8826     .02       0
    9100     .05       0
#XS Ineff= 8 ,-1
    1000    1520     460    8100    8930     432    9046    9100   434.5
    9100   13946     460    1520    1730     460    1730    1900     460
    1900    2520     460    2520    8100     460
Permanent Ineff=
       F       F       F       F       T       F       T       F
Bank Sta=8930,9046
XS Rating Curve= 0 ,0
Exp/Cntr=0.3,0.1

Type RM Length L Ch R = 1 ,93205   ,50,50,50
BEGIN DESCRIPTION:
This cross section corresponds to cross section 93190 of the non-georeferenced CDC model which was the source of this model.
END DESCRIPTION:
XS GIS Cut Line= 6
      2453153.74      7038905.78     2448582.553     7038854.674
      2447608.67     7038065.234     2446572.991     7037782.506
     2443805.416     7037845.641   2440912.26527   7038404.73134
#Sta/Elev= 30
    1000   451.3    1483   444.4    2755     445    2793     441    3901   440.9
    4749   450.4    6224   450.1    6330   444.6    7532   443.5    7680   447.5
    8415     432    8496     432    8566     440    8915   436.8    8965   413.7
    9007   410.2    9041   416.8    9102   441.7    9181   448.1    9628   443.2
   10849   444.4   11046   449.2   11463   443.5   12993   445.9   13121   448.4
   13267   463.8   13373   466.2   13375   470.6   13403   474.1   13657   483.8
#Mann= 8 ,-1,0
    1000     .07       0    2755    .045       0    3901     .14       0
    6330    .055       0    8415    .035       0    8496     .12       0
    8915     .05       0    9102    .045       0
#XS Ineff= 8 ,-1
    1000    1520     460    8050    8915   436.8    9102    9181   441.7
    9181   13657     460    1520    1730     460    1730    1900     460
    1900    2520     460    2520    8050     460
Permanent Ineff=
       F       F       F       F       T       F       T       F
Bank Sta=8915,9102
XS Rating Curve= 0 ,0
Exp/Cntr=0.3,0.1

Type RM Length L Ch R = 1 ,93155   ,759,789,739
BEGIN DESCRIPTION:
This cross section corresponds to cross section 93141 of the non-georeferenced CDC model which was the source of this model.
END DESCRIPTION:
XS GIS Cut Line= 6
2453165.058925337038843.361045142448594.03788367 7038794.2240043
2447632.440069357038006.71606489  2446574.4408737037721.01223996
2445907.796865087037851.960140792440871.561530777037738.01909572
#Sta/Elev= 30
    1000   451.3    1483   444.4    2755     445    2793     441    3901   440.9
    4252   447.4    5558   451.3    6224   450.1    6330   444.6    7680   447.5
    8415     432    8496     432    8566     440    8915   436.8    8965   413.7
    9007   410.2    9041   416.8    9102   441.7    9181   448.1    9628   443.2
   10849   444.4   11046   449.2   11463   443.5   12993   445.9   13121   448.4
   13267   463.8   13373   466.2   13375   470.6   13403   474.1   13657   483.8
#Mann= 8 ,-1,0
    1000     .07       0    2755    .045       0    3901     .14       0
    6330    .055       0    8415    .035       0    8496     .12       0
    8915     .05       0    9102    .045       0
#XS Ineff= 8 ,-1
    1000    1520     460    8050    8915   436.8    9102    9181   441.7
    9181   13657     460    1520    1730     460    1900    2520     460
    2520    8050     460    1730    1900     460
Permanent Ineff=
       F       F       F       F       T       T       F       F
Bank Sta=8915,9102
XS Rating Curve= 0 ,0
Exp/Cntr=0.3,0.1

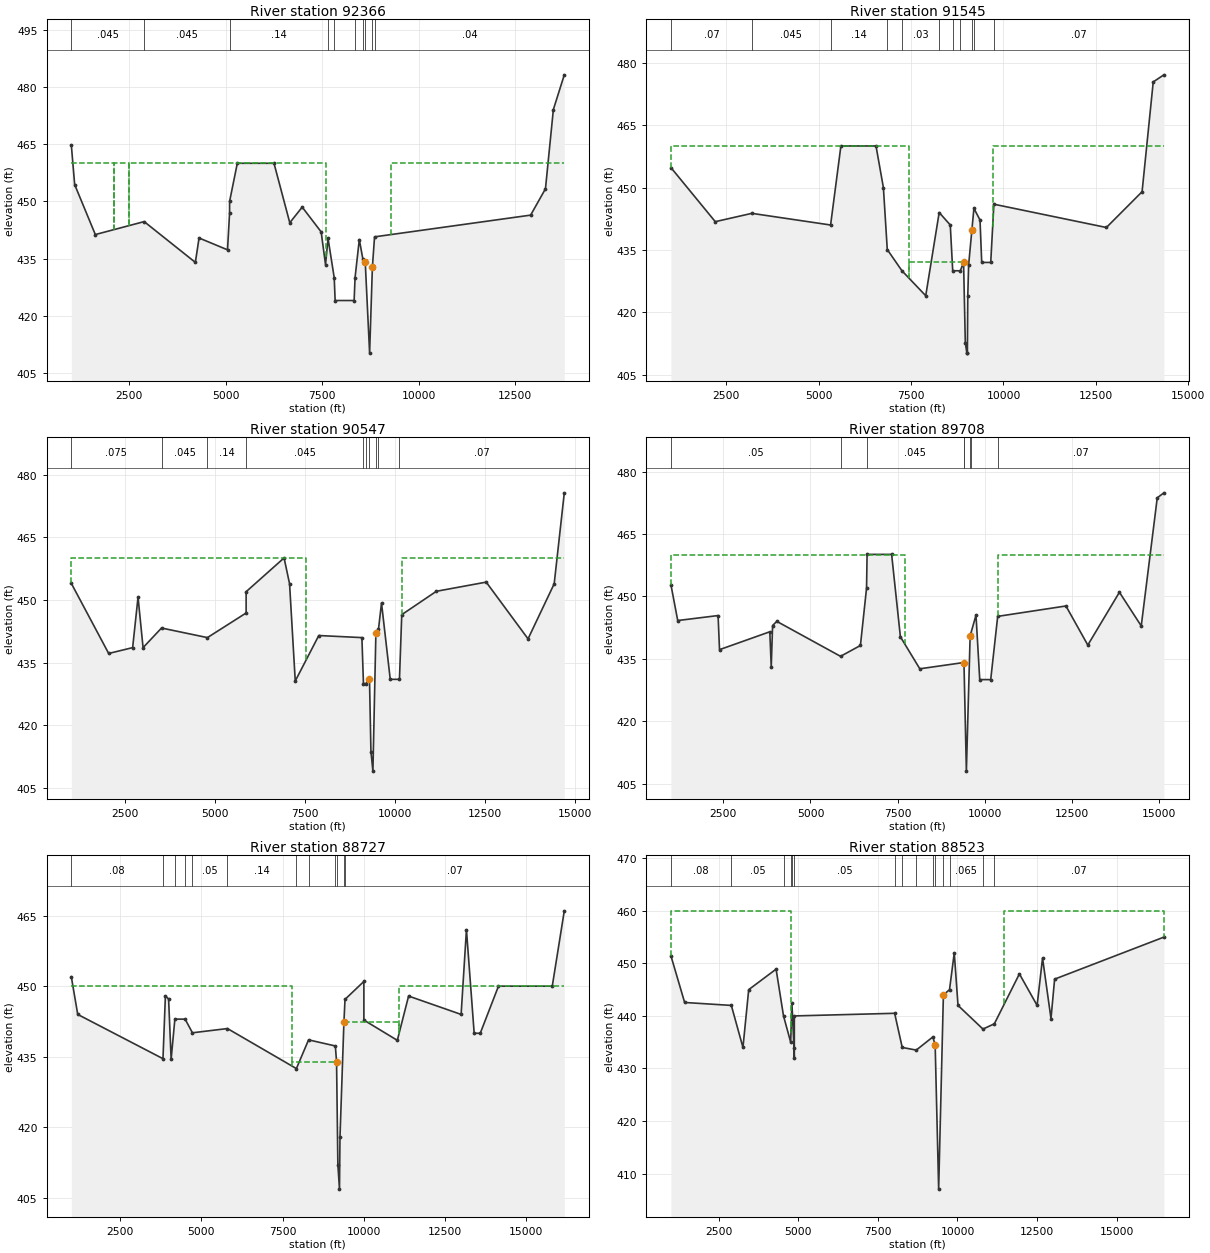
Type RM Length L Ch R = 1 ,92366   ,820,821,820
BEGIN DESCRIPTION:
This cross section corresponds to cross section 92351 of the non-georeferenced CDC model which was the source of this model.
END DESCRIPTION:
XS GIS Cut Line= 3
2453370.468947597038416.698184552446778.237053337037093.70312713
2440731.940090847037076.10801797
#Sta/Elev= 30
    1000   464.8    1087   454.4    1622   441.3    2887   444.7    4213     434
    4309   440.4    5046   437.3    5100     447    5100     450    5300     460
    6250     460    6659   444.4    6981   448.5    7472     442    7585   433.4
    7650   440.3    7810     430    7834     424    8326     424    8350     430
    8460     440    8550     435    8613   434.2    8727   410.2    8799   432.8
    8855   440.7   12898   446.4   13282   453.3   13487   474.1   13770   483.2
#Mann= 10 ,-1,0
    1000    .045       0    2887    .045       0    5100     .14       0
    7650     .05       0    7810     .03       0    8350     .05       0
    8550     .14       0    8613     .05       0    8799     .14       0
    8855     .04       0
#XS Ineff= 6 ,-1
    1000    2100     460    7600    8613   434.2    8799    9270   432.8
    9270   13770     460    2100    2500     460    2500    7600     460
Permanent Ineff=
       F       F       F       F       T       F
Bank Sta=8613,8799
XS Rating Curve= 0 ,0
Exp/Cntr=0.3,0.1

Type RM Length L Ch R = 1 ,91545   ,1000,998,1000
BEGIN DESCRIPTION:
This cross section corresponds to cross section 91530 of the non-georeferenced CDC model which was the source of this model.
END DESCRIPTION:
XS GIS Cut Line= 3
2453657.147836187037825.518920722446457.170110177036270.74315888
2440481.816903417036362.92932622
#Sta/Elev= 30
    1000   454.8    2200   441.8    3190   443.8    5321     441    5600     460
    6550     460    6750     450    6855   435.1    7252     430    7896     424
    8260     444    8560     441    8626     430    8832     430    8920     432
    8967   412.7    9009   410.2    9023   410.2    9034     424    9057   431.4
    9145   439.8    9200     445    9365   442.2    9411     432    9655     432
    9740     446   12785   440.4   13751     449   14053   475.4   14342   477.1
#Mann= 11 ,-1,0
    1000     .07       0    3190    .045       0    5321     .14       0
    6855    .035       0    7252     .03       0    8260    .045       0
    8626     .03       0    8832     .05       0    9145     .14       0
    9200    .035       0    9740     .07       0
#XS Ineff= 4 ,-1
    1000    7450     460    7450    8920     432    9145    9706   439.8
    9706   14342     460
Permanent Ineff=
       F       F       F       F
Bank Sta=8920,9145
XS Rating Curve= 0 ,0
Exp/Cntr=0.3,0.1

Type RM Length L Ch R = 1 ,90547   ,651,839,951
BEGIN DESCRIPTION:
This cross section corresponds to cross section 90532 of the non-georeferenced CDC model which was the source of this model.
END DESCRIPTION:
XS GIS Cut Line= 4
2453987.691138337037147.536024722446511.170002167035271.50893688
2443460.91166702 7035345.00649332440514.705617167035390.60810813
#Sta/Elev= 30
    1000     454    2039   437.2    2705   438.6    2855   450.7    2995   438.6
    3508   443.3    4784     441    5860   446.9    5860     452    6915   460.1
    7068   453.9    7226   430.6    7880   441.5    9079     441    9122     430
    9198     430    9290     431    9330   413.7    9385     409    9468   442.1
    9540     443    9624   449.3    9867     431   10123     431   10187   446.5
   11149   452.1   12535   454.3   13698   440.7   14425   453.9   14706   475.7
#Mann= 10 ,-1,0
    1000    .075       0    3508    .045       0    4784     .14       0
    5860    .045       0    9122     .03       0    9198    .045       0
    9290     .05       0    9468     .14       0    9540    .035       0
   10123     .07       0
#XS Ineff= 4 ,-1
    1000    7530     460    7530    9290     431    9468   10187   442.1
   10187   14706     460
Permanent Ineff=
       F       F       F       F
Bank Sta=9290,9468
XS Rating Curve= 0 ,0
Exp/Cntr=0.3,0.1

Type RM Length L Ch R = 1 ,89708   ,799,981,999
BEGIN DESCRIPTION:
This cross section corresponds to cross section 89694 of the non-georeferenced CDC model which was the source of this model.
---------------------------------------------------------------------
CDC CAR040507-1 Western Extrusions
Cross-section 89694-91530
Located in LOB within ineffective flow area.
---------------------------------------------------------------------
END DESCRIPTION:
XS GIS Cut Line= 5
2454416.018037597036265.561082632446415.268947247034636.62405179
2445895.703057267034393.601243882444214.567311917034485.10959105
2440505.224665027034647.44227163
#Sta/Elev= 30
    1000   452.8    1195   444.2    2352   445.4    2393   437.2    3835   441.5
    3876   433.1    3915     443    4036     444    5863   435.6    6433   438.2
    6609     452    6624   460.1    7328   460.1    7579   440.3    8136   432.6
    9390   434.1    9402   434.1    9471     408    9579   440.5    9592   440.9
    9747   445.5    9854     430   10169     430   10369   445.2   12326   447.7
   12953   438.3   13859     451   14485   442.9   14944   473.7   15135   474.9
#Mann= 8 ,-1,0
    1000     .05       0    5863     .14       0    6609    .045       0
    9390     .14       0    9402     .05       0    9579     .14       0
    9592     .05       0   10369     .07       0
#XS Ineff= 4 ,-1
    1000    7700     460    7700    9402   434.1    9579   10369   440.5
   10369   15135     460
Permanent Ineff=
       F       F       F       F
Bank Sta=9402,9579
XS Rating Curve= 0 ,0
Exp/Cntr=0.3,0.1

Type RM Length L Ch R = 1 ,88727   ,205,204,203
BEGIN DESCRIPTION:
This cross section corresponds to cross section 88712 of the non-georeferenced CDC model which was the source of this model.
Includes CDC Elm Fork Water Treatment Plant Improvements project (CDC #: CAR 041718-01) from Station 93141 to 88712 (in LOB).
END DESCRIPTION:
XS GIS Cut Line= 5
2454761.838868267035572.279004632447177.857973257033966.21692805
2446440.408988837033572.352230222443455.711218097033782.00502613
 2439876.38143457033996.23688114
#Sta/Elev= 30
    1000     452 1197.54     444    3820   434.6    3894   447.9  3992.5   447.3
    4071   434.5  4185.7     443 4500.86     443    4726   440.1    5804     441
    7924   432.5    8299   438.6    9123   437.3    9160   433.9    9200   412.1
    9250   406.9    9265   417.9    9386   442.3    9420   447.2   10000     451
   10000   442.8   11029   438.5   11376   447.9 12991.8     444 13155.5     462
 13393.5     440 13580.5     440 14141.1     450   15796     450   16166     466
#Mann= 12 ,-1,0
    1000     .08       0    3820     .08       0  4185.7     .02       0
 4500.86     .08       0    4726     .05       0    5804     .14       0
    7924     .07       0    8299     .05       0    9123     .12       0
    9160     .05       0    9386     .12       0    9420     .07       0
#XS Ineff= 4 ,-1
    1000    7800     450    7800    9160   433.9    9386   11077   442.3
   11077   16166     450
Permanent Ineff=
       F       F       F       F
Bank Sta=9160,9386
XS Rating Curve= 0 ,0
Exp/Cntr=0.3,0.1

Type RM Length L Ch R = 1 ,88523   ,524,514,513
BEGIN DESCRIPTION:
This cross section corresponds to cross section 88468 of the non-georeferenced CDC model which was the source of this model.
END DESCRIPTION:
XS GIS Cut Line= 6
2455165.712732437034857.16101231 2447326.1893695 7033783.3226088
2447001.097828097033620.349181472446796.72586152 7033543.5494663
2446559.522923837033366.655791222439880.406032747033799.01713121
#Sta/Elev= 30
    1000  451.43 1430.51  442.56 2896.97     442  3262.1     434  3442.8     445
    4303   448.9 4536.31     440  4761.2     435 4798.89  442.54 4865.54  433.91
 4875.44     432  4876.3     440 8026.34   440.5 8264.74     434 8705.74   433.5
 9226.49     436 9299.29   434.5    9409  407.04 9557.74     444 9750.17     445
 9899.17     45210017.17     44210800.17   437.511158.17   438.511945.17     448
12501.17     44212672.17     45112937.17   439.513051.17     44716484.09     455
#Mann= 15 ,-1,0
    1000     .08       0 2896.97     .05       0 4536.31     .02       0
  4761.2     .02       0 4798.89     .02       0 4865.54     .05       0
 8026.34     .14       0 8264.74     .07       0 8705.74    .045       0
 9226.49     .12       0 9299.29     .05       0 9557.74     .12       0
 9750.17    .065       010800.17     .14       011158.17     .07       0
#XS Ineff= 2 , 0
       0 4770.19     460   11470       0     460
Permanent Ineff=
       F       F
Bank Sta=9299.29,9557.74
XS Rating Curve= 0 ,0
Exp/Cntr=0.3,0.1

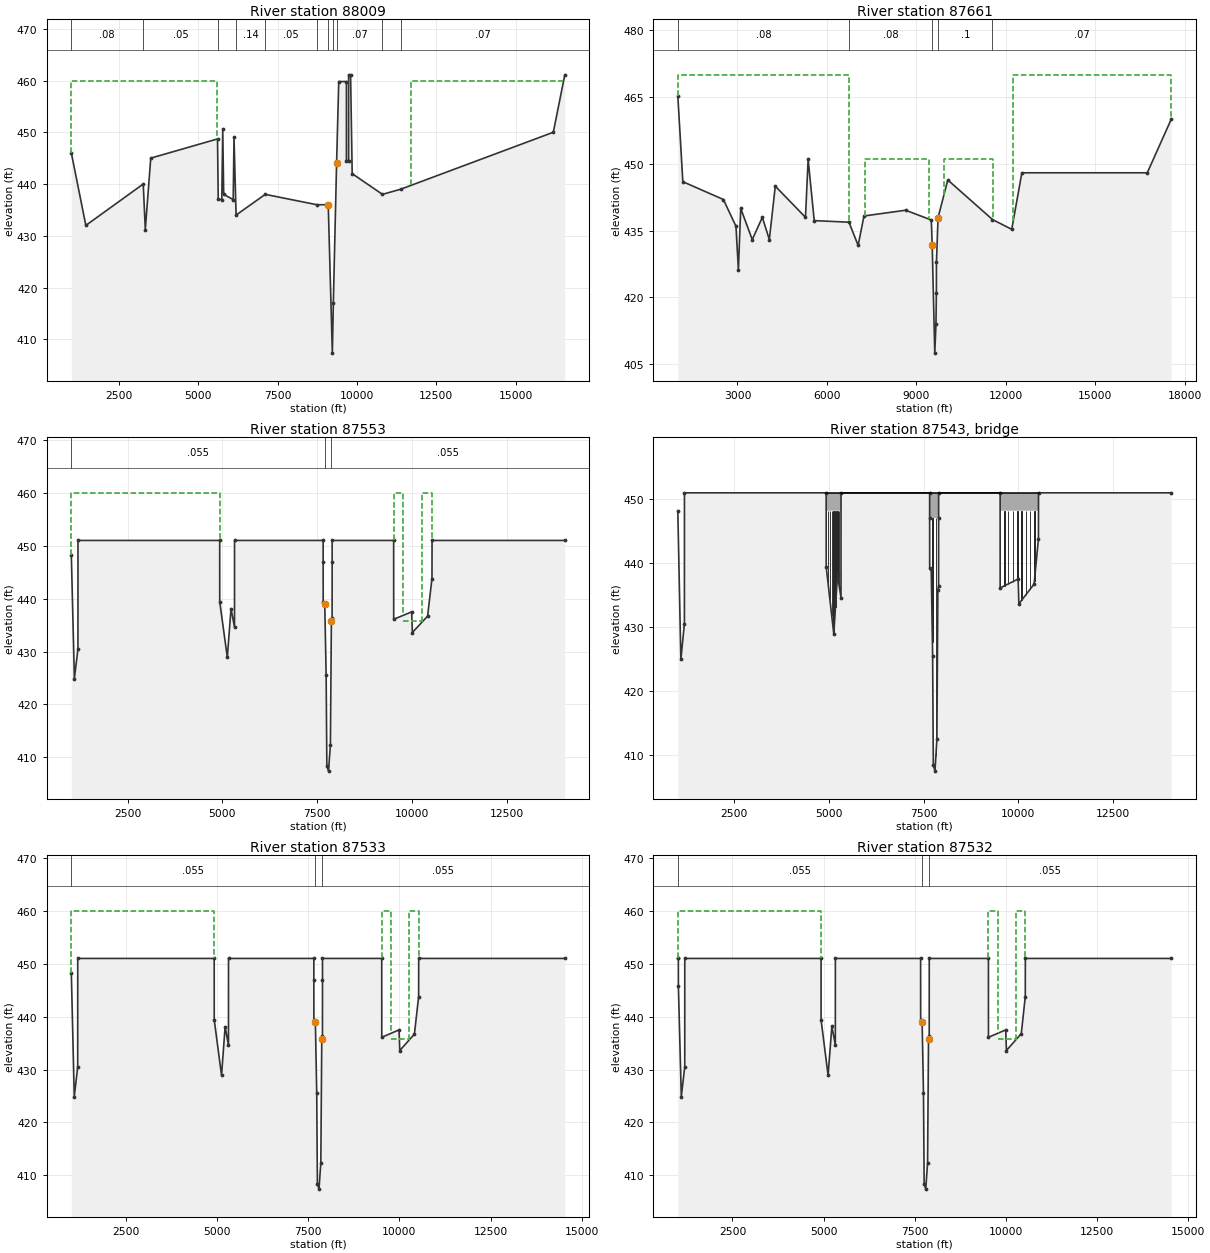
Type RM Length L Ch R = 1 ,88009   ,407,348,286
BEGIN DESCRIPTION:
This cross section corresponds to cross section 87965 of the non-georeferenced CDC model which was the source of this model.
END DESCRIPTION:
XS GIS Cut Line= 6
  2455333.4548517033993.49607296  2447680.3559847033383.32242455
2447194.283465337033179.911742142446917.856196677033024.98915172
2442202.486690437033316.299592722439902.766224277033447.38660088
#Sta/Elev= 30
    1000     446 1457.52     432 3266.29     440    3331   431.2 3502.81     445
  5607.2  448.71  5629.3  437.01  5741.6     437  5771.7  450.58  5801.8     438
  6101.7  436.99  6126.7     449 6192.09     434 7111.79     438 8736.46     436
 9096.46     436 9225.91  407.32 9257.76   417.1 9359.66     444 9427.92   459.8
 9669.67   459.8 9669.67   444.5 9738.86   444.5 9738.86   461.1 9800.81   461.1
 9851.41     44210805.41     43811383.01     43916189.79     450   16549     461
#Mann= 11 ,-1,0
    1000     .08       0 3266.29     .05       0  5607.2     .08       0
 6192.09     .14       0 7111.79     .05       0 8736.46     .12       0
 9096.46     .05       0 9257.76     .12       0 9359.66     .07       0
10805.41     .14       011383.01     .07       0
#XS Ineff= 2 , 0
       0    5596     460   11700       0     460
Permanent Ineff=
       F       F
Bank Sta=9096.46,9359.66
XS Rating Curve= 0 ,0
Exp/Cntr=0.3,0.1

Type RM Length L Ch R = 1 ,87661   ,108,108,108
BEGIN DESCRIPTION:
This cross section corresponds to cross section 87645 of the non-georeferenced CDC model which was the source of this model.
Luna Road Extension USACE Permit Number 199300443
Cross-section 87645 - 90532. Located in LOB.
-------------------------------------------
CDC CAR171221-01 Valwood Crossing
LOB between cross-sections 87541 - 88712.
This project supercedes previous two CDC projects listed below.
CDC PROJECTS: CAR032511-1 AND CAR032511-2 PROPOSED LUNA ROAD LP and #2 LP
--------------------------
END DESCRIPTION:
XS GIS Cut Line= 6
2455887.09514791 7033701.99403132455520.128034097033523.18992697
  2454945.8729497033352.136135222448091.474912437032838.97213531
2439726.696366437033333.714256052439450.78484476 7033400.9532948
#Sta/Elev= 30
    1000  465.29 1168.59     446 2528.56     442 2949.73     436 3031.52  426.22
 3109.47     440 3496.07     433  3834.8     438  4069.4     433  4268.4     445
 5281.31     438  5370.2     451 5575.21  437.26    6740   436.9    7047   431.7
    7243   438.3 8639.04  439.59    9501   437.4    9531   431.7    9617   407.5
    9657     414    9671   421.1    9673   427.9    9727   437.910053.13  446.39
11552.79   437.5   12198   435.312537.56     448 16743.4     448 17544.8     460
#Mann= 5 ,-1,0
    1000     .08       0    6740     .08       0    9531     .05       0
    9727      .1       011552.79     .07       0
#XS Ineff= 4 ,-1
    1000 6740.01     470    7280    9420     451    9920   11560     451
 12249.9 17544.8     470
Permanent Ineff=
       F       F       F       F
Bank Sta=9531,9727
XS Rating Curve= 0 ,0
Exp/Cntr=0.3,0.1

Type RM Length L Ch R = 1 ,87553   ,20,20,20
BEGIN DESCRIPTION:
This cross section corresponds to cross section 87541 of the non-georeferenced CDC model which was the source of this model.
---------------------------------------------------------------------
CDC PROJECTS: CAR032511-1 AND CAR032511-2 PROPOSED LUNA ROAD LP and #2 LP
CROSS-SECTION 87541 - 89694
---------------------------------------------------------------------
END DESCRIPTION:
XS GIS Cut Line= 6
2454102.120371437033203.139057892451323.501912927032973.65756147
2449224.330586347032814.517131722447823.491196427032749.33812821
 2446156.59164317032832.145377292441112.34216543 7033123.6423869
#Sta/Elev= 30
  1015.6   448.2    1096   424.9    1190   430.5    1191     451    4930     451
    4931   439.4    5131   428.9    5229  438.12    5321   434.6    5322     451
    7660     451    7660     447    7661   439.3    7702     439    7739   425.5
    7757   408.4    7801   407.4    7851   412.4    7877   435.8    7896   436.4
    7897     447    7897     451    9520     451    9521   436.1    9995   437.5
   10014   433.6 10415.5   436.7   10531   443.8   10533     451   14033     451
#Mann= 3 ,0,0
  1015.6    .055       0    7702     .05       0    7877    .055       0
#XS Ineff= 6 ,-1
    1000    4930     460    4930    7702     439    7877    9520   435.8
    9520    9778     460    9778   10268   435.8   10268   10533     460
Permanent Ineff=
       F       F       F       F       F       F
Bank Sta=7702,7877
XS Rating Curve= 0 ,0
Exp/Cntr=0.5,0.3

Type RM Length L Ch R = 3 ,87543   ,,,
BEGIN DESCRIPTION:
Southern Pacific Railroad
END DESCRIPTION:
Node Name=SP Railroad
Bridge Culvert--1,0,-1,-1, 0
Deck Dist Width WeirC Skew NumUp NumDn MinLoCord MaxHiCord MaxSubmerge Is_Ogee
1,18,2.6,0, 46, 46, , , 0.95, 0, ,,,
    4930    4930    4974    4984    5023    5033    5072    5082    5121    5131
    5170    5180    5219    5229    5268    5278    5322    5322    7660    7660
    7729    7737    7820    7828    7897    7897    9520    9520  9624.5  9641.5
  9737.5  9754.5  9850.5  9867.5  9963.5  9980.5 10076.5 10093.5 10189.5 10206.5
 10302.5 10319.5 10415.5 10432.5   10533   10533
     451     451     451     451     451     451     451     451     451     451
     451     451     451     451     451     451     451     451     451     451
     451     451     451     451     451     451     451     451     451     451
     451     451     451     451     451     451     451     451     451     451
     451     451     451     451     451     451
     451   448.2   448.2   448.2   448.2   448.2   448.2   448.2   448.2   448.2
   448.2   448.2   448.2   448.2   448.2   448.2   448.2     451     451     447
     447     447     447     447     447     451     451   448.2   448.2   448.2
   448.2   448.2   448.2   448.2   448.2   448.2   448.2   448.2   448.2   448.2
   448.2   448.2   448.2   448.2   448.2     451
    4930    4930    4974    4984    5023    5033    5072    5082    5121    5131
    5170    5180    5219    5229    5268    5278    5322    5322    7660    7660
    7729    7737    7820    7828    7897    7897    9520    9520  9624.5  9641.5
  9737.5  9754.5  9850.5  9867.5  9963.5  9980.5 10076.5 10093.5 10189.5 10206.5
 10302.5 10319.5 10415.5 10432.5   10533   10533
     451     451     451     451     451     451     451     451     451     451
     451     451     451     451     451     451     451     451     451     451
     451     451     451     451     451     451     451     451     451     451
     451     451     451     451     451     451     451     451     451     451
     451     451     451     451     451     451
     451   448.2   448.2   448.2   448.2   448.2   448.2   448.2   448.2   448.2
   448.2   448.2   448.2   448.2   448.2   448.2   448.2     451     451     447
     447     447     447     447     447     451     451   448.2   448.2   448.2
   448.2   448.2   448.2   448.2   448.2   448.2   448.2   448.2   448.2   448.2
   448.2   448.2   448.2   448.2   448.2     451
Pier Skew, UpSta & Num, DnSta & Num=  ,4979, 2 ,4979, 2 , 0 , 0 , 0 ,,
      10      10
     420     450
      10      10
     420     450
Pier Skew, UpSta & Num, DnSta & Num=  ,5028, 2 ,5028, 2 , 0 , 0 , 0 ,,
      10      10
     420     450
      10      10
     420     450
Pier Skew, UpSta & Num, DnSta & Num=  ,5077, 2 ,5077, 2 , 0 , 0 , 0 ,,
      10      10
     420     450
      10      10
     420     450
Pier Skew, UpSta & Num, DnSta & Num=  ,5126, 2 ,5126, 2 , 0 , 0 , 0 ,,
      10      10
     420     450
      10      10
     420     450
Pier Skew, UpSta & Num, DnSta & Num=  ,5175, 2 ,5175, 2 , 0 , 0 , 0 ,,
      10      10
     420     450
      10      10
     420     450
Pier Skew, UpSta & Num, DnSta & Num=  ,5224, 2 ,5224, 2 , 0 , 0 , 0 ,,
      10      10
     420     450
      10      10
     420     450
Pier Skew, UpSta & Num, DnSta & Num=  ,5273, 2 ,5273, 2 , 0 , 0 , 0 ,,
      10      10
     420     450
      10      10
     420     450
Pier Skew, UpSta & Num, DnSta & Num=  ,7733, 2 ,7733, 2 , 0 , 0 , 0 ,,
       8       8
     420     450
       8       8
     420     450
Pier Skew, UpSta & Num, DnSta & Num=  ,7824, 2 ,7824, 2 , 0 , 0 , 0 ,,
       8       8
     420     450
       8       8
     420     450
Pier Skew, UpSta & Num, DnSta & Num=  ,9633, 2 ,9633, 2 , 0 , 0 , 0 ,,
      17      17
     420     450
      17      17
     420     450
Pier Skew, UpSta & Num, DnSta & Num=  ,9729, 2 ,9729, 2 , 0 , 0 , 0 ,,
      17      17
     420     450
      17      17
     420     450
Pier Skew, UpSta & Num, DnSta & Num=  ,9859, 2 ,9859, 2 , 0 , 0 , 0 ,,
      17      17
     420     450
      17      17
     420     450
Pier Skew, UpSta & Num, DnSta & Num=  ,9972, 2 ,9972, 2 , 0 , 0 , 0 ,,
      17      17
     420     450
      17      17
     420     450
Pier Skew, UpSta & Num, DnSta & Num=  ,10085, 2 ,10085, 2 , 0 , 0 , 0 ,,
      17      17
     420     450
      17      17
     420     450
Pier Skew, UpSta & Num, DnSta & Num=  ,10198, 2 ,10198, 2 , 0 , 0 , 0 ,,
      17      17
     420     450
      17      17
     420     450
Pier Skew, UpSta & Num, DnSta & Num=  ,10311, 2 ,10311, 2 , 0 , 0 , 0 ,,
      17      17
     420     450
      17      17
     420     450
Pier Skew, UpSta & Num, DnSta & Num=  ,10424, 2 ,10424, 2 , 0 , 0 , 0 ,,
      17      17
     420     450
      17      17
     420     450
BR Coef= 1 , 0 , 0 ,1.05, 0 ,,,0.8,-1,0.5,1,
WSPro=,,,, 1 ,,,, 0 ,,,, 0 ,,,,-1 ,-1 ,-1 , 0 , 0 , 0 , 0 , 0
BC Design=,, 0 ,, 0 ,,,,,,
BC Use User HTab Curves=0
BC User HTab FreeFlow(D)= 0

Type RM Length L Ch R = 1 ,87533   ,1,1,1
BEGIN DESCRIPTION:
This cross section corresponds to cross section 87522 of the non-georeferenced CDC model which was the source of this model.
END DESCRIPTION:
XS GIS Cut Line= 6
2454120.089167517033189.222747132451256.687085937032950.51850013
2449170.19257125 7032792.92695182447774.69765884 7032732.9585678
2446114.146846097032813.27960138 2440630.59999147033120.73640699
#Sta/Elev= 30
  1015.6   448.2    1096   424.9    1190   430.5    1191     451    4930     451
    4931   439.4    5131   428.9    5229  438.12    5321   434.6    5322     451
    7660     451    7660     447    7661   439.3    7702     439    7739   425.5
    7757   408.4    7801   407.4    7851   412.4    7877   435.8    7896   436.4
    7897     447    7897     451    9520     451    9521   436.1    9995   437.5
   10014   433.6 10415.5   436.7   10531   443.8   10533     451   14533     451
#Mann= 3 ,0,0
  1015.6    .055       0    7702     .05       0    7877    .055       0
#XS Ineff= 6 ,-1
    1000    4930     460    4930    7702     439    7877    9520   435.8
    9520    9778     460    9778   10268   435.8   10268   10533     460
Permanent Ineff=
       F       F       F       F       F       F
Bank Sta=7702,7877
XS Rating Curve= 0 ,0
Exp/Cntr=0.5,0.3

Type RM Length L Ch R = 1 ,87532   ,120,93,70
BEGIN DESCRIPTION:
This cross section corresponds to cross section 87521 of the non-georeferenced CDC model which was the source of this model.
END DESCRIPTION:
XS GIS Cut Line= 6
2454132.295179847033189.360870212451253.417079337032949.31935555
2449167.344807927032791.790799222447772.13106292 7032732.0963648
2446111.913910937032812.286493142440627.212328417033119.31093543
#Sta/Elev= 30
    1000     451    1015     451    1016   445.7    1096   424.9    1190   430.5
    1191     451    4930     451    4930   439.4    5122   428.9    5226   438.2
    5321   434.6    5322     451    7660     451    7661   439.3    7702     439
    7739   425.5    7757   408.4    7801   407.4    7851   412.4    7877   435.8
    7896   436.4    7897     451    9520     451    9521   436.1    9995   437.5
   10014   433.6   10422   436.8   10531   443.8   10533     451   14533     451
#Mann= 3 ,0,0
    1000    .055       0    7702     .05       0    7877    .055       0
#XS Ineff= 6 ,-1
    1000    4930     460    4930    7702     439    7877    9520   435.8
    9520    9778     460    9778   10268   435.8   10268   10533     460
Permanent Ineff=
       F       F       F       F       F       F
Bank Sta=7702,7877
XS Rating Curve= 0 ,0
Exp/Cntr=0.5,0.3