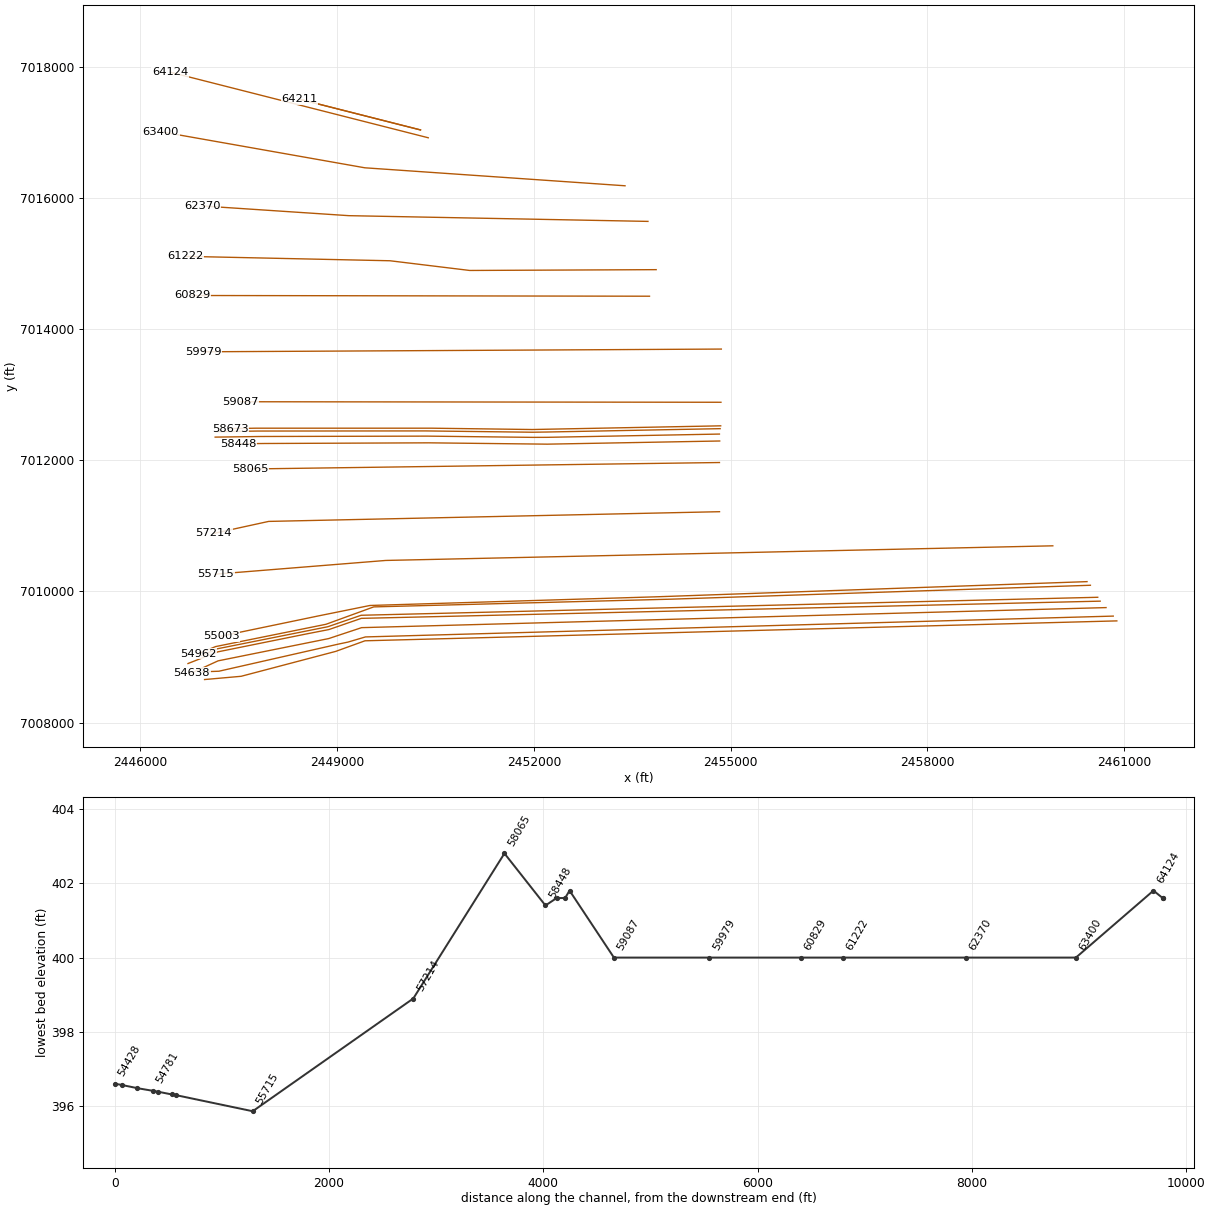
HEC-RAS study CDC_Consolidated_Model.prj: Upper Trinity CDC Consolidated Model

--- CDC_Consolidated_Model.g01 (geometry) --- (continued)

Type RM Length L Ch R = 3 ,64253   ,,,
BEGIN DESCRIPTION:
IH 635/LBJ Freeway East Bound
END DESCRIPTION:
Node Name=IH 635 EB
Bridge Culvert--1,0,-1,-1, 0
Deck Dist Width WeirC Skew NumUp NumDn MinLoCord MaxHiCord MaxSubmerge Is_Ogee
2,82,2.6,0, 45, 45, , , 0.95, 0, ,,,
    3740    3817    3823    3907    3913    3997    4003    4122    4128    4202
    4208    4282    4288    4362    4368    4368    4442    4448    4522    4528
    4602    4608    4682    4688    4762    4768    4842    4848  4893.5  4896.5
  4984.5  4987.5  5109.5  5112.5  5201.5  5204.5    5283    5289    5387    5393
    5477    5483    5568    5574    5639
   450.5   450.5   450.5   450.5   450.5   450.5   450.5   450.5   450.5   450.5
   450.5   450.5   450.5   450.5   450.5   450.5   450.5   450.5   450.5   450.5
   450.5   450.5   450.5   450.5   450.5   450.5   450.5   450.5   450.5   450.5
   450.5   450.5   450.5   450.5   450.5   450.5   450.5   450.5   450.5   450.5
   450.5   450.5   450.5   450.5   450.5
   444.5   444.5   444.5   444.5   444.5   444.5   444.5   444.5   444.5   444.5
   444.5   444.5   444.5   444.5   444.5   444.5   444.5   444.5   444.5   444.5
   444.5   444.5   444.5   444.5   444.5   444.5   444.5   444.5   444.5   444.5
   444.5   444.5   444.5   444.5   444.5   444.5   444.5   444.5   444.5   444.5
   444.5   444.5   444.5   444.5   444.5
    3740    3817    3823    3907    3913    3997    4003    4122    4128    4202
    4208    4282    4288    4362    4368    4368    4442    4448    4522    4528
    4602    4608    4682    4688    4762    4768    4842    4848  4893.5  4896.5
  4984.5  4987.5  5109.5  5112.5  5201.5  5204.5    5283    5289    5387    5393
    5477    5483    5568    5574    5639
   450.5   450.5   450.5   450.5   450.5   450.5   450.5   450.5   450.5   450.5
   450.5   450.5   450.5   450.5   450.5   450.5   450.5   450.5   450.5   450.5
   450.5   450.5   450.5   450.5   450.5   450.5   450.5   450.5   450.5   450.5
   450.5   450.5   450.5   450.5   450.5   450.5   450.5   450.5   450.5   450.5
   450.5   450.5   450.5   450.5   450.5
   444.5   444.5   444.5   444.5   444.5   444.5   444.5   444.5   444.5   444.5
   444.5   444.5   444.5   444.5   444.5   444.5   444.5   444.5   444.5   444.5
   444.5   444.5   444.5   444.5   444.5   444.5   444.5   444.5   444.5   444.5
   444.5   444.5   444.5   444.5   444.5   444.5   444.5   444.5   444.5   444.5
   444.5   444.5   444.5   444.5   444.5
Pier Skew, UpSta & Num, DnSta & Num=  ,3820, 2 ,3820, 2 , 0 , 0 , 0 ,,
       6       6
     415     450
       6       6
     415     450
Pier Skew, UpSta & Num, DnSta & Num=  ,3910, 2 ,3910, 2 , 0 , 0 , 0 ,,
       6       6
     415     450
       6       6
     415     450
Pier Skew, UpSta & Num, DnSta & Num=  ,4000, 2 ,4000, 2 , 0 , 0 , 0 ,,
       6       6
     415     450
       6       6
     415     450
Pier Skew, UpSta & Num, DnSta & Num=  ,4125, 2 ,4125, 2 , 0 , 0 , 0 ,,
       6       6
     415     450
       6       6
     415     450
Pier Skew, UpSta & Num, DnSta & Num=  ,4205, 2 ,4205, 2 , 0 , 0 , 0 ,,
       6       6
     415     450
       6       6
     415     450
Pier Skew, UpSta & Num, DnSta & Num=  ,4285, 2 ,4285, 2 , 0 , 0 , 0 ,,
       6       6
     415     450
       6       6
     415     450
Pier Skew, UpSta & Num, DnSta & Num=  ,4365, 2 ,4365, 2 , 0 , 0 , 0 ,,
       6       6
     415     450
       6       6
     415     450
Pier Skew, UpSta & Num, DnSta & Num=  ,4445, 2 ,4445, 2 , 0 , 0 , 0 ,,
       6       6
     415     450
       6       6
     415     450
Pier Skew, UpSta & Num, DnSta & Num=  ,4525, 2 ,4525, 2 , 0 , 0 , 0 ,,
       6       6
     415     450
       6       6
     415     450
Pier Skew, UpSta & Num, DnSta & Num=  ,4605, 2 ,4605, 2 , 0 , 0 , 0 ,,
       6       6
     415     450
       6       6
     415     450
Pier Skew, UpSta & Num, DnSta & Num=  ,4685, 2 ,4685, 2 , 0 , 0 , 0 ,,
       6       6
     415     450
       6       6
     415     450
Pier Skew, UpSta & Num, DnSta & Num=  ,4765, 2 ,4765, 2 , 0 , 0 , 0 ,,
       6       6
     415     450
       6       6
     415     450
Pier Skew, UpSta & Num, DnSta & Num=  ,4845, 2 ,4845, 2 , 0 , 0 , 0 ,,
       6       6
     415     450
       6       6
     415     450
Pier Skew, UpSta & Num, DnSta & Num=  ,4895, 2 ,4895, 2 , 0 , 0 , 0 ,,
       3       3
     415     450
       3       3
     415     450
Pier Skew, UpSta & Num, DnSta & Num=  ,4986, 2 ,4986, 2 , 0 , 0 , 0 ,,
       3       3
     415     450
       3       3
     415     450
Pier Skew, UpSta & Num, DnSta & Num=  ,5111, 2 ,5111, 2 , 0 , 0 , 0 ,,
       3       3
     415     450
       3       3
     415     450
Pier Skew, UpSta & Num, DnSta & Num=  ,5203, 2 ,5203, 2 , 0 , 0 , 0 ,,
       3       3
     415     450
       3       3
     415     450
Pier Skew, UpSta & Num, DnSta & Num=  ,5285, 2 ,5285, 2 , 0 , 0 , 0 ,,
       6       6
     415     450
       6       6
     415     450
Pier Skew, UpSta & Num, DnSta & Num=  ,5390, 2 ,5390, 2 , 0 , 0 , 0 ,,
       6       6
     415     450
       6       6
     415     450
Pier Skew, UpSta & Num, DnSta & Num=  ,5480, 2 ,5480, 2 , 0 , 0 , 0 ,,
       6       6
     415     450
       6       6
     415     450
Pier Skew, UpSta & Num, DnSta & Num=  ,5571, 2 ,5571, 2 , 0 , 0 , 0 ,,
       6       6
     415     450
       6       6
     415     450
BR Coef= 1 , 0 , 0 ,1.05, 0 ,,,0.8,-1,0.5,1,
WSPro=,,,, 1 ,,,, 0 ,,,, 0 ,,,,-1 ,-1 ,-1 , 0 , 0 , 0 , 0 , 0
BC Design=,, 0 ,, 0 ,,,,,,
BC HTab HWMax=450.5
BC Use User HTab Curves=0
BC User HTab FreeFlow(D)= 0

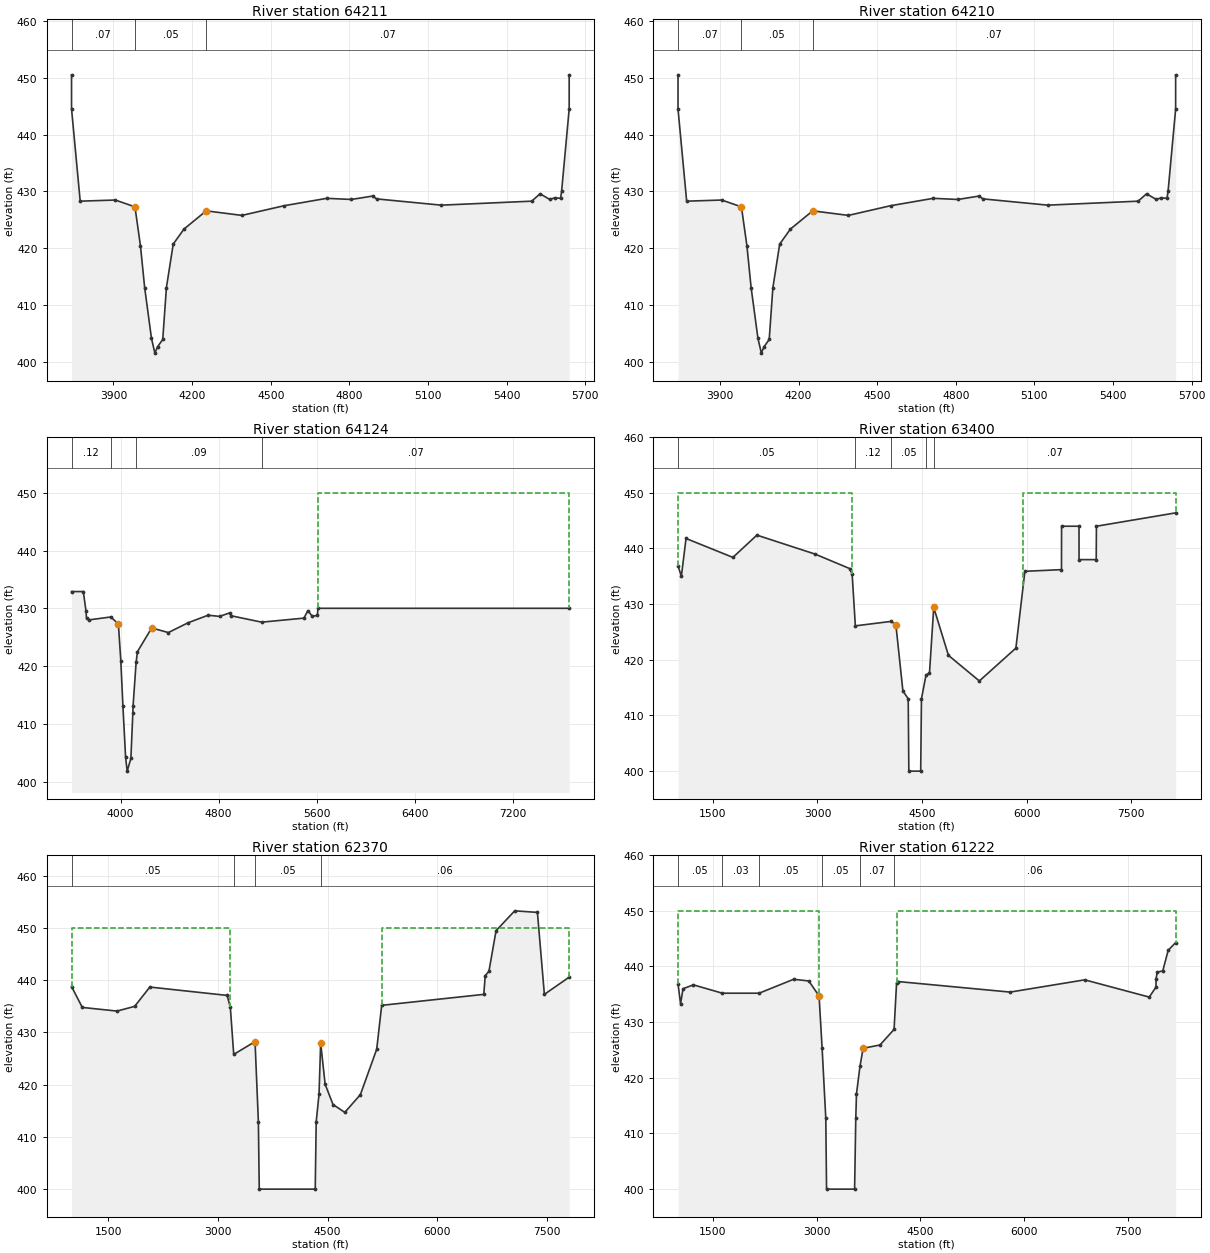
Type RM Length L Ch R = 1 ,64211   ,1,1,1
BEGIN DESCRIPTION:
This cross section corresponds to cross section 64196 of the non-georeferenced CDC model which was the source of this model.
END DESCRIPTION:
XS GIS Cut Line= 2
2450271.562415757017045.48863047 2448431.02803917017513.07102863
#Sta/Elev= 30
    3740   450.5    3740   444.5    3773   428.3    3907   428.5    3982   427.3
    4003  420.44    4019   413.1    4045   404.2    4058   401.6    4068   402.7
    4088     404    4102   413.1    4128  420.76    4169   423.4    4254   426.6
    4390   425.8    4551   427.5    4714   428.8    4808   428.6    4889   429.2
    4904   428.7    5151   427.6    5496   428.3    5528   429.6    5565   428.6
    5584   428.9    5606   428.8    5610     430    5639   444.5    5639   450.5
#Mann= 3 ,0,0
    3740     .07       0    3982     .05       0    4254     .07       0
#XS Ineff= 2 , 0
       0    3982   427.3    4254       0   426.6
Permanent Ineff=
       F       F
Bank Sta=3982,4254
XS Rating Curve= 0 ,0
Exp/Cntr=0.5,0.3

Type RM Length L Ch R = 1 ,64210   ,86,86,86
BEGIN DESCRIPTION:
This cross section corresponds to cross section 64195 of the non-georeferenced CDC model which was the source of this model.
One foot downstream of IH 635.  Duplication of following bridge cross-section (64196) without bridge piers.
Channel data from COD Elm Fork channel survey.
END DESCRIPTION:
XS GIS Cut Line= 2
2450271.582756947017044.505036642448431.050348767017512.09629305
#Sta/Elev= 30
    3740   450.5    3740   444.5    3773   428.3    3907   428.5    3982   427.3
    4003  420.44    4019   413.1    4045   404.2    4058   401.6    4068   402.7
    4088     404    4102   413.1    4128  420.76    4169   423.4    4254   426.6
    4390   425.8    4551   427.5    4714   428.8    4808   428.6    4889   429.2
    4904   428.7    5151   427.6    5496   428.3    5528   429.6    5565   428.6
    5584   428.9    5606   428.8    5610     430    5639   444.5    5639   450.5
#Mann= 3 ,0,0
    3740     .07       0    3982     .05       0    4254     .07       0
#XS Ineff= 2 , 0
       0    3982   427.3    4254       0   426.6
Permanent Ineff=
       F       F
Bank Sta=3982,4254
XS Rating Curve= 0 ,0
Exp/Cntr=0.3,0.1

Type RM Length L Ch R = 1 ,64124   ,751,724,721
BEGIN DESCRIPTION:
This cross section corresponds to cross section 64104 of the non-georeferenced CDC model which was the source of this model.
Cross-section EF085.  92 feet downstream of I.H. 635.  Effective flow limit set at sta 3600 in LOB, at sta 5660 in ROB.  Royal Lane Reclamation in LOB and ROB.
Channel data from COD Elm Fork channel survey - cross-section EF#085 surveyed February 1994.
END DESCRIPTION:
XS GIS Cut Line= 3
2450389.696037777016925.415707892448393.332576427017433.48293322
2446455.115480987017926.75212034
#Sta/Elev= 30
    3600   432.9    3696   432.9    3718   429.5    3722   428.3    3745     428
    3920   428.5    3982   427.3    4002   420.9    4019   413.1    4041   404.2
    4054   401.8    4084     404    4100   411.8    4102   413.1    4127   420.7
    4138   422.5    4254   426.6    4390   425.8    4551   427.5    4714   428.8
    4808   428.6    4889   429.2    4904   428.7    5151   427.6    5496   428.3
    5528   429.6    5565   428.6    5606   428.8    5610     430    7660     430
#Mann= 4 ,-1,0
    3600     .12       0    3920     .05       0    4127     .09       0
    5151     .07       0
#XS Ineff= 3 ,-1
    3600    3982   427.3    4254    5610   426.6    5610    7660     450
Permanent Ineff=
       F       F       F
Bank Sta=3982,4254
XS Rating Curve= 0 ,0
Exp/Cntr=0.3,0.1

Type RM Length L Ch R = 1 ,63400   ,1000,1030,1100
BEGIN DESCRIPTION:
This cross section corresponds to cross section 63381 of the non-georeferenced CDC model which was the source of this model.
Cross-section EF084.  Effective flow limit set at sta 3497 in LOB, at sta 5949 in ROB.  Royal Lane Reclamation in LOB and ROB.
Channel data from Royal Lane Reclamation project plans.
END DESCRIPTION:
XS GIS Cut Line= 3
2453390.246795187016192.570060722449422.949939767016467.05901305
2446312.103471167017017.78232105
#Sta/Elev= 30
    1000   436.9    1048     435    1115   441.8    1787   438.4    2131   442.4
    2964     439    3460   436.4    3497   435.4    3543   426.1    4056   426.9
    4124   426.3    4225   414.4    4301     413    4310     400    4480     400
    4491     413    4557   417.3    4606   417.6    4667   429.4    4878   420.8
    5321   416.2    5845   422.1    5974   435.9    6499   436.2    6500     444
    6750     444    6751     438    6997     438    7000     444    8136   446.4
#Mann= 5 ,-1,0
    1000     .05       0    3543     .12       0    4056     .05       0
    4557     .12       0    4667     .07       0
#XS Ineff= 4 ,-1
    1000    3497     450    3497    4124   426.3    4667    5949   429.4
    5949    8136     450
Permanent Ineff=
       F       F       F       F
Bank Sta=4124,4667
XS Rating Curve= 0 ,0
Exp/Cntr=0.3,0.1

Type RM Length L Ch R = 1 ,62370   ,800,1148,700
BEGIN DESCRIPTION:
This cross section corresponds to cross section 62351 of the non-georeferenced CDC model which was the source of this model.
Cross-section EF083.  Effective flow limit set at sta 3170 in LOB, at sta 5238 in ROB.  Royal Lane Reclamation in LOB and ROB.
Channel data from Royal Lane Reclamation project plans.
LOMR#14-06-2597P & CDC# FB100113-1 Mercer Crossing
Cross-sections 67169 & 62351.  Fill was added in innefective flow area so no physical cross-section change.
END DESCRIPTION:
XS GIS Cut Line= 3
2453739.509876167015648.992079632449179.379888837015736.34918839
2446945.265590677015884.68288122
#Sta/Elev= 30
    1000   438.8    1147   434.8    1621   434.1    1862     435    2070   438.7
    3126   437.1    3170   434.8    3216   425.8    3501   428.2    3509   427.7
    3553   412.9    3565     400    4330     400    4343   412.9    4382   418.2
    4404     428    4465   420.1    4573   416.2    4734   414.7    4947   418.1
    5170   426.8    5238   435.2    6633   437.3    6653   440.9    6703   441.7
    6801   449.5    7056   453.3    7366     453    7461   437.3    7800   440.6
#Mann= 4 ,-1,0
    1000     .05       0    3216      .1       0    3501     .05       0
    4404     .06       0
#XS Ineff= 4 ,-1
    1000    3170     450    3170    3501   428.2    4404    5238     428
    5238    7800     450
Permanent Ineff=
       F       F       F       F
Bank Sta=3501,4404
XS Rating Curve= 0 ,0
Exp/Cntr=0.3,0.1

Type RM Length L Ch R = 1 ,61222   ,400,393,550
BEGIN DESCRIPTION:
This cross section corresponds to cross section 61203 of the non-georeferenced CDC model which was the source of this model.
Cross-section EF082.  Effective flow limit set at sta 3037 in LOB, at sta 4156 in ROB.  Royal Lane Reclamation in LOB and ROB.
Channel data from Royal Lane Reclamation project plans.
END DESCRIPTION:
XS GIS Cut Line= 4
2453864.556870167014912.291125222451020.959867097014900.08609714
2449806.514133247015048.058242132446688.293335597015115.47936714
#Sta/Elev= 30
    1000   436.9    1037   433.3    1072     436    1222   436.7    1640   435.2
    2171   435.2    2669   437.7    2889   437.4    3037   434.7    3081   425.3
    3134   412.7    3145     400    3550     400    3567   412.7    3577   417.1
    3628   422.1    3673   425.3    3917   425.9    4120   428.7    4156     437
    4173   437.3    5796   435.4    6873   437.6    7805   434.5    7902   436.3
    7903   437.8    7921     439    8000   439.2    8078   442.9    8186   444.3
#Mann= 6 ,-1,0
    1000     .05       0    1640     .03       0    2171     .05       0
    3081     .05       0    3628     .07       0    4120     .06       0
#XS Ineff= 3 ,-1
    1000    3037     450    3673    4156   425.3    4156    8186     450
Permanent Ineff=
       F       F       F
Bank Sta=3037,3673
XS Rating Curve= 0 ,0
Exp/Cntr=0.3,0.1

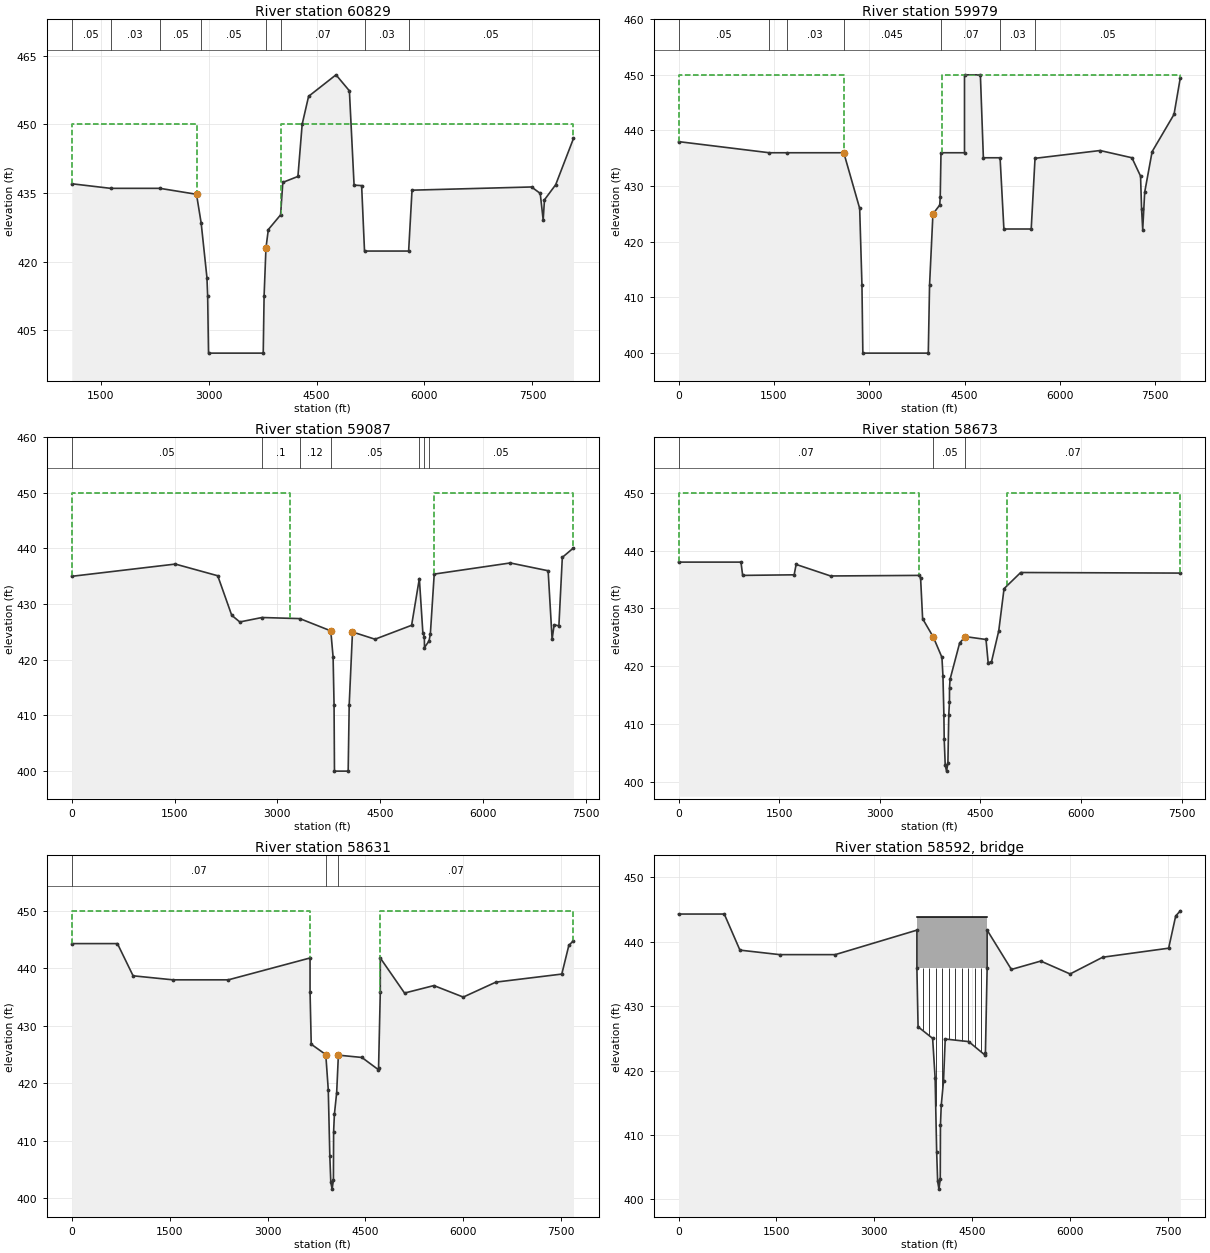
Type RM Length L Ch R = 1 ,60829   ,830,850,850
BEGIN DESCRIPTION:
This cross section corresponds to cross section 60810 of the non-georeferenced CDC model which was the source of this model.
Cross-section EF081.  Effective flow limit set at sta 2833 in LOB, at sta 4001 in ROB.  Royal Lane Reclamation in LOB and ROB.
Channel data from Royal Lane Reclamation project plans.
END DESCRIPTION:
XS GIS Cut Line= 2
 2453763.08200757014506.986161542446793.090698187014517.86606105
#Sta/Elev= 30
    1100     437    1640     436    2325     436    2833   434.7    2898   428.4
    2978   416.5    2988   412.5    3000     400    3760     400    3772   412.5
    3798     423    3831     427    4001   430.2    4032   437.3    4242   438.6
    4301     450    4390   456.1    4771   460.8    4957   457.3    5022   436.7
    5127   436.6    5167   422.3    5780   422.3    5827   435.6    7487   436.3
    7608   434.9    7649   429.1    7667   433.5    7823   436.8    8070   446.9
#Mann= 8 ,-1,0
    1100     .05       0    1640     .03       0    2325     .05       0
    2898     .05       0    3798     .08       0    4001     .07       0
    5167     .03       0    5780     .05       0
#XS Ineff= 3 ,-1
    1100    2833     450    3798    4001     423    4001    8070     450
Permanent Ineff=
       F       F       F
Bank Sta=2833,3798
XS Rating Curve= 0 ,0
Exp/Cntr=0.3,0.1

Type RM Length L Ch R = 1 ,59979   ,805,892,784
BEGIN DESCRIPTION:
This cross section corresponds to cross section 59960 of the non-georeferenced CDC model which was the source of this model.
Cross-section EF080.  Effective flow limit set at sta 2600 in LOB, at sta 4150 in ROB.  Royal Lane Reclamation in LOB and ROB.
Channel data from Royal Lane Reclamation project plans.
END DESCRIPTION:
XS GIS Cut Line= 3
2454858.365645387013700.116963382454028.377080597013695.76009372
2446961.474547747013658.66371122
#Sta/Elev= 30
       0     438    1428     436    1700     436    2600     436    2850     426
    2886   412.2    2900     400    3930     400    3950   412.2    4003     425
    4110   426.6    4118     428    4130     436    4500     436    4500     450
    4750     450    4797   435.1    5060   435.1    5120   422.3    5550   422.3
    5610     435    6634   436.4    7135   435.1    7271   431.8    7287   425.9
    7305   422.2    7336   428.9    7453   436.2    7798   442.9    7897   449.5
#Mann= 7 ,-1,0
       0     .05       0    1428     .06       0    1700     .03       0
    2600    .045       0    4130     .07       0    5060     .03       0
    5610     .05       0
#XS Ineff= 3 ,-1
       0    2600     450    4003    4150     425    4150    7897     450
Permanent Ineff=
       F       F       F
Bank Sta=2600,4003
XS Rating Curve= 0 ,0
Exp/Cntr=0.3,0.1

Type RM Length L Ch R = 1 ,59087   ,414,414,414
BEGIN DESCRIPTION:
This cross section corresponds to cross section 59073 of the non-georeferenced CDC model which was the source of this model.
Cross-section EF079.  Effective flow limit set at sta 3180 in LOB, at sta 5291 in ROB.  Royal Lane Reclamation in LOB and ROB.  At Elm Fork/Farmers Branch confluence.
Channel data from Royal Lane Reclamation project plans.
END DESCRIPTION:
XS GIS Cut Line= 3
2454852.649579977012888.107581982454012.650077917012889.02220589
2447528.654187687012896.08223113
#Sta/Elev= 30
       0     435    1512   437.2    2131   435.1    2335     428    2453   426.8
    2777   427.6    3330   427.4    3781   425.2    3815   420.5    3829   411.9
    3835     400    4035     400    4050   411.9    4098     425    4427   423.7
    4961   426.2    5074   434.6    5125   424.9    5147   424.1    5149   422.2
    5216   423.4    5235   424.7    5291   435.4    6401   437.4    6954     436
    7012   423.7    7042   426.3    7111   426.1    7161   438.4    7324   440.1
#Mann= 7 ,-1,0
       0     .05       0    2777      .1       0    3330     .12       0
    3781     .05       0    5074     .07       0    5147     .02       0
    5216     .05       0
#XS Ineff= 4 ,-1
       0    3180     450    3180    3781   425.2    4098    5291     425
    5291    7324     450
Permanent Ineff=
       F       F       F       F
Bank Sta=3781,4098
XS Rating Curve= 0 ,0
Exp/Cntr=0.3,0.1

Type RM Length L Ch R = 1 ,58673   ,42,42,42
BEGIN DESCRIPTION:
This cross section corresponds to cross section 58654 of the non-georeferenced CDC model which was the source of this model.
Cross-section EF078.  43 feet upstream of Royal Lane.  Effective flow limit set at sta 3590 in LOB, at sta 4900 in ROB.  Royal Lane Reclamation in LOB and
ROB.Channel data from COD Elm Fork channel survey - cross-section EF#078 surveyed February 1994.
END DESCRIPTION:
XS GIS Cut Line= 6
2454848.755781297012528.446664872453998.919134267012511.78313097
2451975.095097937012472.100139472450436.093910847012492.41604371
2447764.428978597012492.416043712447369.497353767012485.82517764
#Sta/Elev= 30
       0     438     930     438     955   435.7    1723   435.8    1752   437.6
    2266   435.6    3590   435.7    3608   435.2    3638   428.2    3798     425
    3926   421.5    3941   418.3    3955   411.6    3960   407.3    3975   402.8
    3995   401.8    4015   403.2    4028   411.6    4038   413.7    4039   416.2
    4047   417.7    4190     424    4275   425.1    4583   424.6    4615   420.6
    4664   420.7    4773   426.1    4852   433.4    5100   436.2    7480   436.1
#Mann= 3 ,0,0
       0     .07       0    3798     .05       0    4275     .07       0
#XS Ineff= 4 ,-1
       0    3590     450    3590    3798     425    4275    4900   425.1
    4900    7480     450
Permanent Ineff=
       F       F       F       F
Bank Sta=3798,4275
XS Rating Curve= 0 ,0
Exp/Cntr=0.3,0.1

Type RM Length L Ch R = 1 ,58631   ,79,79,79
BEGIN DESCRIPTION:
This cross section corresponds to cross section 58612 of the non-georeferenced CDC model which was the source of this model.
END DESCRIPTION:
XS GIS Cut Line= 6
2454840.271420717012485.239766162452198.67831218 7012433.9302683
2451977.422849187012430.837426722450352.339813267012450.69893555
2447789.279650667012448.807535132447151.997460667012438.79607221
#Sta/Elev= 30
       0   444.3     700   444.3     940   438.7    1550     438    2400     438
  3651.8   441.8  3651.8   435.9    3670   426.8    3893     425    3931   418.9
    3955   407.3    3970   402.8    3990   401.6    4010   403.2    4013   411.6
    4025   414.6    4060   418.4    4086   424.9    4446   424.5    4696   422.4
    4702   422.7  4728.3  435.88  4728.3   441.8    5100   435.7    5550     437
    6000     435    6500   437.6    7510     439    7618     444    7689   444.8
#Mann= 3 ,0,0
       0     .07       0    3893     .05       0    4086     .07       0
#XS Ineff= 4 ,-1
       0    3651     450    3651    3893     425    4086    4728   424.9
    4728    7689     450
Permanent Ineff=
       F       F       F       F
Bank Sta=3893,4086
XS Rating Curve= 0 ,0
Exp/Cntr=0.5,0.3

Type RM Length L Ch R = 3 ,58592   ,,,
BEGIN DESCRIPTION:
Royal Lane
END DESCRIPTION:
Node Name=Royal Lane
Bridge Culvert--1,0,-1,-1, 0
Deck Dist Width WeirC Skew NumUp NumDn MinLoCord MaxHiCord MaxSubmerge Is_Ogee
1,77,2.6,0, 22, 22, , , 0.95, 0, ,,,
  3651.8  3738.5  3741.5  3838.5  3841.5  3938.5  3941.5  4038.5  4041.5  4138.5
  4141.5  4238.5  4241.5  4338.5  4341.5  4438.5  4441.5  4538.5  4541.5  4638.5
  4641.5  4728.3
   443.8   443.8   443.8   443.8   443.8   443.8   443.8   443.8   443.8   443.8
   443.8   443.8   443.8   443.8   443.8   443.8   443.8   443.8   443.8   443.8
   443.8   443.8
   435.9   435.9   435.9   435.9   435.9   435.9   435.9   435.9   435.9   435.9
   435.9   435.9   435.9   435.9   435.9   435.9   435.9   435.9   435.9   435.9
   435.9   435.9
  3651.8  3738.5  3741.5  3838.5  3841.5  3938.5  3941.5  4038.5  4041.5  4138.5
  4141.5  4238.5  4241.5  4338.5  4341.5  4438.5  4441.5  4538.5  4541.5  4638.5
  4641.5  4728.3
   443.8   443.8   443.8   443.8   443.8   443.8   443.8   443.8   443.8   443.8
   443.8   443.8   443.8   443.8   443.8   443.8   443.8   443.8   443.8   443.8
   443.8   443.8
   435.9   435.9   435.9   435.9   435.9   435.9   435.9   435.9   435.9   435.9
   435.9   435.9   435.9   435.9   435.9   435.9   435.9   435.9   435.9   435.9
   435.9   435.9
Pier Skew, UpSta & Num, DnSta & Num=  ,3740, 2 ,3740, 2 , 0 , 0 , 0 ,,
       3       3
     410     440
       3       3
     410     440
Pier Skew, UpSta & Num, DnSta & Num=  ,3840, 2 ,3840, 2 , 0 , 0 , 0 ,,
       3       3
     410     440
       3       3
     410     440
Pier Skew, UpSta & Num, DnSta & Num=  ,3940, 2 ,3940, 2 , 0 , 0 , 0 ,,
       3       3
     410     440
       3       3
     410     440
Pier Skew, UpSta & Num, DnSta & Num=  ,4040, 2 ,4040, 2 , 0 , 0 , 0 ,,
       3       3
     410     440
       3       3
     410     440
Pier Skew, UpSta & Num, DnSta & Num=  ,4140, 2 ,4140, 2 , 0 , 0 , 0 ,,
       3       3
     410     440
       3       3
     410     440
Pier Skew, UpSta & Num, DnSta & Num=  ,4240, 2 ,4240, 2 , 0 , 0 , 0 ,,
       3       3
     410     440
       3       3
     410     440
Pier Skew, UpSta & Num, DnSta & Num=  ,4340, 2 ,4340, 2 , 0 , 0 , 0 ,,
       3       3
     410     440
       3       3
     410     440
Pier Skew, UpSta & Num, DnSta & Num=  ,4440, 2 ,4440, 2 , 0 , 0 , 0 ,,
       3       3
     410     440
       3       3
     410     440
Pier Skew, UpSta & Num, DnSta & Num=  ,4540, 2 ,4540, 2 , 0 , 0 , 0 ,,
       3       3
     410     440
       3       3
     410     440
Pier Skew, UpSta & Num, DnSta & Num=  ,4640, 2 ,4640, 2 , 0 , 0 , 0 ,,
       3       3
     410     440
       3       3
     410     440
BR Coef= 1 , 0 , 0 ,1.05, 0 ,,,0.8,-1,0.5,1,
WSPro=,,,, 1 ,,,, 0 ,,,, 0 ,,,,-1 ,-1 ,-1 , 0 , 0 , 0 , 0 , 0
BR D #Sta/Elev= 88
     700   444.3     940   438.7    1550     438    1650     438    2050     438
    2150     438    2300     438    2400     438    3620   441.7    3640   441.8
  3651.8   441.8  3651.8   435.9    3670   426.8  3738.5  426.05  3741.5  426.02
    3743     426    3759   425.7    3789   425.4  3838.5  425.77  3841.5   425.8
    3842   425.8    3869   425.6    3893     425    3921   420.3    3931   418.9
  3938.5   415.6  3941.5  414.26    3943   413.6    3948   411.6    3955   407.3
    3970   402.8    3990   401.6    4010   403.2    4013   411.6    4025   414.6
    4031   415.7  4038.5   416.4  4041.5  416.68    4060   418.4    4086   424.9
    4102   425.6  4138.5   425.6  4141.5   425.6    4143   425.6    4205     425
  4238.5  424.81  4241.5   424.8    4259   424.7    4297   424.2  4338.5     424
  4341.5  423.94    4381   423.7    4411   423.8  4438.5  424.35  4441.5   424.4
    4446   424.5    4481   422.9    4512   422.8  4538.5  422.37  4541.5   422.3
    4543   422.3    4598   422.3    4625   422.5  4638.5  423.14  4641.5   423.3
    4644   423.4    4650     423    4678     423    4696   422.4    4702   422.7
  4728.3  435.88  4728.3   441.8    4740   441.8    4760   441.7    5100   435.7
    5200   435.7    5450     437    5550     437    5900     435    6000     435
    6500   437.6    7510     439    7543   439.9    7586   442.4    7600   442.8
    7618     444    7646   444.6    7689   444.8
BR D #Mann= 3
     700     .07    3893     .05    4086     .07
BC Design=,, 0 ,, 0 ,,,,,,
BC HTab HWMax=444.8
BC Use User HTab Curves=0
BC User HTab FreeFlow(D)= 0

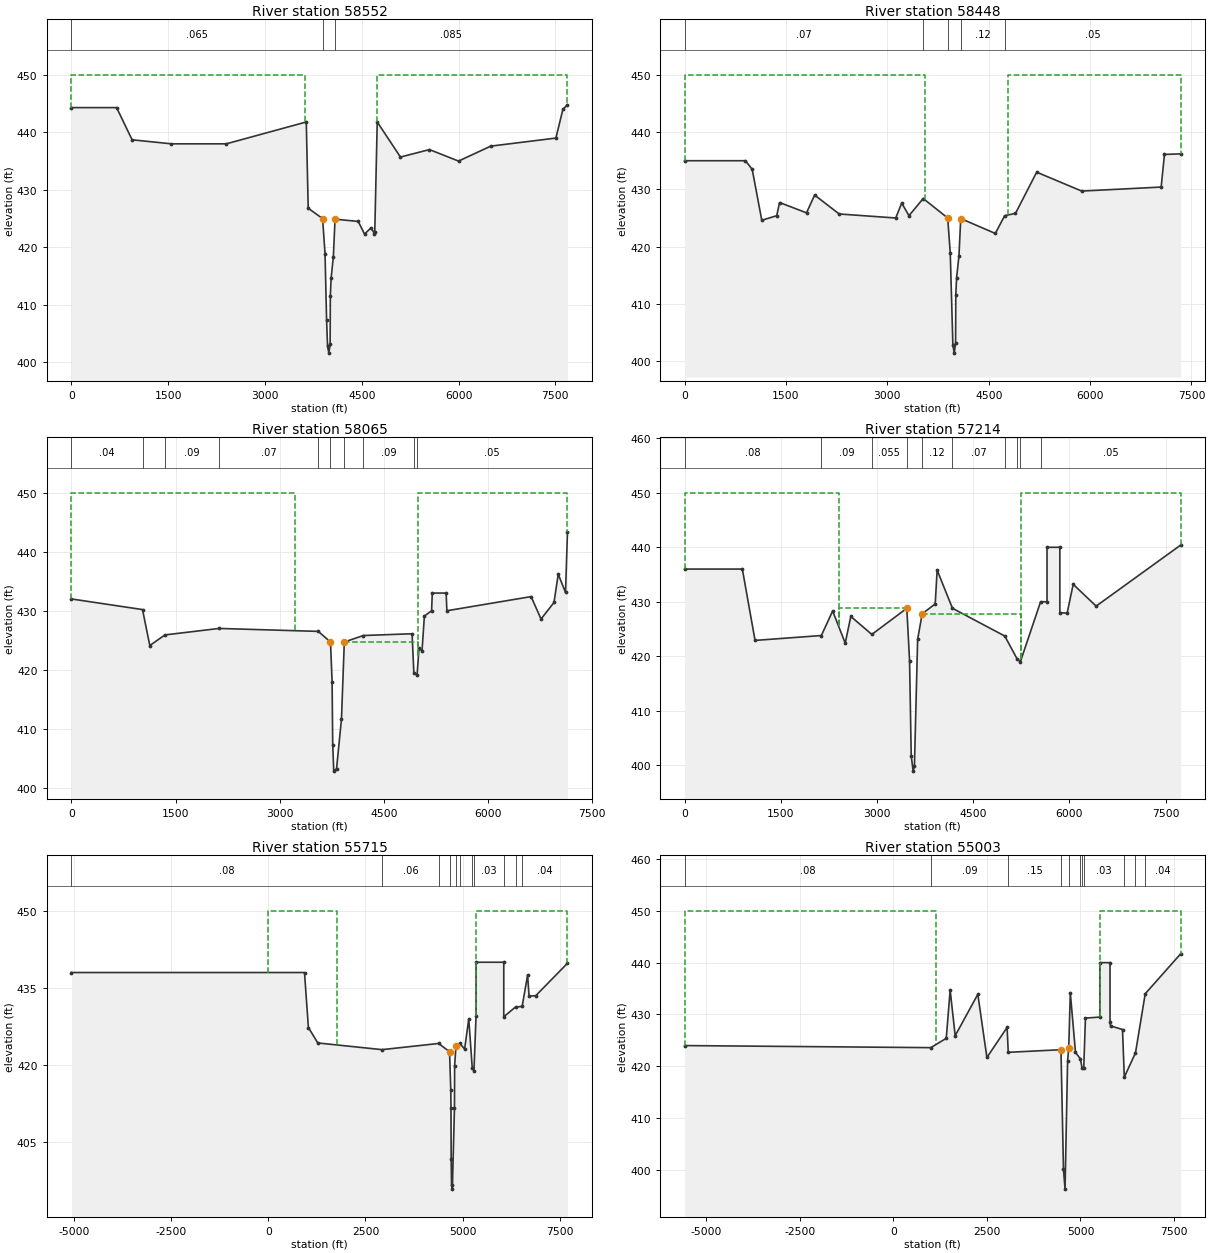
Type RM Length L Ch R = 1 ,58552   ,104,104,104
BEGIN DESCRIPTION:
This cross section corresponds to cross section 58532 of the non-georeferenced CDC model which was the source of this model.
One-foot downstream of Royal Lane.
Effective flow limit set at sta 3620 in LOB, at sta 4740 in ROB.  Stemmons North Industrial District in LOB east of Luna Road.  L.B. Houston Golf Course
in LOB.  Las Colinas Service Center in ROB.
Channel data from COD Elm Fork channel survey.
END DESCRIPTION:
XS GIS Cut Line= 6
 2454829.11679827012402.706492852452200.856129357012352.91796313
2451981.86083242 7012352.24145532450373.41063726 7012371.2374803
2447836.61452976 7012365.74339682447140.775698337012356.11513522
#Sta/Elev= 30
       0   444.3     700   444.3     940   438.7    1550     438    2400     438
    3640   441.8    3670   426.8    3893     425    3931   418.9    3955   407.3
    3970   402.8    3990   401.6    4010   403.2    4013   411.6    4025   414.6
    4060   418.4    4086   424.9    4446   424.5    4543   422.3    4644   423.4
    4696   422.4    4702   422.7    4740   441.8    5100   435.7    5550     437
    6000     435    6500   437.6    7510     439    7618     444    7689   444.8
#Mann= 3 ,0,0
       0    .065       0    3893     .05       0    4086    .085       0
#XS Ineff= 4 ,-1
       0    3620     450    3620    3893     425    4086    4740   424.9
    4740    7689     450
Permanent Ineff=
       F       F       F       F
Bank Sta=3893,4086
XS Rating Curve= 0 ,0
Exp/Cntr=0.3,0.1

Type RM Length L Ch R = 1 ,58448   ,330,383,360
BEGIN DESCRIPTION:
This cross section corresponds to cross section 58429 of the non-georeferenced CDC model which was the source of this model.
Cross-section EF076.  104 feet downstream of Royal Lane.  Effective flow limit set at sta 3550 in LOB, at sta 4780 in ROB.  Stemmons North Industrial District in LOB east of Luna Road.  L.B. Houston Golf Course in LOB.
Las Colinas Service Center in ROB.
Channel data from COD Elm Fork channel survey.
END DESCRIPTION:
XS GIS Cut Line= 6
2454833.31214267 7012296.90878872453933.463884597012280.38267513
2452203.658945267012248.614037892450400.539848097012268.93092638
2447891.41002384 7012258.77313832447493.916724327012254.24197939
#Sta/Elev= 30
       0     435     900     435    1000   433.5    1142   424.6    1363   425.4
    1405   427.7    1804   425.9    1924     429    2287   425.7    3124     425
    3213   427.6    3320   425.4    3531   428.4    3893     425    3931   418.9
    3970   402.8    3990   401.4    4010   403.2    4013   411.6    4025   414.6
    4060   418.4    4086   424.9    4598   422.3    4736   425.4    4896   425.8
    5210     433    5876   429.7    7052   430.4    7101   436.1    7340   436.2
#Mann= 5 ,-1,0
       0     .07       0    3531     .12       0    3893     .05       0
    4086     .12       0    4736     .05       0
#XS Ineff= 4 ,-1
       0    3550     450    3550    3893     425    4086    4780   424.9
    4780    7340     450
Permanent Ineff=
       F       F       F       F
Bank Sta=3893,4086
XS Rating Curve= 0 ,0
Exp/Cntr=0.3,0.1

Type RM Length L Ch R = 1 ,58065   ,780,851,790
BEGIN DESCRIPTION:
This cross section corresponds to cross section 58046 of the non-georeferenced CDC model which was the source of this model.
-------------------------------------------
CDC IRV101405-1 North Hills School Addition
Cross-section 58046 - 58429
Located in ROB within ineffective area.
-------------------------------------------
Cross-section EF075.  Effective flow limit set at sta 3220 in LOB, at sta 5000 in ROB.  Stemmons North Industrial District in LOB east of Luna Road.  L.B. Houston Golf Course in LOB.  Conveyance removed from ponds in LOB.
END DESCRIPTION:
XS GIS Cut Line= 3
2454829.654837617011968.325749982453929.740138777011955.93483321
  2447682.3323587011869.91433597
#Sta/Elev= 30
       0     432    1024   430.2    1129   424.1    1347   425.9    2128     427
    3557   426.5    3733   424.7    3756     418    3765   407.3    3780   402.8
    3820   403.2    3891   411.6    3932   424.7    4207   425.8    4909   426.1
    4934   419.5    4981   419.1    5008   423.6    5052   423.2    5086   429.1
    5190     430    5200     433    5400     433    5410     430    6624   432.4
    6767   428.6    6954   431.4    7015   436.2    7120   433.1    7148   443.3
#Mann= 10 ,-1,0
       0     .04       0    1024     .12       0    1347     .09       0
    2128     .07       0    3557     .12       0    3733     .05       0
    3932     .12       0    4207     .09       0    4934    .035       0
    4981     .05       0
#XS Ineff= 4 ,-1
       0    3220     450    3220    3733   424.7    3932    5000   424.7
    5000    7148     450
Permanent Ineff=
       F       F       F       F
Bank Sta=3733,3932
XS Rating Curve= 0 ,0
Exp/Cntr=0.3,0.1

Type RM Length L Ch R = 1 ,57214   ,640,1499,640
BEGIN DESCRIPTION:
This cross section corresponds to cross section 57195 of the non-georeferenced CDC model which was the source of this model.
Cross-section EF074.  Effective flow limit set at sta 2400 in LOB, at sta 5250 in ROB.  Stemmons North Industrial District in LOB east of Luna Road.  L.B. Houston Golf Course in LOB.  Conveyance removed from ponds in LOB.
Las Colinas Service Center in ROB.  Ineffective flow from sta 5650 - 5850 in LOB.
Channel data from COD Elm Fork channel survey.
END DESCRIPTION:
XS GIS Cut Line= 4
 2454830.46863997011217.681086772453930.677800927011198.27886821
2447956.673016677011069.461212472447118.855138517010886.29458405
#Sta/Elev= 30
       0     436     900     436    1098   422.9    2132   423.8    2308   428.3
    2504   422.4    2591   427.3    2919     424    3464   428.8    3507   419.2
    3533   401.7    3563   398.9    3583   399.9    3633   423.1    3704   427.8
    3907   429.6    3937   435.8    4176   428.8    4992   423.7    5184   419.5
    5235     419    5550     430    5650     430    5650     440    5850     440
    5850     428    5964   427.9    6058   433.2    6416   429.2    7733   440.4
#Mann= 10 ,-1,0
       0     .08       0    2132     .09       0    2919    .055       0
    3464     .05       0    3704     .12       0    4176     .07       0
    4992     .15       0    5184    .035       0    5235     .15       0
    5550     .05       0
#XS Ineff= 4 ,-1
       0    2400     450    2400    3464   428.8    3704    5250   427.8
    5250    7733     450
Permanent Ineff=
       F       F       F       F
Bank Sta=3464,3704
XS Rating Curve= 0 ,0
Exp/Cntr=0.3,0.1

Type RM Length L Ch R = 1 ,55715   ,671,712,681
BEGIN DESCRIPTION:
This cross section corresponds to cross section 55696 of the non-georeferenced CDC model which was the source of this model.
Cross-section EF073.  Effective flow limit set at sta 1770 in LOB, at sta 5346 in ROB.  Stemmons North Industrial District in LOB east of Luna Road.  L.B. Houston Golf Course in LOB.  Conveyance removed from ponds in LOB.
 Las Colinas Service Center in ROB.
Channel data from COD Elm Fork channel survey.
END DESCRIPTION:
XS GIS Cut Line= 4
2459912.197360127010696.939828932453913.643058097010565.23453063
2449742.268854927010473.647115382447153.067012347010264.68362255
#Sta/Elev= 30
   -5070     438     930     438    1030   427.3    1272   424.3    2925     423
    4383   424.2    4664   422.6    4696   415.1    4701   411.7    4706   401.7
    4716   396.6    4736  395.87    4791   411.7    4795   419.9    4829   423.7
    4930   424.2    5052   423.1    5159     429    5249   419.4    5293   418.9
    5346   429.5    5346     440    6060     440    6060   429.4    6365   431.3
    6533   431.4    6674   437.5    6711   433.4    6884   433.5    7700   439.8
#Mann= 11 ,-1,0
   -5070     .08       0    2925     .06       0    4383     .15       0
    4664     .05       0    4829     .15       0    4930     .07       0
    5249    .035       0    5293     .03       0    6060     .03       0
    6365     .03       0    6533     .04       0
#XS Ineff= 4 ,-1
       0    1770     450    1770    4664   422.6    4829    5346   423.7
    5346    7700     450
Permanent Ineff=
       F       F       F       F
Bank Sta=4664,4829
XS Rating Curve= 0 ,0
Exp/Cntr=0.3,0.1

Type RM Length L Ch R = 1 ,55003   ,41,41,36
BEGIN DESCRIPTION:
This cross section corresponds to cross section 54985 of the non-georeferenced CDC model which was the source of this model.
Cross-section EF072.  Effective flow limit set at sta 1150 in LOB, at sta 5520 in ROB.  Stemmons North Industrial District in LOB east of Luna Road.  L.B. Houston Golf Course in LOB.  Conveyance removed from ponds in LOB.
 Las Colinas Service Center in ROB.
Channel data from COD Elm Fork channel survey.
END DESCRIPTION:
XS GIS Cut Line= 6
2460434.000396017010150.277736982454437.727967927009938.81386746
2453841.462100097009917.786022382449500.831017587009786.25905447
2448716.278124757009627.228204552447230.890019427009318.01589647
#Sta/Elev= 30
   -5580     424    1000   423.6    1413   425.4    1517   434.7    1652   425.9
    2257   433.9    2499   421.7    3039   427.5    3070   422.7    4479   423.2
    4546   400.1    4588   396.3    4656     421    4687   423.6    4729   434.2
    4867   422.7    5001   421.4    5041   419.7    5088   419.7    5133   429.3
    5520   429.5    5520     440    5790     440    5790   428.6    5803   427.8
    6124   427.1    6172   417.9    6471   422.6    6731     434    7677   441.7
#Mann= 11 ,-1,0
   -5580     .08       0    1000     .09       0    3070     .15       0
    4479     .05       0    4687     .15       0    5001     .03       0
    5041    .035       0    5088     .03       0    6172     .03       0
    6471      .1       0    6731     .04       0
#XS Ineff= 4 ,-1
   -5580    1150     450    1150    4479   423.2    4687    5520   423.6
    5520    7677     450
Permanent Ineff=
       F       F       F       F
Bank Sta=4479,4687
XS Rating Curve= 0 ,0
Exp/Cntr=0.3,0.1

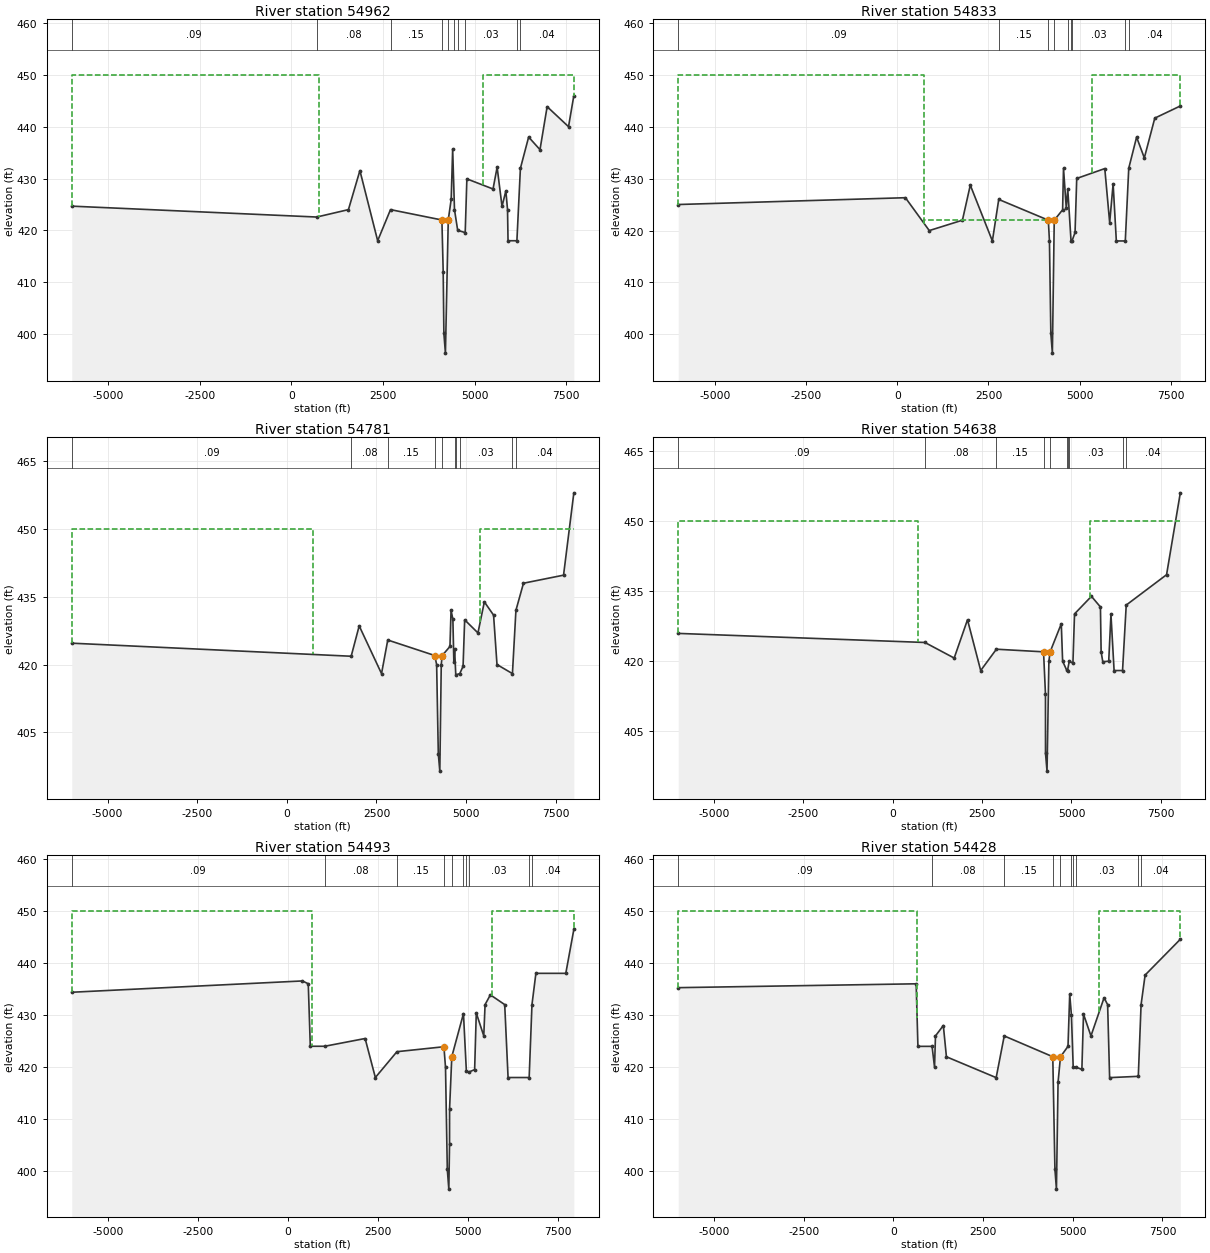
Type RM Length L Ch R = 1 ,54962   ,111,129,116
BEGIN DESCRIPTION:
This cross section corresponds to cross section 54948 of the non-georeferenced CDC model which was the source of this model.
Added cross-section.
END DESCRIPTION:
XS GIS Cut Line= 6
2460485.525092127010094.774753622454103.001603257009882.74344155
2449558.522175167009764.589150292448830.744103167009499.31113756
2447148.799960497009159.033602882446881.189931427009049.55875622
#Sta/Elev= 30
   -6000  424.67   690.5  422.57 1556.15     424 1869.25  431.53 2354.41     418
 2705.24     424 4108.81     422 4144.18     412 4162.89  400.12 4204.89  396.32
 4282.43     422 4362.55     426 4402.65  435.67  4452.4     424 4539.91     420
 4745.25  419.57 4790.68  429.93 5505.49  427.98 5617.18  432.19 5750.67  424.62
 5855.45  427.61 5901.17     424 5914.93     418 6157.12     418  6252.7  431.96
 6477.66     438  6787.6  435.56 6982.84  443.86 7566.92     440 7712.33     446
#Mann= 10 ,-1,0
   -6000     .09       0   690.5     .08       0 2705.24     .15       0
 4108.81     .05       0 4282.43     .15       0  4452.4     .03       0
 4539.91    .035       0 4745.25     .03       0 6157.12      .1       0
  6252.7     .04       0
#XS Ineff= 4 ,-1
   -6000     748     450     748 4108.81     422 4282.43    5225     422
    5225 7712.33     450
Permanent Ineff=
       F       F       F       F
Bank Sta=4108.81,4282.43
XS Rating Curve= 0 ,0
Exp/Cntr=0.3,0.1

Type RM Length L Ch R = 1 ,54833   ,48,52,48
BEGIN DESCRIPTION:
This cross section corresponds to cross section 54811 of the non-georeferenced CDC model which was the source of this model.
Added cross-section.
END DESCRIPTION:
XS GIS Cut Line= 6
2460597.345633917009911.39991964   2454599.13828   7009764.74202
  2449366.855235 7009636.8111906 2448858.5219348 7009461.8112126
 2447169.6332522 7009124.3112314 2446929.8761858 7009020.6300083
#Sta/Elev= 30
   -6000  425.02   223.9  426.33  877.58     420 1785.92     422 2001.19  428.75
 2606.32     418 2780.57     426 4138.89     422 4169.77     418 4207.94400.1937
 4249.94396.3937 4301.16     422 4530.47     424 4554.75     432 4631.26  424.28
 4671.66     428 4760.88  418.03 4787.54     418 4871.11  419.63 4917.09  430.04
 5685.95  431.94 5819.71  421.53 5914.26  429.01 6002.21     418 6247.61     418
 6342.29     432  6557.4     438 6769.19     434 7055.69  441.66 7754.95     444
#Mann= 9 ,-1,0
   -6000     .09       0 2780.57     .15       0 4138.89     .05       0
 4301.16     .15       0 4671.66     .03       0 4760.88    .035       0
 4787.54     .03       0 6247.61      .1       0 6342.29     .04       0
#XS Ineff= 4 ,-1
   -6000     737     450     737 4138.89     422 4301.16 5330.62     422
 5330.62 7754.95     450
Permanent Ineff=
       F       F       F       F
Bank Sta=4138.89,4301.16
XS Rating Curve= 0 ,0
Exp/Cntr=0.3,0.1

Type RM Length L Ch R = 1 ,54781   ,138,143,138
BEGIN DESCRIPTION:
This cross section corresponds to cross section 54763 of the non-georeferenced CDC model which was the source of this model.
Added cross-section.
END DESCRIPTION:
XS GIS Cut Line= 6
2460634.365586547009852.24738975  2449369.633117 7009589.5891722
 2448875.1885681 7009418.7558525 2448533.5219286 7009352.0889911
 2447182.1332272 7009078.4779897 2446726.5344009 7008900.2017715
#Sta/Elev= 30
   -6000  424.73 1793.61  421.84 2017.31  428.56 2640.34     418 2814.19  425.43
 4125.45     422 4125.65  421.97 4177.49     420 4224.37400.2197 4266.37396.4197
 4306.41     420 4332.47     422 4549.08     424 4579.57     432 4630.77     430
 4657.65  420.56 4678.03  423.47 4711.43  417.71 4822.61     418 4914.75  419.61
 4959.31   429.9 5329.96     427 5508.38  433.87 5765.74  430.94 5861.01     420
 6291.74     418 6389.23     432  6599.8     438 7717.38  439.78  8004.8     458
#Mann= 10 ,-1,0
   -6000     .09       0 1793.61     .08       0 2814.19     .15       0
 4125.65     .05       0 4332.47     .15       0 4678.03     .03       0
 4711.43    .035       0 4822.61     .03       0 6291.74      .1       0
 6389.23     .04       0
#XS Ineff= 4 ,-1
   -6000     737     450     737 4125.45     422 4332.47    5390     422
    5390  8004.8     450
Permanent Ineff=
       F       F       F       F
Bank Sta=4125.45,4332.47
XS Rating Curve= 0 ,0
Exp/Cntr=0.3,0.1

Type RM Length L Ch R = 1 ,54638   ,142,145,142
BEGIN DESCRIPTION:
This cross section corresponds to cross section 54619 of the non-georeferenced CDC model which was the source of this model.
Added cross-section.
END DESCRIPTION:
XS GIS Cut Line= 6
2460723.948659167009753.93118406   2454726.12812   7009592.22534
  2449373.799775 7009447.9224608 2448872.4110146 7009281.2557994
 2447185.1886673 7008940.9779366 2446785.7819858 7008757.9136702
#Sta/Elev= 30
   -6000  425.94  899.83     424 1719.02  420.67 2091.55  428.86 2460.78     418
 2899.64  422.56 4218.74     422 4272.39  412.98    4274  400.29    4316  396.49
 4368.42     420 4402.73     422 4715.03     428 4752.29     420 4860.93  418.17
 4888.96     418  4938.3     420 5040.44  419.57 5085.41  430.11 5558.46  433.87
 5810.17  431.59 5829.54     422 5875.75  419.88 6041.98     420 6104.45     430
 6192.12     418 6428.58     418  6531.8     432 7660.01  438.49  8044.5     456
#Mann= 10 ,-1,0
   -6000     .09       0  899.83     .08       0 2899.64     .15       0
 4218.74     .05       0 4402.73     .15       0 4860.93    .035       0
 4888.96     .03       0  4938.3     .03       0 6428.58      .1       0
  6531.8     .04       0
#XS Ineff= 4 ,-1
   -6000     693     450     693 4218.74     422 4402.73    5525     422
    5525  8044.5     450
Permanent Ineff=
       F       F       F       F
Bank Sta=4218.74,4402.73
XS Rating Curve= 0 ,0
Exp/Cntr=0.3,0.1

Type RM Length L Ch R = 1 ,54493   ,60,65,60
BEGIN DESCRIPTION:
This cross section corresponds to cross section 54473 of the non-georeferenced CDC model which was the source of this model.
Added cross-section.
END DESCRIPTION:
XS GIS Cut Line= 6
2460833.692593467009624.18911221  2449432.410878 7009306.2557494
 2449164.3553126  7009227.088913 2449025.4664828 7009197.9223046
 2447197.6886423 7008782.6445919 2446951.2071798 7008773.9923782
#Sta/Elev= 30
   -6000  434.37   407.1  436.54  569.76     436  626.72     424 1027.08     424
 2149.49  425.49 2433.63     418 3033.15  422.96 4338.48  423.91 4382.75  419.96
 4432.84400.3761 4474.84 396.576 4494.84405.1761  4495.9     412 4557.45     422
 4881.58  430.27 4962.84  419.16 5041.88  419.08 5192.06  419.52 5237.71  430.38
 5445.68     426  5482.1     432 5628.97  433.87 6027.36     432 6120.94     418
  6706.9     418 6784.83     432 6893.92     438 7724.56     438 7948.13  446.43
#Mann= 10 ,-1,0
   -6000     .09       0 1027.08     .08       0 3033.15     .15       0
 4338.48     .05       0 4557.45     .15       0 4881.58     .03       0
 4962.84    .035       0 5041.88     .03       0  6706.9      .1       0
 6784.83     .04       0
#XS Ineff= 4 ,-1
   -6000     677     450     677 4338.48  423.91 4557.45    5671     422
    5671 7948.13     450
Permanent Ineff=
       F       F       F       F
Bank Sta=4338.48,4557.45
XS Rating Curve= 0 ,0
Exp/Cntr=0.3,0.1

Type RM Length L Ch R = 1 ,54428   ,178,177,144
BEGIN DESCRIPTION:
This cross section corresponds to cross section 54411 of the non-georeferenced CDC model which was the source of this model.
Added cross-section.
END DESCRIPTION:
XS GIS Cut Line= 6
2460888.397042837009550.96973644   2454890.50286   7009392.01889
    2449425.1406   7009247.18073  2448979.980353 7009085.7483164
  2447536.222414 7008705.1959279 2446979.1943286 7008655.7340846
#Sta/Elev= 30
   -6000  435.26   633.4     436  682.35     424 1077.04     424 1145.62     420
 1171.65     426 1390.86     428 1476.88     422 2863.96     418 3088.74     426
 4442.25  422.01 4502.11400.4098 4544.11396.6098 4589.17  417.11 4656.45     422
 4866.49     424  4914.3     434 4962.01     430 5011.57     420 5088.25     420
 5253.37  419.58 5298.47  430.19 5506.35     426 5871.92  433.32 5971.28     432
 6026.83     418  6826.5  418.25  6903.9     432 7016.49  437.68  7997.7  444.54
#Mann= 10 ,-1,0
   -6000     .09       0 1077.04     .08       0 3088.74     .15       0
 4442.25     .05       0 4656.45     .15       0 4962.01     .03       0
 5011.57    .035       0 5088.25     .03       0  6826.5      .1       0
  6903.9     .04       0
#XS Ineff= 4 ,-1
   -6000     660     450     660 4442.25  422.01 4656.45    5735     422
    5735  7997.7     450
Permanent Ineff=
       F       F       F       F
Bank Sta=4442.25,4656.45
XS Rating Curve= 0 ,0
Exp/Cntr=0.3,0.1