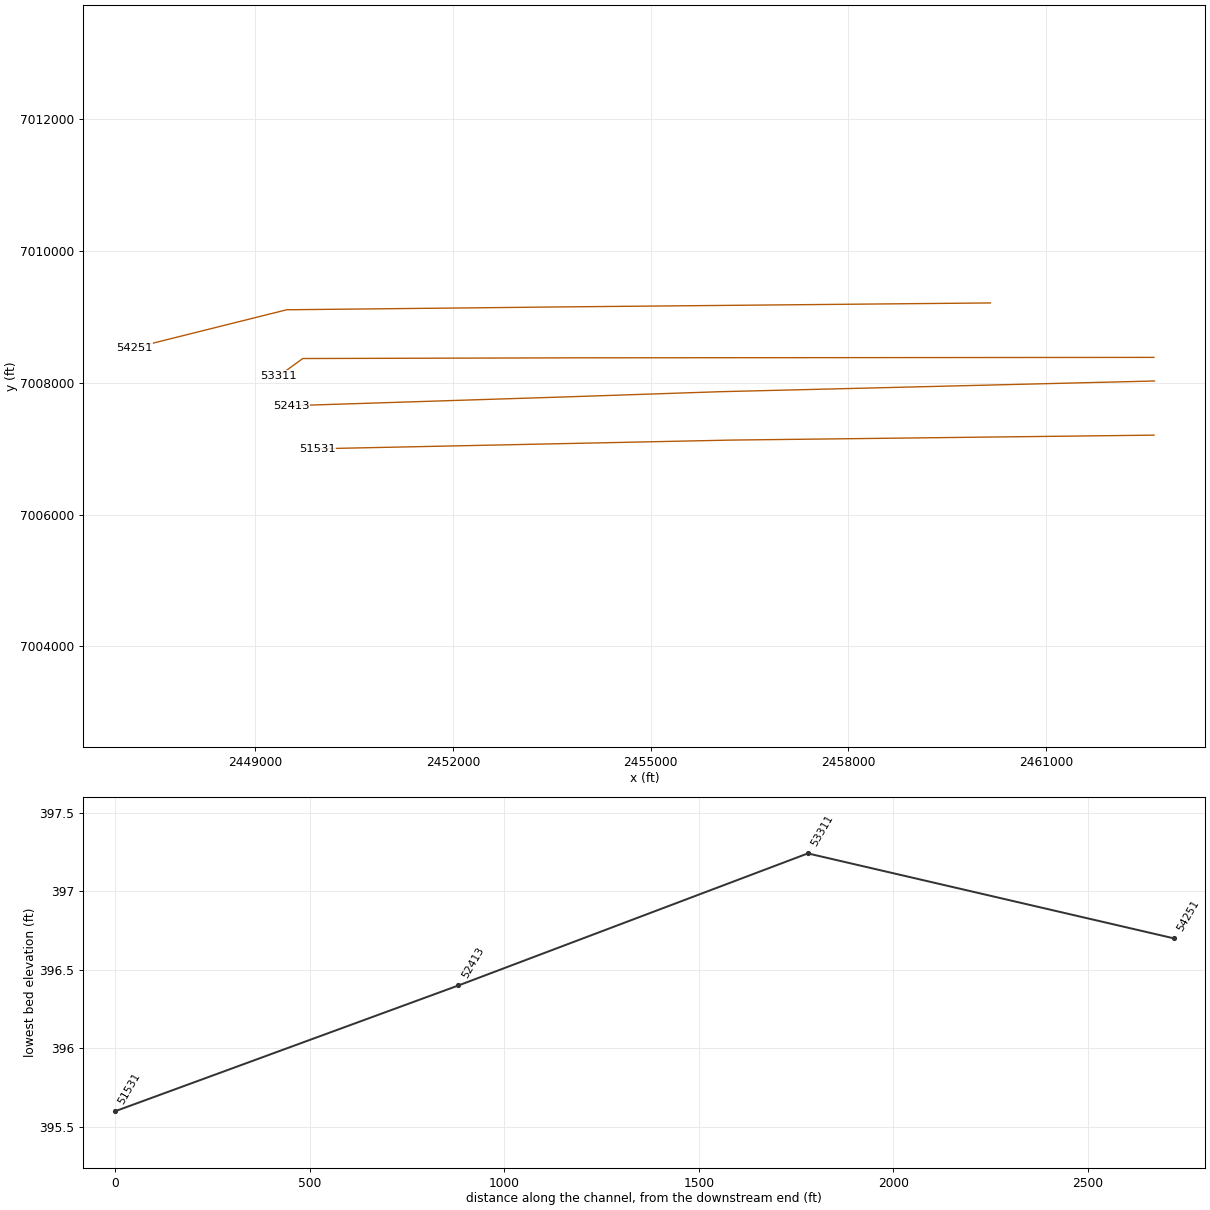
HEC-RAS study CDC_Consolidated_Model.prj: Upper Trinity CDC Consolidated Model

--- CDC_Consolidated_Model.g01 (geometry) --- (continued)

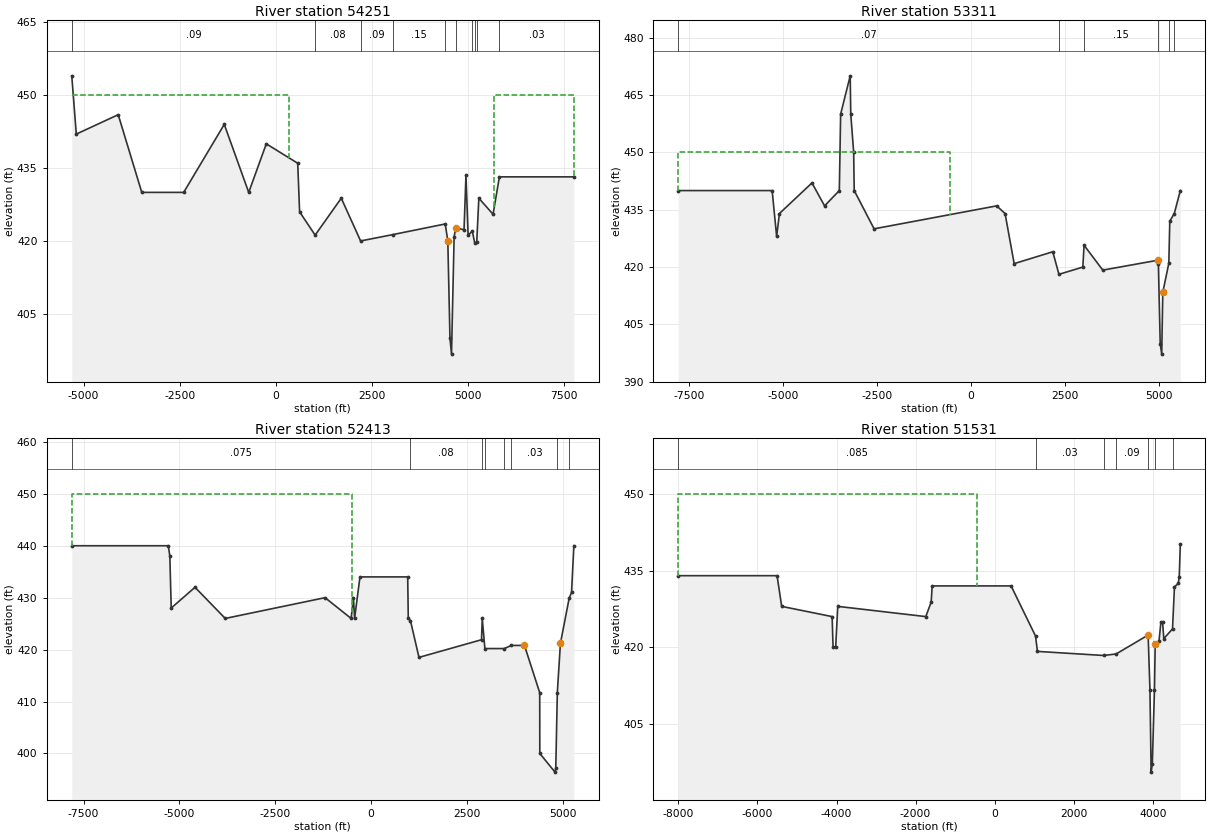
Type RM Length L Ch R = 1 ,54251   ,749,940,899
BEGIN DESCRIPTION:
This cross section corresponds to cross section 54233 of the non-georeferenced CDC model which was the source of this model.
------------------------------------
CDC IRV012908-1 O'Connor Substation
Cross-section 54233 - 54985
Located in ROB.
------------------------------------
Cross-section EF071.  Effective flow limit set at sta 350 in LOB, at sta 5680 in ROB.  Stemmons North Industrial District in LOB east of Luna Road.  L.B. Houston Golf Course in LOB.  Conveyance removed from ponds in LOB.
Las Colinas Service Center in ROB.
END DESCRIPTION:
XS GIS Cut Line= 5
2460156.426504257009215.047926552453838.89091101 7009156.4230438
2449479.97705668 7009111.29124432448139.793713427008776.59998456
2447169.590845877008534.30595697
#Sta/Elev= 30
 -5308.3     454 -5190.6     442 -4100.4     446 -3487.4     430 -2397.8     430
 -1341.9     444  -706.1     430    -249     440  568.51     436   617.4     426
    1021   421.2    1701   428.8    2204     420    3036   421.3    4405   423.5
    4472     420    4528     400    4568   396.7    4636   420.8    4678   422.7
    4894   422.3    4944   433.5    5000   421.2    5109     422    5172   419.6
    5224   419.7    5279   428.8    5649   425.5    5814   433.2    7750   433.2
#Mann= 10 ,-1,0
 -5308.3     .09       0    1021     .08       0    2204     .09       0
    3036     .15       0    4405     .05       0    4678     .15       0
    5109     .05       0    5172    .035       0    5224     .05       0
    5814     .03       0
#XS Ineff= 4 ,-1
 -5308.3     350     450     350    4472     420    4678    5680   422.7
    5680    7750     450
Permanent Ineff=
       F       F       F       F
Bank Sta=4472,4678
XS Rating Curve= 0 ,0
Exp/Cntr=0.3,0.1

Type RM Length L Ch R = 1 ,53311   ,650,898,650
BEGIN DESCRIPTION:
This cross section corresponds to cross section 53292 of the non-georeferenced CDC model which was the source of this model.
Cross-section EF070.  Effective flow limit set at sta -550 in LOB, at Las Colinas Levee in ROB.  Stemmons North Industrial District in LOB east of Luna Road.  L.B. Houston Golf Course in LOB.  Conveyance removed from pond in LOB. At Hackberry Creek/Elm Fork confluence in ROB.
Channel data from COD Elm Fork channel survey - cross-section EF#070 surveyed
 February 1994.
END DESCRIPTION:
XS GIS Cut Line= 5
2462636.30510629 7008388.26831812460136.30580959 7008386.3930878
2453834.382061757008381.666063132449723.352882277008370.99613696
2449356.613458257008105.19745597
#Sta/Elev= 30
 -7785.9     440 -5285.9     440 -5166.1     428 -5092.1     434 -4225.7     442
 -3890.1     436 -3497.5     440 -3462.4     460   -3208     470 -3193.1     460
 -3115.4     450 -3101.2     440 -2571.9     430   690.7     436   914.9     434
    1157   420.9    2185     424    2349   418.1    2985     420    3018   425.7
    3516   419.2    4986   421.8    4996   420.8    5045     400    5085  397.24
    5114   413.4    5274     421    5300     432    5420     434    5580     440
#Mann= 6 ,-1,0
 -7785.9     .07       0    2349      .1       0    3018     .15       0
    4996     .05       0    5274     .08       0    5420    .035       0
#XS Ineff= 3 ,-1
 -7785.9    -550     450    -550    4986   421.8    5114    5580   413.4
Permanent Ineff=
       F       F       F
Bank Sta=4986,5114
XS Rating Curve= 0 ,0
Exp/Cntr=0.3,0.1

Type RM Length L Ch R = 1 ,52413   ,690,882,670
BEGIN DESCRIPTION:
This cross section corresponds to cross section 52394 of the non-georeferenced CDC model which was the source of this model.
Cross-section EF069.  Effective flow limit set at sta -500 in LOB at Burlington Northern Railroad, at Las Colinas Levee in ROB.  Stemmons North Industrial District in LOB east of Luna Road. L.B. Houston Golf Course in LOB.  Conveyance removed from pond in LOB.
Channel data from COD Elm Fork channel survey.
END DESCRIPTION:
XS GIS Cut Line= 5
2462643.637376487008029.971736162460144.397328857007968.33421263
2456049.718838427007867.349178392453824.26101899 7007792.2171108
2449555.109124247007655.18096755
#Sta/Elev= 30
   -7806     440 -5288.1     440 -5248.2     438 -5212.6     428 -4592.5     432
 -3803.7     426   -1200     430    -520     426    -460     430    -430     426
    -290     434     955     434     970     426    1026   425.6    1249   418.5
    2880   421.9    2899     426    2968   420.2    3473   420.2    3659   420.8
    4000   420.8    4398   411.7    4400     400    4797   396.4    4817   397.2
    4857   411.7    4938   421.2    5166   429.9    5228     431    5288     440
#Mann= 8 ,-1,0
   -7806    .075       0    1026     .08       0    2880    .035       0
    2968     .02       0    3473     .07       0    3659     .03       0
    4857     .05       0    5166    .035       0
#XS Ineff= 3 ,-1
   -7806    -500     450    -500    4000   420.8    4938    5288   421.2
Permanent Ineff=
       F       F       F
Bank Sta=4000,4938
XS Rating Curve= 0 ,0
Exp/Cntr=0.3,0.1

Type RM Length L Ch R = 1 ,51531   ,750,759,750
BEGIN DESCRIPTION:
This cross section corresponds to cross section 51512 of the non-georeferenced CDC model which was the source of this model.
Cross-section EF068.  Effective flow limit set at sta -450 in LOB at Burlington Northern Railroad, at Las Colinas Levee in ROB. Stemmons North Industrial District in LOB east of Luna Road. L.B. Houston Golf Course in LOB.  Conveyance removed from pond in LOB.
Channel data from COD Elm Fork channel survey.
END DESCRIPTION:
XS GIS Cut Line= 4
2462637.917126797007208.013196652460138.088286347007178.75967629
2456231.689931187007133.046185052449940.341293427007001.01167221
#Sta/Elev= 30
 -8003.4     434 -5503.4     434 -5387.2     428 -4110.6     426 -4087.5     420
 -4021.3     420 -3968.4     428 -1742.3     426 -1605.8  428.83   -1580     432
   415.7     432    1034   422.2    1082   419.2    2759   418.4    3073   418.7
    3882   422.4    3928   411.7    3958   395.6    3988   397.2    4042   411.7
    4061   420.6    4158   421.3    4205   424.9    4248   424.9    4278   421.7
    4499   423.6    4548   431.8    4646   432.5    4669   433.8    4696   440.1
#Mann= 7 ,-1,0
 -8003.4    .085       0    1034     .03       0    2759     .02       0
    3073     .09       0    3882     .05       0    4061     .06       0
    4499    .035       0
#XS Ineff= 3 ,-1
 -8003.4    -450     450    -450    3882   422.4    4061    4696   420.6
Permanent Ineff=
       F       F       F
Bank Sta=3882,4061
XS Rating Curve= 0 ,0
Exp/Cntr=0.3,0.1