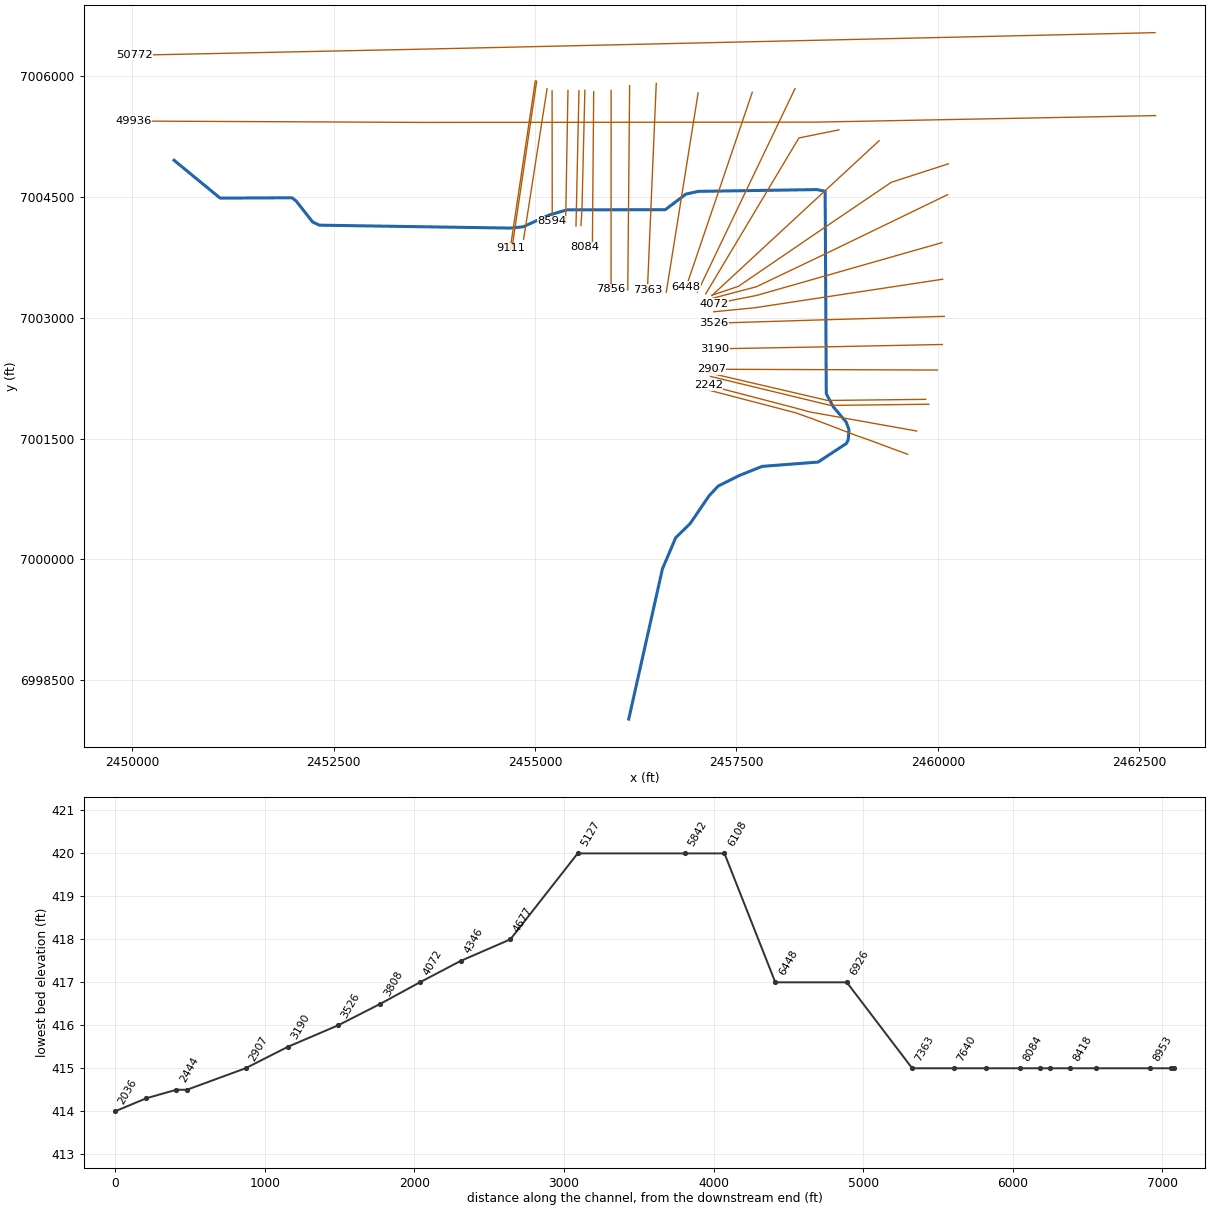
HEC-RAS study CDC_Consolidated_Model.prj: Upper Trinity CDC Consolidated Model

--- CDC_Consolidated_Model.g01 (geometry) --- (continued)

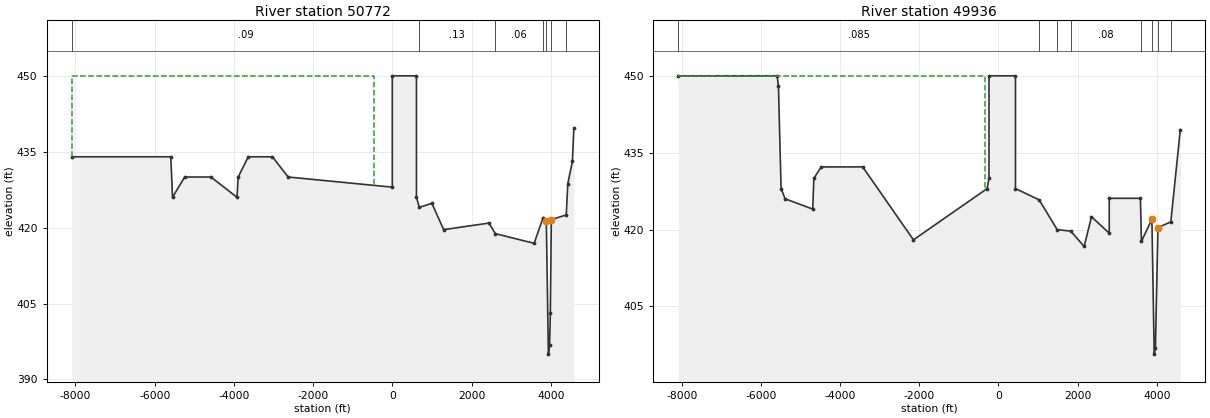
Type RM Length L Ch R = 1 ,50772   ,869,836,829
BEGIN DESCRIPTION:
This cross section corresponds to cross section 50753 of the non-georeferenced CDC model which was the source of this model.
Cross-section EF067.  Effective flow limit set at sta -460 in LOB at Burlington Northern Railroad, at Las Colinas Levee in ROB. Ineffective flow from sta 0 - 610.  Stemmons North Industrial District east of Luna Road in LOB.
Channel data from COD Elm Fork channel survey - cross-section EF#067 surveyed February 1994.
END DESCRIPTION:
XS GIS Cut Line= 4
2462696.620144067006539.123915782460197.254506597006482.80864038
2453595.102028527006334.050079632450022.619015997006258.97313005
#Sta/Elev= 30
 -8093.1     434 -5593.1     434   -5549     426 -5242.1     430   -4580     430
 -3921.3     426 -3890.6     430 -3636.7     434 -3026.8     434   -2630     430
       0     428       0     450     610     450     610     426   681.7     424
    1000   424.8    1297   419.6    2441   420.9    2603   418.8    3581   416.9
    3809     422    3889   421.4    3941     395    3971   396.8    3991   403.2
    4015   421.6    4392   422.5    4432   428.7    4548   433.1    4584   439.7
#Mann= 7 ,-1,0
 -8093.1     .09       0   681.7     .13       0    2603     .06       0
    3809     .15       0    3889     .05       0    4015    .075       0
    4392    .035       0
#XS Ineff= 3 ,-1
 -8093.1    -460     450    -460    3889   421.4    4015    4584   421.6
Permanent Ineff=
       F       F       F
Bank Sta=3889,4015
XS Rating Curve= 0 ,0
Exp/Cntr=0.3,0.1

Type RM Length L Ch R = 1 ,49936   ,0,0,0
BEGIN DESCRIPTION:
This cross section corresponds to cross section 49916 of the non-georeferenced CDC model which was the source of this model.
Cross-section EF066.  Effective flow imit set at sta -349.05 LOB at Burlington Northern Railroad, at Las Colinas Levee in ROB.  Ineffective flow from sta -240 - 430.  Winchester Gun Club in LOB. Stemmons North Industrial District east of Luna Road in LOB. Ineffective flow from sta 2800 - 3135 due to Winchester Gun Club levee -  conveyance removed below elev. 426.1.
Channel data fro
END DESCRIPTION:
XS GIS Cut Line= 5
2462703.889352597005509.338557192460204.348652517005461.41895089
  2458483.9761097005428.437061472453607.589864437005425.03614964
2450015.204988847005441.82318956
#Sta/Elev= 30
 -8093.5     450 -5593.5     450 -5560.9     448 -5493.9     428 -5391.4     426
 -4694.8     424 -4665.5     430 -4480.2  432.22 -3431.6  432.23 -2148.9     418
 -285.75     428    -240     430    -240     450     430     450     430     428
    1028   425.8    1484     420    1827   419.7    2166   416.7    2351   422.5
    2800   419.3    2800   426.1    3588   426.1    3613   417.7    3878     422
    3936   395.7    3966   396.8    4031   420.4    4356   421.5    4596   439.5
#Mann= 8 ,-1,0
 -8093.5    .085       0    1028     .05       0    1484      .1       0
    1827     .08       0    3613     .05       0    3878     .05       0
    4031     .15       0    4356    .035       0
#XS Ineff= 3 ,-1
 -8093.5 -349.05     450 -349.05    3878     422    4031    4596   420.4
Permanent Ineff=
       F       F       F
Bank Sta=3878,4031
XS Rating Curve= 0 ,0
Exp/Cntr=0.3,0.1

River Reach=Elm Fork Split1 ,efs1
Reach XY= 30
      2450520.46       7004955.1       2451091.8     7004485.366
      2451983.89     7004489.366     2452035.895     7004449.362
     2452239.916     7004189.336     2452323.924     7004149.332
      2454697.52      7004113.21      2454854.08      7004129.49
      2455170.85      7004273.73      2455400.65      7004340.46
      2456617.34      7004341.08      2456873.19      7004534.61
      2457026.68      7004568.96      2458498.38      7004591.24
      2458602.19      7004571.22      2458616.23      7002057.28
      2458703.76      7001894.41      2458863.47      7001704.89
       2458898.8      7001608.72       2458887.5      7001481.44
      2458864.88      7001439.01      2458514.15      7001208.75
      2457820.55      7001155.54      2457536.75      7001042.19
      2457273.68      7000910.34      2457161.36      7000790.02
     2456925.972     7000444.975     2456747.051     7000269.632
     2456582.443     6999883.163      2456164.29      6998018.92

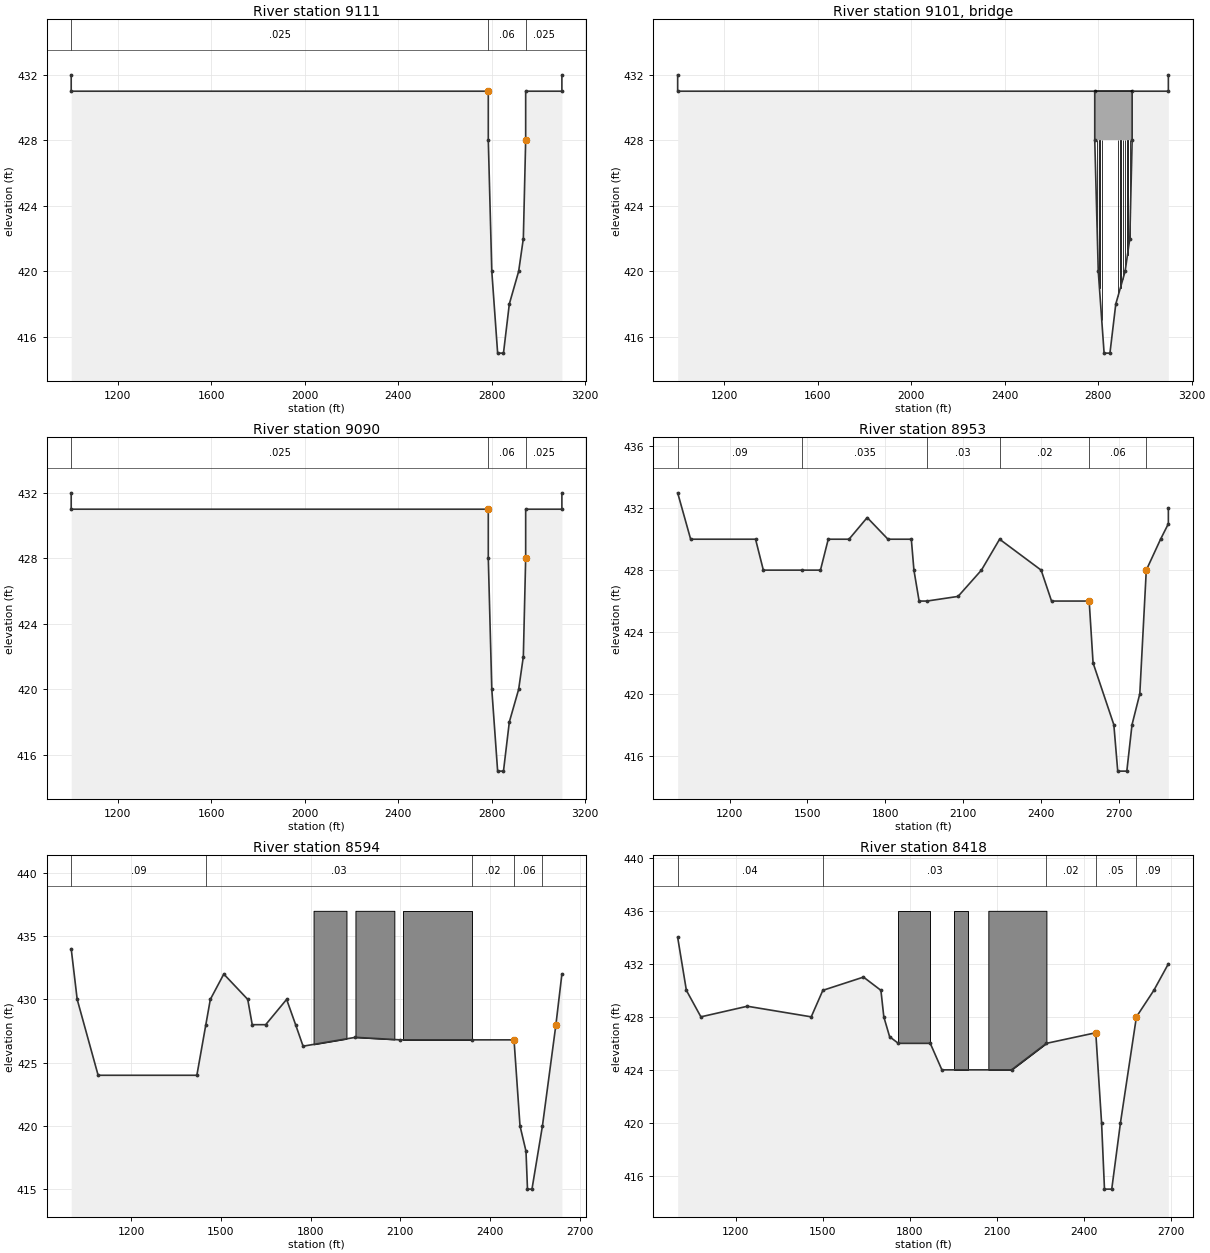
Type RM Length L Ch R = 1 ,9111    ,21,21,21
BEGIN DESCRIPTION:
This cross section corresponds to cross section 9111 of the non-georeferenced CDC model which was the source of this model.
Upstream bounding cross section for Burlington Northern RR bridge.
END DESCRIPTION:
XS GIS Cut Line= 2
2455004.091664587005938.998704392454693.73172101 7003862.0596168
#Sta/Elev= 14
    1000     432    1000     431    2785     431    2785     428    2800     420
    2825     415    2850     415    2875     418    2915     420    2935     422
    2945     428    2945     431    3100     431    3100     432
#Mann= 3 ,-1,0
    1000    .025       0    2785     .06       0    2945    .025       0
Bank Sta=2785,2945
XS Rating Curve= 0 ,0
Exp/Cntr=0.3,0.1

Type RM Length L Ch R = 3 ,9101    ,,,
BEGIN DESCRIPTION:
Burlington Northern Railroad
END DESCRIPTION:
Node Name=BN Railroad
Bridge Culvert--1,0,-1,-1, 0
Deck Dist Width WeirC Skew NumUp NumDn MinLoCord MaxHiCord MaxSubmerge Is_Ogee
1,19,2.6,0, 2, 2, , , 0.95, 0, 0,0,,
    2785    2945
     431     431
     428     428
    2785    2945
     431     431
     428     428
Pier Skew, UpSta & Num, DnSta & Num=  ,2795, 2 ,2795, 2 , 0 , 0 , 0 ,,
       1       1
     400     430
       1       1
     400     430
Pier Skew, UpSta & Num, DnSta & Num=  ,2805, 2 ,2805, 2 , 0 , 0 , 0 ,,
       1       1
     400     430
       1       1
     400     430
Pier Skew, UpSta & Num, DnSta & Num=  ,2815, 2 ,2815, 2 , 0 , 0 , 0 ,,
       1       1
     400     430
       1       1
     400     430
Pier Skew, UpSta & Num, DnSta & Num=  ,2885, 2 ,2885, 2 , 0 , 0 , 0 ,,
       1       1
     400     430
       1       1
     400     430
Pier Skew, UpSta & Num, DnSta & Num=  ,2895, 2 ,2895, 2 , 0 , 0 , 0 ,,
       1       1
     400     430
       1       1
     400     430
Pier Skew, UpSta & Num, DnSta & Num=  ,2905, 2 ,2905, 2 , 0 , 0 , 0 ,,
       1       1
     400     430
       1       1
     400     430
Pier Skew, UpSta & Num, DnSta & Num=  ,2915, 2 ,2915, 2 , 0 , 0 , 0 ,,
       1       1
     400     430
       1       1
     400     430
Pier Skew, UpSta & Num, DnSta & Num=  ,2925, 2 ,2925, 2 , 0 , 0 , 0 ,,
       1       1
     400     430
       1       1
     400     430
Pier Skew, UpSta & Num, DnSta & Num=  ,2935, 2 ,2935, 2 , 0 , 0 , 0 ,,
       1       1
     400     430
       1       1
     400     430
BR Coef=-1 , 0 , 0 ,, 0 ,,,0.8,0,,0,
WSPro=,,,, 1 ,,,, 0 ,,,, 0 ,,,,-1 ,-1 ,-1 , 0 , 0 , 0 , 0 , 0
BC Design=,, 0 ,, 0 ,,,,,,
BC HTab HWMax=432
BC Use User HTab Curves=0
BC User HTab FreeFlow(D)= 0

Type RM Length L Ch R = 1 ,9090    ,137,137,137
BEGIN DESCRIPTION:
This cross section corresponds to cross section 9089 of the non-georeferenced CDC model which was the source of this model.
Downstream bounding cross section for Burlington Northern RR bridge.
END DESCRIPTION:
XS GIS Cut Line= 2
2455021.354097257005936.887488132454714.29664052 7003859.4572598
#Sta/Elev= 14
    1000     432    1000     431    2785     431    2785     428    2800     420
    2825     415    2850     415    2875     418    2915     420    2935     422
    2945     428    2945     431    3100     431    3100     432
#Mann= 3 ,-1,0
    1000    .025       0    2785     .06       0    2945    .025       0
Bank Sta=2785,2945
XS Rating Curve= 0 ,0
Exp/Cntr=0.3,0.1

Type RM Length L Ch R = 1 ,8953    ,160,359,350
BEGIN DESCRIPTION:
This cross section corresponds to cross section 8953 of the non-georeferenced CDC model which was the source of this model.
END DESCRIPTION:
XS GIS Cut Line= 2
2455150.116963097005842.398831962454859.196613167003974.92323622
#Sta/Elev= 30
    1000     433    1050     430    1300     430    1330     428    1480     428
    1550     428    1580     430    1660     430    1730   431.4    1810     430
    1900     430    1910     428    1930     426    1960     426    2080   426.3
    2170     428    2240     430    2400     428    2440     426    2585     426
    2600     422    2680     418    2695     415    2730     415    2750     418
    2780     420    2805     428    2860     430    2890     431    2890     432
#Mann= 6 ,-1,0
    1000     .09       0    1480    .035       0    1960     .03       0
    2240     .02       0    2585     .06       0    2805     .08       0
Bank Sta=2585,2805
XS Rating Curve= 0 ,0
Exp/Cntr=0.3,0.1

Type RM Length L Ch R = 1 ,8594    ,211,176,181
BEGIN DESCRIPTION:
This cross section corresponds to cross section 8594 of the non-georeferenced CDC model which was the source of this model.
END DESCRIPTION:
XS GIS Cut Line= 2
2455212.663425927005817.151179052455214.561059927004197.15212247
#Sta/Elev= 24
    1000     434    1020     430    1090     424    1420     424    1450     428
    1465     430    1510     432    1590     430    1605     428    1650     428
    1720     430    1750     428    1775   426.3    1950     427    2100   426.8
    2340   426.8    2480   426.8    2500     420    2520     418    2525     415
    2540     415    2575     420    2620     428    2640     432
#Mann= 5 ,-1,0
    1000     .09       0    1450     .03       0    2340     .02       0
    2480     .06       0    2575     .08       0
#Block Obstruct= 3 ,-1
    1810    1920     437    1950    2080     437    2110    2340     437
Bank Sta=2480,2620
XS Rating Curve= 0 ,0
Exp/Cntr=0.3,0.1

Type RM Length L Ch R = 1 ,8418    ,131,131,131
BEGIN DESCRIPTION:
This cross section corresponds to cross section 8419 of the non-georeferenced CDC model which was the source of this model.
END DESCRIPTION:
XS GIS Cut Line= 2
2455409.864147017005821.679713292455380.70803735 7004181.9388983
#Sta/Elev= 23
    1000     434    1030     430    1080     428    1240   428.8    1460     428
    1500     430    1640     431    1700     430    1710     428    1730   426.5
    1760     426    1870     426    1910     424    2150     424    2270     426
    2440   426.8    2460     420    2470     415    2495     415    2525     420
    2580     428    2640     430    2690     432
#Mann= 5 ,-1,0
    1000     .04       0    1500     .03       0    2270     .02       0
    2440     .05       0    2580     .09       0
#Block Obstruct= 3 ,-1
    1760    1870     436    1950    2000     436    2070    2270     436
Bank Sta=2440,2580
XS Rating Curve= 0 ,0
Exp/Cntr=0.3,0.1

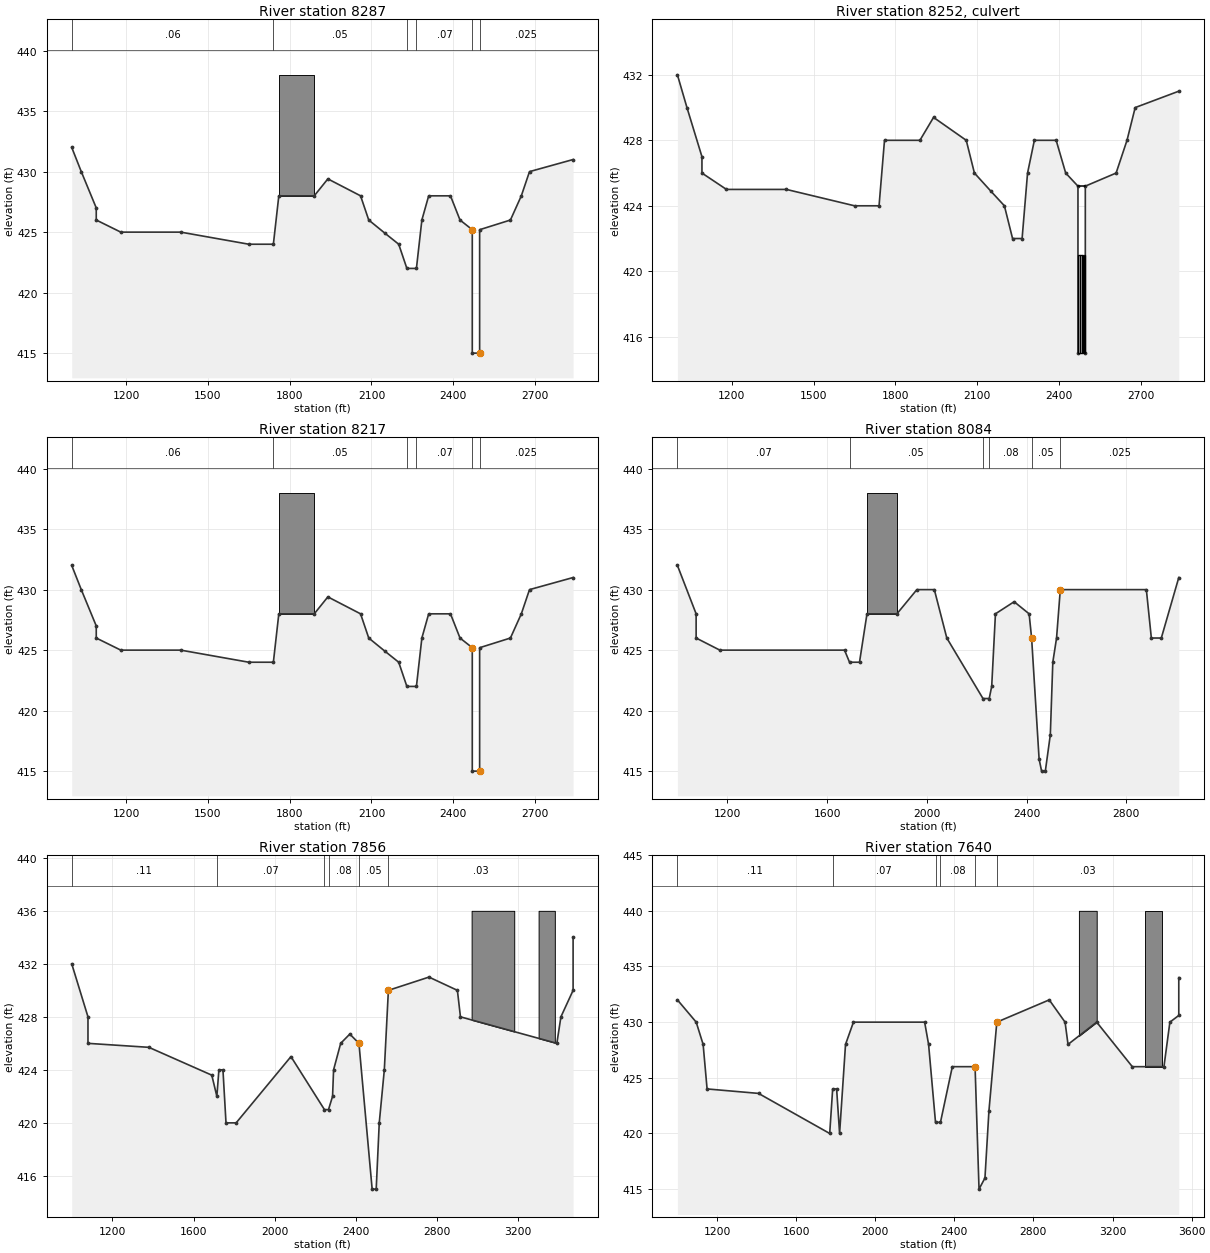
Type RM Length L Ch R = 1 ,8287    ,70,70,70
BEGIN DESCRIPTION:
This cross section corresponds to cross section 8293 of the non-georeferenced CDC model which was the source of this model.
Upstream bounding cross section for the Spangler Road bridge.
END DESCRIPTION:
XS GIS Cut Line= 2
2455546.387167937005818.321124212455509.511257417004138.72605821
#Sta/Elev= 29
    1000     432    1035     430    1090     427    1090     426    1180     425
    1400     425    1650     424    1740     424    1760     428    1890     428
    1940   429.4    2060     428    2090     426    2150   424.9    2200     424
    2230     422    2265     422    2285     426    2310     428    2390     428
    2425     426    2470   425.2    2470     415    2497     415    2497   425.2
    2610     426    2650     428    2680     430    2840     431
#Mann= 6 ,-1,0
    1000     .06       0    1740     .05       0    2230     .02       0
    2265     .07       0    2470     .05       0    2497    .025       0
#Block Obstruct= 1 ,-1
    1760    1890     438
Bank Sta=2470,2497
XS Rating Curve= 0 ,0
Exp/Cntr=0.3,0.1

Type RM Length L Ch R = 2 ,8252    ,,,
BEGIN DESCRIPTION:
Spangler Road
END DESCRIPTION:
Node Name=Spangler Road
Bridge Culvert--1,0,-1,-1, 0
Deck Dist Width WeirC Skew NumUp NumDn MinLoCord MaxHiCord MaxSubmerge Is_Ogee
1,68,2.6,0, 2, 2, , , 0.95, 0, 0,0,,
    2470    2497
   425.2   425.2
    2470    2497
   425.2   425.2
BR Coef=-1 , 0 , 0 ,, 0 ,,,0.8,-1,,0,
WSPro=,,,, 1 ,,,, 0 ,,,, 0 ,,,,-1 ,-1 ,-1 , 0 , 0 , 0 , 0 , 0
Multiple Barrel Culv=2,6,6,68,0.16,0.5,1,10,1,415,415, 4,Culvert #1  , 0 ,1
    2473    2473    2480    2480    2487    2487    2494    2494
BC Culvert Barrel=1,Barrel #1,0
BC Culvert Barrel=2,Barrel #2,0
BC Culvert Barrel=3,Barrel #3,0
BC Culvert Barrel=4,Barrel #4,0
Culvert Bottom n=0.16
BC Design=,, 0 ,, 0 ,,,,,,
BC HTab HWMax=432
BC Use User HTab Curves=0
BC User HTab FreeFlow(D)= 0

Type RM Length L Ch R = 1 ,8217    ,125,133,140
BEGIN DESCRIPTION:
This cross section corresponds to cross section 8217 of the non-georeferenced CDC model which was the source of this model.
Downstream bounding cross section for the Spangler Road bridge.
END DESCRIPTION:
XS GIS Cut Line= 3
2455619.579934927005824.043225632455583.656122277004341.81292239
2455570.661069517004144.90682013
#Sta/Elev= 29
    1000     432    1035     430    1090     427    1090     426    1180     425
    1400     425    1650     424    1740     424    1760     428    1890     428
    1940   429.4    2060     428    2090     426    2150   424.9    2200     424
    2230     422    2265     422    2285     426    2310     428    2390     428
    2425     426    2470   425.2    2470     415    2497     415    2497   425.2
    2610     426    2650     428    2680     430    2840     431
#Mann= 6 ,-1,0
    1000     .06       0    1740     .05       0    2230     .02       0
    2265     .07       0    2470     .05       0    2497    .025       0
#Block Obstruct= 1 ,-1
    1760    1890     438
Bank Sta=2470,2497
XS Rating Curve= 0 ,0
Exp/Cntr=0.3,0.1

Type RM Length L Ch R = 1 ,8084    ,228,228,228
BEGIN DESCRIPTION:
This cross section corresponds to cross section 8084 of the non-georeferenced CDC model which was the source of this model.
END DESCRIPTION:
XS GIS Cut Line= 3
2455729.113508497005804.651532132455713.315967927003937.66215588
  2455614.3637387003873.48118189
#Sta/Elev= 30
    1000     432    1075     428    1075     426    1170     425    1670     425
    1690     424    1730     424    1760     428    1880     428    1960     430
    2030     430    2080     426    2225     421    2250     421    2260     422
    2275     428    2350     429    2410     428    2420     426    2450     416
    2460     415    2475     415    2495     418    2505     424    2520     426
    2535     430    2880     430    2900     426    2940     426    3010     431
#Mann= 6 ,-1,0
    1000     .07       0    1690     .05       0    2225     .02       0
    2250     .08       0    2420     .05       0    2535    .025       0
#Block Obstruct= 1 ,-1
    1760    1880     438
Bank Sta=2420,2535
XS Rating Curve= 0 ,0
Exp/Cntr=0.3,0.1

Type RM Length L Ch R = 1 ,7856    ,216,216,216
BEGIN DESCRIPTION:
This cross section corresponds to cross section 7856 of the non-georeferenced CDC model which was the source of this model.
END DESCRIPTION:
XS GIS Cut Line= 2
2455945.542865667005823.038962542455944.75546569 7003353.0389813
#Sta/Elev= 30
    1000     432    1080     428    1080     426    1380   425.7    1690   423.6
    1715     422    1725     424    1745     424    1760     420    1810     420
    2080     425    2245     421    2265     421    2285     422    2290     424
    2325     426    2370   426.7    2415     426    2480     415    2500     415
    2515     420    2540     424    2560     430    2760     431    2900     430
    2915     428    3390     426    3410     428    3470     430    3470     434
#Mann= 6 ,-1,0
    1000     .11       0    1715     .07       0    2245     .02       0
    2265     .08       0    2415     .05       0    2560     .03       0
#Block Obstruct= 2 ,-1
    2970    3180     436    3300    3380     436
Bank Sta=2415,2560
XS Rating Curve= 0 ,0
Exp/Cntr=0.3,0.1

Type RM Length L Ch R = 1 ,7640    ,298,277,259
BEGIN DESCRIPTION:
This cross section corresponds to cross section 7639 of the non-georeferenced CDC model which was the source of this model.
END DESCRIPTION:
XS GIS Cut Line= 2
2456175.122787097005880.597574472456152.28260967 7003345.7004133
#Sta/Elev= 30
    1000     432    1095     430    1130     428    1150     424    1410   423.6
    1770     420    1785     424    1805     424    1820     420    1850     428
    1890     430    2250     430    2270     428    2305     421    2330     421
    2390     426    2505     426    2525     415    2555     416    2575     422
    2615     430    2880     432    2960     430    2975     428    3120     430
    3300     426    3460     426    3490     430    3535   430.6    3535     434
#Mann= 6 ,-1,0
    1000     .11       0    1785     .07       0    2305     .02       0
    2330     .08       0    2505     .05       0    2615     .03       0
#Block Obstruct= 2 ,-1
    3030    3120     440    3365    3450     440
Bank Sta=2505,2615
XS Rating Curve= 0 ,0
Exp/Cntr=0.3,0.1

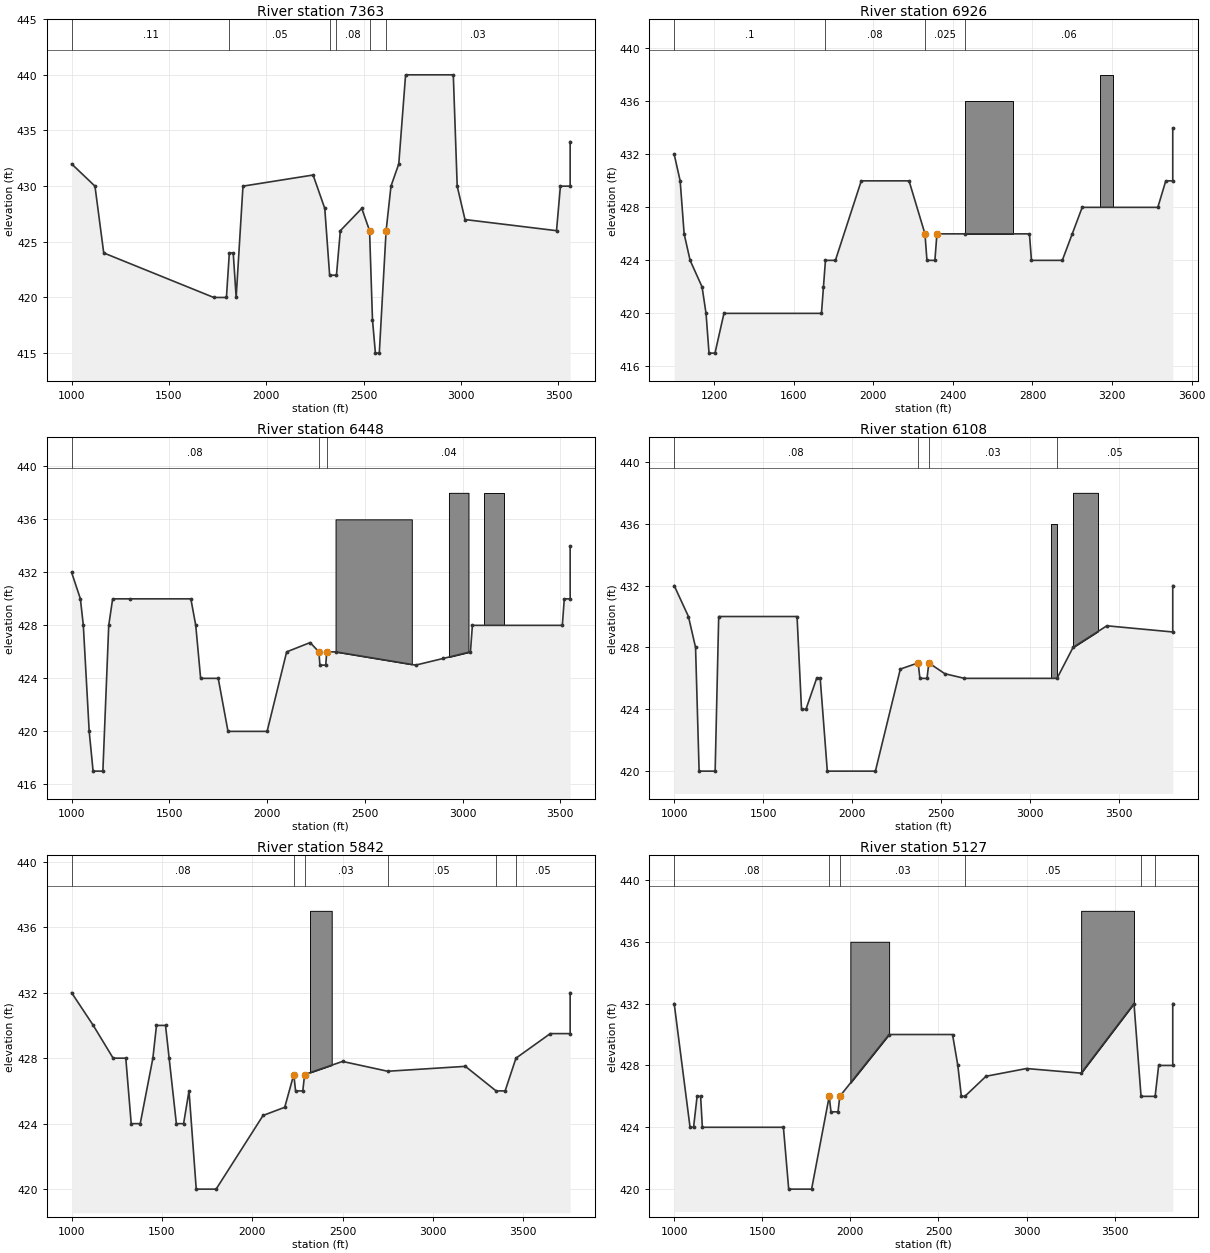
Type RM Length L Ch R = 1 ,7363    ,452,437,311
BEGIN DESCRIPTION:
This cross section corresponds to cross section 7360 of the non-georeferenced CDC model which was the source of this model.
END DESCRIPTION:
XS GIS Cut Line= 2
2456505.616876757005908.161167642456396.289995677003350.49666356
#Sta/Elev= 30
    1000     432    1120     430    1165     424    1730     420    1795     420
    1810     424    1830     424    1845     420    1880     430    2240     431
    2300     428    2325     422    2360     422    2380     426    2490     428
    2530     426    2545     418    2560     415    2580     415    2615     426
    2640     430    2680     432    2715     440    2960     440    2980     430
    3020     427    3490     426    3510     430    3560     430    3560     434
#Mann= 6 ,-1,0
    1000     .11       0    1810     .05       0    2325     .02       0
    2360     .08       0    2530     .05       0    2615     .03       0
Bank Sta=2530,2615
XS Rating Curve= 0 ,0
Exp/Cntr=0.3,0.1

Type RM Length L Ch R = 1 ,6926    ,561,478,350
BEGIN DESCRIPTION:
This cross section corresponds to cross section 6925 of the non-georeferenced CDC model which was the source of this model.
END DESCRIPTION:
XS GIS Cut Line= 2
2457025.548579667005791.406479882456630.352847767003317.77658464
#Sta/Elev= 29
    1000     432    1030     430    1050     426    1080     424    1140     422
    1160     420    1175     417    1205     417    1250     420    1740     420
    1750     422    1760     424    1810     424    1940     430    2180     430
    2260     426    2270     424    2310     424    2320     426    2460     426
    2785     426    2795     424    2950     424    3000     426    3050     428
    3430     428    3470     430    3505     430    3505     434
#Mann= 4 ,-1,0
    1000      .1       0    1760     .08       0    2260    .025       0
    2460     .06       0
#Block Obstruct= 2 ,-1
    2460    2700     436    3140    3205     438
Bank Sta=2260,2320
XS Rating Curve= 0 ,0
Exp/Cntr=0.3,0.1

Type RM Length L Ch R = 1 ,6448    ,400,340,250
BEGIN DESCRIPTION:
This cross section corresponds to cross section 6448 of the non-georeferenced CDC model which was the source of this model.
END DESCRIPTION:
XS GIS Cut Line= 2
2457697.747038427005798.583958972456877.258521917003384.18983763
#Sta/Elev= 30
    1000     432    1045     430    1060     428    1090     420    1110     417
    1160     417    1190     428    1210     430    1300     430    1610     430
    1635     428    1660     424    1750     424    1800     420    2000     420
    2100     426    2220   426.7    2265     426    2270     425    2300     425
    2305     426    2350     426    2760     425    2900   425.5    3040     426
    3050     428    3510     428    3520     430    3550     430    3550     434
#Mann= 3 ,-1,0
    1000     .08       0    2265     .02       0    2305     .04       0
#Block Obstruct= 3 ,-1
    2350    2740     436    2930    3030     438    3110    3210     438
Bank Sta=2265,2305
XS Rating Curve= 0 ,0
Exp/Cntr=0.3,0.1

Type RM Length L Ch R = 1 ,6108    ,289,266,190
BEGIN DESCRIPTION:
This cross section corresponds to cross section 6108 of the non-georeferenced CDC model which was the source of this model.
END DESCRIPTION:
XS GIS Cut Line= 2
2458228.105885837005844.132096222457018.314670267003318.97769772
#Sta/Elev= 25
    1000     432    1080     430    1120     428    1140     420    1230     420
    1250     430    1690     430    1715     424    1740     424    1800     426
    1820     426    1860     420    2130     420    2270   426.6    2370     427
    2380     426    2420     426    2430     427    2520   426.3    2630     426
    3150     426    3240     428    3430   429.4    3800     429    3800     432
#Mann= 4 ,-1,0
    1000     .08       0    2370     .02       0    2430     .03       0
    3150     .05       0
#Block Obstruct= 2 ,-1
    3115    3150     436    3240    3380     438
Bank Sta=2370,2430
XS Rating Curve= 0 ,0
Exp/Cntr=0.3,0.1

Type RM Length L Ch R = 1 ,5842    ,751,715,400
BEGIN DESCRIPTION:
This cross section corresponds to cross section 5841 of the non-georeferenced CDC model which was the source of this model.
END DESCRIPTION:
XS GIS Cut Line= 3
2458772.544101427005332.150180552458276.446996517005232.09395021
2457119.936186167003297.51153331
#Sta/Elev= 30
    1000     432    1120     430    1230     428    1300     428    1330     424
    1380     424    1450     428    1470     430    1520     430    1540     428
    1580     424    1620     424    1650     426    1690     420    1800     420
    2060   424.5    2180     425    2230     427    2240     426    2280     426
    2290     427    2500   427.8    2750   427.2    3180   427.5    3350     426
    3400     426    3460     428    3650   429.5    3760   429.5    3760     432
#Mann= 6 ,-1,0
    1000     .08       0    2230     .02       0    2290     .03       0
    2750     .05       0    3350     .02       0    3460     .05       0
#Block Obstruct= 1 ,-1
    2320    2440     437
Bank Sta=2230,2290
XS Rating Curve= 0 ,0
Exp/Cntr=0.3,0.1

Type RM Length L Ch R = 1 ,5127    ,440,450,240
BEGIN DESCRIPTION:
This cross section corresponds to cross section 5127 of the non-georeferenced CDC model which was the source of this model.
END DESCRIPTION:
XS GIS Cut Line= 2
2459271.896777247005197.728205292457195.246403017003275.11951771
#Sta/Elev= 27
    1000     432    1090     424    1110     424    1130     426    1150     426
    1160     424    1620     424    1650     420    1780     420    1880     426
    1890     425    1930     425    1940     426    2220     430    2580     430
    2610     428    2630     426    2650     426    2770   427.3    3000   427.8
    3310   427.5    3610     432    3650     426    3730     426    3750     428
    3830     428    3830     432
#Mann= 6 ,-1,0
    1000     .08       0    1880    .025       0    1940     .03       0
    2650     .05       0    3650     .02       0    3730     .04       0
#Block Obstruct= 2 ,-1
    2000    2220     436    3310    3610     438
Bank Sta=1880,1940
XS Rating Curve= 0 ,0
Exp/Cntr=0.3,0.1

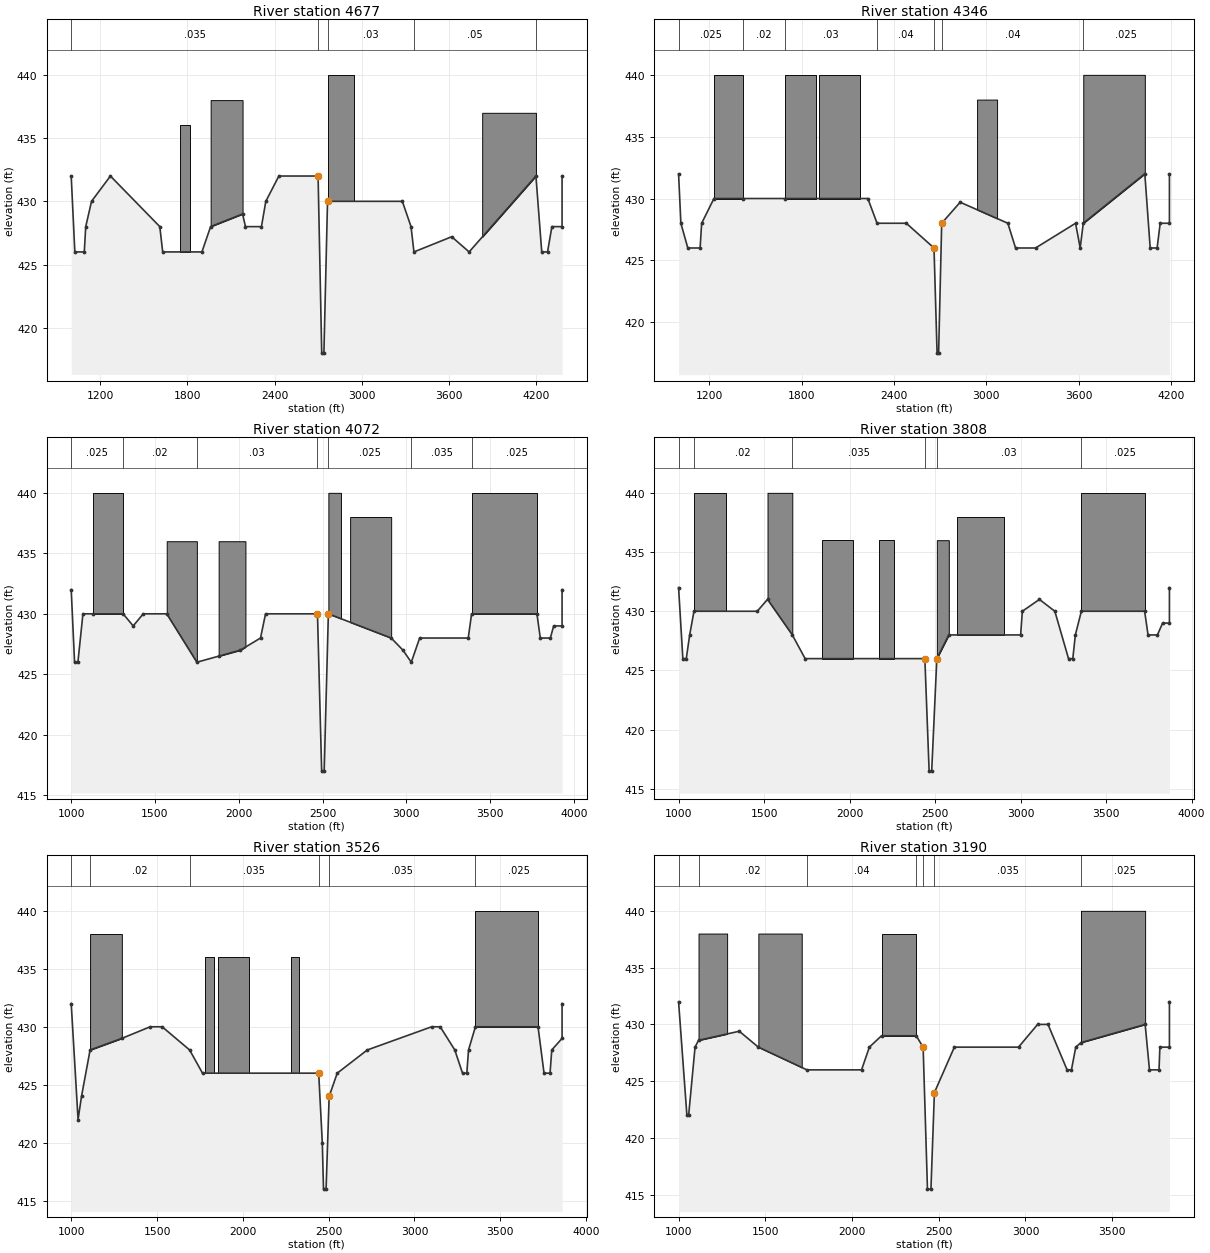
Type RM Length L Ch R = 1 ,4677    ,349,331,190
BEGIN DESCRIPTION:
This cross section corresponds to cross section 4677 of the non-georeferenced CDC model which was the source of this model.
END DESCRIPTION:
XS GIS Cut Line= 5
2460132.002668597004910.78324114 2459424.57888667004682.24006306
2458600.146152267004123.669001712457523.919958267003389.42998463
2457203.595467697003281.85014731
#Sta/Elev= 30
    1000     432    1025     426    1090     426    1100     428    1140     430
    1270     432    1610     428    1630     426    1900     426    1960     428
    2180     429    2200     428    2310     428    2340     430    2430     432
    2700     432    2725     418    2740     418    2765     430    3280     430
    3340     428    3360     426    3620   427.2    3740     426    4200     432
    4240     426    4280     426    4310     428    4380     428    4380     432
#Mann= 5 ,-1,0
    1000    .035       0    2700    .025       0    2765     .03       0
    3360     .05       0    4200    .025       0
#Block Obstruct= 4 ,-1
    1750    1820     436    1960    2180     438    2765    2950     440
    3830    4200     437
Bank Sta=2700,2765
XS Rating Curve= 0 ,0
Exp/Cntr=0.3,0.1

Type RM Length L Ch R = 1 ,4346    ,330,274,170
BEGIN DESCRIPTION:
This cross section corresponds to cross section 4345 of the non-georeferenced CDC model which was the source of this model.
END DESCRIPTION:
XS GIS Cut Line= 4
2460121.269094267004527.358483052458599.089067767003790.60995655
2457748.655073087003384.786949312457210.331674677003243.34070988
#Sta/Elev= 28
    1000     432    1015     428    1060     426    1140     426    1150     428
    1230     430    1420     430    1690     430    2230     430    2290     428
    2480     428    2660     426    2680   417.5    2690   417.5    2710     428
    2830   429.7    3140     428    3190     426    3320     426    3580     428
    3610     426    3630     428    4030     432    4065     426    4110     426
    4130     428    4190     428    4190     432
#Mann= 7 ,-1,0
    1000    .025       0    1420     .02       0    1690     .03       0
    2290     .04       0    2660    .025       0    2710     .04       0
    3630    .025       0
#Block Obstruct= 5 ,-1
    1230    1420     440    1690    1890     440    1915    2180     440
    2940    3070     438    3630    4030     440
Bank Sta=2660,2710
XS Rating Curve= 0 ,0
Exp/Cntr=0.3,0.1

Type RM Length L Ch R = 1 ,4072    ,338,264,189
BEGIN DESCRIPTION:
This cross section corresponds to cross section 4071 of the non-georeferenced CDC model which was the source of this model.
END DESCRIPTION:
XS GIS Cut Line= 3
 2460052.31582017003932.686444042457750.880134257003277.21597022
2457224.037683997003173.04819955
#Sta/Elev= 30
    1000     432    1020     426    1040     426    1070     430    1130     430
    1310     430    1370     429    1430     430    1570     430    1750     426
    1880   426.5    2010     427    2130     428    2160     430    2470     430
    2495     417    2510     417    2535     430    2910     428    2980     427
    3030     426    3080     428    3370     428    3390     430    3780     430
    3800     428    3860     428    3880     429    3930     429    3930     432
#Mann= 7 ,-1,0
    1000    .025       0    1310     .02       0    1750     .03       0
    2470    .025       0    2535    .025       0    3030    .035       0
    3390    .025       0
#Block Obstruct= 6 ,-1
    1130    1310     440    1570    1750     436    1880    2040     436
    2535    2610     440    2665    2910     438    3390    3780     440
Bank Sta=2470,2535
XS Rating Curve= 0 ,0
Exp/Cntr=0.3,0.1

Type RM Length L Ch R = 1 ,3808    ,371,282,221
BEGIN DESCRIPTION:
This cross section corresponds to cross section 3806 of the non-georeferenced CDC model which was the source of this model.
END DESCRIPTION:
XS GIS Cut Line= 3
2460060.824005197003478.478034882457730.219086357003124.53222047
2457219.985526747003074.59760904
#Sta/Elev= 28
    1000     432    1025     426    1045     426    1065     428    1090     430
    1460     430    1520     431    1665     428    1740     426    2440     426
    2465   416.5    2480   416.5    2510     426    2580     428    3000     428
    3010     430    3110     431    3200     430    3280     426    3305     426
    3320     428    3355     430    3725     430    3745     428    3800     428
    3830     429    3870     429    3870     432
#Mann= 6 ,-1,0
    1000    .025       0    1090     .02       0    1665    .035       0
    2440    .025       0    2510     .03       0    3355    .025       0
#Block Obstruct= 7 ,-1
    1090    1280     440    1520    1665     440    1840    2020     436
    2170    2260     436    2510    2580     436    2630    2900     438
    3355    3725     440
Bank Sta=2440,2510
XS Rating Curve= 0 ,0
Exp/Cntr=0.3,0.1

Type RM Length L Ch R = 1 ,3526    ,339,336,324
BEGIN DESCRIPTION:
This cross section corresponds to cross section 3525 of the non-georeferenced CDC model which was the source of this model.
END DESCRIPTION:
XS GIS Cut Line= 3
 2460081.37284867003017.559009212458610.531958257002975.42195438
2457222.637424357002932.57394296
#Sta/Elev= 29
    1000     432    1040     422    1060     424    1110     428    1295     429
    1460     430    1530     430    1690     428    1765     426    2442     426
    2463     420    2470     416    2485     416    2503     424    2550     426
    2725     428    3100     430    3150     430    3235     428    3280     426
    3305     426    3315     428    3355     430    3720     430    3755     426
    3790     426    3800     428    3860     429    3860     432
#Mann= 6 ,-1,0
    1000    .025       0    1110     .02       0    1690    .035       0
    2442    .025       0    2503    .035       0    3355    .025       0
#Block Obstruct= 5 ,-1
    1110    1295     438    1780    1830     436    2280    2330     436
    3355    3720     440    1855    2035     436
Bank Sta=2442,2503
XS Rating Curve= 0 ,0
Exp/Cntr=0.3,0.1

Type RM Length L Ch R = 1 ,3190    ,291,283,271
BEGIN DESCRIPTION:
This cross section corresponds to cross section 3188 of the non-georeferenced CDC model which was the source of this model.
END DESCRIPTION:
XS GIS Cut Line= 3
2460056.792845257002668.427817722458681.387131517002640.37898929
2457227.311955667002614.34032747
#Sta/Elev= 30
    1000     432    1048     422    1058     422    1095     428    1115   428.6
    1350   429.4    1460     428    1740     426    2055     426    2100     428
    2170     429    2370     429    2410     428    2435   415.5    2455   415.5
    2475     424    2590     428    2960     428    3070     430    3130     430
    3240     426    3265     426    3290     428    3320   428.4    3690     430
    3715     426    3770     426    3775     428    3830     428    3830     432
#Mann= 7 ,-1,0
    1000    .025       0    1115     .02       0    1740     .04       0
    2370     .03       0    2410    .025       0    2475    .035       0
    3320    .025       0
#Block Obstruct= 4 ,-1
    1115    1280     438    1460    1710     438    2170    2370     438
    3320    3690     440
Bank Sta=2410,2475
XS Rating Curve= 0 ,0
Exp/Cntr=0.3,0.1

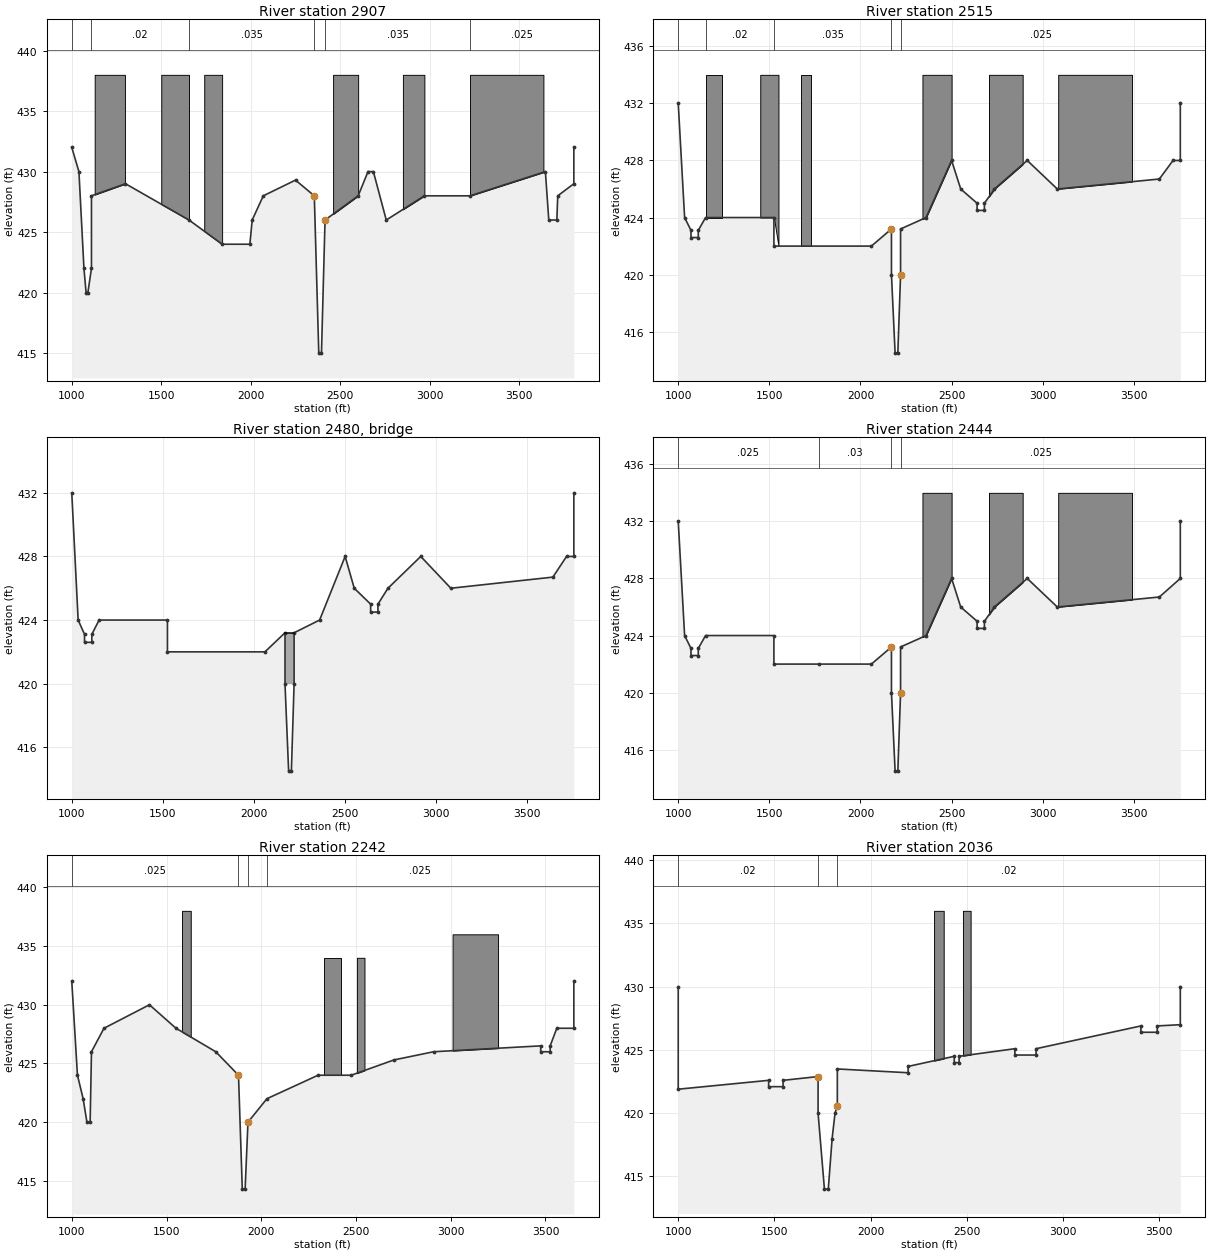
Type RM Length L Ch R = 1 ,2907    ,370,392,330
BEGIN DESCRIPTION:
This cross section corresponds to cross section 2906 of the non-georeferenced CDC model which was the source of this model.
END DESCRIPTION:
XS GIS Cut Line= 2
2459994.546906777002351.267034712457189.563999687002361.02587347
#Sta/Elev= 30
    1000     432    1040     430    1068     422    1080     420    1090     420
    1110     422    1110     428    1300     429    1655     426    1840     424
    1995     424    2008     426    2070     428    2250   429.3    2355     428
    2380     415    2395     415    2415     426    2600     428    2655     430
    2685     430    2757     426    2970     428    3225     428    3646     430
    3665     426    3710     426    3715     428    3805     429    3805     432
#Mann= 6 ,-1,0
    1000    .025       0    1110     .02       0    1655    .035       0
    2355    .025       0    2415    .035       0    3225    .025       0
#Block Obstruct= 6 ,-1
    1128    1297     438    1500    1655     438    1740    1840     438
    2460    2600     438    2850    2970     438    3225    3635     438
Bank Sta=2355,2415
XS Rating Curve= 0 ,0
Exp/Cntr=0.3,0.1

Type RM Length L Ch R = 1 ,2515    ,71,71,71
BEGIN DESCRIPTION:
This cross section corresponds to cross section 2514 of the non-georeferenced CDC model which was the source of this model.
Upstream bounding cross section for Lombardy Lane bridge.
END DESCRIPTION:
XS GIS Cut Line= 4
2459850.826393667001987.409166632458632.215970017001973.51713406
  2457152.7228667002317.915723472457135.911219847002321.82910147
#Sta/Elev= 30
    1000     432    1035     424    1070   423.1    1070   422.6    1110   422.6
    1110   423.1    1150     424    1525     424    1525     422    2060     422
    2170   423.2    2170     420    2190   414.5    2205   414.5    2220     420
    2220   423.2    2360     424    2500     428    2550     426    2640     425
    2640   424.5    2680   424.5    2680     425    2735     426    2915     428
    3080     426    3640   426.7    3715     428    3755     428    3755     432
#Mann= 5 ,-1,0
    1000    .025       0    1150     .02       0    1525    .035       0
    2170    .025       0    2220    .025       0
#Block Obstruct= 6 ,-1
    2340    2500     434    2705    2890     434    3085    3490     434
    1150    1240     434    1450    1550     434    1675    1730     434
Bank Sta=2170,2220
XS Rating Curve= 0 ,0
Exp/Cntr=0.3,0.1

Type RM Length L Ch R = 3 ,2480    ,,,
BEGIN DESCRIPTION:
Lombardy Lane
END DESCRIPTION:
Node Name=Lombardy Lane
Bridge Culvert--1,0,-1,-1, 0
Deck Dist Width WeirC Skew NumUp NumDn MinLoCord MaxHiCord MaxSubmerge Is_Ogee
1,69,2.6,0, 2, 2, , , 0.95, 0, 0,0,,
    2170    2220
   423.2   423.2
     420     420
    2170    2220
   423.2   423.2
     420     420
BR Coef=-1 , 0 , 0 ,, 0 ,,,0.8,-1,,0,
WSPro=,,,, 1 ,,,, 0 ,,,, 0 ,,,,-1 ,-1 ,-1 , 0 , 0 , 0 , 0 , 0
BC Design=,, 0 ,, 0 ,,,,,,
BC HTab HWMax=432
BC Use User HTab Curves=0
BC User HTab FreeFlow(D)= 0

Type RM Length L Ch R = 1 ,2444    ,239,202,140
BEGIN DESCRIPTION:
This cross section corresponds to cross section 2243 of the non-georeferenced CDC model which was the source of this model.
Downstream bounding cross section for Lombardy Lane bridge.
END DESCRIPTION:
XS GIS Cut Line= 5
2459889.651119177001926.708172542458668.732957337001912.19704671
2458166.184749847002033.626265792458166.170642267002033.62889047
2457177.647684937002272.48438388
#Sta/Elev= 30
    1000     432    1035     424    1070   423.1    1070   422.6    1110   422.6
    1110   423.1    1150     424    1525     424    1525     422    1770     422
    2060     422    2170   423.2    2170     420    2190   414.5    2205   414.5
    2220     420    2220   423.2    2360     424    2500     428    2550     426
    2640     425    2640   424.5    2680   424.5    2680     425    2735     426
    2915     428    3080     426    3640   426.7    3755     428    3755     432
#Mann= 4 ,-1,0
    1000    .025       0    1770     .03       0    2170    .035       0
    2220    .025       0
#Block Obstruct= 3 ,-1
    2340    2500     434    2705    2890     434    3085    3490     434
Bank Sta=2170,2220
XS Rating Curve= 0 ,0
Exp/Cntr=0.3,0.1

Type RM Length L Ch R = 1 ,2242    ,210,206,120
BEGIN DESCRIPTION:
This cross section corresponds to cross section 2241 of the non-georeferenced CDC model which was the source of this model.
END DESCRIPTION:
XS GIS Cut Line= 5
2459736.78397083 7001594.50903382458410.805979767001831.38421622
2458247.243970937001876.353942542457711.441892927002016.01868947
2457150.49288359 7002162.2382133
#Sta/Elev= 26
    1000     432    1030     424    1060     422    1080     420    1097     420
    1104     426    1170     428    1410     430    1550     428    1760     426
    1880     424    1900   414.3    1915   414.3    1930     420    2030     422
    2300     424    2475     424    2700   425.3    2910     426    3475   426.5
    3475     426    3525     426    3525   426.5    3560     428    3650     428
    3650     432
#Mann= 4 ,-1,0
    1000    .025       0    1880     .04       0    1930     .07       0
    2030    .025       0
#Block Obstruct= 4 ,-1
    1582    1628     438    2330    2420     434    2505    2545     434
    3010    3250     436
Bank Sta=1880,1930
XS Rating Curve= 0 ,0
Exp/Cntr=0.3,0.1

Type RM Length L Ch R = 1 ,2036    ,100,100,100
BEGIN DESCRIPTION:
This cross section corresponds to cross section 2035 of the non-georeferenced CDC model which was the source of this model.
Upstream bounding cross section for SH 348/Northwest Highway bridge.
END DESCRIPTION:
XS GIS Cut Line= 6
2459627.049938357001305.04307731 2459145.04007567001483.89606605
 2459002.6738905 7001533.13317232458456.552935517001741.61208604
2458229.431998677001822.451163222457146.04833868 7002104.7540763
#Sta/Elev= 30
    1000     430    1000   421.9    1470   422.6    1470   422.1    1545   422.1
    1545   422.6    1727   422.9    1727     420    1760     414    1780     414
    1800     418    1815     420    1827   420.6    1827   423.5    2195   423.2
    2195   423.7    2435   424.5    2435     424    2460     424    2460   424.5
    2750   425.1    2750   424.6    2860   424.6    2860   425.1    3405   426.9
    3405   426.4    3490   426.4    3490   426.9    3610     427    3610     430
#Mann= 3 ,-1,0
    1000     .02       0    1727     .03       0    1827     .02       0
#Block Obstruct= 2 ,-1
    2330    2380     436    2480    2520     436
Bank Sta=1727,1827
XS Rating Curve= 0 ,0
Exp/Cntr=0.3,0.1