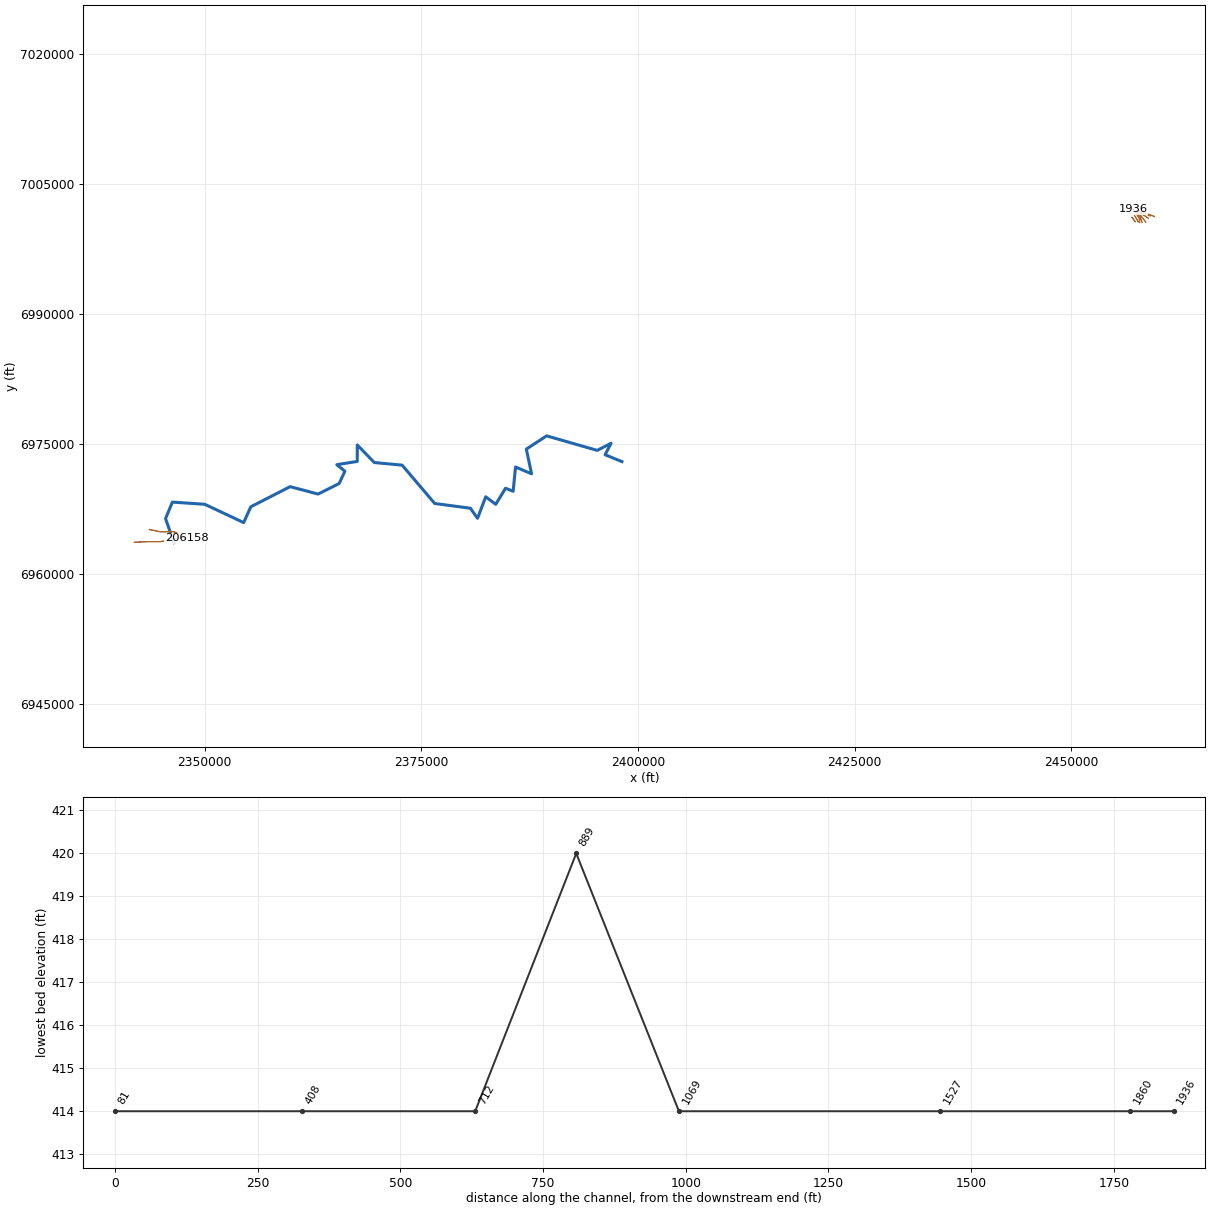
HEC-RAS study CDC_Consolidated_Model.prj: Upper Trinity CDC Consolidated Model

--- CDC_Consolidated_Model.g01 (geometry) --- (continued)

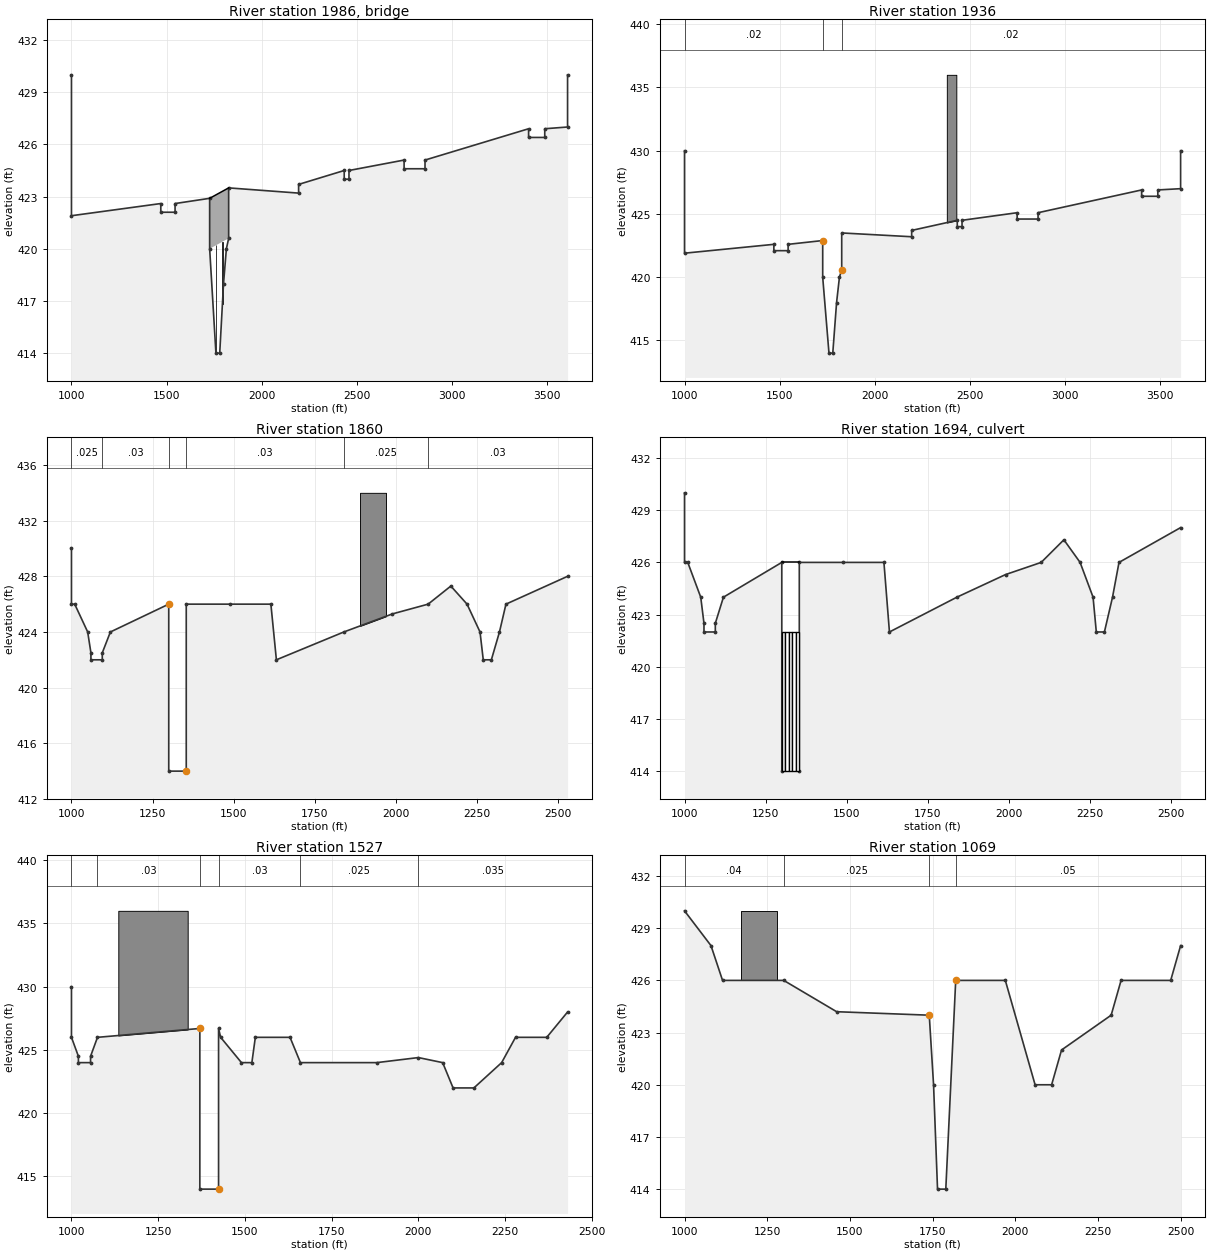
Type RM Length L Ch R = 3 ,1986    ,,,
BEGIN DESCRIPTION:
State Highway 348/Northwest Highway
END DESCRIPTION:
Node Name=Northwest Highwa
Bridge Culvert--1,0,-1,-1, 0
Deck Dist Width WeirC Skew NumUp NumDn MinLoCord MaxHiCord MaxSubmerge Is_Ogee
2,96,2.6,0, 2, 2, , , 0.95, 0, 0,0,,
    1727    1827
   422.9   423.5
     420   420.6
    1727    1827
   422.9   423.5
     420   420.6
Pier Skew, UpSta & Num, DnSta & Num=  ,1760, 2 ,1760, 2 , 0 , 0 , 0 ,,
       2       2
     400     422
       2       2
     400     422
Pier Skew, UpSta & Num, DnSta & Num=  ,1794, 2 ,1794, 2 , 0 , 0 , 0 ,,
       2       2
     400     422
       2       2
     400     422
BR Coef=-1 , 0 , 0 ,, 0 ,,,0.8,-1,,0,
WSPro=,,,, 1 ,,,, 0 ,,,, 0 ,,,,-1 ,-1 ,-1 , 0 , 0 , 0 , 0 , 0
BC Design=,, 0 ,, 0 ,,,,,,
BC HTab HWMax=430
BC Use User HTab Curves=0
BC User HTab FreeFlow(D)= 0

Type RM Length L Ch R = 1 ,1936    ,76,76,76
BEGIN DESCRIPTION:
This cross section corresponds to cross section 1936 of the non-georeferenced CDC model which was the source of this model.
Downstream bounding cross section for SH 348/Northwest Highway bridge.
END DESCRIPTION:
XS GIS Cut Line= 6
2459590.126127667001210.093135972459106.108066837001389.72597881
2458490.092894677001624.34821297 2458202.66007067001735.66196671
 2457663.98595117001939.199945462457128.039188337002064.76170221
#Sta/Elev= 30
    1000     430    1000   421.9    1470   422.6    1470   422.1    1545   422.1
    1545   422.6    1727   422.9    1727     420    1760     414    1780     414
    1800     418    1815     420    1827   420.6    1827   423.5    2195   423.2
    2195   423.7    2435   424.5    2435     424    2460     424    2460   424.5
    2750   425.1    2750   424.6    2860   424.6    2860   425.1    3405   426.9
    3405   426.4    3490   426.4    3490   426.9    3610     427    3610     430
#Mann= 3 ,-1,0
    1000     .02       0    1727     .03       0    1827     .02       0
#Block Obstruct= 1 ,-1
    2380    2430     436
Bank Sta=1727,1827
XS Rating Curve= 0 ,0
Exp/Cntr=0.3,0.1

Type RM Length L Ch R = 1 ,1860    ,331,333,220
BEGIN DESCRIPTION:
This cross section corresponds to cross section 1859 of the non-georeferenced CDC model which was the source of this model.
Upstream end of 5 cell box culvert (8'W x 10'H )
END DESCRIPTION:
XS GIS Cut Line= 3
2459109.734043847001282.172060042458792.49583316 7001441.2081593
2457854.378286847001741.46969788
#Sta/Elev= 27
    1000     430    1000     426    1010     426    1050     424    1060   422.5
    1060     422    1095     422    1095   422.5    1120     424    1300     426
    1300     414    1354     414    1354     426    1490     426    1615     426
    1632     422    1840     424    1990   425.3    2100     426    2170   427.3
    2220     426    2260     424    2270     422    2295     422    2320     424
    2340     426    2530     428
#Mann= 6 ,-1,0
    1000    .025       0    1095     .03       0    1300    .025       0
    1354     .03       0    1840    .025       0    2100     .03       0
#Block Obstruct= 1 ,-1
    1890    1970     434
Bank Sta=1300,1354
XS Rating Curve= 0 ,0
Exp/Cntr=0.3,0.1

Type RM Length L Ch R = 2 ,1694    ,,,
BEGIN DESCRIPTION:
5 cell concrete box culvert (5-8'hx10'w )
END DESCRIPTION:
Node Name=culvert
Bridge Culvert--1,0,-1,-1, 0
Deck Dist Width WeirC Skew NumUp NumDn MinLoCord MaxHiCord MaxSubmerge Is_Ogee
1,330,2.6,0, 2, 2, , , 0.95, 0, 0,0,,
    1300    1354
     426     426
    1370    1424
   426.7   426.7
Multiple Barrel Culv=2,8,10,328,0.016,0.5,1,11,3,414,414, 5,Culvert #1  , 0 ,1
    1305    1375    1316    1386    1327    1397    1338    1408    1349    1419
BC Culvert Barrel=1,Barrel #1,0
BC Culvert Barrel=2,Barrel #2,0
BC Culvert Barrel=3,Barrel #3,0
BC Culvert Barrel=4,Barrel #4,0
BC Culvert Barrel=5,Barrel #5,0
Culvert Bottom n=0.016
BC Design=,, 0 ,, 0 ,,,,,,
BC HTab HWMax=430
BC Use User HTab Curves=0
BC User HTab FreeFlow(D)= 0

Type RM Length L Ch R = 1 ,1527    ,400,458,300
BEGIN DESCRIPTION:
This cross section corresponds to cross section 1510 of the non-georeferenced CDC model which was the source of this model.
Downstream end of 5 cell box culvert (8'H x 10'W)
END DESCRIPTION:
XS GIS Cut Line= 3
2458889.712830337001010.939006722458541.642988417001247.25021388
2457716.17022991 7001716.0245388
#Sta/Elev= 26
    1000     430    1000     426    1020   424.5    1020     424    1055     424
    1055   424.5    1075     426    1370   426.7    1370     414    1424     414
    1424   426.7    1430     426    1490     424    1520     424    1530     426
    1630     426    1660     424    1880     424    2000   424.4    2070     424
    2100     422    2160     422    2240     424    2280     426    2370     426
    2430     428
#Mann= 6 ,-1,0
    1000    .025       0    1075     .03       0    1370     .02       0
    1424     .03       0    1660    .025       0    2000    .035       0
#Block Obstruct= 1 ,-1
    1135    1335     436
Bank Sta=1370,1424
XS Rating Curve= 0 ,0
Exp/Cntr=0.3,0.1

Type RM Length L Ch R = 1 ,1069    ,260,180,110
BEGIN DESCRIPTION:
This cross section corresponds to cross section 1069 of the non-georeferenced CDC model which was the source of this model.
END DESCRIPTION:
XS GIS Cut Line= 2
2458594.765913677000559.849029632457690.085636447001718.49205355
#Sta/Elev= 18
    1000     430    1080     428    1115     426    1300     426    1460   424.2
    1740     424    1753     420    1765     414    1790     414    1820     426
    1970     426    2060     420    2110     420    2140     422    2290     424
    2320     426    2470     426    2500     428
#Mann= 4 ,-1,0
    1000     .04       0    1300    .025       0    1740     .04       0
    1820     .05       0
#Block Obstruct= 1 ,-1
    1170    1280     430
Bank Sta=1740,1820
XS Rating Curve= 0 ,0
Exp/Cntr=0.3,0.1

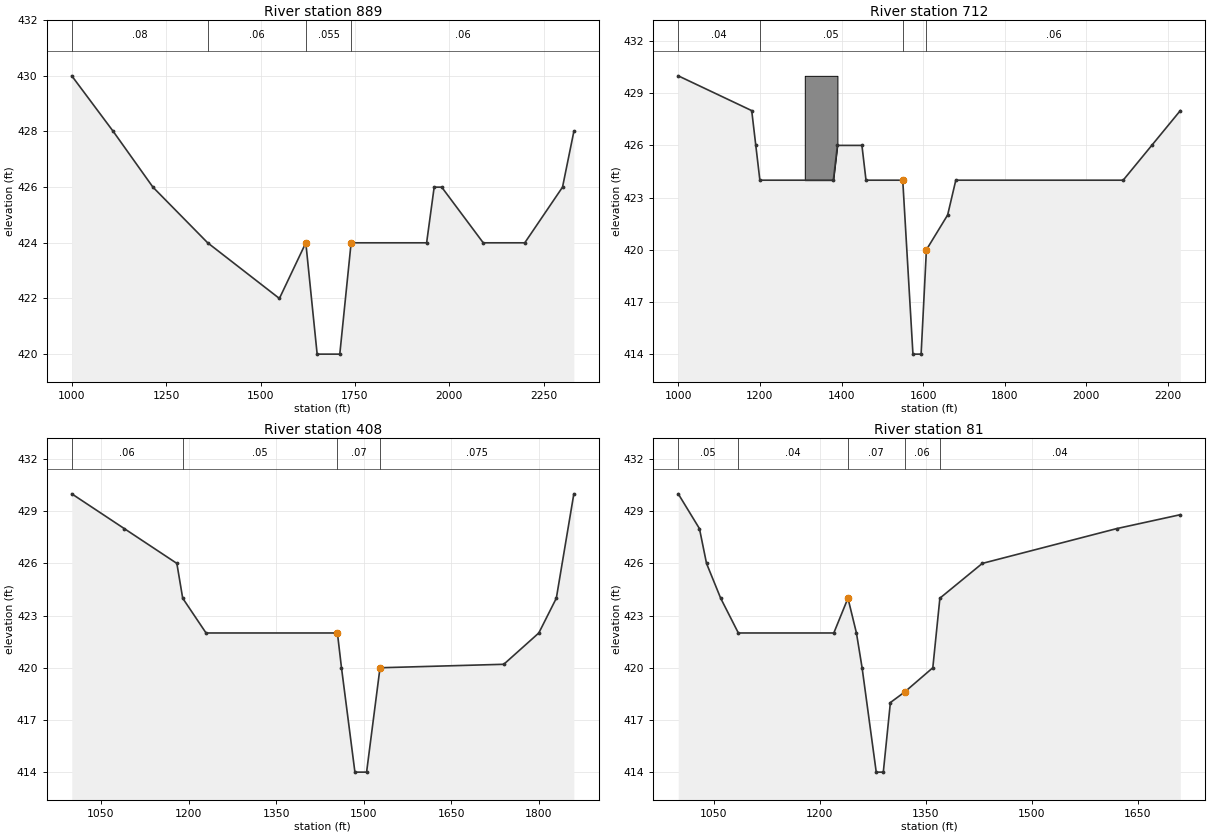
Type RM Length L Ch R = 1 ,889     ,177,177,177
BEGIN DESCRIPTION:
This cross section corresponds to cross section 889 of the non-georeferenced CDC model which was the source of this model.
END DESCRIPTION:
XS GIS Cut Line= 3
2458161.806149667000531.314965962457929.777086177001175.21918997
  2457618.6904387001706.39365254
#Sta/Elev= 16
    1000     430    1110     428    1215     426    1360     424    1550     422
    1620     424    1650     420    1710     420    1740     424    1940     424
    1960     426    1980     426    2090     424    2200     424    2300     426
    2330     428
#Mann= 4 ,-1,0
    1000     .08       0    1360     .06       0    1620    .055       0
    1740     .06       0
Bank Sta=1620,1740
XS Rating Curve= 0 ,0
Exp/Cntr=0.3,0.1

Type RM Length L Ch R = 1 ,712     ,280,304,290
BEGIN DESCRIPTION:
This cross section corresponds to cross section 712 of the non-georeferenced CDC model which was the source of this model.
END DESCRIPTION:
XS GIS Cut Line= 3
2457885.36411726 7000567.13707282457838.728055697001008.64898504
2457457.022454267001614.45650047
#Sta/Elev= 17
    1000     430    1180     428    1190     426    1200     424    1380     424
    1390     426    1450     426    1460     424    1550     424    1575     414
    1595     414    1608     420    1660     422    1680     424    2090     424
    2160     426    2230     428
#Mann= 4 ,-1,0
    1000     .04       0    1200     .05       0    1550    .065       0
    1608     .06       0
#Block Obstruct= 1 ,-1
    1310    1390     430
Bank Sta=1550,1608
XS Rating Curve= 0 ,0
Exp/Cntr=0.3,0.1

Type RM Length L Ch R = 1 ,408     ,300,327,350
BEGIN DESCRIPTION:
This cross section corresponds to cross section 408 of the non-georeferenced CDC model which was the source of this model.
END DESCRIPTION:
XS GIS Cut Line= 2
2457724.418901097000584.181986212457317.52076477 7001307.6001588
#Sta/Elev= 14
    1000     430    1090     428    1180     426    1190     424    1230     422
    1455     422    1462     420    1485     414    1505     414    1528     420
    1740   420.2    1800     422    1830     424    1860     430
#Mann= 4 ,-1,0
    1000     .06       0    1190     .05       0    1455     .07       0
    1528    .075       0
Bank Sta=1455,1528
XS Rating Curve= 0 ,0
Exp/Cntr=0.3,0.1

Type RM Length L Ch R = 1 ,81      ,0,0,0
BEGIN DESCRIPTION:
This cross section corresponds to cross section 81 of the non-georeferenced CDC model which was the source of this model.
END DESCRIPTION:
XS GIS Cut Line= 2
2457383.519976597000616.041174472457006.568630757001108.28887764
#Sta/Elev= 18
    1000     430    1030     428    1040     426    1060     424    1085     422
    1220     422    1240     424    1252     422    1260     420    1280     414
    1290     414    1300     418    1320   418.6    1360     420    1370     424
    1430     426    1620     428    1710   428.8
#Mann= 5 ,-1,0
    1000     .05       0    1085     .04       0    1240     .07       0
    1320     .06       0    1370     .04       0
Bank Sta=1240,1320
XS Rating Curve= 0 ,0
Exp/Cntr=0.3,0.1

River Reach=West Fork       ,wf3
Reach XY= 30
       2346473.9        6963584.      2345494.34      6966352.98
      2346286.59      6968259.29      2350023.34      6968003.69
       2354512.4      6965894.36      2355330.74      6967716.62
      2359871.65      6970041.49      2363096.49      6969184.51
      2365532.14      6970407.58      2366189.04      6971823.97
      2365252.88      6972579.18      2367613.99      6972950.01
      2367619.48       6974853.9      2369582.09      6972823.37
      2372792.67      6972522.24      2376551.53      6968098.36
      2380668.89      6967549.98      2381491.36      6966391.92
      2382440.84      6968870.18       2383593.3      6968002.34
      2384725.84      6969858.66       2385600.2      6969508.62
      2385877.69      6972305.46      2387730.11       6971519.9
      2387123.85      6974369.92      2389461.82      6975900.01
      2395299.96      6974224.43      2396899.94      6975052.14
      2396212.76      6973722.55      2398149.68       6972930.3

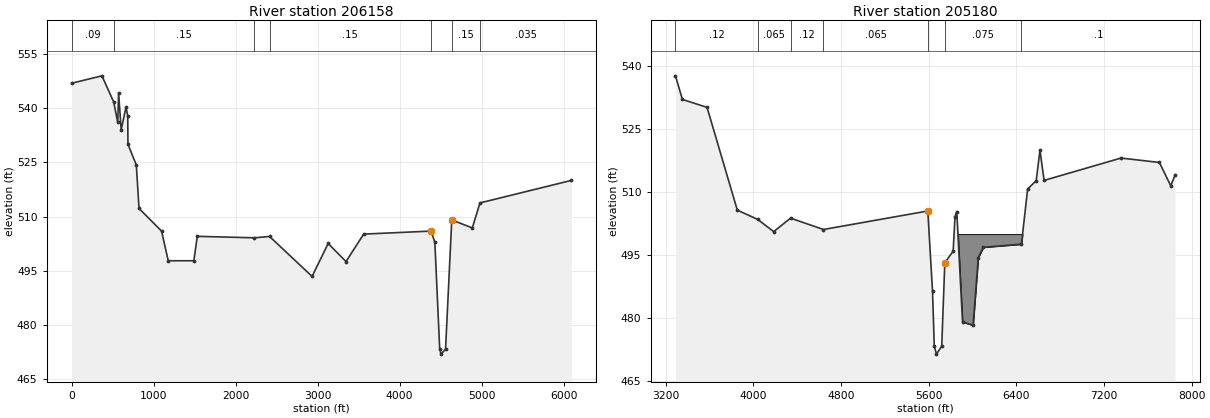
Type RM Length L Ch R = 1 ,206158  ,1071,978,460
BEGIN DESCRIPTION:
This cross section corresponds to cross section 206218 of the non-georeferenced CDC model which was the source of this model.
Downstream of East 1st Street.
END DESCRIPTION:
XS GIS Cut Line= 6
  2341904.095961 6963632.5437376   2343430.68391   6963683.60684
     2344852.789   6963698.88109   2345465.41508   6963790.52001
   2347058.22685   6964146.11608      2347944.51      6964068.28
#Sta/Elev= 30
       0  546.85  369.23   548.9  512.04  541.71  562.18  536.03  572.53  544.23
  603.81  533.98  663.08  540.28  684.12  537.77  686.41     530  788.51  524.26
  821.63  512.25 1096.67     506  1177.8   497.8 1490.48   497.8  1532.1  504.55
 2227.97  504.14 2413.28  504.51 2932.16  493.48 3128.06  502.57 3345.99  497.58
 3560.99  505.16 4383.29     506 4429.29  502.89 4488.22  473.47 4503.96     472
 4559.71  473.37 4635.51  509.09 4886.06  506.87 4979.55  513.78 6093.63     520
#Mann= 7 ,-1,0
       0     .09       0  512.04     .15       0 2227.97     .06       0
 2413.28     .15       0 4383.29    .066       0 4635.51     .15       0
 4979.55    .035       0
Bank Sta=4383.29,4635.51
XS Rating Curve= 0 ,0
Exp/Cntr=0.3,0.1

Type RM Length L Ch R = 1 ,205180  ,800,920,900
BEGIN DESCRIPTION:
This cross section corresponds to cross section 205240 of the non-georeferenced CDC model which was the source of this model.
ROB updated with 2009 TNRIS LiDAR
END DESCRIPTION:
XS GIS Cut Line= 6
  2343638.127123 6965094.4051029 2343922.8423688 6965034.2533849
   2344871.03011      6964833.93   2346477.14501      6964833.93
     2347171.557   6964475.169892347670.10784933 6964217.5993346
#Sta/Elev= 30
    3291   537.6    3354     532    3579   530.1    3855   505.7    4041   503.5
    4187   500.6    4341   503.8    4641   501.1    5593   505.5    5636   486.4
    5652   473.4    5672   471.5    5720   473.4    5748   493.2 5824.32  495.96
 5840.89  504.11  5857.3  505.35 5909.68  479.13 6006.13  478.36  6053.3  494.42
  6099.2  496.87 6447.21  497.62 6503.68  510.73 6581.57  512.68 6616.27  519.92
 6653.93  512.76  7355.7  518.07 7705.91  517.02 7809.26  511.48 7849.67  514.11
#Mann= 7 ,-1,0
    3291     .12       0    4041    .065       0    4341     .12       0
    4641    .065       0    5593    .055       0    5748    .075       0
 6447.21      .1       0
#XS Ineff= 2 , 0
            5593   505.5    5748           493.2
Permanent Ineff=
       F       F
#Block Obstruct= 1 ,-1
 5861.35 6480.54     500
Bank Sta=5593,5748
XS Rating Curve= 0 ,0
Exp/Cntr=0.3,0.1