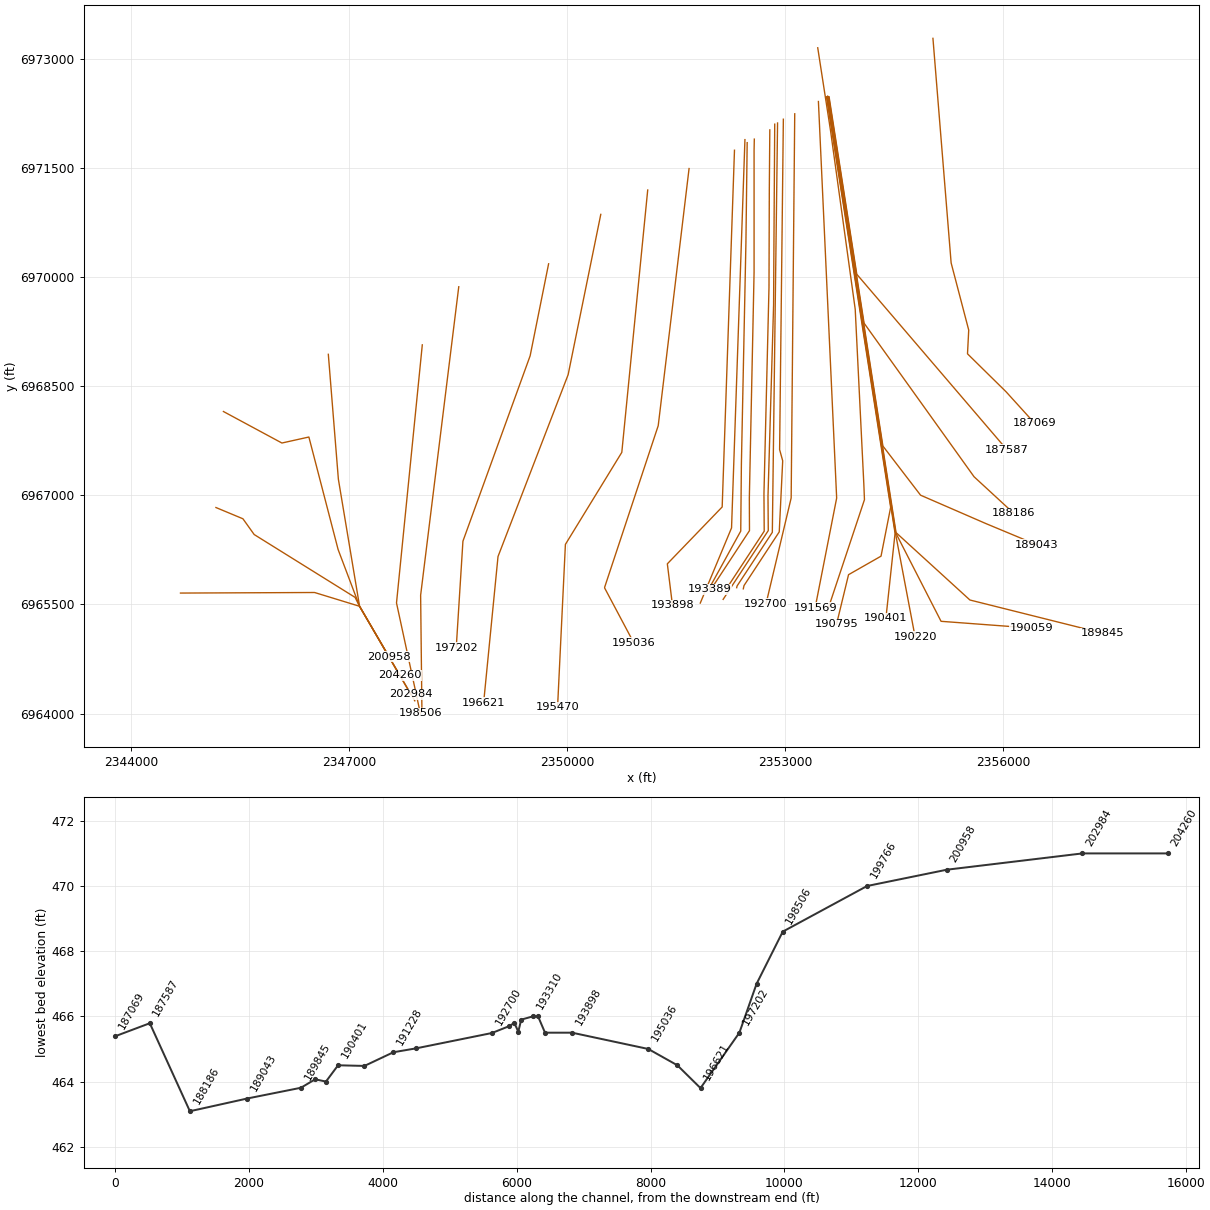
HEC-RAS study CDC_Consolidated_Model.prj: Upper Trinity CDC Consolidated Model

--- CDC_Consolidated_Model.g01 (geometry) --- (continued)

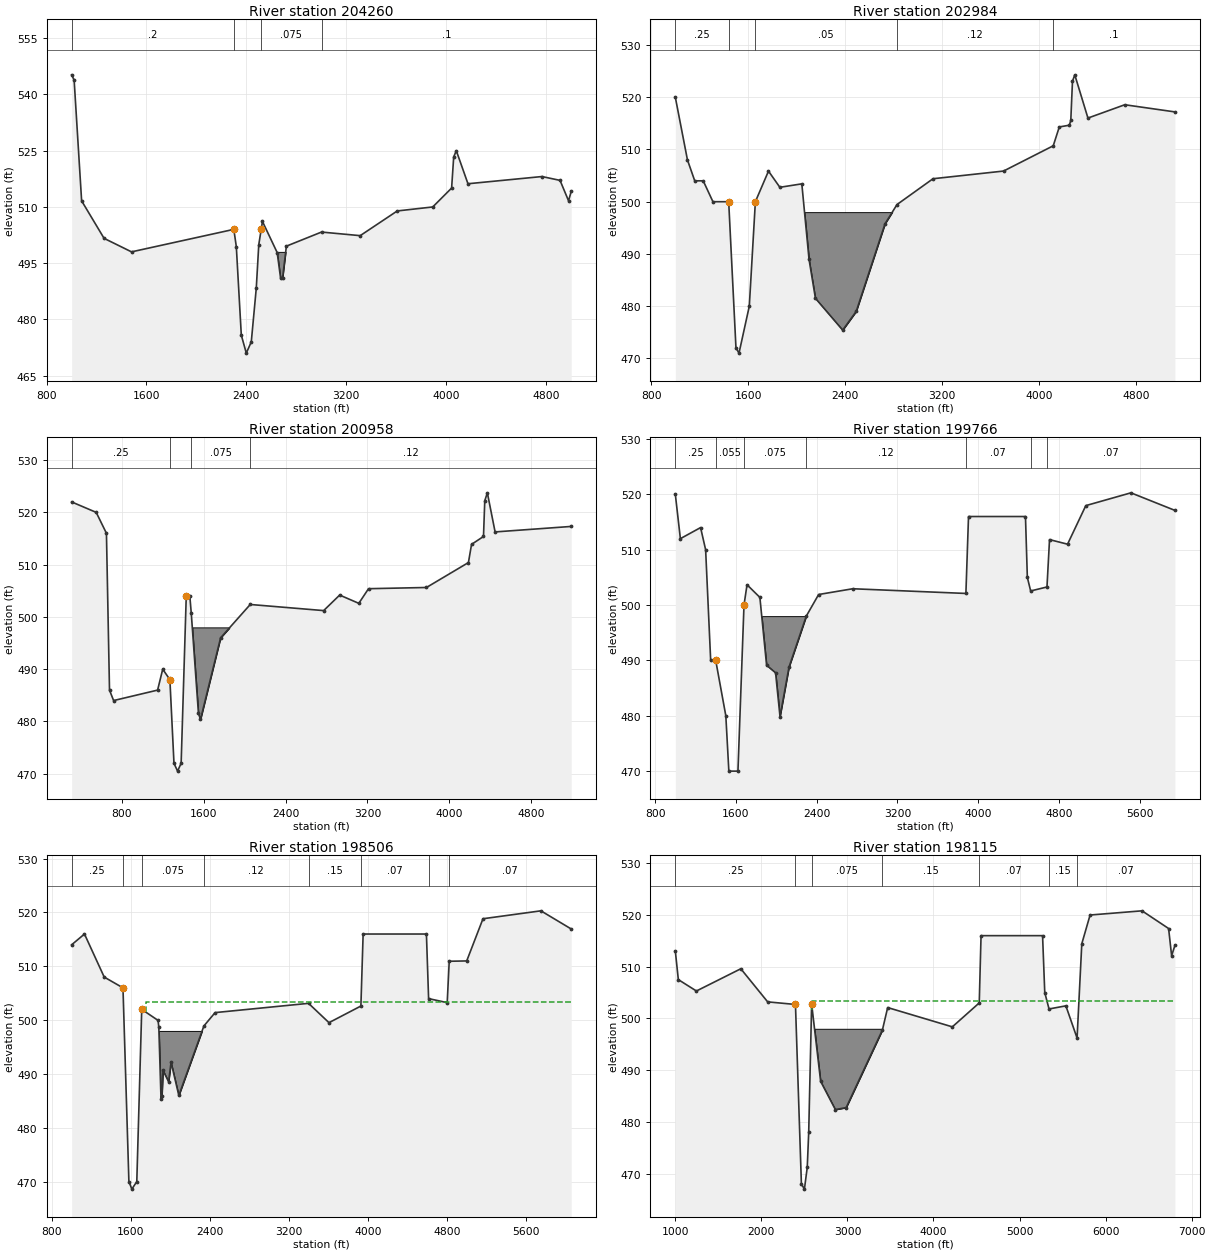
Type RM Length L Ch R = 1 ,204260  ,720,1276,145
BEGIN DESCRIPTION:
This cross section corresponds to cross section 204336 of the non-georeferenced CDC model which was the source of this model.
ROB updated with Halff Survey & 2009 TNRIS LiDAR
END DESCRIPTION:
XS GIS Cut Line= 5
  2344675.495232 6965656.7653464     2344766.751     6965657.144
     2346520.754     6965664.422     2347139.385     6965475.194
2347690.989661416964526.03722299
#Sta/Elev= 30
    1000   545.2    1020   543.8    1080   511.6    1260   501.6    1480     498
    2300     504    2320   499.4    2360   475.8    2400     471    2440     474
    2480   488.3    2500   499.9    2520   504.1 2529.47  506.11 2647.55  497.81
  2674.9     491 2690.71     491 2721.35  499.52 3002.93  503.28 3313.06  502.32
 3610.27  508.91 3894.45  509.97 4045.89  515.01 4062.53  523.31 4083.48  524.97
 4176.83  516.16 4770.05  518.08 4914.96  517.06 4983.21  511.61 5004.37   514.1
#Mann= 4 ,-1,0
    1000      .2       0    2300    .055       0    2520    .075       0
 3002.93      .1       0
#XS Ineff= 2 , 0
       0    2300     504    2520       0   504.1
Permanent Ineff=
       F       F
#Block Obstruct= 1 ,-1
 2628.13 2742.16     498
Bank Sta=2300,2520
XS Rating Curve= 0 ,0
Exp/Cntr=0.3,0.1

Type RM Length L Ch R = 1 ,202984  ,1688,2026,226
BEGIN DESCRIPTION:
This cross section corresponds to cross section 203180 of the non-georeferenced CDC model which was the source of this model.
New XS from 99 topo, interpolated FL, ROB updated with Halff Survey & 2009 TNRIS LiDAR
END DESCRIPTION:
XS GIS Cut Line= 6
      2345163.49      6966832.88      2345534.79      6966678.18
      2345689.49      6966461.59      2347077.94      6965597.59
    2347139.4996    6965475.21592347842.921038816964265.58805683
#Sta/Elev= 30
    1000     520    1100     508    1160     504    1230     504    1310     500
    1440     500    1500     472    1525     471    1610     480    1660     500
 1768.15  505.86 1861.89  502.76 2043.01  503.42 2102.64  488.94 2155.16   481.5
 2379.83  475.41 2491.72     479 2729.01  495.77 2828.13  499.46 3124.91   504.4
 3706.36  505.87 4116.31  510.71 4166.18  514.32 4248.99  514.65 4260.97  515.57
 4274.86  523.08 4293.79   524.3 4402.38  516.02 4705.99  518.57 5119.25   517.2
#Mann= 5 ,-1,0
    1000     .25       0    1440    .055       0    1660     .05       0
 2828.13     .12       0 4116.31      .1       0
#XS Ineff= 2 , 0
       0    1440     500 1768.15       0  505.86
Permanent Ineff=
       F       F
#Block Obstruct= 1 ,-1
    2040    2840     498
Bank Sta=1440,1660
XS Rating Curve= 0 ,0
Exp/Cntr=0.3,0.1

Type RM Length L Ch R = 1 ,200958  ,930,1192,380
BEGIN DESCRIPTION:
This cross section corresponds to cross section 201380 of the non-georeferenced CDC model which was the source of this model.
New XS from 99 topo, ROB updated with Halff Survey & 2009 TNRIS LiDAR
END DESCRIPTION:
XS GIS Cut Line= 6
      2345266.63      6968153.05       2346071.1      6967719.87
       2346442.4      6967802.38      2346844.64      6966255.32
      2347139.74      6965475.342347544.989937456964781.49227665
#Sta/Elev= 30
     310     522     550     520     650     516     680     486     720     484
    1150     486    1200     490    1270     488    1310     472    1345   470.5
    1380     472    1430     504 1464.58  504.03 1478.78  500.75  1549.1  481.54
 1568.96  480.38 1765.56     496 2055.38  502.38 2772.55  501.21 2929.15  504.18
 3116.13   502.6 3211.09   505.4 3777.11  505.63 4187.32   510.4 4217.82  513.88
 4334.55  515.39 4347.11  522.23 4372.27  523.74 4447.89  516.26 5191.53  517.31
#Mann= 4 ,-1,0
     310     .25       0    1270    .055       0 1478.78    .075       0
 2055.38     .12       0
#XS Ineff= 2 , 0
       0    1270     488    1430       0     504
Permanent Ineff=
       F       F
#Block Obstruct= 1 ,-1
    1450    1850     498
Bank Sta=1270,1430
XS Rating Curve= 0 ,0
Exp/Cntr=0.3,0.1

Type RM Length L Ch R = 1 ,199766  ,1454,1260,582
BEGIN DESCRIPTION:
This cross section corresponds to cross section 199650 of the non-georeferenced CDC model which was the source of this model.
New XS from 99 topo, ROB updated with Halff Survey & 2009 TNRIS LiDAR.
END DESCRIPTION:
XS GIS Cut Line= 4
     2346709.982     6968939.532     2346848.265     6967221.919
      2347139.86      6965475.382347900.20100835 6964175.2772821
#Sta/Elev= 30
    1000     520    1050     512    1250     514    1300     510    1350     490
    1400     490    1500     480    1530     470    1620     470    1680     500
 1710.03  503.67 1837.22  501.39 1903.67  489.13 1992.62  487.77 2036.58  479.85
 2125.81   488.8 2296.56     498 2419.07  501.91  2756.9  502.95 3877.32   502.1
 3903.31     516 4467.21     516 4485.82     505 4518.55  502.55 4680.23  503.27
 4705.46  511.83 4884.01     511  5064.8  517.97  5511.5  520.28 5946.79  517.11
#Mann= 7 ,-1,0
    1000     .25       0    1400    .055       0    1680    .075       0
 2296.56     .12       0 3877.32     .07       0 4518.55     .12       0
 4680.23     .07       0
#XS Ineff= 2 , 0
       0    1400     490 1710.03       0  503.67
Permanent Ineff=
       F       F
#Block Obstruct= 1 ,-1
 1837.06 2346.15     498
Bank Sta=1400,1680
XS Rating Curve= 0 ,0
Exp/Cntr=0.3,0.1

Type RM Length L Ch R = 1 ,198506  ,349,391,368
BEGIN DESCRIPTION:
This cross section corresponds to cross section 206218 of the non-georeferenced CDC model which was the source of this model.
ROB updated with Halff Survey & 2009 TNRIS LiDAR.
END DESCRIPTION:
XS GIS Cut Line= 4
  2348003.085197 6969069.6508566 2347648.1905658 6965520.7055267
 2347906.2956927  6964326.969069 2347976.4651557 6964002.4352358
#Sta/Elev= 30
    1000     514    1130     516    1330     508    1520     506    1580     470
    1610   468.6    1660     470    1710     502 1875.43  499.95 1883.11  498.64
 1905.52   485.3 1914.73  485.94 1925.51  490.66 1982.34  488.55 2007.16  492.15
 2085.73     486 2339.86  498.92 2453.16   501.4  3399.9  503.12 3606.91  499.53
 3930.15  502.62 3952.88     516    4594     516 4616.11     504 4804.64  503.25
 4824.95  510.94  5002.2     511 5167.04  518.84 5753.77  520.31 6060.59  516.94
#Mann= 8 ,-1,0
    1000     .25       0    1520    .055       0    1710    .075       0
 2339.86     .12       0  3399.9     .15       0 3930.15     .07       0
 4616.11     .15       0 4824.95     .07       0
#XS Ineff= 2 , 0
       0    1520     506 1749.35       0  503.34
Permanent Ineff=
       F       F
#Block Obstruct= 1 ,-1
 1840.91 2392.05     498
Bank Sta=1520,1710
XS Rating Curve= 0 ,0
Exp/Cntr=0.3,0.1

Type RM Length L Ch R = 1 ,198115  ,290,257,209
BEGIN DESCRIPTION:
This cross section corresponds to cross section 198174 of the non-georeferenced CDC model which was the source of this model.
ROB updated with Halff Survey & 2009 TNRIS LiDAR.
END DESCRIPTION:
XS GIS Cut Line= 4
  2348504.949801  6969868.622957   2348502.25415   6969846.83204
   2347980.22009      6965626.85      2347997.38      6964089.91
#Sta/Elev= 30
    1000     513    1035   507.5    1245   505.3    1761   509.6    2073   503.2
    2396   502.7    2465     468    2500     467    2533   471.2    2550     478
    2584   502.8 2688.58  487.83 2859.56  482.38 2985.18  482.76 3406.38  497.76
 3467.49   502.1 4218.93  498.37 4531.75     503 4552.65     516 5267.57     516
    5293     505 5342.63  501.83 5538.47  502.43 5668.55   496.2 5723.42  514.44
 5819.85  519.99 6423.42   520.8 6732.17  517.38 6767.22  512.11 6805.11   514.1
#Mann= 7 ,-1,0
    1000     .25       0    2396    .055       0    2584    .075       0
 3406.38     .15       0 4531.75     .07       0 5342.63     .15       0
 5668.55     .07       0
#XS Ineff= 2 , 0
       0    2396   502.7 2592.56       0  503.36
Permanent Ineff=
       F       F
#Block Obstruct= 1 ,-1
 2602.27 3460.23     498
Bank Sta=2396,2584
XS Rating Curve= 0 ,0
Exp/Cntr=0.3,0.1

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
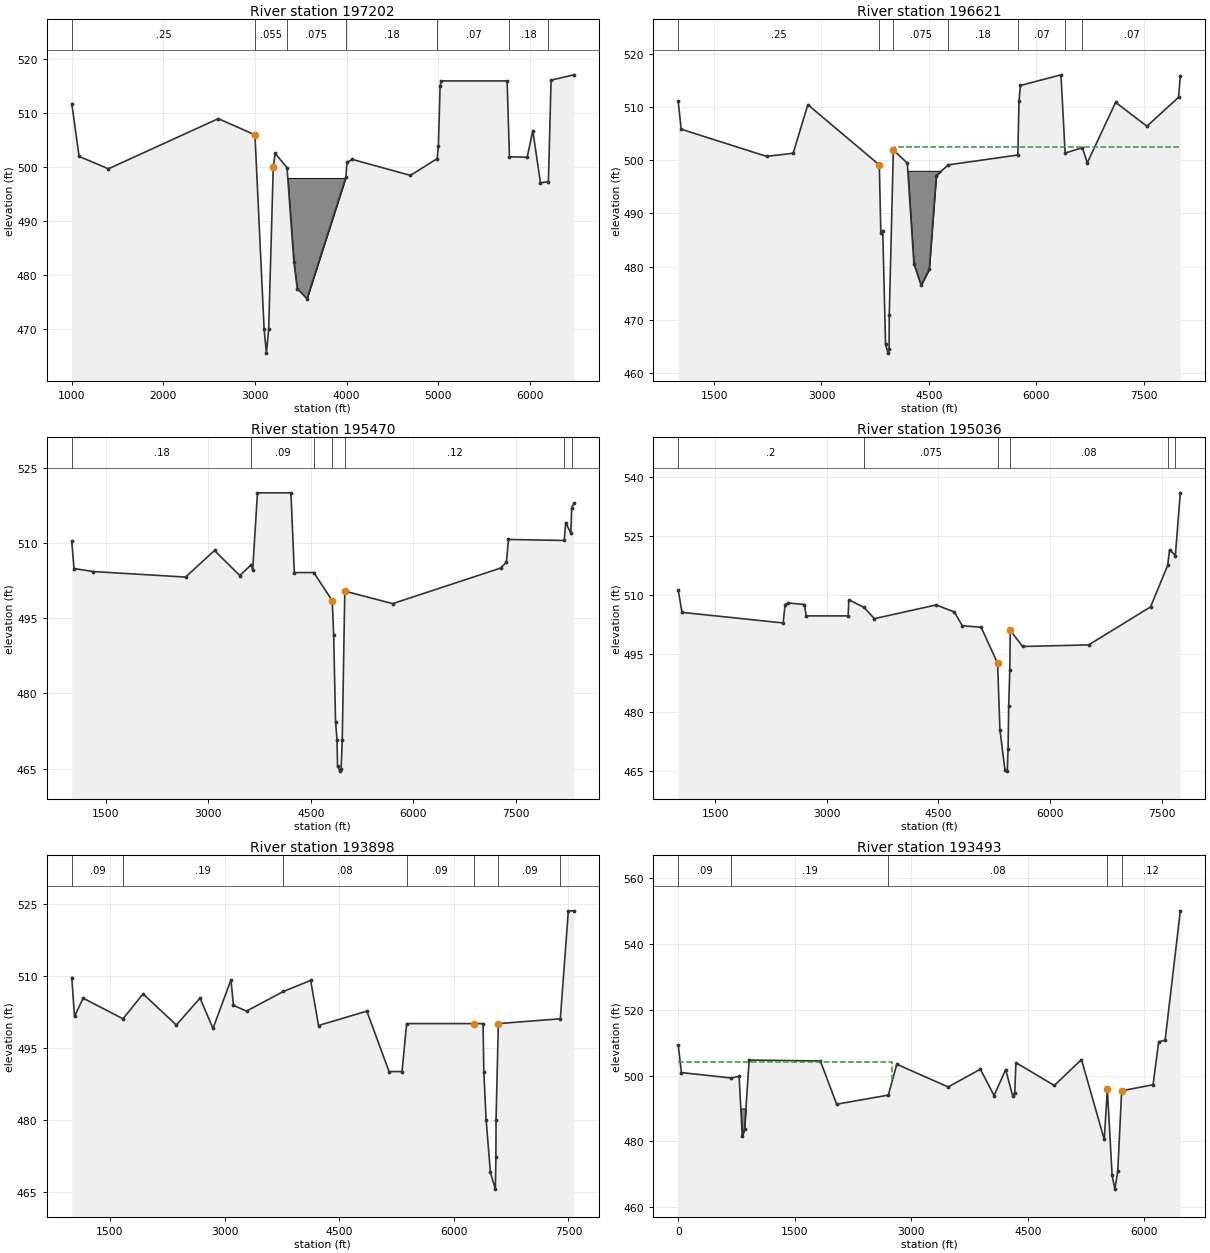
Type RM Length L Ch R = 1 ,197202  ,645,581,488
BEGIN DESCRIPTION:
This cross section corresponds to cross section 197450 of the non-georeferenced CDC model which was the source of this model.
New XS from 99 topo, interpolated FL, ROB updated with Halff Survey & 2009 TNRIS LiDAR.
END DESCRIPTION:
XS GIS Cut Line= 5
   2349741.33176 6970183.8905078 2349487.1895125 6968919.0894779
 2348562.3127533 6966370.3012684 2348476.2778204 6965004.4949449
2348469.991076486964904.69275628
#Sta/Elev= 30
    1000   511.8    1080     502    1400   499.7    2600     509    3000     506
    3100     470    3125   465.5    3150     470    3200     500  3221.2  502.56
 3350.16   499.9 3424.87  482.49 3461.66  477.45 3568.31   475.6 3992.64  498.11
 4004.66  500.91 4064.85  501.43  4697.8  498.47  4990.1  501.59 5003.08     504
 5021.71     515 5032.14     516 5753.18     516 5779.05  501.93 5972.35  501.84
 6033.88  506.77 6117.03  497.12 6204.19  497.28 6233.31  516.14 6481.95  517.13
#Mann= 7 ,-1,0
    1000     .25       0    3000    .055       0 3350.16    .075       0
 3992.64     .18       0  4990.1     .07       0 5779.05     .18       0
 6204.19     .07       0
#XS Ineff= 3 ,-1
    1000    3000     506  3221.2 6033.82  502.56 6033.82 6222.04  506.74
Permanent Ineff=
       F       F       T
#Block Obstruct= 1 ,-1
 3335.23 4034.09     498
Bank Sta=3000,3200
XS Rating Curve= 0 ,0
Exp/Cntr=0.3,0.1

Type RM Length L Ch R = 1 ,196621  ,254,346,207
BEGIN DESCRIPTION:
This cross section corresponds to cross section 196680 of the non-georeferenced CDC model which was the source of this model.
ROB updated with Halff Survey & 2009 TNRIS LiDAR.
END DESCRIPTION:
XS GIS Cut Line= 4
   2350459.27714   6970863.80901   2350010.07593   6968659.57294
   2349045.13003   6966159.15996 2348846.7584696 6964144.5914655
#Sta/Elev= 30
    1000     511    1041   505.8    2235   500.7    2605   501.3    2810   510.4
    3808   499.1    3829   486.3    3856   486.8    3895   465.5    3930   463.8
    3945   464.5    3947     471    4004   501.9 4198.79  499.45 4290.71  480.59
 4391.66  476.52 4504.75  479.51 4604.34  497.11 4770.88  499.11 5742.08  500.96
 5758.21     511 5778.32     514 6344.68     516 6402.86  501.32 6643.71  502.34
 6712.02  499.49 7107.86  510.84 7544.96  506.36 7986.24  511.78  8011.3  515.76
#Mann= 7 ,-1,0
    1000     .25       0    3808    .055       0    4004    .075       0
 4770.88     .18       0 5742.08     .07       0 6402.86     .18       0
 6643.71     .07       0
#XS Ineff= 2 , 0
       0    3808   499.1 4030.27       0  502.37
Permanent Ineff=
       F       F
#Block Obstruct= 1 ,-1
 4166.67 4666.67     498
Bank Sta=3808,4004
XS Rating Curve= 0 ,0
Exp/Cntr=0.3,0.1

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
Type RM Length L Ch R = 1 ,195470  ,500,434,700
BEGIN DESCRIPTION:
This cross section corresponds to cross section 195526 of the non-georeferenced CDC model which was the source of this model.
ROB updated with Halff Survey & 2009 TNRIS LiDAR.
END DESCRIPTION:
XS GIS Cut Line= 5
  2351105.088864  6971198.753877   2351105.06685   6971198.53111
   2350748.60005   6967591.37494   2349972.41984   6966325.86402
   2349864.37806   6964083.99515
#Sta/Elev= 30
    1000   510.3    1033   504.9    1317   504.3    2666   503.2    3091   508.5
    3461   503.5    3632   505.7    3650   504.6    3720     520    4210     520
    4260   504.1    4545   504.1    4815   498.5    4836   491.7    4864   474.3
    4885   470.8    4893   465.5    4928   464.5    4945     465    4962   470.8
    4999   500.4    5700   497.9    7283     505    7367   506.2    7396   510.7
    8213   510.5    8235     514    8310     512    8322     517    8354   517.9
#Mann= 7 ,-1,0
    1000     .18       0    3632     .09       0    4545      .1       0
    4815    .055       0    4999     .12       0    8213     .04       0
    8322     .12       0
#XS Ineff= 2 , 0
       0    4815   498.5    4999       0   500.4
Permanent Ineff=
       F       F
Bank Sta=4815,4999
XS Rating Curve= 0 ,0
Exp/Cntr=0.3,0.1

Type RM Length L Ch R = 1 ,195036  ,1140,1139,827
BEGIN DESCRIPTION:
This cross section corresponds to cross section 195089 of the non-georeferenced CDC model which was the source of this model.
END DESCRIPTION:
XS GIS Cut Line= 6
   2351674.21992   6971493.79496   2351249.84084   6967958.91883
   2350512.53293   6965737.03055   2350512.53293   6965726.17985
   2350695.08309   6965382.96893   2350913.68502   6964971.97598
#Sta/Elev= 30
    1000   511.1    1051   505.5    2411   502.8    2437   507.5    2476   507.9
    2697   507.5    2721   504.6    3285   504.6    3294   508.7    3497   506.8
    3637   503.9    4469   507.4    4713   505.6    4820   502.1    5074   501.7
    5295   492.5    5326   475.6    5393   465.4    5425     465    5436   470.7
    5444   481.7    5459   490.8    5465   500.9    5631   496.8    6519   497.2
    7352   506.9    7582   517.5    7608   521.5    7685     520    7752     536
#Mann= 6 ,-1,0
    1000      .2       0    3497    .075       0    5295     .05       0
    5465     .08       0    7582     .04       0    7685     .08       0
#XS Ineff= 2 , 0
       0    5295   492.5               0
Permanent Ineff=
       F       F
Bank Sta=5295,5465
XS Rating Curve= 0 ,0
Exp/Cntr=0.3,0.1

Type RM Length L Ch R = 1 ,193898  ,158,404,739
BEGIN DESCRIPTION:
This cross section corresponds to cross section 193960 of the non-georeferenced CDC model which was the source of this model.
END DESCRIPTION:
XS GIS Cut Line= 6
  2352299.126757 6971745.9850765 2352208.5338073 6969120.7800194
 2352129.8380986 6966840.8078733 2351752.5311104 6966449.8037341
 2351375.2149359 6966058.8038599  2351445.887498 6965487.9918045
#Sta/Elev= 30
    1000   509.6    1036   501.5    1149   505.3    1670     501    1933   506.2
    2368   499.7    2678   505.3    2848     499    3083   509.1    3116   503.8
    3287   502.6    3769   506.7    4126     509    4229   499.6    4861   502.6
    5152     490    5322     490    5382     500    6262     500    6382     500
    6392     490    6422     480    6478     469    6543   465.5    6550   472.2
    6552     480    6582     500    7393     501    7498   523.5    7570   523.5
#Mann= 7 ,-1,0
    1000     .09       0    1670     .19       0    3769     .08       0
    5382     .09       0    6262    .055       0    6582     .09       0
    7393     .04       0
#XS Ineff= 2 , 0
       0    6262   498.8    6582       0   498.8
Permanent Ineff=
       F       F
Bank Sta=6262,6582
XS Rating Curve= 0 ,0
Exp/Cntr=0.3,0.1

Type RM Length L Ch R = 1 ,193493  ,106,104,61
BEGIN DESCRIPTION:
This cross section corresponds to cross section 193550 of the non-georeferenced CDC model which was the source of this model.
END DESCRIPTION:
XS GIS Cut Line= 3
  2352443.025935 6971891.6115285 2352258.7703713  6966552.700172
 2351828.4115221 6965519.1106147
#Sta/Elev= 30
       0  509.18   41.13   500.9  677.13  499.27  783.58  499.76  824.05  481.51
  852.93  483.73  912.97   504.7 1829.18  504.42 2039.15   491.3 2703.93  494.06
  2812.7  503.43 3474.17  496.54 3888.24  501.93 4064.79  493.93 4214.01  501.83
 4304.49  493.79 4330.97   494.8 4345.66  503.93 4839.83  496.99 5189.74  504.85
 5482.76  480.59 5522.98  495.82 5583.86  469.74 5619.12   465.5 5656.59  470.97
 5706.85  495.36 6111.13  497.21 6183.22  510.26 6266.13  510.73  6461.7  550.03
#Mann= 5 ,-1,0
       0     .09       0  677.13     .19       0 2703.93     .08       0
 5522.98    .055       0 5706.85     .12       0
#XS Ineff= 2 , 0
       0    2751     504               0
Permanent Ineff=
       T       F
#Block Obstruct= 1 ,-1
       0    2751     490
Bank Sta=5522.98,5706.85
XS Rating Curve= 0 ,0
Exp/Cntr=0.3,0.1

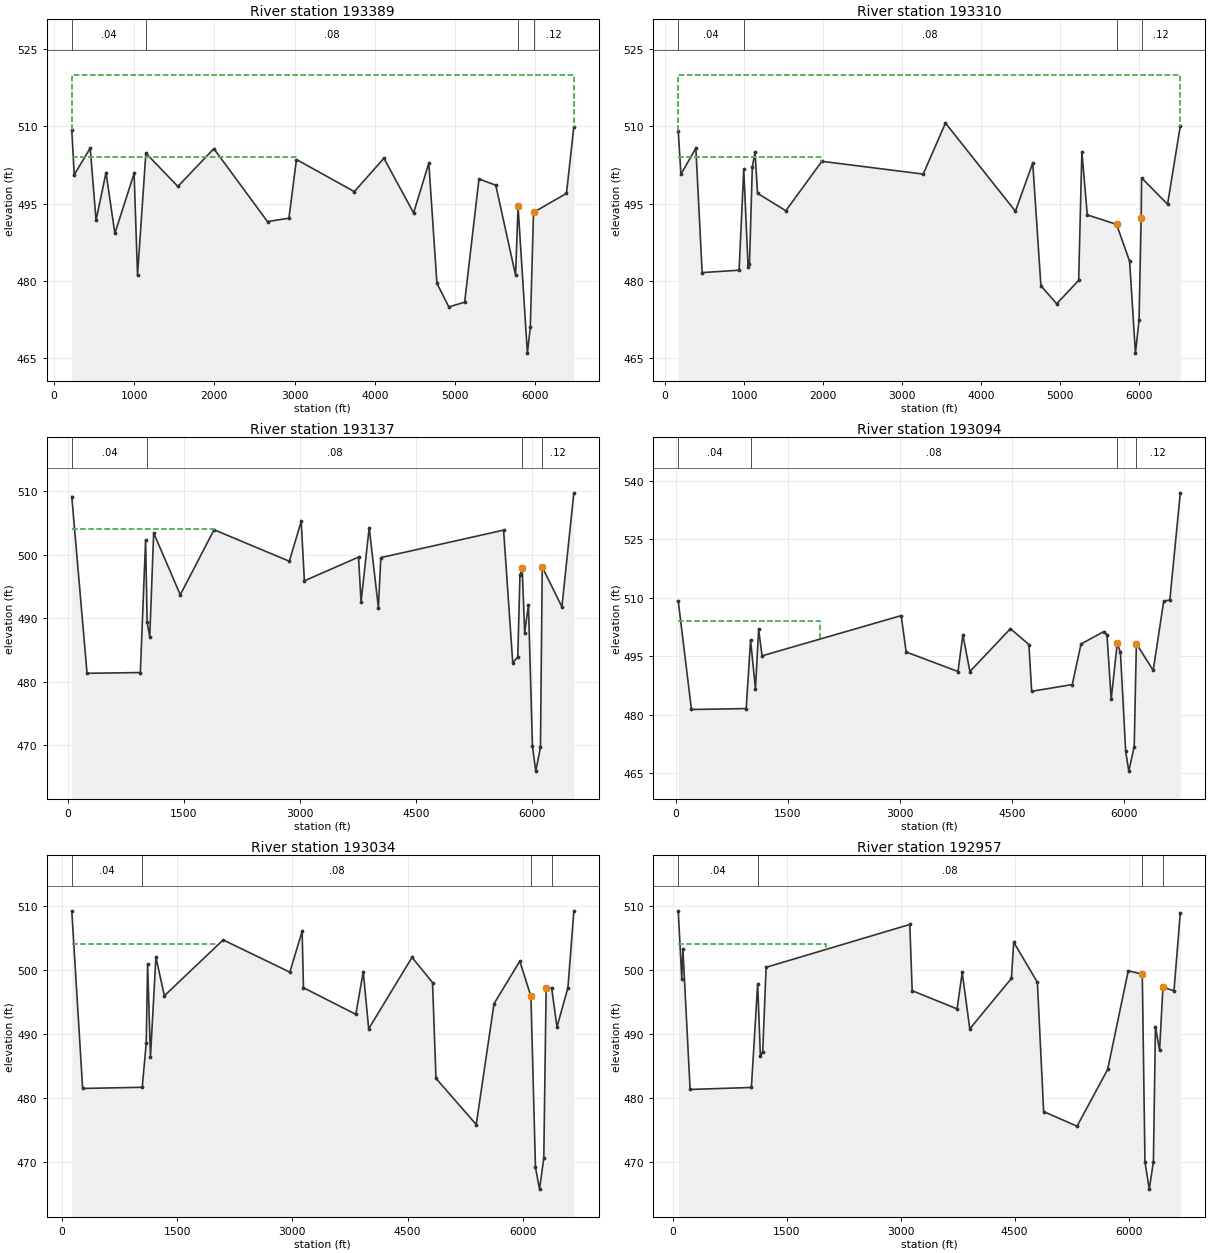
Type RM Length L Ch R = 1 ,193389  ,122,78,51
BEGIN DESCRIPTION:
This cross section corresponds to cross section 193445 of the non-georeferenced CDC model which was the source of this model.
END DESCRIPTION:
XS GIS Cut Line= 6
2352473.837041296971849.97693733 2352456.5881012 6970477.4485659
 2352394.3050893 6967434.9139686 2352385.2775483 6966508.8721855
 2351974.1408146  6965763.491814      2351950.69      6965705.94
#Sta/Elev= 30
  224.08  509.32  254.81  500.62  453.74  505.78   526.7  491.79  650.64  501.03
  761.17  489.23  1000.6  500.87 1043.32  481.13 1147.23   504.8 1546.14  498.34
 1994.09  505.68 2662.67  491.53 2929.41  492.18 3023.46  503.57 3744.55  497.34
 4112.99  503.82 4482.76  493.21 4672.53  502.87 4773.32  479.55 4921.56  474.97
 5118.77  475.88 5297.32   499.8 5506.87  498.58  5753.1  481.14 5784.16  494.47
 5900.72     466 5937.01  471.06 5976.78  493.32 6387.44  496.99 6479.37  509.94
#Mann= 4 ,-1,0
  224.08     .04       0 1147.23     .08       0 5784.16    .055       0
 5976.78     .12       0
#XS Ineff= 3 ,-1
  224.08  224.08     520  224.08    3023     504    3023    5400     495
Permanent Ineff=
       F       T       T
Bank Sta=5784.16,5976.78
XS Rating Curve= 0 ,0
Exp/Cntr=0.3,0.1

Type RM Length L Ch R = 1 ,193310  ,205,174,200
BEGIN DESCRIPTION:
This cross section corresponds to cross section 193367 of the non-georeferenced CDC model which was the source of this model.
END DESCRIPTION:
XS GIS Cut Line= 6
2352572.123409026971898.47775193  2352568.827706 6971743.1375957
 2352568.8277062 6970066.9018148 2352503.7235057 6966965.3394484
 2352505.5683183  6966515.035559       2351971.1      6965700.84
#Sta/Elev= 30
  166.21  509.13  200.37   500.7  389.26  505.77  469.18  481.63  936.98  482.09
  995.79  501.69 1050.82  482.71 1068.34  483.31 1104.48  502.09 1138.52  505.03
 1170.41  497.01 1528.56  493.63 1985.19  503.22 3268.55  500.74 3550.35  510.64
 4436.17  493.53 4655.42  502.89 4759.06  479.07  4958.8  475.58 5237.04  480.12
 5277.69  505.07 5346.19  492.82 5716.61  490.99 5882.44  483.82 5955.94     466
 6001.45  472.34 6028.73   492.3 6034.24     500 6362.69  494.89 6524.33  510.11
#Mann= 4 ,-1,0
  166.21     .04       0  995.79     .08       0 5716.61    .055       0
 6034.24     .12       0
#XS Ineff= 3 ,-1
  166.21  166.21     520  166.21    1976     504    1976    5277     495
Permanent Ineff=
       F       T       T
Bank Sta=5716.61,6028.73
XS Rating Curve= 0 ,0
Exp/Cntr=0.3,0.1

Type RM Length L Ch R = 1 ,193137  ,57,43,48
BEGIN DESCRIPTION:
This cross section corresponds to cross section 193191 of the non-georeferenced CDC model which was the source of this model.
END DESCRIPTION:
XS GIS Cut Line= 6
2352785.392499146972025.51509574 2352778.4631137 6971204.4018364
 2352774.1228992 6969863.2558966 2352704.7654264 6967023.4121669
 2352708.2375323 6966507.4401017 2352176.3939033 6965698.3965122
#Sta/Elev= 30
   50.54  509.13  247.89   481.3  936.48  481.42 1004.48   502.3 1024.63   489.3
 1057.99  487.03 1108.82   503.4 1452.78  493.66  1889.3   503.9 2861.37  498.94
 3015.24  505.21 3055.94  495.86 3755.73  499.59  3788.4  492.53 3893.22  504.23
 4012.21  491.64 4043.83  499.51 5630.05  503.84  5747.9  482.99 5813.19  483.84
 5841.43  496.77 5870.72  497.81 5902.14  487.69 5951.19  492.03 6002.89  469.82
 6045.64   465.9 6106.29  469.63 6129.35  498.03 6383.54  491.76 6537.71  509.71
#Mann= 4 ,-1,0
   50.54     .04       0 1024.63     .08       0 5870.72    .055       0
 6129.35     .12       0
#XS Ineff= 2 , 0
       0    1889     504               0
Permanent Ineff=
       T       F
Bank Sta=5870.72,6129.35
XS Rating Curve= 0 ,0
Exp/Cntr=0.3,0.1

Type RM Length L Ch R = 1 ,193094  ,60,60,66
BEGIN DESCRIPTION:
This cross section corresponds to cross section 193150 of the non-georeferenced CDC model which was the source of this model.
END DESCRIPTION:
XS GIS Cut Line= 6
2352852.87844495 6972104.0872561 2352840.5612366 6970218.7025511
 2352837.4241144 6969621.6036281 2352760.3903363  6966987.815267
 2352764.1084071  6966515.620283 2352143.1905934   6965569.92899
#Sta/Elev= 30
   35.86   509.2  212.61  481.34  945.59  481.57 1004.06  499.15 1069.66  486.64
 1112.03   501.9 1158.23   495.1 3020.37  505.42 3087.22  496.08 3780.94  491.08
 3846.26  500.52 3939.83  491.08 4482.74  502.06    4730     498    4767     486
 5310.69  487.74 5427.39  498.13 5728.71  501.29 5775.07  500.54 5831.45  483.94
 5912.64  498.34 5955.03  496.02 6025.82  470.57 6067.43  465.53 6139.66  471.83
 6168.79  498.23 6393.85  491.35 6534.23  509.12 6616.55  509.43 6756.83  536.91
#Mann= 4 ,-1,0
   35.86     .04       0 1004.06     .08       0 5912.64    .055       0
 6168.79     .12       0
#XS Ineff= 2 ,-1
   35.86    1927     504    1927    5600     495
Permanent Ineff=
       T       T
Bank Sta=5912.64,6168.79
XS Rating Curve= 0 ,0
Exp/Cntr=0.3,0.1

Type RM Length L Ch R = 1 ,193034  ,123,77,86
BEGIN DESCRIPTION:
This cross section corresponds to cross section 193090 of the non-georeferenced CDC model which was the source of this model.
END DESCRIPTION:
XS GIS Cut Line= 4
 2352892.02243966972120.15922691   2352820.01192   6966491.78397
   2352334.57293   6965753.66996 2352329.4506053 6965730.4427391
#Sta/Elev= 30
   128.7  509.17  270.24  481.49 1046.04  481.67 1098.25   488.6 1115.99  500.87
 1153.14  486.41 1223.99  501.96 1334.13  495.93 2099.58  504.64  2967.5  499.61
 3127.86  505.99 3144.69  497.19 3826.58  493.04 3923.29   499.7 3993.92  490.78
  4557.8  501.92    4825     498 4870.25  483.06 5394.06  475.87 5625.78  494.71
 5961.22  501.32 6106.15  495.83 6165.19  469.18    6218   465.8 6273.41  470.62
 6304.06  497.07 6375.99  497.14 6445.56  491.07 6587.76   497.2 6664.76   509.1
#Mann= 4 ,-1,0
   128.7     .04       0 1046.04     .08       0 6106.15    .055       0
 6375.99     .12       0
#XS Ineff= 2 ,-1
   128.7    2024     504    2024 6106.15     495
Permanent Ineff=
       T       T
Bank Sta=6106.15,6304.06
XS Rating Curve= 0 ,0
Exp/Cntr=0.3,0.1

Type RM Length L Ch R = 1 ,192957  ,130,257,335
BEGIN DESCRIPTION:
This cross section corresponds to cross section 193010 of the non-georeferenced CDC model which was the source of this model.
END DESCRIPTION:
XS GIS Cut Line= 6
 2352971.71732316972172.17847792 2352920.2764783 6967629.3866767
 2352962.6376141 6967475.2199903 2352915.2525382  6966498.299372
 2352430.4598727 6965760.0442868 2352420.5763125 6965714.8465052
#Sta/Elev= 30
   71.23  509.17  117.97  498.57  132.87  503.14  227.51  481.27 1034.38  481.58
 1117.05  497.77 1153.08  486.43 1183.83  487.18    1228  500.35 3120.14  507.04
 3151.34   496.7 3742.62  493.85 3810.14  499.54 3909.82  490.74  4458.1  498.62
 4488.22  504.27    4800     498 4882.31  477.81 5322.27  475.53 5724.98  484.39
 5996.06   499.8 6181.08   499.3 6216.49  469.96 6273.04   465.7 6327.41  469.99
 6354.58   491.1 6408.59  487.36 6452.91  497.24  6598.2  496.68 6681.76  508.88
#Mann= 4 ,-1,0
   71.23     .04       0 1117.05     .08       0 6181.08    .055       0
 6452.91     .12       0
#XS Ineff= 2 ,-1
   71.23    2012     504    2500 6181.08     495
Permanent Ineff=
       T       T
Bank Sta=6181.08,6452.91
XS Rating Curve= 0 ,0
Exp/Cntr=0.3,0.1

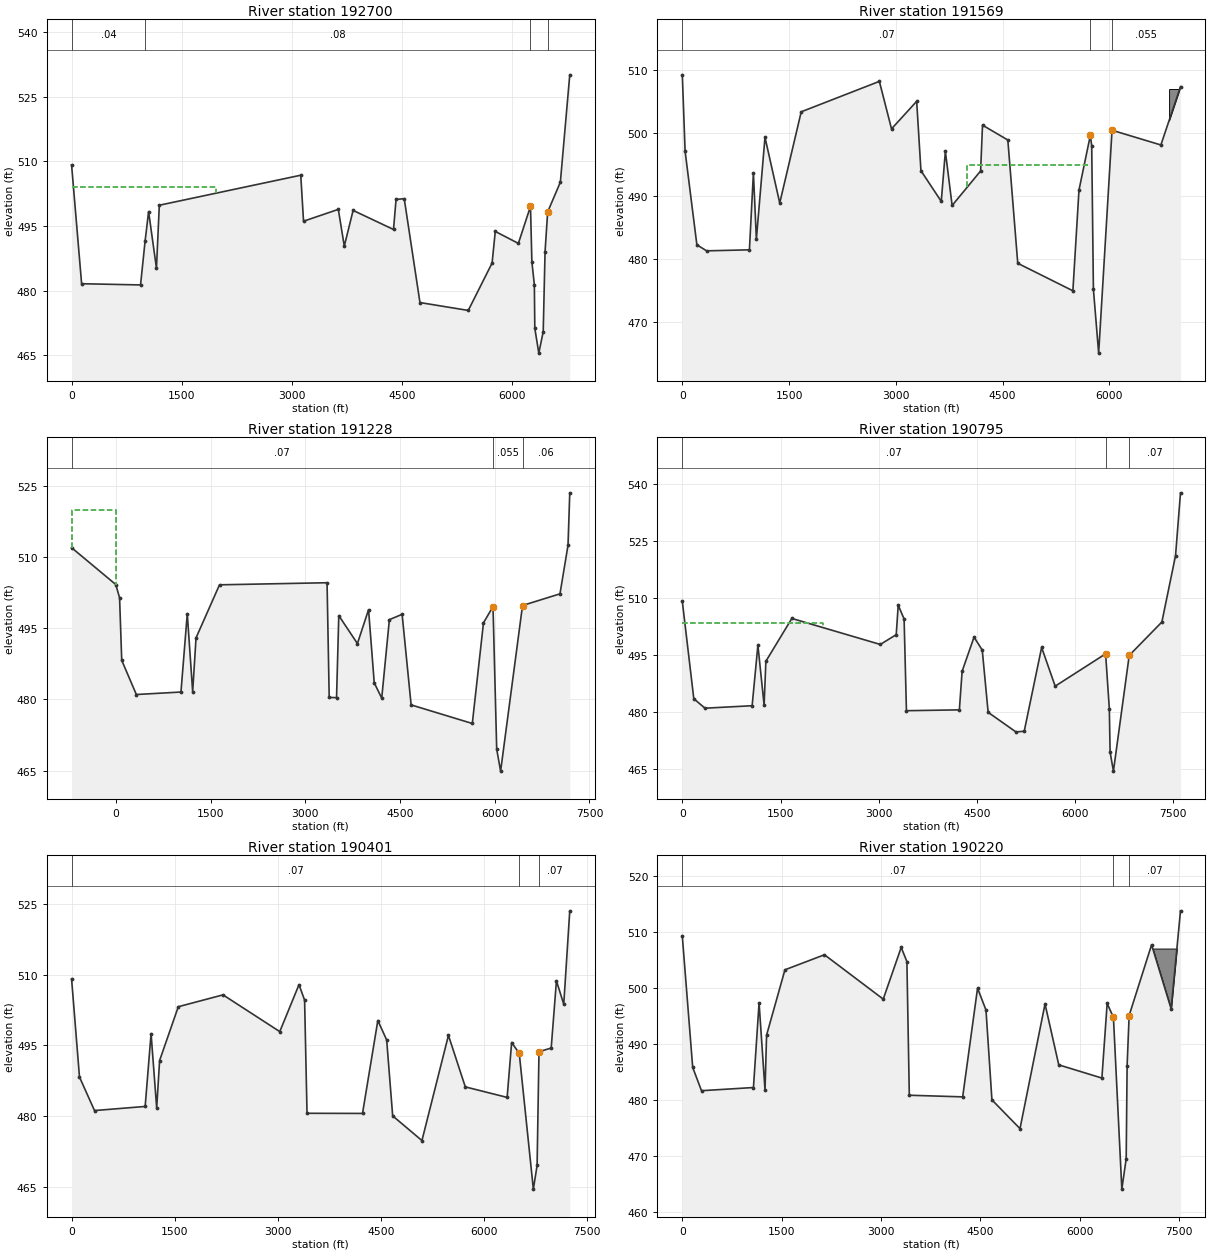
Type RM Length L Ch R = 1 ,192700  ,607,1131,666
BEGIN DESCRIPTION:
This cross section corresponds to cross section 192756 of the non-georeferenced CDC model which was the source of this model.
---------------------------------------------------------------------
CDC FW121411-01 Goodman A Gas Well Site Pad
Cross-section 192756 - 193191
Project located in LOB.
---------------------------------------------------------------------
END DESCRIPTION:
XS GIS Cut Line= 4
  2353128.240989 6972246.6742974   2353128.24096   6972246.67108
   2353079.20004   6966964.39916   2352733.06688   6965508.05004
#Sta/Elev= 30
       0  509.18  136.61   481.6  938.54  481.32 1000.06  491.43 1048.26  498.35
 1155.25  485.19 1193.84  499.82 3118.81  506.79  3156.6  496.11 3629.96  498.86
 3711.19  490.33 3831.21  498.62 4380.82  494.19 4415.66  501.17 4526.84  501.34
 4740.87  477.23 5398.19   475.4 5722.52   486.4 5765.83  493.74 6080.24  490.96
 6245.12  499.56 6263.85  486.66 6297.54   481.4 6303.81  471.25 6358.17  465.49
 6418.16  470.47 6443.12  489.03 6478.67  498.26 6651.54  505.18 6779.42  530.09
#Mann= 4 ,-1,0
       0     .04       0 1000.06     .08       0 6245.12    .055       0
 6478.67     .07       0
#XS Ineff= 2 ,-1
       0    1971     504    2000 6245.12     495
Permanent Ineff=
       T       T
Bank Sta=6245.12,6478.67
XS Rating Curve= 0 ,0
Exp/Cntr=0.3,0.1

Type RM Length L Ch R = 1 ,191569  ,400,341,222
BEGIN DESCRIPTION:
This cross section corresponds to cross section 191625 of the non-georeferenced CDC model which was the source of this model.
END DESCRIPTION:
XS GIS Cut Line= 3
  2353454.155125 6972415.7538811  2353705.260242 6966962.8503038
 2353408.5971956  6965451.957321
#Sta/Elev= 30
       0  509.26      39  497.12   204.5  482.24  340.91  481.28  942.64  481.44
  998.62  493.66 1040.32  483.14 1161.26  499.33 1368.44  488.88  1670.2  503.38
 2768.11  508.22 2938.86  500.67  3292.2  505.05 3352.13  494.02 3637.63  489.14
 3695.25  497.09 3790.16  488.49 4190.42  493.98    4217  501.26 4572.67   498.9
 4712.12   479.3 5486.61  474.93 5572.24  490.94 5732.33  499.66 5751.04  497.95
 5774.91  475.17 5848.65  465.02 6036.57  500.45 6722.72  498.11 6998.43  507.39
#Mann= 3 ,-1,0
       0     .07       0 5732.33    .055       0 6036.57    .055       0
#XS Ineff= 2 ,-1
       0    2106   503.5    4000    5693     495
Permanent Ineff=
       T       T
#Block Obstruct= 2 ,-1
                            6838    6998     507
Bank Sta=5732.33,6036.57
XS Rating Curve= 0 ,0
Exp/Cntr=0.3,0.1

Type RM Length L Ch R = 1 ,191228  ,284,433,141
BEGIN DESCRIPTION:
This cross section corresponds to cross section 191291 of the non-georeferenced CDC model which was the source of this model.
END DESCRIPTION:
XS GIS Cut Line= 6
 2353444.71827056973154.60396188 2353620.0158925 6972021.9690989
 2353960.6323372 6969558.7702851 2354079.3820998  6967149.916179
 2354087.7157445 6966940.5412697 2353571.0487988 6965390.5410888
#Sta/Elev= 30
    -700     512       0  504.23   60.11  501.43   94.05  488.26  325.34  481.05
 1031.92  481.57 1131.88  498.08 1217.34  481.61 1270.59  492.99 1642.22  504.17
 3345.13  504.61 3379.14  480.43  3495.4  480.39 3530.82  497.68 3825.93  491.79
 4002.17  498.93 4092.24  483.51 4210.62  480.29 4331.85  496.83 4533.62  497.95
  4676.1  478.86  5644.9  474.94 5821.76  496.16 5972.63  499.58 6031.15  469.52
  6093.2   464.9 6440.01  499.81 7033.03  502.27 7160.27  512.52 7187.94  523.56
#Mann= 3 ,0,0
    -700     .07       0 5972.63    .055       0 6440.01     .06       0
#XS Ineff= 3 ,-1
    -700       0     520       0    2088   503.5    2088    5836     495
Permanent Ineff=
       F       T       T
Bank Sta=5972.63,6440.01
XS Rating Curve= 0 ,0
Exp/Cntr=0.3,0.1

Type RM Length L Ch R = 1 ,190795  ,5,394,616
BEGIN DESCRIPTION:
This cross section corresponds to cross section 190850 of the non-georeferenced CDC model which was the source of this model.
END DESCRIPTION:
XS GIS Cut Line= 6
  2353565.956683 6972477.4829845 2354046.7762485 6969402.5125301
 2354448.1848144 6966835.3648757 2354315.9538162   6966164.24788
 2353868.8366297 6965909.4975494 2353703.2560966 6965227.3501749
#Sta/Elev= 30
       0  509.16  175.37  483.55  345.87  481.05 1066.59   481.7 1154.68  497.65
 1249.49  481.85 1276.82  493.41 1673.24  504.68 3024.75  497.83 3268.02  500.41
 3298.54  508.16 3388.31  504.54 3424.13  480.39 4232.66  480.61 4274.88  490.77
 4456.81  499.76 4582.46  496.35 4672.22  479.96 5097.04   474.8 5223.47  474.98
  5489.5  497.04 5696.43  486.85 6466.94  495.36 6523.81  480.92 6535.53   469.5
 6586.55  464.48 6827.82  494.95 7326.43  503.73 7535.27  521.21 7611.25  537.75
#Mann= 3 ,0,0
       0     .07       0 6466.94     .05       0 6827.82     .07       0
#XS Ineff= 2 ,-1
       0    2144   503.5    2144    5489     495
Permanent Ineff=
       T       T
Bank Sta=6466.94,6827.82
XS Rating Curve= 0 ,0
Exp/Cntr=0.3,0.1

Type RM Length L Ch R = 1 ,190401  ,1,181,319
BEGIN DESCRIPTION:
This cross section corresponds to cross section 190456 of the non-georeferenced CDC model which was the source of this model.
END DESCRIPTION:
XS GIS Cut Line= 6
  2353570.896656 6972478.2554258 2354051.7162213 6969403.2849736
 2354317.7046715 6967702.1903658 2354448.8880042 6966863.2331041
 2354508.9223442 6966479.2914287  2354382.983564 6965311.0014349
#Sta/Elev= 30
       0   509.1  115.02  488.27  333.58  481.16 1070.24  482.03 1156.45  497.47
 1238.06  481.67 1280.55  491.77 1552.48  503.18 2203.02  505.69  3028.6   497.9
 3308.18  507.85 3389.58  504.58 3425.07  480.58 4232.14  480.55 4454.99  500.25
 4583.56  496.13 4670.93  480.03 5096.61   474.8 5482.09   497.1 5727.24  486.18
 6335.81  483.95 6401.47  495.59 6512.03   493.3 6717.22   464.5 6771.75  469.52
 6799.31  493.64 6976.88  494.42    7053  508.67 7159.46   503.7 7246.92  523.51
#Mann= 3 ,0,0
       0     .07       0 6512.03     .05       0 6799.31     .07       0
#XS Ineff= 2 ,-1
       0    2140   503.5    2140    5482     495
Permanent Ineff=
       T       T
Bank Sta=6512.03,6799.31
XS Rating Curve= 0 ,0
Exp/Cntr=0.3,0.1

Type RM Length L Ch R = 1 ,190220  ,1,161,285
BEGIN DESCRIPTION:
This cross section corresponds to cross section 190275 of the non-georeferenced CDC model which was the source of this model.
---------------------------------------------------------------------
CDC FW021297-1 Randol Mill Road
Located in ROB.
Cross-sections 190275 - 205240
---------------------------------------------------------------------
END DESCRIPTION:
XS GIS Cut Line= 6
  2353575.836629 6972479.0278671  2354056.656194 6969404.0574172
 2354322.6446458 6967702.9627996 2354453.8279779 6966864.0055417
 2354510.9875144 6966498.4492909 2354783.9703103 6965058.0982749
#Sta/Elev= 30
       0  509.18  156.65  485.75  289.52  481.59 1073.51  482.16 1158.47  497.29
  1248.1  481.67  1271.9  491.53 1548.96   503.2  2145.3  505.89 3032.45  497.96
  3303.7   507.2 3389.61  504.67    3426  480.78  4231.6  480.49 4455.97  499.91
 4583.31  496.01 4672.98  479.95 5096.75  474.81 5474.35  497.09 5681.61  486.21
 6332.68  483.85 6412.19  497.19 6506.91  494.69 6633.52     464 6699.51  469.43
 6713.28  486.03 6743.96  495.03 7082.81  507.67 7377.54  496.23 7519.24  513.74
#Mann= 3 ,-1,0
       0     .07       0 6506.91     .05       0 6743.96     .07       0
#XS Ineff= 2 ,-1
       0    2145   503.5    2145    5474     495
Permanent Ineff=
       T       T
#Block Obstruct= 2 ,-1
                            7082    7471     507
Bank Sta=6506.91,6743.96
XS Rating Curve= 0 ,0
Exp/Cntr=0.3,0.1

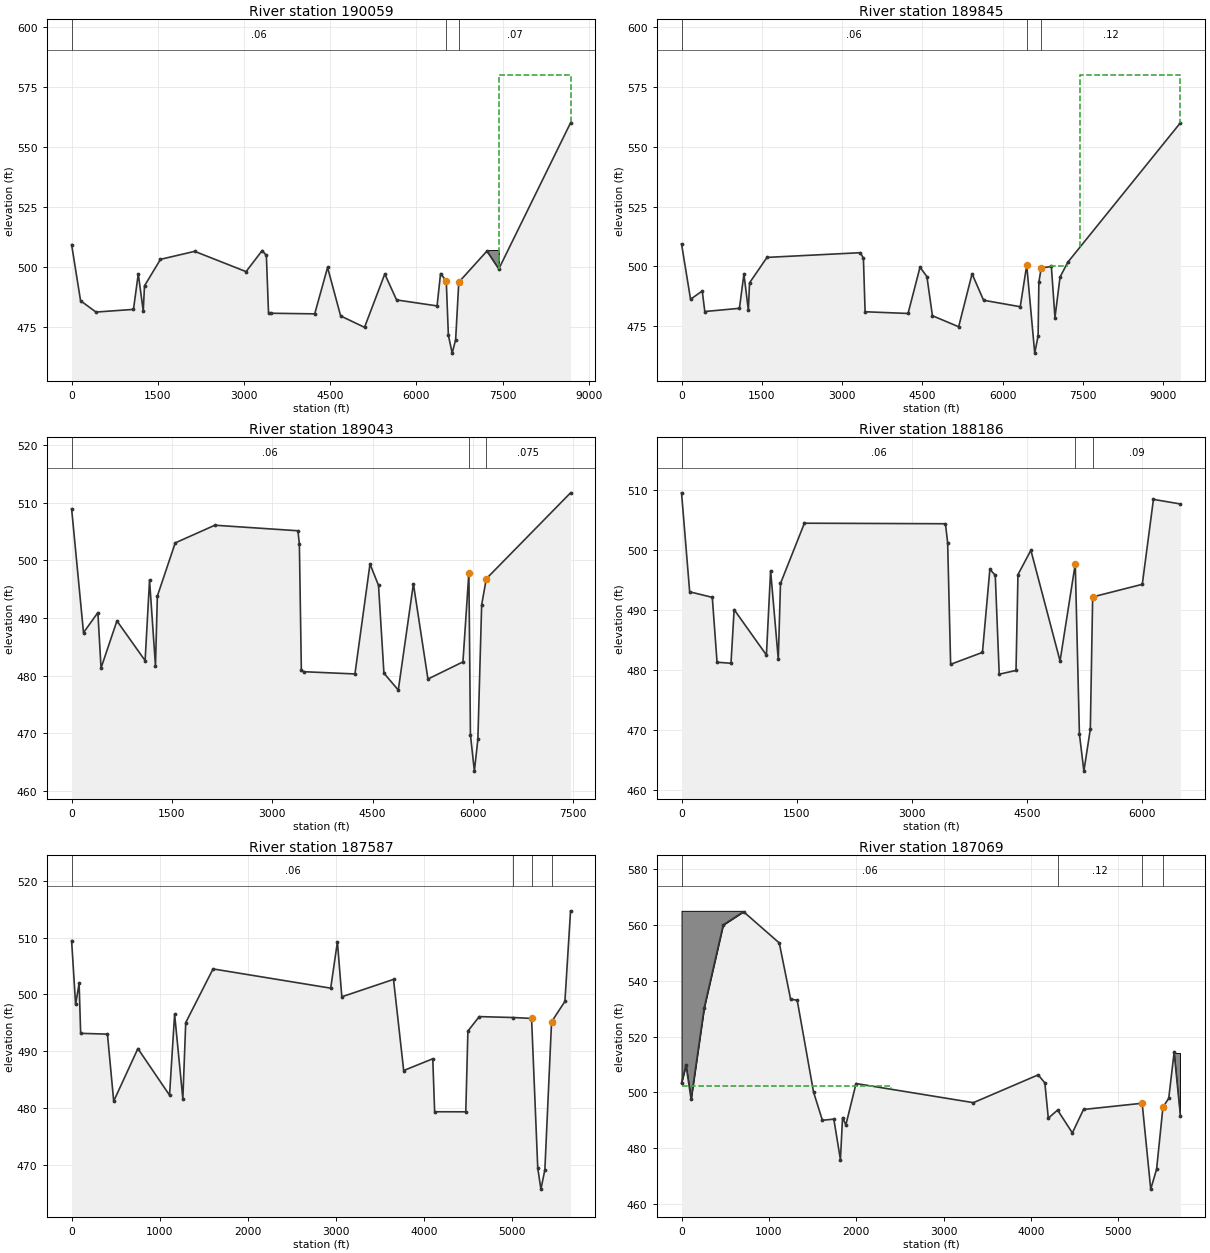
Type RM Length L Ch R = 1 ,190059  ,1,213,381
BEGIN DESCRIPTION:
This cross section corresponds to cross section 190115 of the non-georeferenced CDC model which was the source of this model.
END DESCRIPTION:
XS GIS Cut Line= 6
  2353580.776603 6972479.8003084 2354061.5961679 6969404.8298539
 2354327.5846207 6967703.7352294 2354518.2680876 6966484.2527345
 2355141.8264285 6965268.36204132356387.498169226965175.35615251
#Sta/Elev= 30
       0  509.27  156.15  485.88  423.91  481.18 1076.79  482.29 1160.49  497.11
 1246.54  481.62 1268.72  492.12 1547.06  503.14  2142.1  506.47  3036.3  498.02
 3316.84   506.8 3389.63  504.77 3426.94  480.97 3473.23  480.68 4231.08  480.43
  4455.1  499.77 4682.52  479.56 5098.08  474.82 5450.68  497.03  5656.1  486.23
    6361  483.74 6421.42  497.21 6520.72  494.14 6557.71   471.5 6623.91  464.07
 6683.91  469.66  6738.8  493.62 7228.24  506.57 7434.86  499.13    8684     560
#Mann= 3 ,0,0
       0     .06       0 6520.72     .05       0  6738.8     .07       0
#XS Ineff= 3 ,-1
 7434.86    8684     580       0    2142   503.5    2142    5467     495
Permanent Ineff=
       F       T       T
#Block Obstruct= 2 ,-1
                            7228 7434.86     507
Bank Sta=6520.72,6738.8
XS Rating Curve= 0 ,0
Exp/Cntr=0.3,0.1

Type RM Length L Ch R = 1 ,189845  ,1,803,909
BEGIN DESCRIPTION:
This cross section corresponds to cross section 189901 of the non-georeferenced CDC model which was the source of this model.
END DESCRIPTION:
XS GIS Cut Line= 6
   2353582.51789 6972482.2357489 2353586.2020718 6972477.4678726
 2354066.5361417 6969405.6022906 2354522.7915073 6966487.6891884
 2355539.0205824 6965561.33068952357363.778471166965104.81204488
#Sta/Elev= 30
       0   509.4   168.6  486.31  387.15  489.74  434.83  481.18  1082.1  482.52
 1166.09  496.83 1249.35  481.64 1270.99  493.16 1597.54  503.78 3342.72  505.74
 3399.29  503.39 3430.76  481.08 4233.43  480.37 4456.98  499.67 4585.68  495.78
 4688.84  479.43 5179.28  474.82 5430.01  496.91 5644.99  485.89 6330.29  483.18
 6451.17  500.51 6600.84  463.81 6663.77  470.97 6678.48  493.45 6722.35  499.35
 6911.75     500 6979.17  478.61 7073.91  495.56 7218.78  501.75 9324.67     560
#Mann= 3 ,0,0
       0     .06       0 6451.17     .05       0 6722.35     .12       0
#XS Ineff= 4 ,-1
 7443.67 9324.67     580       0    2074   503.6    6898    7218   500.2
    2074    5430     495
Permanent Ineff=
       F       T       T       T
Bank Sta=6451.17,6722.35
XS Rating Curve= 0 ,0
Exp/Cntr=0.3,0.1

Type RM Length L Ch R = 1 ,189043  ,739,856,528
BEGIN DESCRIPTION:
This cross section corresponds to cross section 189097 of the non-georeferenced CDC model which was the source of this model.
END DESCRIPTION:
XS GIS Cut Line= 6
  2353583.991303 6972482.6603119 2353590.8445572 6972480.1428294
 2354341.7134457 6967678.1069597 2354860.0492788 6967002.4654647
 2355765.3872703 6966609.4866348  2356461.301574 6966320.0472803
#Sta/Elev= 30
       0  508.92  177.87  487.46  392.64  490.94  440.08  481.34  677.63   489.5
 1098.92  482.62 1165.15  496.57 1253.87  481.72 1281.94   493.8 1549.34  503.01
 2142.02  506.07 3383.74  505.11 3405.36   502.8 3434.92  481.03 3468.25   480.7
  4236.1  480.31 4461.13  499.34 4588.63  495.66 4669.68  480.44 4884.29  477.52
 5110.34  495.92 5327.62  479.43 5851.01   482.4 5939.63  497.83 5963.16  469.77
 6021.95  463.48 6074.14  468.98 6130.96  492.31 6200.58   496.8 7459.91  511.68
#Mann= 3 ,0,0
       0     .06       0 5939.63     .05       0 6200.58    .075       0
#XS Ineff= 2 ,-1
       0    2078   503.5    2078    5110     495
Permanent Ineff=
       T       T
Bank Sta=5939.63,6200.58
XS Rating Curve= 0 ,0
Exp/Cntr=0.3,0.1

Type RM Length L Ch R = 1 ,188186  ,510,599,593
BEGIN DESCRIPTION:
This cross section corresponds to cross section 188241 of the non-georeferenced CDC model which was the source of this model.
END DESCRIPTION:
XS GIS Cut Line= 6
  2353581.795535 6972484.7269168 2353595.8144979   6972480.72362
  2353971.235672 6970079.8026428 2354082.5483857 6969367.9295718
 2355596.2065314 6967255.8948639 2356139.0513741 6966756.1962577
#Sta/Elev= 30
       0  509.45     106  492.96  400.85  492.04  462.83  481.23  644.41  481.06
  685.35     490 1106.09  482.43 1160.58  496.49 1260.87   481.7 1289.47  494.35
  1601.1  504.39 3438.74   504.3 3467.57  501.17  3506.5  480.88 3921.21  482.87
 4017.81  496.72  4088.1  495.71 4139.76  479.24 4358.53  479.86  4383.9  495.83
 4552.26  499.88 4932.25  481.44 5130.54  497.61 5184.75  469.27 5242.88  463.09
 5326.84  470.11 5357.36  492.11 6003.91  494.21 6149.25  508.36 6501.45  507.59
#Mann= 3 ,-1,0
       0     .06       0 5130.54     .05       0 5357.36     .09       0
#XS Ineff= 2 ,-1
       0    2087  503.35    2087    4606     495
Permanent Ineff=
       T       T
Bank Sta=5130.54,5357.36
XS Rating Curve= 0 ,0
Exp/Cntr=0.3,0.1

Type RM Length L Ch R = 1 ,187587  ,569,518,549
BEGIN DESCRIPTION:
This cross section corresponds to cross section 187647 of the non-georeferenced CDC model which was the source of this model.
END DESCRIPTION:
XS GIS Cut Line= 5
  2353580.503907 6972486.0831262 2353600.7024976 6972481.8284456
 2353982.4950238  6970040.160931  2356037.893289 6967639.7841515
2356048.674190216967628.14697283
#Sta/Elev= 30
       0  509.46   45.35  498.24   85.21  501.97  102.74  493.17   407.1  493.03
  478.08  481.25  753.03  490.49 1112.37   482.3 1170.07  496.54 1263.72  481.65
 1296.32  495.06 1606.63  504.49 2943.26  501.11 3019.47  509.24 3069.56  499.59
 3656.78  502.65 3772.41  486.63 4102.78   488.7 4124.08  479.39 4477.81  479.38
 4501.99  493.57 4630.64  496.11 5014.72  495.95 5225.24  495.79 5295.56  469.46
  5331.3  465.79 5376.07  469.17 5452.24  495.19 5603.94  498.78 5667.98   514.7
#Mann= 4 ,-1,0
       0     .06       0 5014.72     .09       0 5225.24    .035       0
 5452.24     .05       0
#XS Ineff= 2 ,-1
       0    2159  502.55    2159    5225     495
Permanent Ineff=
       T       T
Bank Sta=5225.24,5452.24
XS Rating Curve= 0 ,0
Exp/Cntr=0.3,0.1

Type RM Length L Ch R = 1 ,187069  ,43,43,43
BEGIN DESCRIPTION:
This cross section corresponds to cross section 187126 of the non-georeferenced CDC model which was the source of this model.
END DESCRIPTION:
XS GIS Cut Line= 6
   2355030.20067 6973284.3490503 2355280.5893523 6970196.0734002
 2355522.6350467 6969272.7090083 2355505.8401202 6968946.4146536
 2356036.5789468 6968424.6031872 2356432.0792441  6967988.981145
#Sta/Elev= 30
       0  503.41   50.84  509.79  109.41   497.6  260.38  530.39  476.96  559.94
  709.88   564.7 1118.95   553.5 1248.57  533.42 1324.54  532.98 1511.29  500.15
 1612.46  490.04 1743.67  490.44 1819.25  475.95 1843.53  490.99 1881.54  488.39
 1998.17  503.18 3341.56  496.34  4083.6  506.29 4159.82   503.4 4199.24  490.79
  4305.7  493.69  4474.6  485.52 4602.23   493.9 5273.85  496.13 5371.85  465.39
 5439.07  472.53 5511.69  494.67 5578.13  497.94 5639.62  514.31 5712.37  491.52
#Mann= 4 ,-1,0
       0     .06       0  4305.7     .12       0 5273.85    .035       0
 5511.69     .08       0
#XS Ineff= 2 , 0
       0    2399   502.3               0
Permanent Ineff=
       T       F
#Block Obstruct= 2 ,-1
       0     704     565    5639    5712     514
Bank Sta=5273.85,5511.69
XS Rating Curve= 0 ,0
Exp/Cntr=0.3,0.1