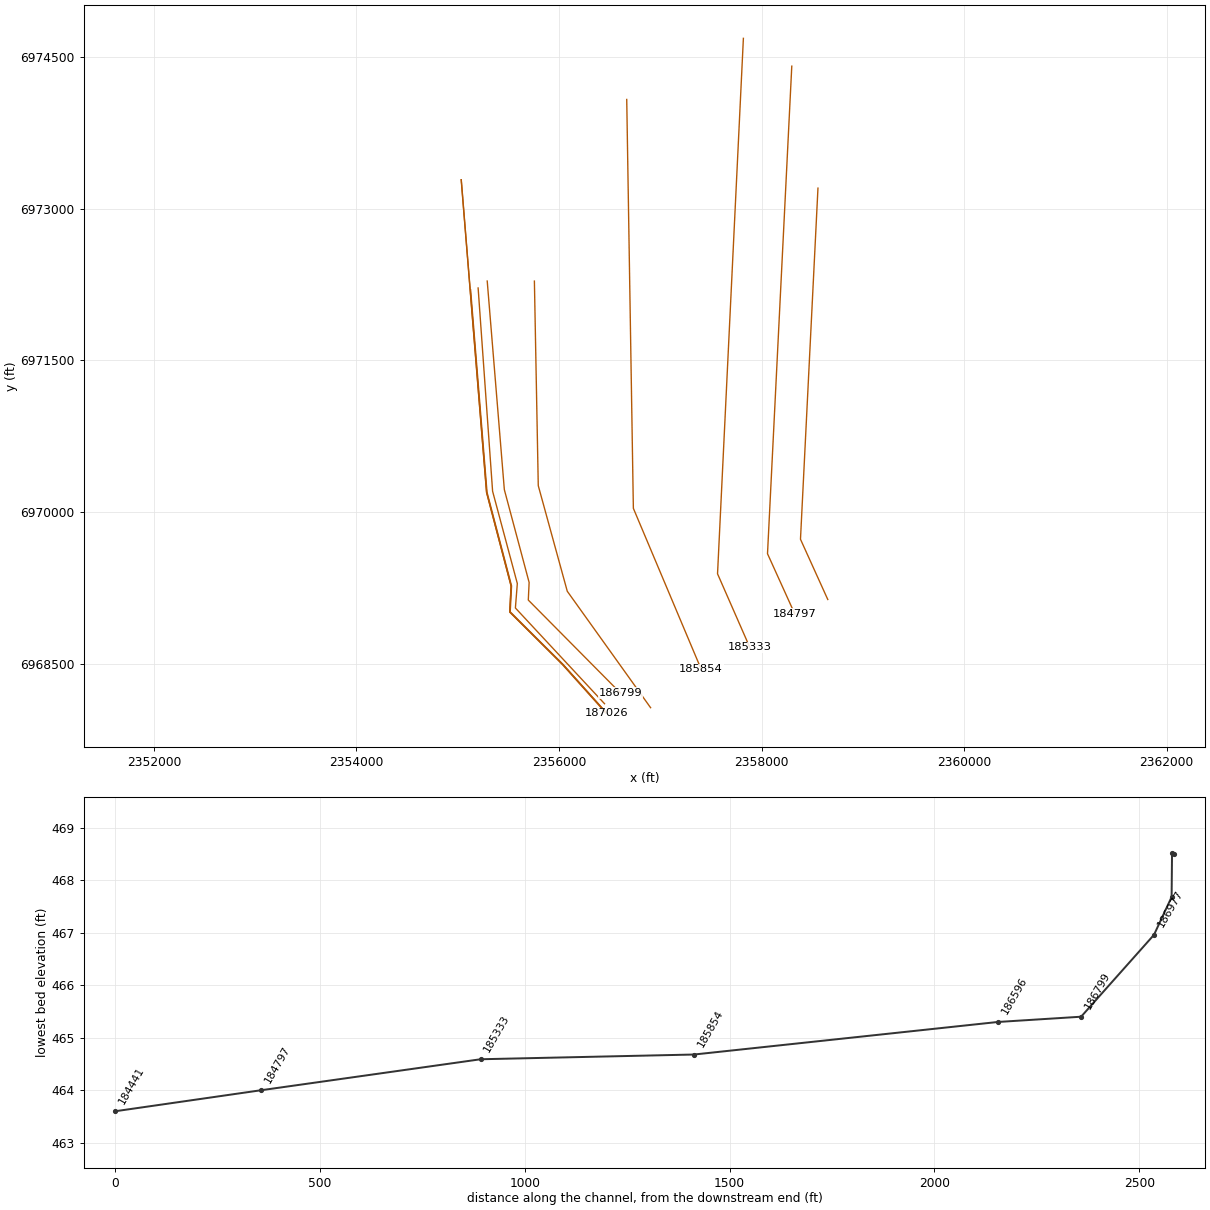
HEC-RAS study CDC_Consolidated_Model.prj: Upper Trinity CDC Consolidated Model

--- CDC_Consolidated_Model.g01 (geometry) --- (continued)

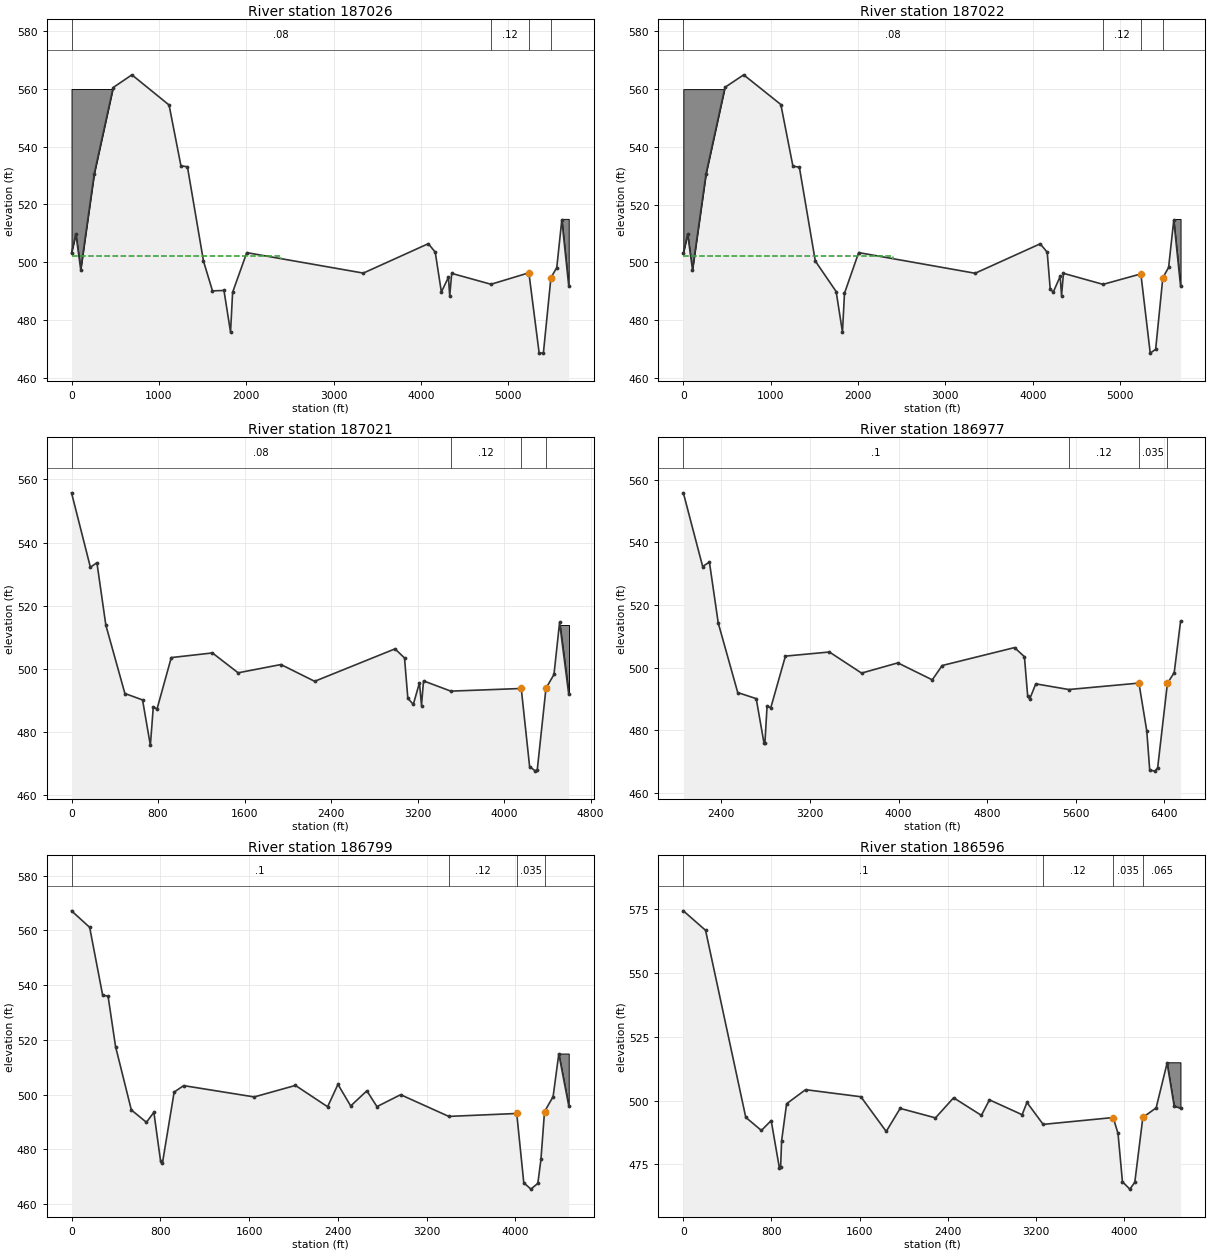
Type RM Length L Ch R = 1 ,187026  ,4,4,4
BEGIN DESCRIPTION:
This cross section corresponds to cross section 187080 of the non-georeferenced CDC model which was the source of this model.
END DESCRIPTION:
XS GIS Cut Line= 6
  2355034.187587 6973284.6722984 2355284.5478373  6970196.747333
 2355526.6616585 6969273.1230483 2355513.3928139  6969015.339526
 2356035.0545063 6968495.8877612 2356466.7776305 6968014.9053763
#Sta/Elev= 30
       0  503.24   49.53  509.82  105.24  497.43  260.12  530.62  476.48  560.48
  691.35  564.89 1116.93  554.44 1252.75  533.39 1327.21  533.04 1511.03  500.37
 1613.98  490.07 1745.62   490.2 1820.96  475.76 1844.45  489.57  2006.8   503.3
 3341.13  496.22 4085.83  506.41 4164.83  503.47 4235.12  489.66 4315.64  494.78
 4330.75  488.38  4353.4  496.12 4803.16  492.35 5237.14  496.32 5354.82   468.5
 5403.08   468.5 5489.58  494.65  5556.4  498.11 5614.38  514.71 5693.55  491.76
#Mann= 4 ,-1,0
       0     .08       0 4803.16     .12       0 5237.14    .035       0
 5489.58     .05       0
#XS Ineff= 2 , 0
       0    2396   502.3               0
Permanent Ineff=
       T       F
#Block Obstruct= 2 ,-1
       0     516     560    5614    5693     515
Bank Sta=5237.14,5489.58
XS Rating Curve= 0 ,0
Exp/Cntr=0.3,0.1

Type RM Length L Ch R = 1 ,187022  ,1,1,1
BEGIN DESCRIPTION:
This cross section corresponds to cross section 187076 of the non-georeferenced CDC model which was the source of this model.
END DESCRIPTION:
XS GIS Cut Line= 6
  2355035.184316 6973284.7531104 2355285.5374585 6970196.9158162
 2355527.6683105 6969273.2265619 2355514.4145365 6969015.7359138
 2356038.0448299 6968498.5444441 2356469.6945313 6968017.6424713
#Sta/Elev= 30
       0   503.2   49.21  509.83  104.83  497.43  260.06  530.68  476.36  560.62
  691.03  564.96 1116.42  554.67 1255.07  533.25 1328.19     533 1510.97  500.43
 1749.73  489.85 1822.09  475.76 1845.08  489.26 2007.47  503.35 3341.02  496.19
 4086.21   506.4 4166.09  503.49 4200.56  490.74  4235.2  489.65 4314.54   495.1
 4330.31  488.39  4352.1  496.17 4805.91  492.34 5238.52  495.97 5345.77  468.51
 5407.83  469.83 5490.04  494.64  5556.1  498.21 5615.22   514.6 5692.93  491.83
#Mann= 4 ,-1,0
       0     .08       0 4805.91     .12       0 5238.52    .035       0
 5490.04     .05       0
#XS Ineff= 2 , 0
       0    2395  502.25               0
Permanent Ineff=
       T       F
#Block Obstruct= 3 ,-1
       0     740     560                            5615 5692.93     515
Bank Sta=5238.52,5490.04
XS Rating Curve= 0 ,0
Exp/Cntr=0.3,0.1

Type RM Length L Ch R = 1 ,187021  ,43,43,43
BEGIN DESCRIPTION:
This cross section corresponds to cross section 187075 of the non-georeferenced CDC model which was the source of this model.
END DESCRIPTION:
XS GIS Cut Line= 6
    2355127.3757 6972197.1689393 2355289.4959434  6970197.589749
 2355531.6949215 6969273.6406049 2355518.5014268 6969017.3214648
 2356038.8417115 6968499.1848483 2356470.4237565 6968018.3267451
#Sta/Elev= 30
       0  555.77  174.51  532.21  234.91  533.65  317.32   513.9  493.54  492.25
  656.89  490.22  729.26  475.85   756.2  488.05  790.39   487.3  922.41  503.62
 1303.07  505.09 1540.76   498.8  1936.9  501.42 2248.44  496.11 2991.78  506.38
 3079.52   503.5 3110.52   490.7 3160.91  488.81 3217.99  495.65 3236.73  488.42
 3255.28  496.24    3508     493 4159.15  493.84 4236.47  469.14 4290.62  467.68
 4307.57  468.18 4387.91  493.91 4461.84  498.28 4513.72  514.73 4598.45  491.96
#Mann= 4 ,-1,0
       0     .08       0    3508     .12       0 4159.15    .035       0
 4387.91    .065       0
#XS Ineff= 2 , 0
       0    1303   502.1               0
Permanent Ineff=
       T       F
#Block Obstruct= 1 ,-1
    4513 4598.45     514
Bank Sta=4159.15,4387.91
XS Rating Curve= 0 ,0
Exp/Cntr=0.3,0.1

Type RM Length L Ch R = 1 ,186977  ,176,178,178
BEGIN DESCRIPTION:
This cross section corresponds to cross section 187025 of the non-georeferenced CDC model which was the source of this model.
END DESCRIPTION:
XS GIS Cut Line= 6
  2355201.526031 6972215.7832028      2355279.36      6971122.88
      2355344.47      6970208.64      2355588.63      6969297.12
      2355569.64      6969055.67  2356449.925915 6968110.2180641
#Sta/Elev= 30
    2056  555.76 2230.47  532.24 2291.39  533.68 2371.23  514.22 2547.28  492.03
 2714.14  490.09 2784.76  475.83 2792.64  475.94 2812.17  487.74 2845.76  487.19
 2977.72  503.66  3374.9  504.97 3665.66  498.24    3993   501.5 4303.61  496.09
 4393.71  500.66 5046.75  506.38 5135.99  503.46 5165.48   490.9 5184.14     490
  5238.5  494.81    5537     493 6170.02  495.05  6240.6  479.85 6267.54   467.3
  6314.8  466.96 6339.24  468.06  6427.1  494.93  6488.7  498.42 6545.89  514.71
#Mann= 4 ,-1,0
    2056      .1       0    5537     .12       0 6170.02    .035       0
  6427.1    .065       0
#XS Ineff= 2 , 0
       0    3361   502.1               0
Permanent Ineff=
       T       F
Bank Sta=6170.02,6427.1
XS Rating Curve= 0 ,0
Exp/Cntr=0.3,0.1

Type RM Length L Ch R = 1 ,186799  ,199,203,207
BEGIN DESCRIPTION:
This cross section corresponds to cross section 186871 of the non-georeferenced CDC model which was the source of this model.
END DESCRIPTION:
XS GIS Cut Line= 6
  2355291.337509 6972284.4097219  2355368.410033 6971345.3615282
 2355460.4239571 6970224.2679699 2355705.2154622 6969308.0352223
 2355696.9690877 6969133.9899667 2356606.2966653 6968216.7076806
#Sta/Elev= 30
       0  567.19  163.41  561.15   280.8  536.28  329.12  536.01  397.01  517.52
  539.14  494.35  674.96  489.85  742.19   493.5  802.67  475.63  819.61  474.99
  924.84  500.89 1010.44  503.26 1646.52  499.12 2018.03  503.33 2307.97  495.53
 2401.24  503.71 2515.92  495.82 2661.76  501.36 2752.78  495.58 2966.05  499.94
    3400     492  4012.5  493.07 4076.07  467.73    4140   465.4 4202.74  467.51
 4230.74  476.24 4262.89  493.74 4340.25  499.23 4391.71  514.86  4481.3  495.89
#Mann= 4 ,-1,0
       0      .1       0    3400     .12       0  4012.5    .035       0
 4262.89     .06       0
#XS Ineff= 2 , 0
       0    1010   502.1               0
Permanent Ineff=
       T       F
#Block Obstruct= 2 ,-1
                            4391    4481     515
Bank Sta=4012.5,4262.89
XS Rating Curve= 0 ,0
Exp/Cntr=0.3,0.1

Type RM Length L Ch R = 1 ,186596  ,891,742,673
BEGIN DESCRIPTION:
This cross section corresponds to cross section 186691 of the non-georeferenced CDC model which was the source of this model.
END DESCRIPTION:
XS GIS Cut Line= 6
   2355757.17558 6972283.8549662     2355775.952     6971293.699
     2355795.483     6970263.751     2356081.942     6969220.782
 2356631.1696476 6968453.2608311  2356904.680669 6968071.0413639
#Sta/Elev= 30
       0  574.35  201.97  566.71  566.98  493.44  708.77  488.29  797.94  492.16
  871.79  473.73  883.72  474.02  892.38  484.18  937.86  498.76 1110.26  504.27
 1612.38   501.5 1842.68   487.9 1969.13  496.94 2289.95  493.22 2454.63  501.09
 2706.86  494.21 2780.51  500.28 3076.98  494.46 3120.84  499.27 3268.03  490.67
 3903.97  493.35 3947.96  487.11 3988.07   468.2    4055   465.3 4100.25  467.97
 4173.45  493.38 4294.17  497.15 4393.54  514.67 4458.17  497.75 4515.85  497.08
#Mann= 4 ,-1,0
       0      .1       0 3268.03     .12       0 3903.97    .035       0
 4173.45    .065       0
#XS Ineff= 2 , 0
       0    1118   502.2               0
Permanent Ineff=
       T       F
#Block Obstruct= 2 ,-1
                            4393    4515     515
Bank Sta=3903.97,4173.45
XS Rating Curve= 0 ,0
Exp/Cntr=0.3,0.1

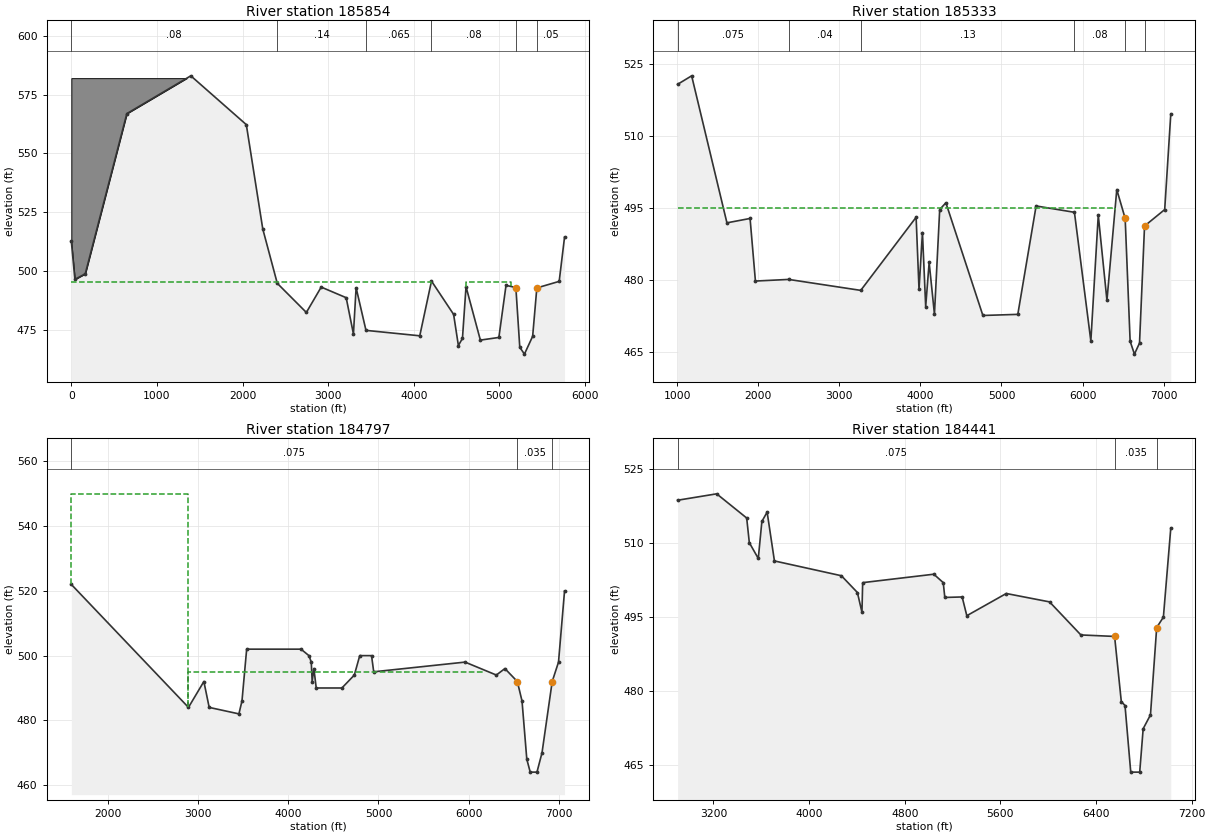
Type RM Length L Ch R = 1 ,185854  ,521,521,521
BEGIN DESCRIPTION:
This cross section corresponds to cross section 185909 of the non-georeferenced CDC model which was the source of this model.
END DESCRIPTION:
XS GIS Cut Line= 3
   2356669.05006 6974077.4875984   2356734.60514   6970039.70305
   2357403.79507   6968451.89586
#Sta/Elev= 30
       0  512.68    41.7  496.44  162.98  498.85  648.47  566.92 1395.66  582.99
 2044.07  562.24 2236.28  517.89 2405.72  494.78 2745.42  482.39 2918.87  493.18
 3210.55  488.67 3295.37  473.26 3326.57  492.91 3441.88  474.78 4070.08  472.47
 4207.08  495.74 4465.58  481.57 4521.23  468.33 4568.79  471.36 4610.48  493.34
 4778.03  470.64 4994.26  471.77 5077.71  493.91 5192.58     493 5238.41   467.6
 5292.67  464.68 5388.76  472.25 5437.64  492.82 5698.67  495.61 5761.38  514.41
#Mann= 6 ,-1,0
       0     .08       0 2405.72     .14       0 3441.88    .065       0
 4207.08     .08       0 5192.58    .035       0 5437.64     .05       0
#XS Ineff= 3 ,-1
    4610    5134   495.5       0    4200   495.5    4200    4610     485
Permanent Ineff=
       T       T       T
#Block Obstruct= 3 ,-1
                                                       0    1374     582
Bank Sta=5192.58,5437.64
XS Rating Curve= 0 ,0
Exp/Cntr=0.3,0.1

Type RM Length L Ch R = 1 ,185333  ,540,536,538
BEGIN DESCRIPTION:
This cross section corresponds to cross section 185387 of the non-georeferenced CDC model which was the source of this model.
END DESCRIPTION:
XS GIS Cut Line= 4
   2357821.11227 6974681.1805126   2357821.11215   6974681.17802
   2357565.79606   6969393.22108   2357883.33807   6968669.22613
#Sta/Elev= 30
    1004  520.71 1177.57  522.48 1612.87   491.9 1898.34  492.81 1964.31  479.79
 2373.91  480.13 3263.54  477.85 3946.72  493.06 3982.57  478.05 4024.87  489.88
 4064.86  474.49 4107.54  483.67 4172.94  472.89 4237.71  494.67 4313.92  496.07
 4770.52  472.63 5201.29  472.86 5427.11  495.41 5899.92  494.09 6102.38  467.32
 6193.95   493.5 6300.93  475.77 6422.26  498.82 6525.76  492.82 6587.08  467.27
 6640.06  464.59 6702.88  466.89 6764.86  491.24 7013.56  494.66 7088.69  514.58
#Mann= 6 ,-1,0
    1004    .075       0 2373.91     .04       0 3263.54     .13       0
 5899.92     .08       0 6525.76    .035       0 6764.86     .05       0
#XS Ineff= 2 , 0
       0    6400     495               0
Permanent Ineff=
       T       F
Bank Sta=6525.76,6764.86
XS Rating Curve= 0 ,0
Exp/Cntr=0.3,0.1

Type RM Length L Ch R = 1 ,184797  ,356,356,356
BEGIN DESCRIPTION:
This cross section corresponds to cross section 184850 of the non-georeferenced CDC model which was the source of this model.
Added Cross Section
END DESCRIPTION:
XS GIS Cut Line= 4
2358299.041962376974406.54958828  2358234.391604 6973108.1581484
 2358059.2944155  6969591.631768 2358328.8555562 6968996.7379447
#Sta/Elev= 30
    1591     522    2891     484    3062     492    3121     484    3451     482
    3485     486    3537     502    4140     502    4228     500    4254     498
    4264     492    4283     496    4309     490    4594     490    4732     494
    4792     500    4923     500    4947     495    5961     498    6308     494
    6403     496    6541     492    6593     486    6646     468    6684     464
    6759     464    6815     470    6928     492    6998     498    7065     520
#Mann= 3 ,0,0
    1591    .075       0    6541    .035       0    6928     .05       0
#XS Ineff= 2 ,-1
    1591    2891     550    2891    6180     495
Permanent Ineff=
       F       T
Bank Sta=6541,6928
XS Rating Curve= 0 ,0
Exp/Cntr=0.3,0.1

Type RM Length L Ch R = 1 ,184441  ,784,784,784
BEGIN DESCRIPTION:
This cross section corresponds to cross section 184495 of the non-georeferenced CDC model which was the source of this model.
END DESCRIPTION:
XS GIS Cut Line= 3
  2358557.588317  6973201.966854   2358384.92795   6969734.37984
   2358654.48909   6969139.48602
#Sta/Elev= 30
    2900   518.7    3227     520    3478   515.1    3500   510.1    3575   506.9
    3605   514.4    3649   516.3    3710   506.4    4270   503.4    4404     500
    4442     496    4448     502    5043  503.71    5122     502    5135     499
    5280   499.1    5319   495.3    5649   499.8    6011   498.1    6273   491.4
    6555   491.1    6611   477.9    6642   477.1    6690   463.6    6765   463.6
    6794   472.4    6855   475.2    6907   492.9    6963     495    7025   513.1
#Mann= 3 ,0,0
    2900    .075       0    6555    .035       0    6907     .05       0
#XS Ineff= 2 , 0
            6555   491.1    6907           492.9
Permanent Ineff=
       F       F
Bank Sta=6555,6907
XS Rating Curve= 0 ,0
Exp/Cntr=0.3,0.1