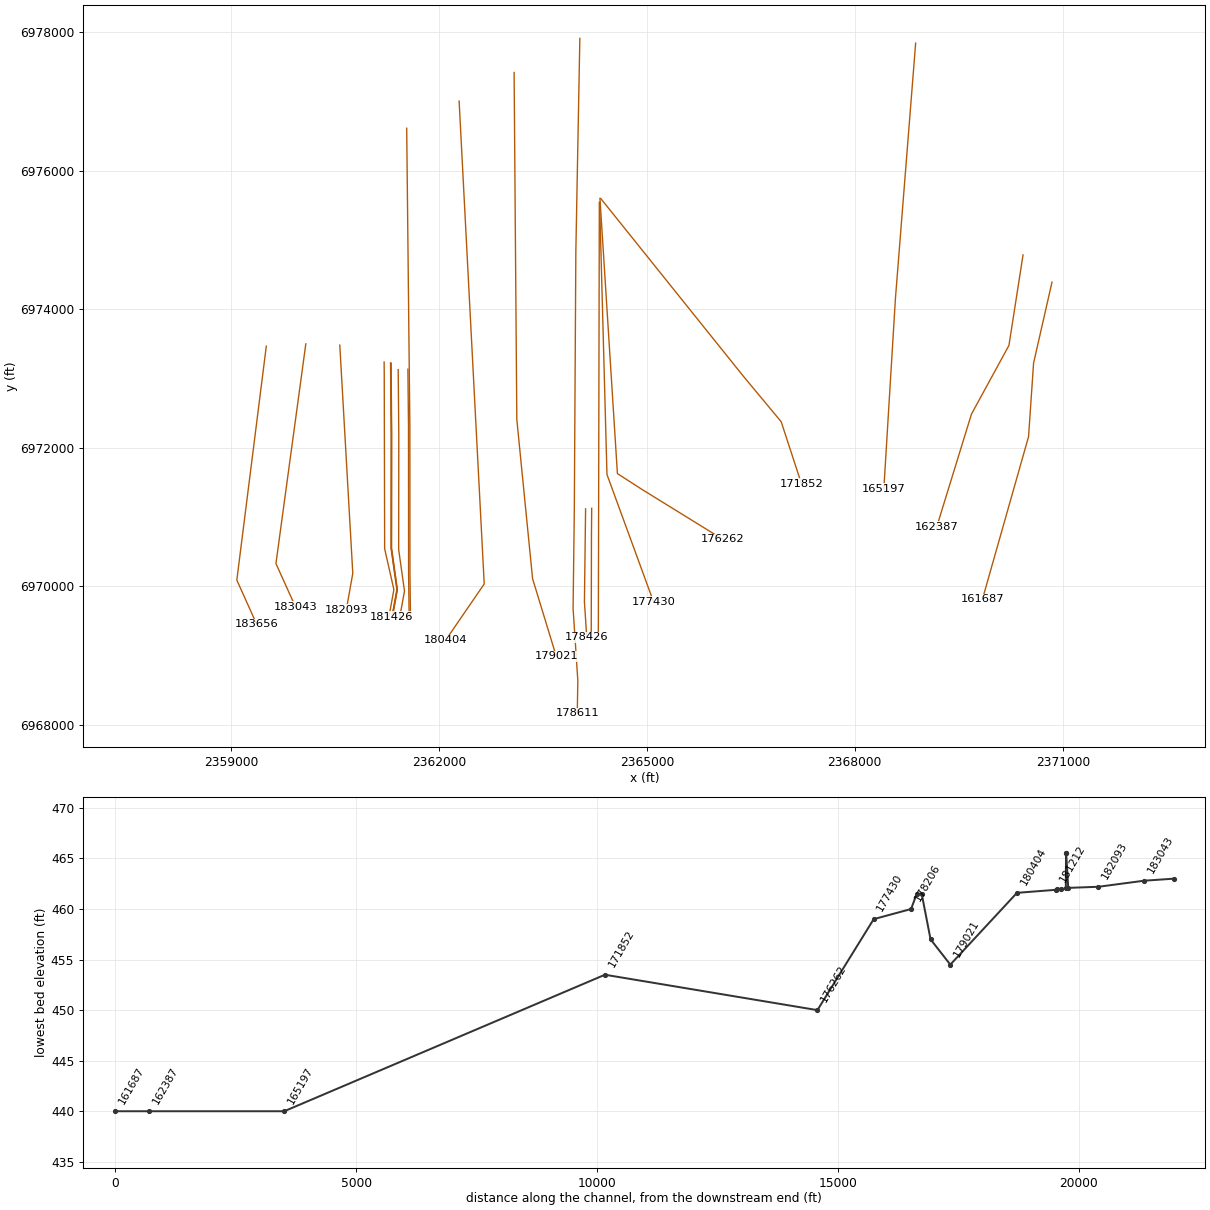
HEC-RAS study CDC_Consolidated_Model.prj: Upper Trinity CDC Consolidated Model

--- CDC_Consolidated_Model.g01 (geometry) --- (continued)

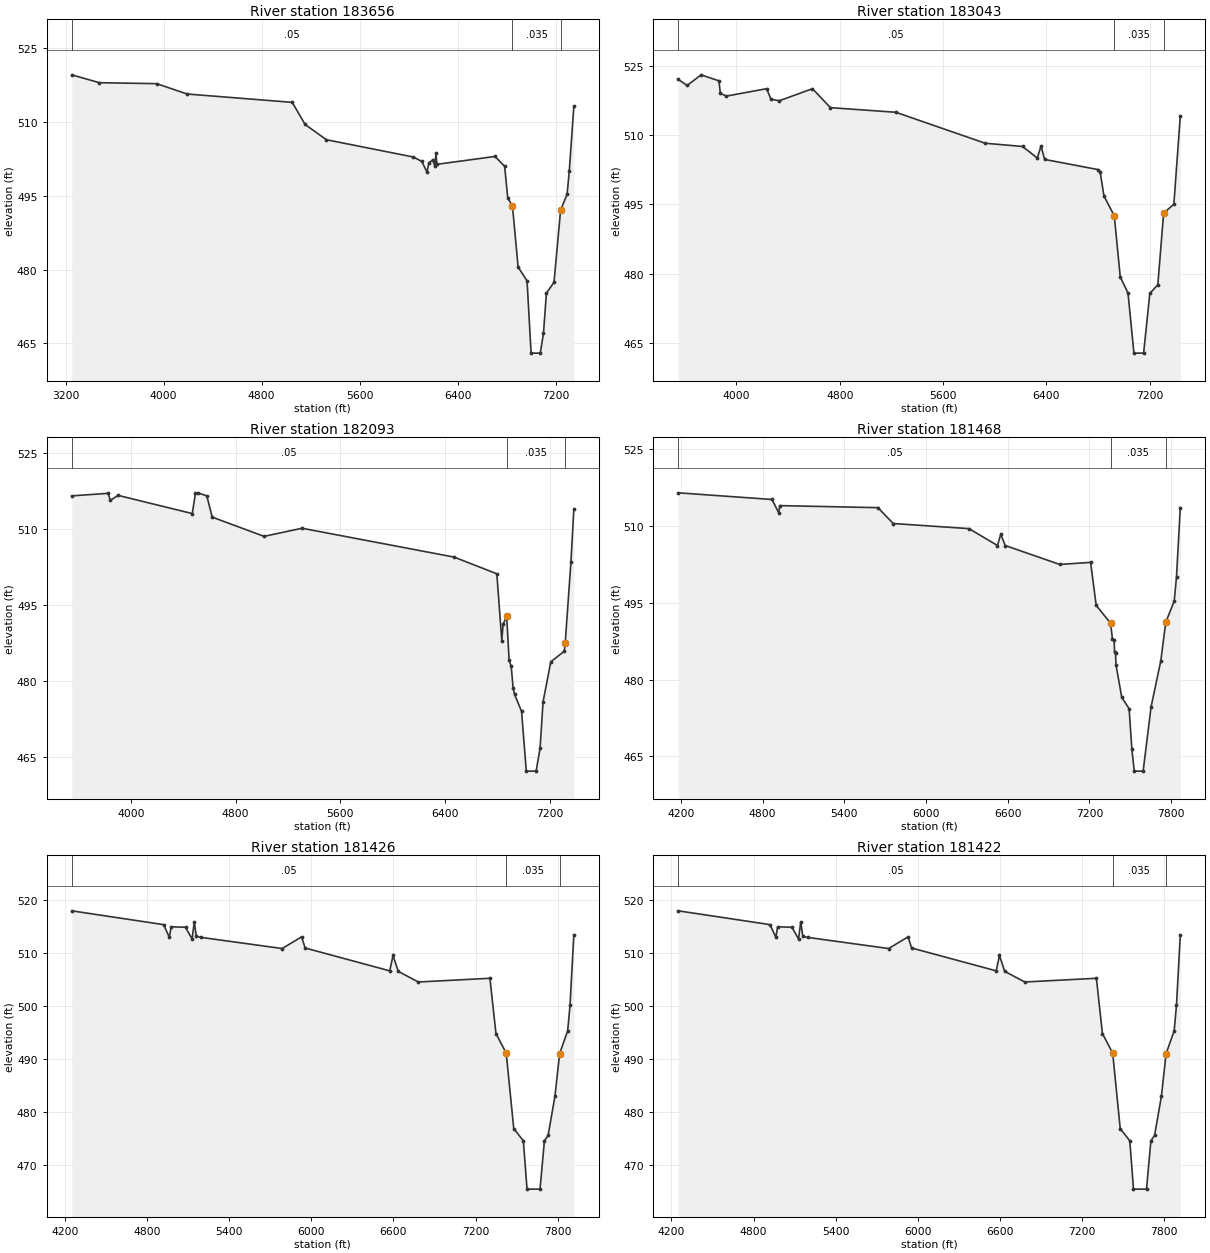
Type RM Length L Ch R = 1 ,183656  ,613,613,613
BEGIN DESCRIPTION:
This cross section corresponds to cross section 183709 of the non-georeferenced CDC model which was the source of this model.
---------------------------------------------------------------------
CDC FW050103-01 Riverbend West Trussway Site
Cross-section 183709 - 185387
---------------------------------------------------------------------
END DESCRIPTION:
XS GIS Cut Line= 3
  2359510.333965 6973466.7569936     2359085.044   6970092.03694
   2359371.13201   6969455.81216
#Sta/Elev= 30
    3250   519.6    3475     518    3944   517.8    4191   515.7    5050     514
    5155   509.5    5329   506.4    6036   502.9    6108     502    6150   499.8
    6165   501.7    6196   502.3    6215     501    6223   503.6    6231   501.4
    6705     503    6784     501    6809   494.6    6848   492.9    6894   480.5
    6967   477.7    7000     463    7075     463    7101     467    7125   475.2
    7187   477.4    7241   492.1    7294   495.3    7312   500.1    7349   513.2
#Mann= 3 ,0,0
    3250     .05       0    6848    .035       0    7241     .05       0
#XS Ineff= 2 , 0
            6848   492.9    7241           492.1
Permanent Ineff=
       F       F
Bank Sta=6848,7241
XS Rating Curve= 0 ,0
Exp/Cntr=0.3,0.1

Type RM Length L Ch R = 1 ,183043  ,1050,950,900
BEGIN DESCRIPTION:
This cross section corresponds to cross section 183096 of the non-georeferenced CDC model which was the source of this model.
END DESCRIPTION:
XS GIS Cut Line= 3
  2360080.302205 6973499.7483181   2359649.32404   6970330.62602
   2359932.37499   6969703.87006
#Sta/Elev= 30
    3550     522    3619   520.7    3727     523    3865   521.7    3876     519
    3923   518.4    4234     520    4268   517.7    4333   517.4    4589     520
    4728   515.9    5234   514.9    5926   508.2    6215   507.5    6329     505
    6358   507.6    6386   504.7    6800   502.5    6816   501.9    6845   496.8
    6925   492.5    6971   479.3    7031   475.8    7077   462.8    7152   462.8
    7200   475.7    7262   477.6    7307   493.1    7386     495    7436   514.1
#Mann= 3 ,0,0
    3550     .05       0    6925    .035       0    7307     .05       0
#XS Ineff= 2 , 0
            6925   492.5    7307           493.1
Permanent Ineff=
       F       F
Bank Sta=6925,7307
XS Rating Curve= 0 ,0
Exp/Cntr=0.3,0.1

Type RM Length L Ch R = 1 ,182093  ,610,625,625
BEGIN DESCRIPTION:
This cross section corresponds to cross section 182146 of the non-georeferenced CDC model which was the source of this model.
END DESCRIPTION:
XS GIS Cut Line= 3
   2360570.38532  6973481.139121   2360758.00785   6970189.29297
   2360664.02707   6969661.78812
#Sta/Elev= 30
    3550   516.6    3828   517.1    3844   515.7    3903   516.7    4470   513.1
    4494   517.1    4511   517.2    4581   516.6    4622   512.4    5018   508.6
    5308   510.2    6469   504.5    6795   501.2    6833     488    6843   491.2
    6870   492.8    6889   484.1    6905   482.9    6919   478.7    6930   477.4
    6984     474    7020   462.2    7095   462.2    7125   466.7    7148   475.9
    7207   483.8    7310   485.9    7317   487.5    7361   503.6    7383     514
#Mann= 3 ,0,0
    3550     .05       0    6870    .035       0    7317     .05       0
#XS Ineff= 2 , 0
            6870   492.8    7317           487.5
Permanent Ineff=
       F       F
Bank Sta=6870,7317
XS Rating Curve= 0 ,0
Exp/Cntr=0.3,0.1

Type RM Length L Ch R = 1 ,181468  ,42,42,42
BEGIN DESCRIPTION:
This cross section corresponds to cross section 181521 of the non-georeferenced CDC model which was the source of this model.
END DESCRIPTION:
XS GIS Cut Line= 5
  2361210.029294 6973237.9957154   2361211.53516   6973077.56016
   2361217.59715   6970543.71713   2361350.82294   6969954.61497
   2361281.10589   6969571.17315
#Sta/Elev= 30
    4180   516.5    4869   515.2    4918   512.6    4926     514    5647   513.6
    5759   510.5    6316   509.5    6525   506.2    6549   508.4    6582   506.2
    6982   502.5    7209   502.9    7250   494.5    7356     491    7369     488
    7382   487.8    7385   485.3    7392   485.1    7396   482.8    7438   476.5
    7492   474.3    7512   466.4    7530  462.09    7595  462.09    7653   474.6
    7725   483.7    7761   491.2    7823   495.3    7840   500.1    7868   513.6
#Mann= 3 ,0,0
    4180     .05       0    7356    .035       0    7761     .05       0
#XS Ineff= 2 , 0
            7356     491    7761           491.2
Permanent Ineff=
       F       F
Bank Sta=7356,7761
XS Rating Curve= 0 ,0
Exp/Cntr=0.3,0.1

Type RM Length L Ch R = 1 ,181426  ,4,4,4
BEGIN DESCRIPTION:
This cross section corresponds to cross section 181479 of the non-georeferenced CDC model which was the source of this model.
END DESCRIPTION:
XS GIS Cut Line= 6
  2361302.493278 6973221.8763323 2361302.4932784 6973221.8763323
 2361311.6129613 6972207.4595381 2361309.9459713 6970552.1327981
 2361393.7978313 6969955.0716581 2361323.0847213 6969566.1537981
#Sta/Elev= 30
    4250   517.9    4921   515.3    4963   512.9    4976   514.9    5081   514.8
    5129   512.6    5145   515.8    5160   513.1    5195   512.9    5787   510.8
    5929     513    5955   510.9    6573   506.6    6597   509.5    6635   506.5
    6782   504.5    7305   505.2    7349   494.8    7424   491.1    7479   476.9
    7549   474.6    7576   465.5    7671   465.5    7703   474.6    7730   475.6
    7780     483    7814     491    7873   495.3    7890   500.1    7918   513.4
#Mann= 3 ,0,0
    4250     .05       0    7424    .035       0    7814     .05       0
#XS Ineff= 2 , 0
            7424   491.1    7814             491
Permanent Ineff=
       F       F
Bank Sta=7424,7814
XS Rating Curve= 0 ,0
Exp/Cntr=0.3,0.1

Type RM Length L Ch R = 1 ,181422  ,4,4,4
BEGIN DESCRIPTION:
This cross section corresponds to cross section 181475 of the non-georeferenced CDC model which was the source of this model.
END DESCRIPTION:
XS GIS Cut Line= 5
  2361306.421067 6973221.1185436 2361315.5407504 6972206.7017494
 2361313.8737604 6970551.3750094 2361397.7256204 6969954.3138694
 2361327.0125104 6969565.3960094
#Sta/Elev= 30
    4250   517.9    4921   515.3    4963   512.9    4976   514.9    5081   514.8
    5129   512.6    5145   515.8    5160   513.1    5195   512.9    5787   510.8
    5929     513    5955   510.9    6573   506.6    6597   509.5    6635   506.5
    6782   504.5    7305   505.2    7349   494.8    7424   491.1    7479   476.9
    7549   474.6    7576   465.5    7671   465.5    7703   474.6    7730   475.6
    7780     483    7814     491    7873   495.3    7890   500.1    7918   513.4
#Mann= 3 ,0,0
    4250     .05       0    7424    .035       0    7814     .05       0
#XS Ineff= 2 , 0
            7424   491.1    7814             491
Permanent Ineff=
       F       F
Bank Sta=7424,7814
XS Rating Curve= 0 ,0
Exp/Cntr=0.3,0.1

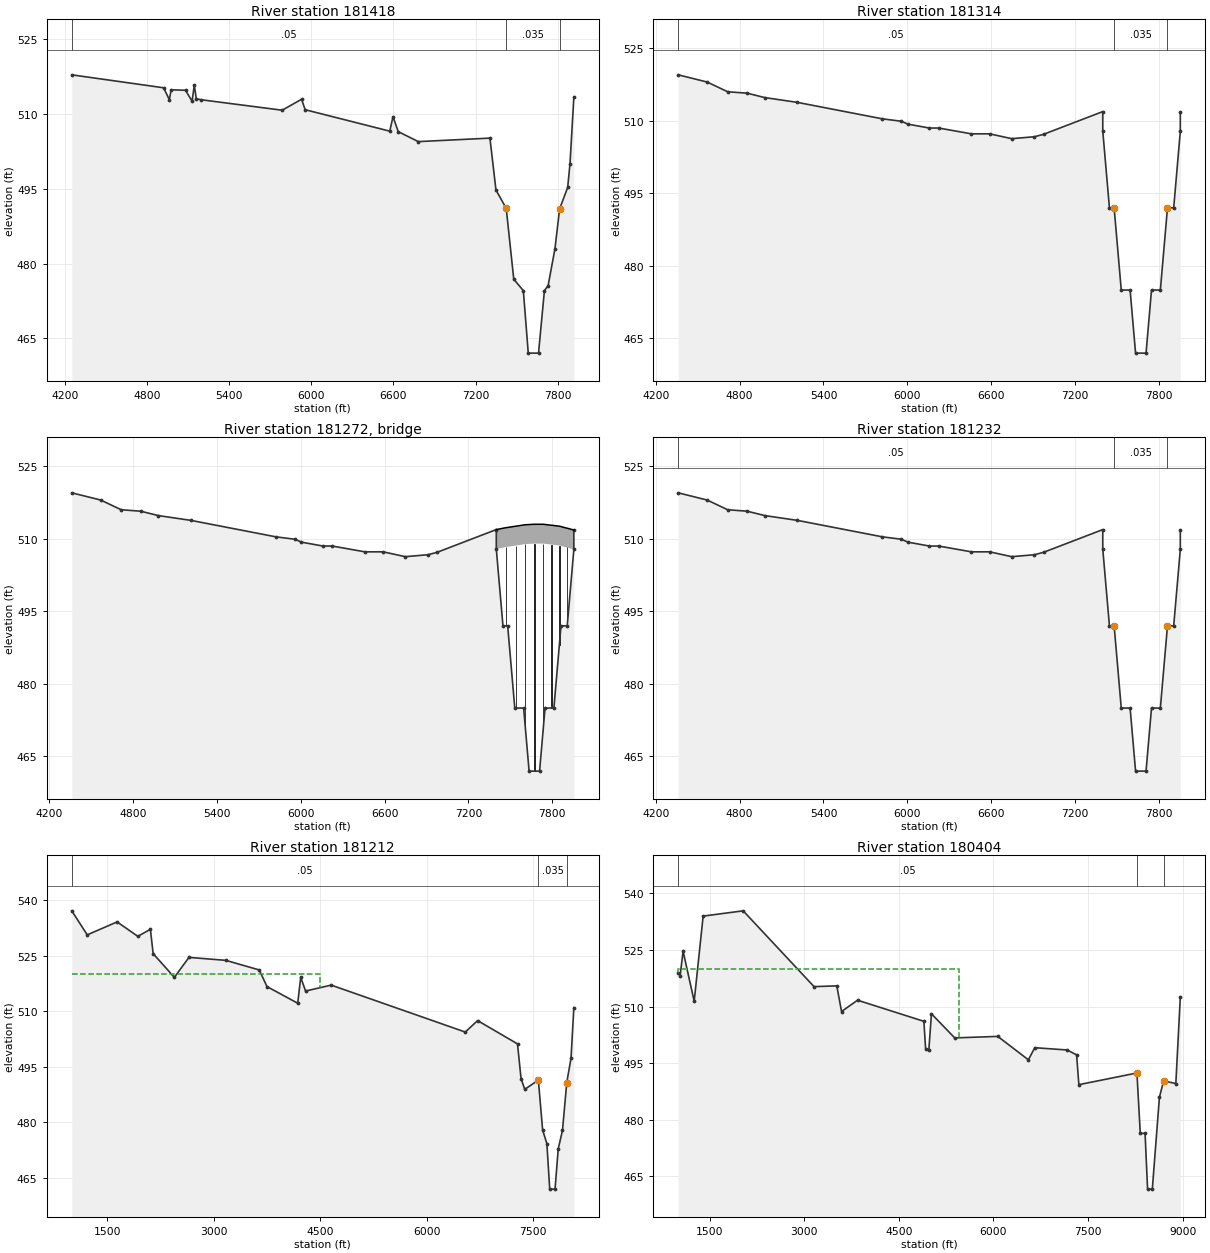
Type RM Length L Ch R = 1 ,181418  ,104,104,104
BEGIN DESCRIPTION:
This cross section corresponds to cross section 181471 of the non-georeferenced CDC model which was the source of this model.
END DESCRIPTION:
XS GIS Cut Line= 5
  2361310.152467 6973220.3986442   2361319.27215   6972205.98185
   2361317.60516   6970550.65511   2361401.45702   6969953.59397
   2361330.74391   6969564.67611
#Sta/Elev= 30
    4250   517.9    4921   515.3    4963   512.9    4976   514.9    5081   514.8
    5129   512.6    5145   515.8    5160   513.1    5195   512.9    5787   510.8
    5929     513    5955   510.9    6573   506.6    6597   509.5    6635   506.5
    6782   504.5    7305   505.2    7349   494.8    7424   491.1    7479   476.9
    7549   474.6    7585  462.06    7660  462.06    7703   474.6    7730   475.6
    7780     483    7814     491    7873   495.3    7890   500.1    7918   513.4
#Mann= 3 ,0,0
    4250     .05       0    7424    .035       0    7814     .05       0
#XS Ineff= 2 , 0
            7424   491.1    7814             491
Permanent Ineff=
       F       F
Bank Sta=7424,7814
XS Rating Curve= 0 ,0
Exp/Cntr=0.3,0.1

Type RM Length L Ch R = 1 ,181314  ,82,82,82
BEGIN DESCRIPTION:
This cross section corresponds to cross section 181367 of the non-georeferenced CDC model which was the source of this model.
END DESCRIPTION:
XS GIS Cut Line= 5
  2361413.135029 6973127.9692752 2361421.6012506 6972186.2394851
 2361419.9342606 6970530.9127451 2361503.7861206 6969933.8516051
 2361433.0730106 6969544.9337451
#Sta/Elev= 30
    4360   519.5    4568     518    4714     516    4854   515.7    4979   514.8
    5214   513.8    5822   510.4    5958   509.9    6005   509.3    6158   508.5
    6225   508.5    6459   507.3    6590   507.3    6748   506.3    6911   506.7
    6976   507.2    7400   511.9    7400   507.9  7447.7     492 7481.43     492
 7532.43     475 7595.81     475 7634.93  461.96 7709.93  461.96 7749.05     475
 7812.43     475 7863.43     492 7907.91     492 7955.31   507.8 7955.31   511.8
#Mann= 3 ,0,0
    4360     .05       0 7481.43    .035       0 7863.43     .05       0
#XS Ineff= 2 , 0
         7481.43     492 7863.43             492
Permanent Ineff=
       F       F
Bank Sta=7481.43,7863.43
XS Rating Curve= 0 ,0
Exp/Cntr=0.5,0.3

Type RM Length L Ch R = 3 ,181272  ,,,
BEGIN DESCRIPTION:
Handley-Ederville Road
END DESCRIPTION:
Node Name=Handley-Edervill
Bridge Culvert--1,0,-1,-1, 0
Deck Dist Width WeirC Skew NumUp NumDn MinLoCord MaxHiCord MaxSubmerge Is_Ogee
1,80,2.6,0, 18, 18, , , 0.95, 0, ,,,
    7400 7469.53 7472.03 7538.75 7541.25  7606.1  7608.6 7671.18 7673.68  7733.8
  7736.3 7793.67 7796.17 7850.51 7853.01 7903.99 7906.49 7955.31
   511.9   512.3   512.3   512.6   512.6   512.9   512.9     513     513     513
     513   512.8   512.8   512.6   512.6   512.2   512.2   511.8
   507.9   508.3   508.3   508.6   508.6   508.9   508.9     509     509     509
     509   508.8   508.8   508.6   508.6   508.2   508.2   507.8
    7400 7469.53 7472.03 7538.75 7541.25  7606.1  7608.6 7671.18 7673.68  7733.8
  7736.3 7793.67 7796.17 7850.51 7853.01 7903.99 7906.49 7955.31
   511.9   512.3   512.3   512.6   512.6   512.9   512.9     513     513     513
     513   512.8   512.8   512.6   512.6   512.2   512.2   511.8
   507.9   508.3   508.3   508.6   508.6   508.9   508.9     509     509     509
     509   508.8   508.8   508.6   508.6   508.2   508.2   507.8
Pier Skew, UpSta & Num, DnSta & Num=  ,7470.78, 2 ,7470.78, 2 , 0 , 0 , 0 ,,
     2.5     2.5
     450     510
     2.5     2.5
     450     510
Pier Skew, UpSta & Num, DnSta & Num=  ,7540, 2 ,7540, 2 , 0 , 0 , 0 ,,
     2.5     2.5
     450     510
     2.5     2.5
     450     510
Pier Skew, UpSta & Num, DnSta & Num=  ,7607.35, 2 ,7607.35, 2 , 0 , 0 , 0 ,,
     2.5     2.5
     450     510
     2.5     2.5
     450     510
Pier Skew, UpSta & Num, DnSta & Num=  ,7672.43, 2 ,7672.43, 2 , 0 , 0 , 0 ,,
     2.5     2.5
     450     510
     2.5     2.5
     450     510
Pier Skew, UpSta & Num, DnSta & Num=  ,7735.05, 2 ,7735.05, 2 , 0 , 0 , 0 ,,
     2.5     2.5
     450     510
     2.5     2.5
     450     510
Pier Skew, UpSta & Num, DnSta & Num=  ,7794.92, 2 ,7794.92, 2 , 0 , 0 , 0 ,,
     2.5     2.5
     450     510
     2.5     2.5
     450     510
Pier Skew, UpSta & Num, DnSta & Num=  ,7851.76, 2 ,7851.76, 2 , 0 , 0 , 0 ,,
     2.5     2.5
     450     510
     2.5     2.5
     450     510
Pier Skew, UpSta & Num, DnSta & Num=  ,7905.24, 2 ,7905.24, 2 , 0 , 0 , 0 ,,
     2.5     2.5
     450     510
     2.5     2.5
     450     510
BR Coef= 1 , 0 , 0 ,1.05, 0 ,,,0.8,-1,0.5,1,
WSPro=,,,, 1 ,,,, 0 ,,,, 0 ,,,,-1 ,-1 ,-1 , 0 , 0 , 0 , 0 , 0
BC Design=,, 0 ,, 0 ,,,,,,
BC HTab HWMax=519.5
BC Use User HTab Curves=0
BC User HTab FreeFlow(D)= 0

Type RM Length L Ch R = 1 ,181232  ,20,20,20
BEGIN DESCRIPTION:
This cross section corresponds to cross section 181285 of the non-georeferenced CDC model which was the source of this model.
END DESCRIPTION:
XS GIS Cut Line= 5
  2361552.884858 6973134.1526615 2361561.6402378 6972306.8421715
 2361562.8780978 6970179.9373115 2361564.3869478 6970066.7462615
 2361571.1129878 6969538.9422015
#Sta/Elev= 30
    4360   519.5    4568     518    4714     516    4854   515.7    4979   514.8
    5214   513.8    5822   510.4    5958   509.9    6005   509.3    6158   508.5
    6225   508.5    6459   507.3    6590   507.3    6748   506.3    6911   506.7
    6976   507.2    7400   511.9    7400   507.9  7447.7     492 7481.43     492
 7532.43     475 7595.81     475 7634.93  461.96 7709.93  461.96 7749.05     475
 7812.43     475 7863.43     492 7907.91     492 7955.31   507.8 7955.31   511.8
#Mann= 3 ,0,0
    4360     .05       0 7481.43    .035       0 7863.43     .05       0
#XS Ineff= 2 , 0
         7481.43     492 7863.43             492
Permanent Ineff=
       F       F
Bank Sta=7481.43,7863.43
XS Rating Curve= 0 ,0
Exp/Cntr=0.3,0.1

Type RM Length L Ch R = 1 ,181212  ,928,808,728
BEGIN DESCRIPTION:
This cross section corresponds to cross section 181265 of the non-georeferenced CDC model which was the source of this model.
END DESCRIPTION:
XS GIS Cut Line= 6
  2361535.702464 6976609.8584375   2361535.70413   6976609.70107
   2361581.28114   6972303.05285     2361582.519   6970176.14799
   2361584.02785   6970062.95694   2361590.75389   6969535.15288
#Sta/Elev= 30
    1000   537.2    1218   530.7    1639   534.2    1931   530.3    2108   532.2
    2147   525.6    2446   519.2    2651   524.6    3171   523.8    3642   521.2
    3751   516.7    4184   512.2    4226   519.2    4295   515.5    4656   517.1
    6545   504.4    6719   507.5    7281   501.2    7331   491.8    7383   488.9
    7575   491.4    7635   477.9    7695   474.2    7735   461.9    7810   461.9
    7855   472.8    7915   477.8    7975   490.7    8035   497.3    8075     511
#Mann= 3 ,0,0
    1000     .05       0    7575    .035       0    7975     .05       0
#XS Ineff= 2 ,-1
    1000    4500     520    4500    7575   491.4
Permanent Ineff=
       F       F
Bank Sta=7575,7975
XS Rating Curve= 0 ,0
Exp/Cntr=0.3,0.1

Type RM Length L Ch R = 1 ,180404  ,852,1383,1553
BEGIN DESCRIPTION:
This cross section corresponds to cross section 180455 of the non-georeferenced CDC model which was the source of this model.
END DESCRIPTION:
XS GIS Cut Line= 3
   2362291.77906   6977002.08906   2362653.95485   6970036.21093
 2362095.2733342 6969221.6854017
#Sta/Elev= 30
    1000     519    1030   518.2    1077   524.7    1253   511.4    1395     534
    2030   535.4    3154   515.3    3515   515.5    3590   508.7    3844   511.7
    4896   506.1    4924   498.7    4975   498.6    5016   508.1    5385   501.7
    6068   502.1    6553   495.9    6655   499.1    7168   498.5    7318   497.2
    7354   489.3    8275   492.4    8328   476.4    8404   476.4    8444   461.6
    8519   461.6    8632     486    8699   490.3    8892   489.6    8963   512.5
#Mann= 3 ,0,0
    1000     .05       0    8275    .035       0    8699     .08       0
#XS Ineff= 2 ,-1
    1000    5450     520    5450    8275   492.4
Permanent Ineff=
       F       F
Bank Sta=8275,8699
XS Rating Curve= 0 ,0
Exp/Cntr=0.3,0.1

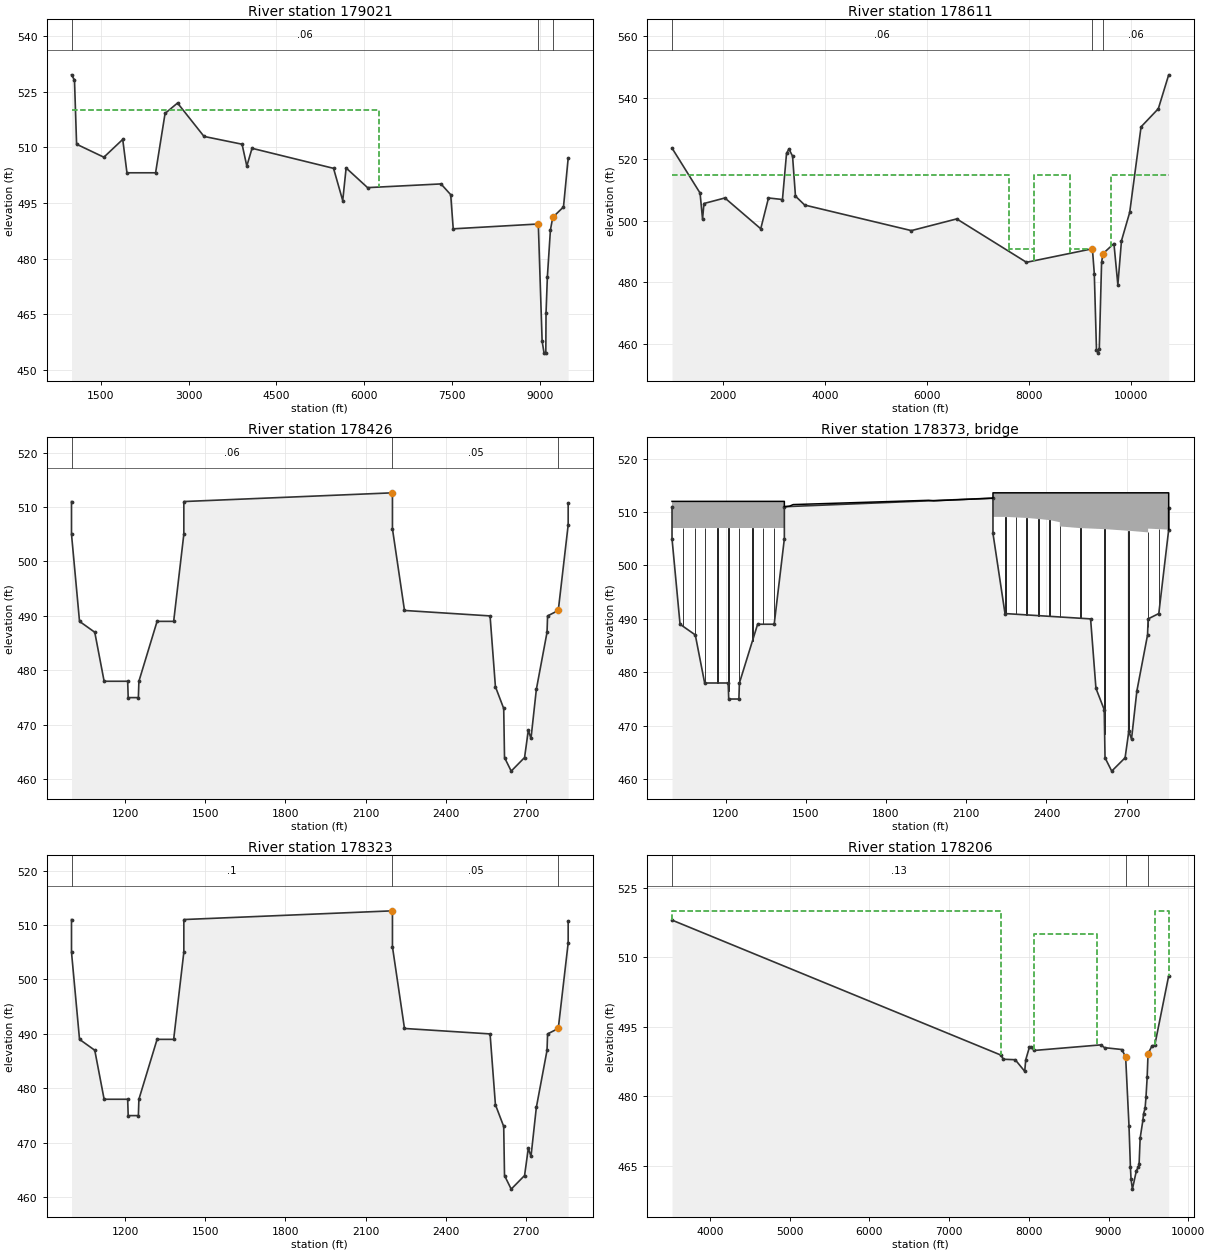
Type RM Length L Ch R = 1 ,179021  ,499,410,399
BEGIN DESCRIPTION:
This cross section corresponds to cross section 179075 of the non-georeferenced CDC model which was the source of this model.
END DESCRIPTION:
XS GIS Cut Line= 4
   2363085.04585     6977414.061   2363124.02904   6972410.30002
   2363351.58403   6970112.34989 2363692.7487769 6968994.3479177
#Sta/Elev= 30
    1000   529.5    1051   528.1    1087   510.8    1553   507.3    1875   512.1
    1947   503.1    2436   503.1    2598   519.1    2811   521.9    3263   512.9
    3913   510.8    3994   504.9    4083   509.7    5475   504.3    5632   495.6
    5690   504.4    6056   499.1    7310   500.1    7476   497.2    7519     488
    8972   489.3    9037   457.8    9070   454.5    9100   454.5    9104   465.3
    9127   475.1    9179   487.7    9219   491.1    9402   493.9    9482     507
#Mann= 3 ,0,0
    1000     .06       0    8972     .05       0    9219     .08       0
#XS Ineff= 2 ,-1
    1000    6250     520    6250    8972   489.3
Permanent Ineff=
       F       F
Bank Sta=8972,9219
XS Rating Curve= 0 ,0
Exp/Cntr=0.3,0.1

Type RM Length L Ch R = 1 ,178611  ,184,184,184
BEGIN DESCRIPTION:
This cross section corresponds to cross section 178664 of the non-georeferenced CDC model which was the source of this model.
END DESCRIPTION:
XS GIS Cut Line= 6
   2364033.43601   6977907.19585   2363975.63396    6974825.7299
   2363953.58414   6971103.01195   2363935.88207   6969681.06794
   2364004.40195   6968639.90204   2363996.04402    6968169.2081
#Sta/Elev= 30
    1000   523.6    1550     509    1599   500.5    1626   505.6    2037   507.4
    2740   497.4    2892   507.4    3166   506.9    3246   521.9    3293   523.3
    3364     521    3421     508    3602   505.1    5694   496.8    6584   500.6
    7952   486.5    9245   490.9    9282   482.8    9325     458    9355     457
    9380   458.5    9425   486.5    9452   489.3    9667   492.6    9744   479.2
    9815   493.5    9976   502.7   10199   530.5   10538   536.4   10741   547.4
#Mann= 3 ,0,0
    1000     .06       0    9245     .05       0    9452     .06       0
#XS Ineff= 6 ,-1
    1000    7600     515    8100    8800     515    9600   10741     515
    8800    9245   490.9    7600    8100   490.9    9452    9600   489.3
Permanent Ineff=
       F       F       F       F       F       F
Bank Sta=9245,9452
XS Rating Curve= 0 ,0
Exp/Cntr=0.3,0.1

Type RM Length L Ch R = 1 ,178426  ,103,103,103
BEGIN DESCRIPTION:
This cross section corresponds to cross section 178479 of the non-georeferenced CDC model which was the source of this model.
END DESCRIPTION:
XS GIS Cut Line= 3
  2364116.307598 6971119.6475117     2364099.592     6969776.937
 2364133.3579617 6969263.8614388
#Sta/Elev= 30
    1000     511    1000     505    1030     489    1087     487    1122     478
    1210     478    1212     475    1250     475    1252     478    1320     489
    1382     489    1420     505    1420     511    2200   512.6    2200     506
    2245     491    2565     490    2585     477    2616     473    2619     464
    2644   461.5    2694     464    2708     469    2718   467.5    2738   476.5
    2778     487    2780     490    2820     491    2857   506.7    2857   510.7
#Mann= 3 ,0,0
    1000     .06       0    2200     .05       0    2820     .06       0
#XS Ineff= 2 , 0
       0    2200     491    2820       0     491
Permanent Ineff=
       F       F
Bank Sta=2200,2820
XS Rating Curve= 0 ,0
Exp/Cntr=0.5,0.3

Type RM Length L Ch R = 3 ,178373  ,,,
BEGIN DESCRIPTION:
IH 820
END DESCRIPTION:
Node Name=IH 820
Bridge Culvert--1,0,-1,-1, 0
Deck Dist Width WeirC Skew NumUp NumDn MinLoCord MaxHiCord MaxSubmerge Is_Ogee
1,100,2.6,0, 36, 36, , , 0.95, 0, ,,,
    1000    1420    1420    1439    1453    1959    1978    2200    2200    2245
    2247    2285    2287    2325    2327    2370    2372    2410    2412    2450
    2450    2452    2525    2528    2616    2619    2705    2708    2778    2780
    2780    2820    2820    2822    2857    2857
     512     512     511   511.1   511.4   512.2   512.1   512.6   513.6   513.6
   513.6   513.6   513.6   513.6   513.6   513.6   513.6   513.6   513.6   513.6
   513.6   513.6   513.6   513.6   513.6   513.6   513.6   513.6   513.6   513.6
   513.6   513.6   513.6   513.6   513.6   506.7
     507     507     511   511.1   511.4   512.2   512.1   512.6   509.1   509.1
   509.1     509     509   508.9   508.9   508.7   508.7   508.5   508.5   508.1
   507.3   507.3     507     507   506.8   506.8   506.5   506.5   506.2   506.2
   506.9   506.8   506.8   506.8   506.7   506.7
    1000    1420    1420    1439    1453    1959    1978    2200    2200    2245
    2247    2285    2287    2325    2327    2370    2372    2410    2412    2450
    2450    2452    2525    2528    2616    2619    2705    2708    2778    2780
    2780    2820    2820    2822    2857    2857
     512     512     511   511.1   511.4   512.2   512.1   512.6   513.6   513.6
   513.6   513.6   513.6   513.6   513.6   513.6   513.6   513.6   513.6   513.6
   513.6   513.6   513.6   513.6   513.6   513.6   513.6   513.6   513.6   513.6
   513.6   513.6   513.6   513.6   513.6   506.7
     507     507     511   511.1   511.4   512.2   512.1   512.6   509.1   509.1
   509.1     509     509   508.9   508.9   508.7   508.7   508.5   508.5   508.1
   507.3   507.3     507     507   506.8   506.8   506.5   506.5   506.2   506.2
   506.9   506.8   506.8   506.8   506.7   506.7
Pier Skew, UpSta & Num, DnSta & Num=  ,1041, 2 ,1041, 2 , 0 , 0 , 0 ,,
       2       2
     475     510
       2       2
     475     510
Pier Skew, UpSta & Num, DnSta & Num=  ,1086, 2 ,1086, 2 , 0 , 0 , 0 ,,
       2       2
     475     510
       2       2
     475     510
Pier Skew, UpSta & Num, DnSta & Num=  ,1123, 2 ,1123, 2 , 0 , 0 , 0 ,,
       2       2
     475     510
       2       2
     475     510
Pier Skew, UpSta & Num, DnSta & Num=  ,1171, 2 ,1171, 2 , 0 , 0 , 0 ,,
       2       2
     475     510
       2       2
     475     510
Pier Skew, UpSta & Num, DnSta & Num=  ,1211, 2 ,1211, 2 , 0 , 0 , 0 ,,
       2       2
     475     510
       2       2
     475     510
Pier Skew, UpSta & Num, DnSta & Num=  ,1251, 2 ,1251, 2 , 0 , 0 , 0 ,,
       2       2
     475     510
       2       2
     475     510
Pier Skew, UpSta & Num, DnSta & Num=  ,1301, 2 ,1301, 2 , 0 , 0 , 0 ,,
       2       2
     475     510
       2       2
     475     510
Pier Skew, UpSta & Num, DnSta & Num=  ,1341, 2 ,1341, 2 , 0 , 0 , 0 ,,
       2       2
     475     510
       2       2
     475     510
Pier Skew, UpSta & Num, DnSta & Num=  ,1381, 2 ,1381, 2 , 0 , 0 , 0 ,,
       2       2
     475     510
       2       2
     475     510
Pier Skew, UpSta & Num, DnSta & Num=  ,2246, 2 ,2246, 2 , 0 , 0 , 0 ,,
       2       2
     465     510
       2       2
     465     510
Pier Skew, UpSta & Num, DnSta & Num=  ,2286, 2 ,2286, 2 , 0 , 0 , 0 ,,
       2       2
     465     510
       2       2
     465     510
Pier Skew, UpSta & Num, DnSta & Num=  ,2326, 2 ,2326, 2 , 0 , 0 , 0 ,,
       2       2
     465     510
       2       2
     465     510
Pier Skew, UpSta & Num, DnSta & Num=  ,2371, 2 ,2371, 2 , 0 , 0 , 0 ,,
       2       2
     465     510
       2       2
     465     510
Pier Skew, UpSta & Num, DnSta & Num=  ,2411, 2 ,2411, 2 , 0 , 0 , 0 ,,
       2       2
     465     510
       2       2
     465     510
Pier Skew, UpSta & Num, DnSta & Num=  ,2451, 2 ,2451, 2 , 0 , 0 , 0 ,,
       2       2
     465     510
       2       2
     465     510
Pier Skew, UpSta & Num, DnSta & Num=  ,2526.5, 2 ,2526.5, 2 , 0 , 0 , 0 ,,
       3       3
     465     510
       3       3
     465     510
Pier Skew, UpSta & Num, DnSta & Num=  ,2617.5, 2 ,2617.5, 2 , 0 , 0 , 0 ,,
       3       3
     465     510
       3       3
     465     510
Pier Skew, UpSta & Num, DnSta & Num=  ,2706.5, 2 ,2706.5, 2 , 0 , 0 , 0 ,,
       3       3
     465     510
       3       3
     465     510
Pier Skew, UpSta & Num, DnSta & Num=  ,2779, 2 ,2779, 2 , 0 , 0 , 0 ,,
       2       2
     465     510
       2       2
     465     510
Pier Skew, UpSta & Num, DnSta & Num=  ,2821, 2 ,2821, 2 , 0 , 0 , 0 ,,
       2       2
     465     510
       2       2
     465     510
BR Coef= 1 , 0 , 0 ,1.05, 0 ,,,0.8,-1,0.5,1,
WSPro=,,,, 1 ,,,, 0 ,,,, 0 ,,,,-1 ,-1 ,-1 , 0 , 0 , 0 , 0 , 0
BC Design=,, 0 ,, 0 ,,,,,,
BC HTab HWMax=512.6
BC Use User HTab Curves=0
BC User HTab FreeFlow(D)= 0

Type RM Length L Ch R = 1 ,178323  ,117,117,117
BEGIN DESCRIPTION:
This cross section corresponds to cross section 178377 of the non-georeferenced CDC model which was the source of this model.
END DESCRIPTION:
XS GIS Cut Line= 3
  2364204.325923 6971127.7267668      2364201.01     6970750.951
 2364197.5843205  6969270.745322
#Sta/Elev= 30
    1000     511    1000     505    1030     489    1087     487    1122     478
    1210     478    1212     475    1250     475    1252     478    1320     489
    1382     489    1420     505    1420     511    2200   512.6    2200     506
    2245     491    2565     490    2585     477    2616     473    2619     464
    2644   461.5    2694     464    2708     469    2718   467.5    2738   476.5
    2778     487    2780     490    2820     491    2857   506.7    2857   510.7
#Mann= 3 ,0,0
    1000      .1       0    2200     .05       0    2820     .08       0
#XS Ineff= 2 , 0
            2200     491    2820             491
Permanent Ineff=
       F       F
Bank Sta=2200,2820
XS Rating Curve= 0 ,0
Exp/Cntr=0.3,0.1

Type RM Length L Ch R = 1 ,178206  ,748,776,848
BEGIN DESCRIPTION:
This cross section corresponds to cross section 178263 of the non-georeferenced CDC model which was the source of this model.
END DESCRIPTION:
XS GIS Cut Line= 6
2364314.499046016975536.583823692364314.475902196975526.58385047
2364311.085333546974061.58777401 2364304.6050658 6971261.5952729
  2364302.290685 6970261.59795112364300.080451376969306.60050878
#Sta/Elev= 30
    3525     518    7650   488.9    7681     488    7830   487.9    7949   485.4
    7962   487.9    8008   490.6    8024   490.7    8070   489.9    8904   491.1
    8950   490.5    9167   490.1    9215   488.5    9257   473.7    9275   464.7
    9283   462.1    9300     460    9350     464    9376   464.8    9384   465.5
    9397     471    9432   474.9    9440   476.3    9459   477.4    9470   479.8
    9485   484.1    9496   489.2    9546   490.9    9580     491    9755     506
#Mann= 3 ,0,0
    3525     .13       0    9215     .05       0    9496     .08       0
#XS Ineff= 6 ,-1
    8070    8850     515    9496    9580   489.2    8850    9215   488.5
    7650    8070   488.5    9580    9755     520    3525    7650     520
Permanent Ineff=
       F       F       F       F       F       F
Bank Sta=9215,9496
XS Rating Curve= 0 ,0
Exp/Cntr=0.3,0.1

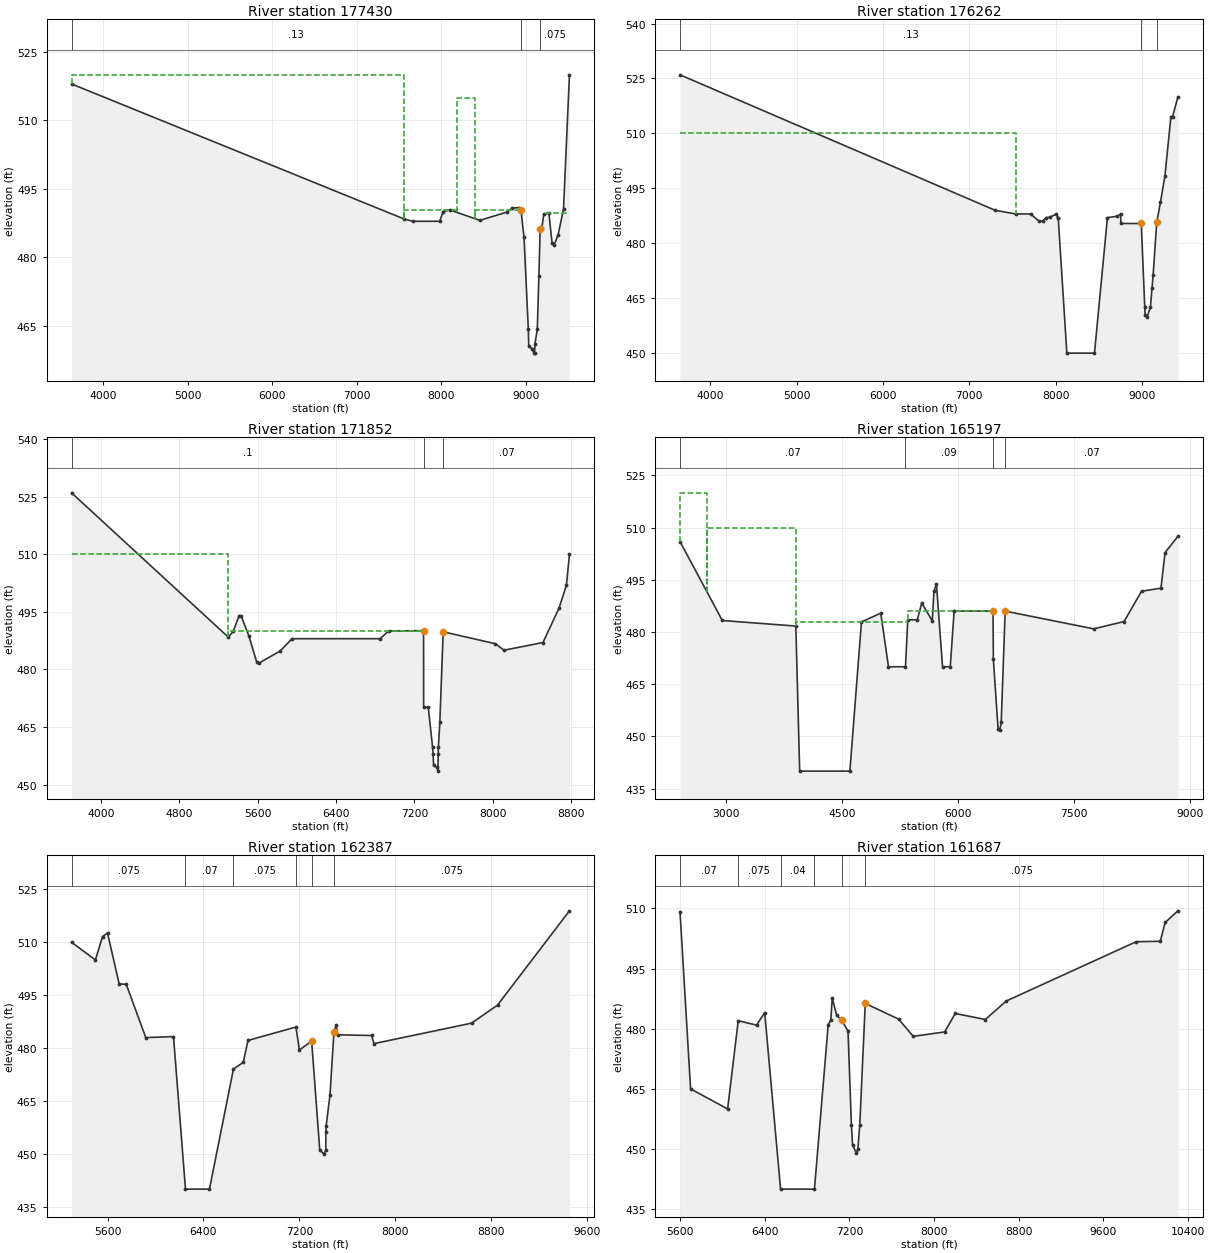
Type RM Length L Ch R = 1 ,177430  ,698,1168,1246
BEGIN DESCRIPTION:
This cross section corresponds to cross section 177485 of the non-georeferenced CDC model which was the source of this model.
END DESCRIPTION:
XS GIS Cut Line= 4
  2364318.534019 6975544.5112703  2364424.556025 6971615.9416408
   2364615.61201   6971093.02903 2365095.1482954 6969781.6802232
#Sta/Elev= 30
    3630     518    7560   488.4    7660   487.9    7980   487.9    8020     490
    8098   490.4    8454   488.1    8772   489.9    8839   490.8    8922   490.9
    8931   490.2    8940   490.4    8976   484.4    9027   464.2    9032   460.5
    9070     460    9095     459    9100     459    9105     461    9133   464.2
    9152     476    9167   486.3    9187   486.4    9209   489.4    9270   489.7
    9307   483.2    9334   482.8    9380     485    9443   490.6    9513     520
#Mann= 3 ,0,0
    3630     .13       0    8940     .05       0    9167    .075       0
#XS Ineff= 5 ,-1
    8180    8400     515    7560    8180   490.4    8400    8940   490.4
    9235    9513   489.7    3630    7560     520
Permanent Ineff=
       F       F       F       T       F
Bank Sta=8940,9167
XS Rating Curve= 0 ,0
Exp/Cntr=0.3,0.1

Type RM Length L Ch R = 1 ,176262  ,2498,4410,1799
BEGIN DESCRIPTION:
This cross section corresponds to cross section 176313 of the non-georeferenced CDC model which was the source of this model.
END DESCRIPTION:
XS GIS Cut Line= 5
  2364323.522998  6975598.919533      2364324.42      6975584.78
      2364575.42      6971628.24   2364925.28889   6971402.70689
   2366091.57395   6970682.30905
#Sta/Elev= 30
 3650.24     526    7300     489    7540     488    7710     488    7810     486
    7850   486.1    7890     487    7930   487.1    8010     488    8023   486.9
    8030     487    8130     450    8450     450    8600     487    8716   487.4
    8752     488    8756   485.4    8992   485.4    9032   462.6    9037   460.5
    9060     460    9098   462.5    9116   467.8    9129   471.2    9171   485.7
    9214   491.2    9266   498.4    9335   514.6    9355   514.6    9416     520
#Mann= 3 ,0,0
 3650.24     .13       0    8992    .065       0    9171    .075       0
#XS Ineff= 4 ,-1
 3650.24    7540     510    7540    8600     487    9171    9416   485.7
    8600    8992   485.4
Permanent Ineff=
       F       T       F       F
Bank Sta=8992,9171
XS Rating Curve= 0 ,0
Exp/Cntr=0.3,0.1

Type RM Length L Ch R = 1 ,171852  ,3799,6655,1500
BEGIN DESCRIPTION:
This cross section corresponds to cross section 171900 of the non-georeferenced CDC model which was the source of this model.
END DESCRIPTION:
XS GIS Cut Line= 6
  2364335.620421 6975595.7691784   2365304.91116   6974387.82788
   2366385.72986   6973040.89915   2366385.83485   6973040.77185
   2366938.19201   6972375.97791   2367230.55298   6971480.70607
#Sta/Elev= 30
    3700     526    5300   488.4    5350   489.9    5410     494    5430     494
    5510   488.7    5590   481.9    5610   481.6    5830   484.8    5950     488
    6850     488    6935     490    7293   490.1    7294   470.1    7341   470.1
    7385   459.7    7390     458    7395     455    7430   454.5    7440   453.5
    7442     458    7444   459.7    7459   466.2    7493   489.8    8024   486.7
    8114     485    8512     487    8676     496    8751   501.9    8782     510
#Mann= 3 ,0,0
    3700      .1       0    7293    .065       0    7493     .07       0
#XS Ineff= 3 ,-1
    3700    5300     510    5300    7293   490.1    7493    8782   489.8
Permanent Ineff=
       F       F       F
Bank Sta=7293,7493
XS Rating Curve= 0 ,0
Exp/Cntr=0.3,0.1

Type RM Length L Ch R = 1 ,165197  ,2402,2810,1151
BEGIN DESCRIPTION:
This cross section corresponds to cross section 165243 of the non-georeferenced CDC model which was the source of this model.
END DESCRIPTION:
XS GIS Cut Line= 5
 2368877.65286136977838.04796955  2368850.022491 6977489.1402989
  2368841.654436 6977383.4711187   2368586.11687   6974156.62297
 2368418.6193932  6971406.669799
#Sta/Elev= 30
    2400     506    2948   483.3    3900   481.7    3950     440    4600     440
    4750   482.9    5000   485.4    5100     470    5320     470    5350   483.5
    5472   483.5    5531   488.3    5667   483.2    5689   491.7    5721   493.8
    5800     470    5900     470    5950     486    6454     486    6458   472.1
    6520     452    6540   451.8    6560     454    6611     486    7758   480.9
    8151     483    8377   491.7    8629   492.6    8681   502.8    8848   507.5
#Mann= 4 ,-1,0
    2400     .07       0    5320     .09       0    6454    .055       0
    6611     .07       0
#XS Ineff= 5 ,-1
    2400    2750     520    2750    3900     510    6611    8848     486
    5350    6454     486    3900    5350     483
Permanent Ineff=
       F       F       F       F       T
Bank Sta=6454,6611
XS Rating Curve= 0 ,0
Exp/Cntr=0.3,0.1

Type RM Length L Ch R = 1 ,162387  ,409,699,898
BEGIN DESCRIPTION:
This cross section corresponds to cross section 162435 of the non-georeferenced CDC model which was the source of this model.
END DESCRIPTION:
XS GIS Cut Line= 5
  2370426.727749 6974782.1451209 2370394.4049795 6974574.6475581
   2370223.44003    6973477.1299   2369682.57891   6972486.03904
  2369181.567299  6970859.262461
#Sta/Elev= 30
    5300   509.9    5499   504.9    5558   511.5    5600   512.5    5697   498.1
    5756     498    5919   482.9    6150   483.2    6250     440    6450     440
    6650     474    6732   475.9    6771   482.1    7171   485.9    7200   479.4
    7302   481.9    7370     451    7405     450    7420     451    7421   456.2
    7423   457.9    7455   466.6    7488   484.4    7506   486.5    7519   483.7
    7802   483.5    7822   481.2    8636     487    8852   492.1    9452   518.8
#Mann= 6 ,-1,0
    5300    .075       0    6250     .07       0    6650    .075       0
    7171     .12       0    7302    .055       0    7488    .075       0
#XS Ineff= 3 ,-1
    7488    9452   484.4    7000    7302   481.9    6000    7000     474
Permanent Ineff=
       F       F       T
Bank Sta=7302,7488
XS Rating Curve= 0 ,0
Exp/Cntr=0.3,0.1

Type RM Length L Ch R = 1 ,161687  ,102,102,102
BEGIN DESCRIPTION:
This cross section corresponds to cross section 161734 of the non-georeferenced CDC model which was the source of this model.
Copied geometry from XS 161634
END DESCRIPTION:
XS GIS Cut Line= 4
  2370844.741162 6974390.6193323 2370578.9524015 6973223.3172414
 2370506.4023515 6972160.9483014 2369840.2425915 6969812.6291814
#Sta/Elev= 30
    5600   509.2    5700     465    6050     460    6150     482    6323   480.9
    6400     484    6550     440    6870     440    7000     481    7025   482.2
    7038   487.7    7080   483.3    7126   482.2    7187   479.4    7219     456
    7230     451    7265     449    7280     450    7298     456    7350   486.3
    7665   482.4    7803   478.1    8100   479.2    8200   483.8    8484   482.3
    8681   486.9    9909   501.7   10136   501.8   10183   506.5   10303   509.4
#Mann= 6 ,-1,0
    5600     .07       0    6150    .075       0    6550     .04       0
    6870     .12       0    7126    .055       0    7350    .075       0
#XS Ineff= 2 , 0
       0    7126     481    7350       0   485.9
Permanent Ineff=
       T       F
Bank Sta=7126,7350
XS Rating Curve= 0 ,0
Exp/Cntr=0.3,0.1