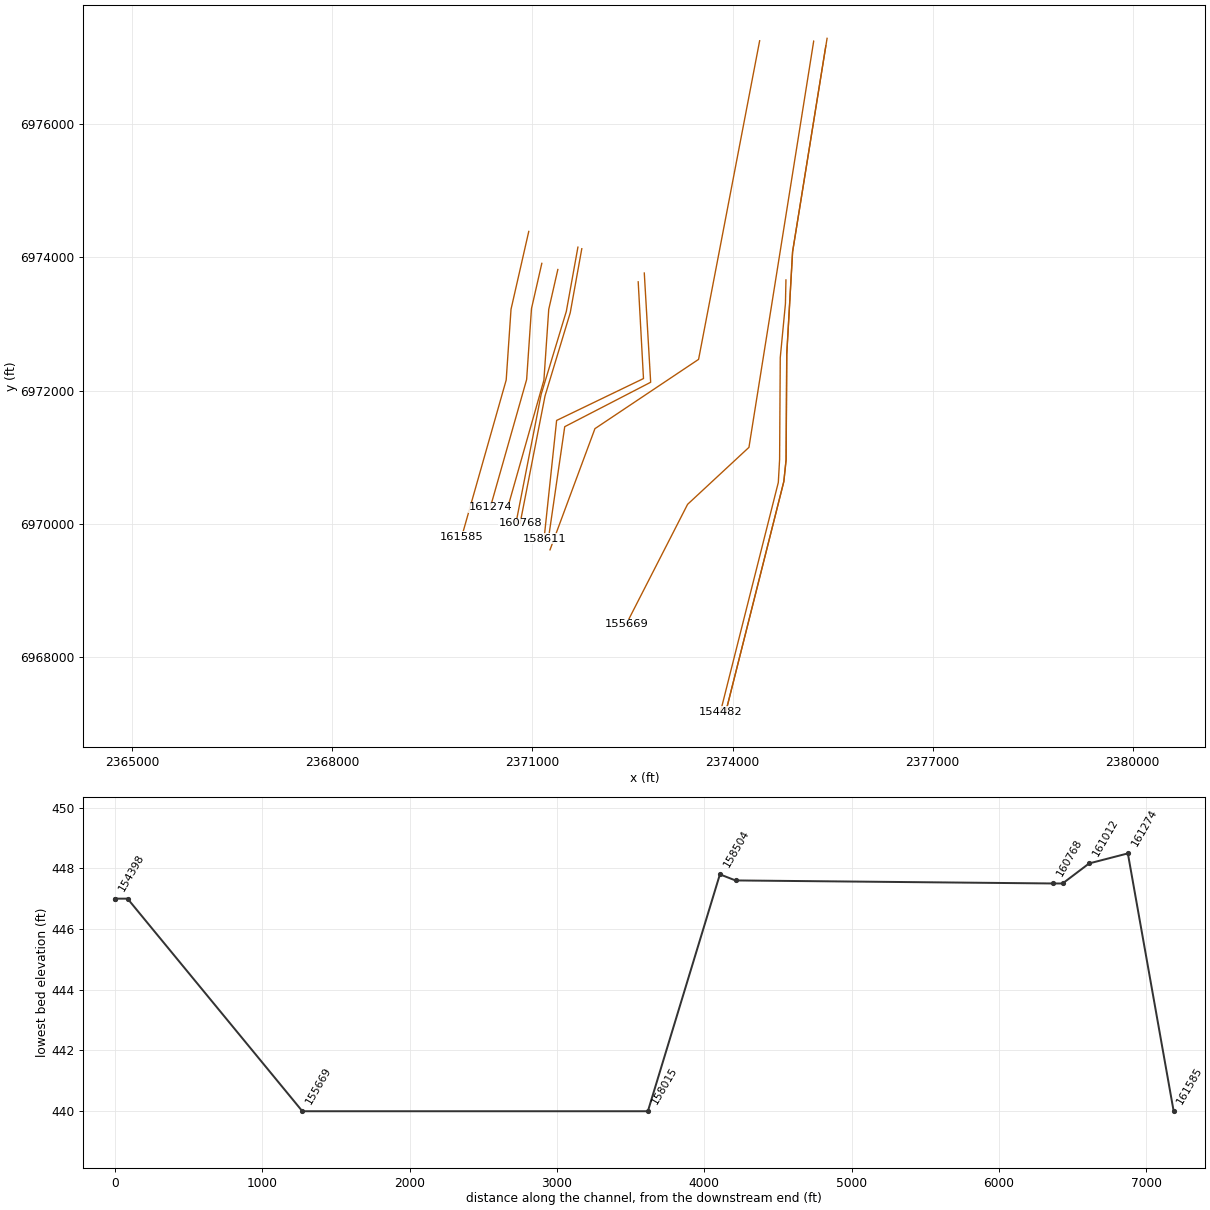
HEC-RAS study CDC_Consolidated_Model.prj: Upper Trinity CDC Consolidated Model

--- CDC_Consolidated_Model.g01 (geometry) --- (continued)

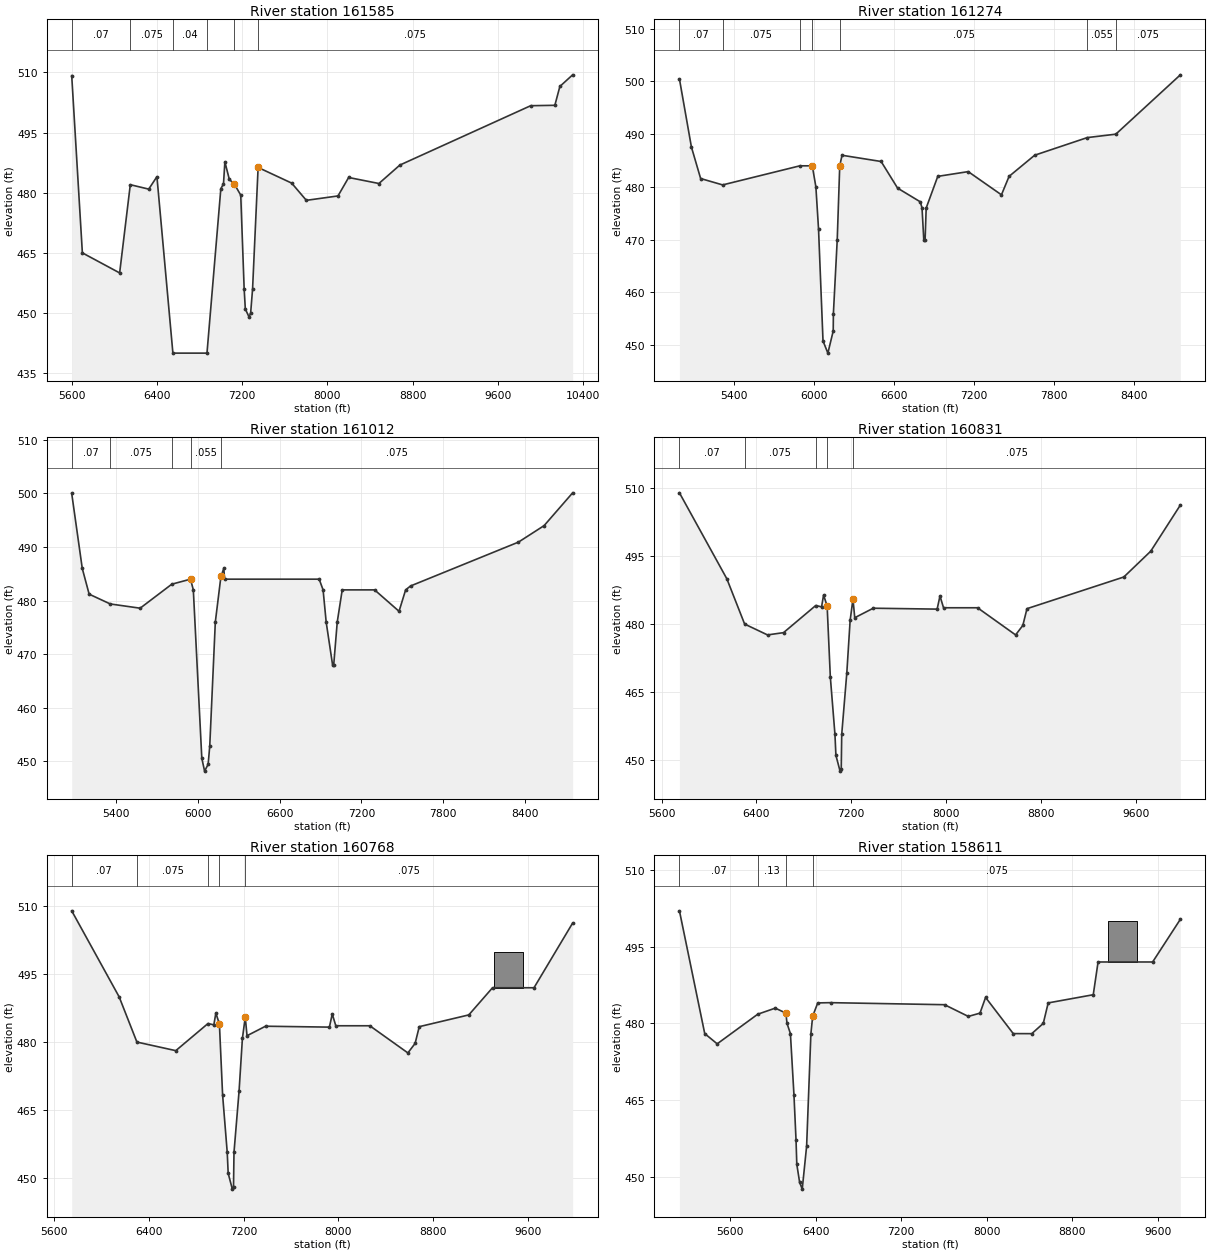
Type RM Length L Ch R = 1 ,161585  ,294,311,209
BEGIN DESCRIPTION:
This cross section corresponds to cross section 161634 of the non-georeferenced CDC model which was the source of this model.
END DESCRIPTION:
XS GIS Cut Line= 4
  2370945.508721 6974390.7510709   2370679.71996   6973223.44898
   2370607.16991   6972161.08004   2369941.01015   6969812.76092
#Sta/Elev= 30
    5600   509.2    5700     465    6050     460    6150     482    6323   480.9
    6400     484    6550     440    6870     440    7000     481    7025   482.2
    7038   487.7    7080   483.3    7126   482.2    7187   479.4    7219     456
    7230     451    7265     449    7280     450    7298     456    7350   486.3
    7665   482.4    7803   478.1    8100   479.2    8200   483.8    8484   482.3
    8681   486.9    9909   501.7   10136   501.8   10183   506.5   10303   509.4
#Mann= 6 ,-1,0
    5600     .07       0    6150    .075       0    6550     .04       0
    6870     .12       0    7126    .055       0    7350    .075       0
#XS Ineff= 2 , 0
       0    7126     481    7350       0   485.9
Permanent Ineff=
       T       F
Bank Sta=7126,7350
XS Rating Curve= 0 ,0
Exp/Cntr=0.3,0.1

Type RM Length L Ch R = 1 ,161274  ,294,263,204
BEGIN DESCRIPTION:
This cross section corresponds to cross section 161322 of the non-georeferenced CDC model which was the source of this model.
XS Added - GeoRas
END DESCRIPTION:
XS GIS Cut Line= 5
  2371141.137944 6973911.8172809  2371041.232307  6973473.047565
 2370986.2134367 6973231.4134114 2370913.6633867 6972169.0444714
  2370370.311757 6970253.6435459
#Sta/Elev= 30
 4994.13  500.46 5083.83  487.57 5152.95  481.59 5317.95  480.38 5896.74     484
 5989.66     484 6016.54     480 6036.48     472 6069.98   450.8 6106.45  448.49
 6146.49  452.69 6147.77     456 6176.58     470 6195.34     484 6212.49     486
 6505.46  484.82 6628.92  479.77 6799.09  477.17 6811.98     476 6825.03     470
 6834.98     470 6843.11     476 6929.92     482 7157.98   482.9 7407.05   478.5
 7464.19     482 7656.11  486.01    8050  489.35    8264     490 8747.77  501.25
#Mann= 7 ,-1,0
 4994.13     .07       0 5317.95    .075       0 5896.74     .13       0
 5989.66    .055       0 6195.34    .075       0    8050    .055       0
    8264    .075       0
Bank Sta=5989.66,6195.34
XS Rating Curve= 0 ,0
Exp/Cntr=0.3,0.1

Type RM Length L Ch R = 1 ,161012  ,210,180,216
BEGIN DESCRIPTION:
This cross section corresponds to cross section 161058 of the non-georeferenced CDC model which was the source of this model.
XS Added - GeoRas
END DESCRIPTION:
XS GIS Cut Line= 5
  2371381.326327 6973819.5147058 2371281.4206906 6973380.7449899
 2371245.0484877 6973221.0040425 2371172.4984377 6972158.6351025
  2370629.146808  6970243.234177
#Sta/Elev= 30
 5077.54     500 5154.87     486 5205.27   481.2 5360.23  479.37 5578.87  478.58
 5810.58  483.06  5947.8     484 5968.42     482 6030.53  450.58 6050.93  448.16
 6076.94  449.43 6088.79  452.85 6129.57     476 6170.58   484.5 6191.54     486
 6197.76     484 6890.25     484 6919.07     482 6941.59     476 6988.54     468
 6996.87     468 7022.73     476 7059.18     482 7296.28     482 7475.44     478
 7523.71     482 7559.85  482.73 8350.35  490.92 8538.28     494 8747.19  500.12
#Mann= 5 ,-1,0
 5077.54     .07       0 5360.23    .075       0 5810.58     .13       0
  5947.8    .055       0 6170.58    .075       0
#XS Ineff= 2 , 0
       0  5947.8     484 6170.58       0   484.5
Permanent Ineff=
       F       F
Bank Sta=5947.8,6170.58
XS Rating Curve= 0 ,0
Exp/Cntr=0.3,0.1

Type RM Length L Ch R = 1 ,160831  ,63,63,69
BEGIN DESCRIPTION:
This cross section corresponds to cross section 160878 of the non-georeferenced CDC model which was the source of this model.
END DESCRIPTION:
XS GIS Cut Line= 5
  2371682.359361 6974154.7699653 2371638.0012066 6973908.7367275
   2371508.76916   6973191.94904    2371131.2499   6971946.14904
 2370758.0835277 6970036.3538995
#Sta/Elev= 30
    5750     509    6150     490    6300     480    6493   477.6    6628   478.1
    6900   484.1    6949   483.8    6966   486.4    6996     484    7023   468.3
    7062   455.6    7070     451    7105   447.5    7115     448    7119   455.6
    7162   469.2    7190   480.8    7214   485.5    7229   481.4    7385   483.5
    7924   483.3    7948   486.2    7978   483.6    8265   483.6    8586   477.6
    8647   479.7    8682   483.4    9499   490.4    9726   496.1    9976   506.3
#Mann= 5 ,-1,0
    5750     .07       0    6300    .075       0    6900     .13       0
    6996    .055       0    7214    .075       0
#XS Ineff= 2 , 0
            6996     484    7214           485.5
Permanent Ineff=
       F       F
Bank Sta=6996,7214
XS Rating Curve= 0 ,0
Exp/Cntr=0.3,0.1

Type RM Length L Ch R = 1 ,160768  ,819,2158,215
BEGIN DESCRIPTION:
This cross section corresponds to cross section 160778 of the non-georeferenced CDC model which was the source of this model.
Copied geometry from XS 160878
END DESCRIPTION:
XS GIS Cut Line= 5
  2371740.543566 6974131.6257075 2371696.1854117 6973885.5924697
 2371566.9533651 6973168.8047822 2371189.4341051 6971923.0047822
 2370816.2677328 6970013.2096417
#Sta/Elev= 30
    5750     509    6150     490    6300     480    6628   478.1    6900   484.1
    6949   483.8    6966   486.4    6996     484    7023   468.3    7062   455.6
    7070     451    7105   447.5    7115     448    7119   455.6    7162   469.2
    7190   480.8    7214   485.5    7229   481.4    7385   483.5    7924   483.3
    7948   486.2    7978   483.6    8265   483.6    8586   477.6    8647   479.7
    8682   483.4    9100     486    9300     492    9650     492    9976   506.3
#Mann= 5 ,-1,0
    5750     .07       0    6300    .075       0    6900     .13       0
    6996    .055       0    7214    .075       0
#XS Ineff= 2 , 0
       0    6996     484    7214       0   485.5
Permanent Ineff=
       F       F
#Block Obstruct= 1 ,-1
    9312    9555     500
Bank Sta=6996,7214
XS Rating Curve= 0 ,0
Exp/Cntr=0.3,0.1

Type RM Length L Ch R = 1 ,158611  ,116,106,126
BEGIN DESCRIPTION:
This cross section corresponds to cross section 158671 of the non-georeferenced CDC model which was the source of this model.
XS Added - GeoRas
END DESCRIPTION:
XS GIS Cut Line= 6
  2372586.090192 6973634.5653238 2372590.9921592 6973544.6989189
      2372644.42     6972565.221     2372665.254     6972183.277
      2371363.17     6971554.804 2371175.1656432 6969781.7211204
#Sta/Elev= 30
 5126.93     502 5363.42     478 5479.76     476 5858.78  481.79 6022.87  482.98
 6122.02     482 6132.39     480 6164.25     478 6197.42     466 6216.78  457.17
 6223.95  452.45 6250.53  448.91 6274.73   447.6 6315.75     456  6355.8     478
 6372.34   481.4 6419.68     484 6540.09  484.05 7604.86  483.65 7827.09  481.36
 7936.19     482 7988.46  485.07 8247.14     478 8420.19  477.99 8527.93     480
 8573.68     484    8995   485.6    9040     492    9550     492 9809.22  500.35
#Mann= 4 ,-1,0
 5126.93     .07       0 5858.78     .13       0 6122.02    .055       0
 6372.34    .075       0
#XS Ineff= 2 , 0
       0 6122.02     482 6372.34       0   481.4
Permanent Ineff=
       F       F
#Block Obstruct= 1 ,-1
    9130    9405     500
Bank Sta=6122.02,6372.34
XS Rating Curve= 0 ,0
Exp/Cntr=0.3,0.1

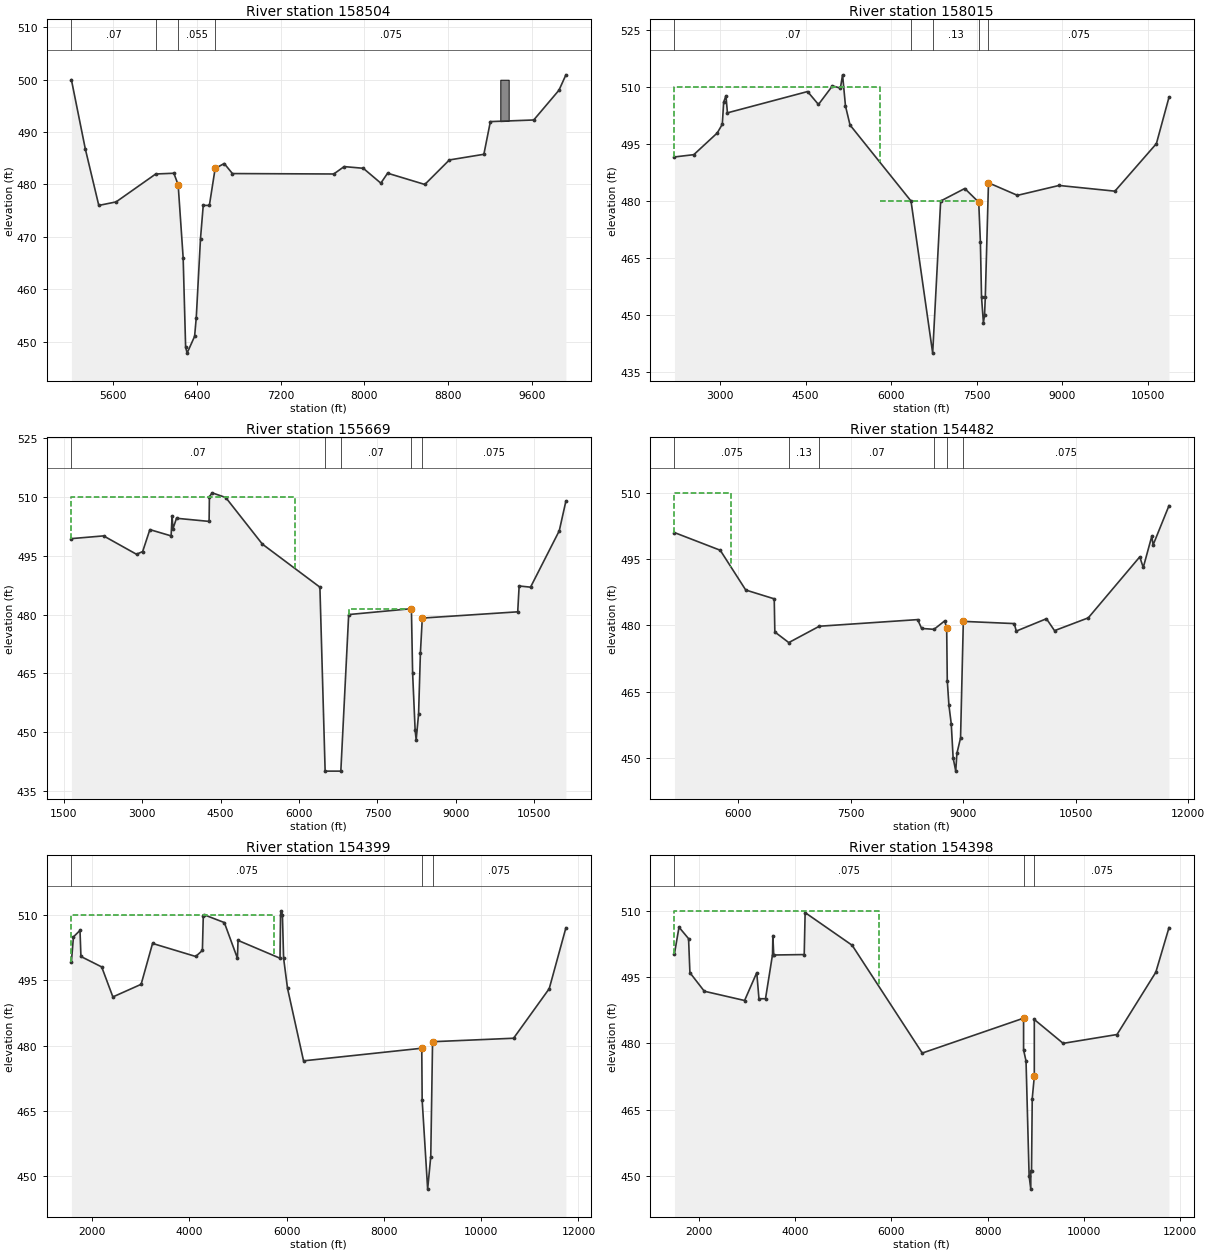
Type RM Length L Ch R = 1 ,158504  ,1106,489,372
BEGIN DESCRIPTION:
This cross section corresponds to cross section 158561 of the non-georeferenced CDC model which was the source of this model.
XS Added - GeoRas
END DESCRIPTION:
XS GIS Cut Line= 6
  2372677.284238 6973766.6996845  2372688.846856 6973568.4868423
     2372748.587     6972544.388     2372772.893     6972127.721
     2371484.698     6971461.054 2371249.3614863 6969841.5680821
#Sta/Elev= 30
 5198.55     500 5331.68  486.78 5460.59     476 5626.01  476.67 6005.02     482
 6178.59  482.14 6219.46  479.93 6267.26     466 6290.82     449 6304.96   447.8
 6376.68     451 6392.39   454.5 6433.14  469.68 6459.26     476 6517.93     476
 6573.23  483.05 6659.85     484 6738.42  482.08 7707.49     482 7806.75  483.41
 7989.45  483.09 8157.59  480.25 8222.28  482.15 8578.14     480 8812.84  484.68
 9142.82  485.76    9205     492 9619.74  492.31 9861.11     498 9927.29  500.93
#Mann= 4 ,-1,0
 5198.55     .07       0 6005.02     .13       0 6219.46    .055       0
 6573.23    .075       0
#XS Ineff= 2 , 0
       0 6219.46  479.93 6573.23       0  483.05
Permanent Ineff=
       F       F
#Block Obstruct= 1 ,-1
    9300    9380     500
Bank Sta=6219.46,6573.23
XS Rating Curve= 0 ,0
Exp/Cntr=0.3,0.1

Type RM Length L Ch R = 1 ,158015  ,1000,2346,1699
BEGIN DESCRIPTION:
This cross section corresponds to cross section 158061of the non-georeferenced CDC model which was the source of this model.
---------------------------------------------------------------------
CDC FW022307-01 Rocking River M Equestrian Center
Cross-section 158061 - 161734
Located in ROB.
---------------------------------------------------------------------
END DESCRIPTION:
XS GIS Cut Line= 5
  2374406.594046 6977251.9090106 2374375.1860997 6977087.8890701
   2373491.15988   6972471.28907   2371937.53995   6971431.67894
 2371264.0377802  6969613.238869
#Sta/Elev= 30
    2200   491.6    2539   492.2    2950   497.9    3039   500.2    3063     506
    3103   507.7    3129   503.2    4535   508.8    4726   505.4    4972   510.3
    5111   509.7    5149   513.2    5200     505    5280     500    6350     480
    6730     440    6870     480    7293   483.3    7538   479.7    7567   469.2
    7587   454.7    7620     448    7640     450    7653   454.7    7709   484.8
    8217   481.5    8947   484.1    9927   482.6   10655   495.1   10876   507.3
#Mann= 5 ,-1,0
    2200     .07       0    6350     .06       0    6730     .13       0
    7538    .055       0    7709    .075       0
#XS Ineff= 3 ,-1
    2200    5800     510    7709   10876     484    5800    7538     480
Permanent Ineff=
       F       F       T
Bank Sta=7538,7709
XS Rating Curve= 0 ,0
Exp/Cntr=0.3,0.1

Type RM Length L Ch R = 1 ,155669  ,350,1187,1499
BEGIN DESCRIPTION:
This cross section corresponds to cross section 155714 of the non-georeferenced CDC model which was the source of this model.
END DESCRIPTION:
XS GIS Cut Line= 5
  2375216.900499 6977247.5845485 2375216.9004995 6977247.5845485
   2374246.14885   6971151.04991   2373326.55916   6970296.25897
   2372405.52196   6968494.91907
#Sta/Elev= 30
    1650   499.4    2265   500.1    2895   495.4    3012   496.1    3150   501.7
    3556   500.1    3575   505.1    3591   501.9    3659   504.6    4282   503.8
    4288   510.1    4340   511.1    4600   509.9    5300     498    6400     487
    6500     440    6800     440    6950     480    8149   481.5    8172   465.1
    8220   450.5    8240     448    8286   454.6    8321   470.2    8357   479.1
   10181   480.7   10208   487.3   10426     487   10975   501.4   11102     509
#Mann= 5 ,-1,0
    1650     .07       0    6500     .04       0    6800     .07       0
    8149    .055       0    8357    .075       0
#XS Ineff= 4 ,-1
    1650    5933     510    6950    8149   481.5    5933    6950     480
    8357   11102   479.1
Permanent Ineff=
       F       F       T       F
Bank Sta=8149,8357
XS Rating Curve= 0 ,0
Exp/Cntr=0.3,0.1

Type RM Length L Ch R = 1 ,154482  ,83,83,83
BEGIN DESCRIPTION:
This cross section corresponds to cross section 154527 of the non-georeferenced CDC model which was the source of this model.
END DESCRIPTION:
XS GIS Cut Line= 6
  2374800.699271 6973662.8791966   2374793.20189    6973308.0141
   2374715.41793     6972496.144   2374705.69485   6970969.63393
   2374686.24902   6970624.46796   2373819.26716     6967181.798
#Sta/Elev= 30
    5150     501    5760     497    6100     488    6480     486    6488   478.5
    6674   476.1    7081   479.8    8392   481.3    8445   479.3    8610   479.1
    8752     481    8779   479.4    8787   467.5    8809   461.9    8840   457.7
    8865     450    8900     447    8915     451    8964   454.5    9001   480.9
    9680   480.4    9707   478.7   10109   481.5   10217   478.8   10667   481.7
   11353   495.5   11400   493.1   11514   500.2   11531   498.2   11743   507.1
#Mann= 6 ,-1,0
    5150    .075       0    6674     .13       0    7081     .07       0
    8610     .13       0    8779    .055       0    9001    .075       0
#XS Ineff= 3 ,-1
    5150    5900     510    9001   11743   480.9    5900    8779   479.4
Permanent Ineff=
       F       F       F
Bank Sta=8779,9001
XS Rating Curve= 0 ,0
Exp/Cntr=0.3,0.1

Type RM Length L Ch R = 1 ,154399  ,1,1,1
BEGIN DESCRIPTION:
This cross section corresponds to cross section 154445 of the non-georeferenced CDC model which was the source of this model.
END DESCRIPTION:
XS GIS Cut Line= 6
  2375398.244882 6977175.2932533 2374899.9057473 6974085.5876751
 2374812.3987045 6972549.3545271 2374802.6756268 6970964.5066469
 2374768.6455112 6970638.7868259 2373893.0406351 6967159.7826291
#Sta/Elev= 30
    1574   499.2    1616     505    1751   506.5    1770   500.5    2197   498.1
    2427   491.2    3008   494.1    3243   503.5    4131   500.5    4268   501.9
    4286   509.8    4302   510.1    4719   508.3    4988   500.1    5001   504.2
    5864   500.1    5875   510.1    5888     511    5913   510.1    5938   500.1
    6018   493.2    6348   476.5    8779   479.4    8787   467.5    8900     447
    8964   454.5    9001   480.9   10667   481.7   11400   493.1   11743   507.1
#Mann= 3 ,0,0
    1574    .075       0    8779    .055       0    9001    .075       0
#XS Ineff= 3 ,-1
    1574    5750     510    9001   11743   480.9    5750    8779   479.4
Permanent Ineff=
       F       F       F
Bank Sta=8779,9001
XS Rating Curve= 0 ,0
Exp/Cntr=0.3,0.1

Type RM Length L Ch R = 1 ,154398  ,41,41,41
BEGIN DESCRIPTION:
This cross section corresponds to cross section 154444 of the non-georeferenced CDC model which was the source of this model.
END DESCRIPTION:
XS GIS Cut Line= 6
   2375417.43061 6977288.3246735 2374900.7797613 6974085.0863637
 2374813.2727185 6972548.8532157 2374803.5496408 6970964.0053356
 2374769.5195252 6970638.2855146 2373893.9146491 6967159.2813177
#Sta/Elev= 30
    1490   500.3    1584   506.3    1783   503.7    1811     496    2110   491.8
    2948   489.7    3201     496    3247   490.1    3383   490.1    3529   500.1
    3536   504.4    3554     500    4188   500.1    4207   509.6    5185   502.2
    6643   477.8    8750   485.7    8750   478.5    8801     476    8865     450
    8900     447    8900     451    8915     451    8930   467.5    8973   472.5
    8973   485.4    9573     480   10693     482   11500   496.1   11774   506.2
#Mann= 3 ,0,0
    1490    .075       0    8750    .055       0    8973    .075       0
#XS Ineff= 2 ,-1
    1490    5750     510    5750    8750   477.8
Permanent Ineff=
       F       F
Bank Sta=8750,8973
XS Rating Curve= 0 ,0
Exp/Cntr=0.3,0.1

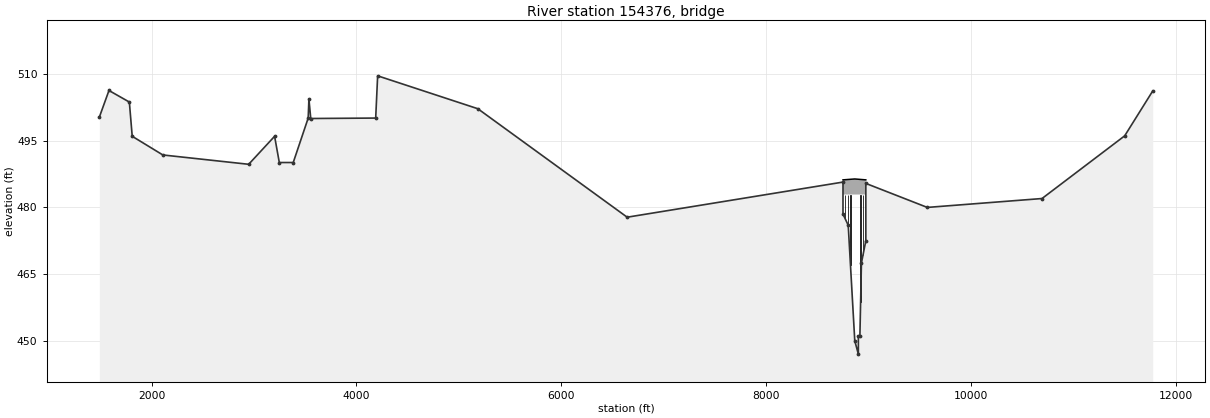
Type RM Length L Ch R = 3 ,154376  ,,,
BEGIN DESCRIPTION:
Precinct Line Road
END DESCRIPTION:
Node Name=Precinct Line Ro
Bridge Culvert--1,0,-1,-1, 0
Deck Dist Width WeirC Skew NumUp NumDn MinLoCord MaxHiCord MaxSubmerge Is_Ogee
1,38,2.6,0, 3, 3, , , 0.95, 0, ,,,
    8750    8865    8973
   486.2   486.4   486.2
   482.9   482.9   482.9
    8750    8865    8973
   486.2   486.4   486.2
   482.9   482.9   482.9
Pier Skew, UpSta & Num, DnSta & Num=  ,8771, 2 ,8771, 2 , 0 , 0 , 0 ,,
       2       2
     455     485
       2       2
     455     485
Pier Skew, UpSta & Num, DnSta & Num=  ,8799.5, 2 ,8799.5, 2 , 0 , 0 , 0 ,,
       3       3
     455     485
       3       3
     455     485
Pier Skew, UpSta & Num, DnSta & Num=  ,8823, 2 ,8823, 2 , 0 , 0 , 0 ,,
       4       4
     455     485
       4       4
     455     485
Pier Skew, UpSta & Num, DnSta & Num=  ,8922, 2 ,8922, 2 , 0 , 0 , 0 ,,
       4       4
     455     485
       4       4
     455     485
Pier Skew, UpSta & Num, DnSta & Num=  ,8946, 2 ,8946, 2 , 0 , 0 , 0 ,,
       2       2
     455     485
       2       2
     455     485
BR Coef= 1 , 0 , 0 ,1.05, 0 ,,,0.8,-1,0.5,1,
WSPro=,,,, 1 ,,,, 0 ,,,, 0 ,,,,-1 ,-1 ,-1 , 0 , 0 , 0 , 0 , 0
BC Design=,, 0 ,, 0 ,,,,,,
BC HTab HWMax=506.2
BC Use User HTab Curves=0
BC User HTab FreeFlow(D)= 0