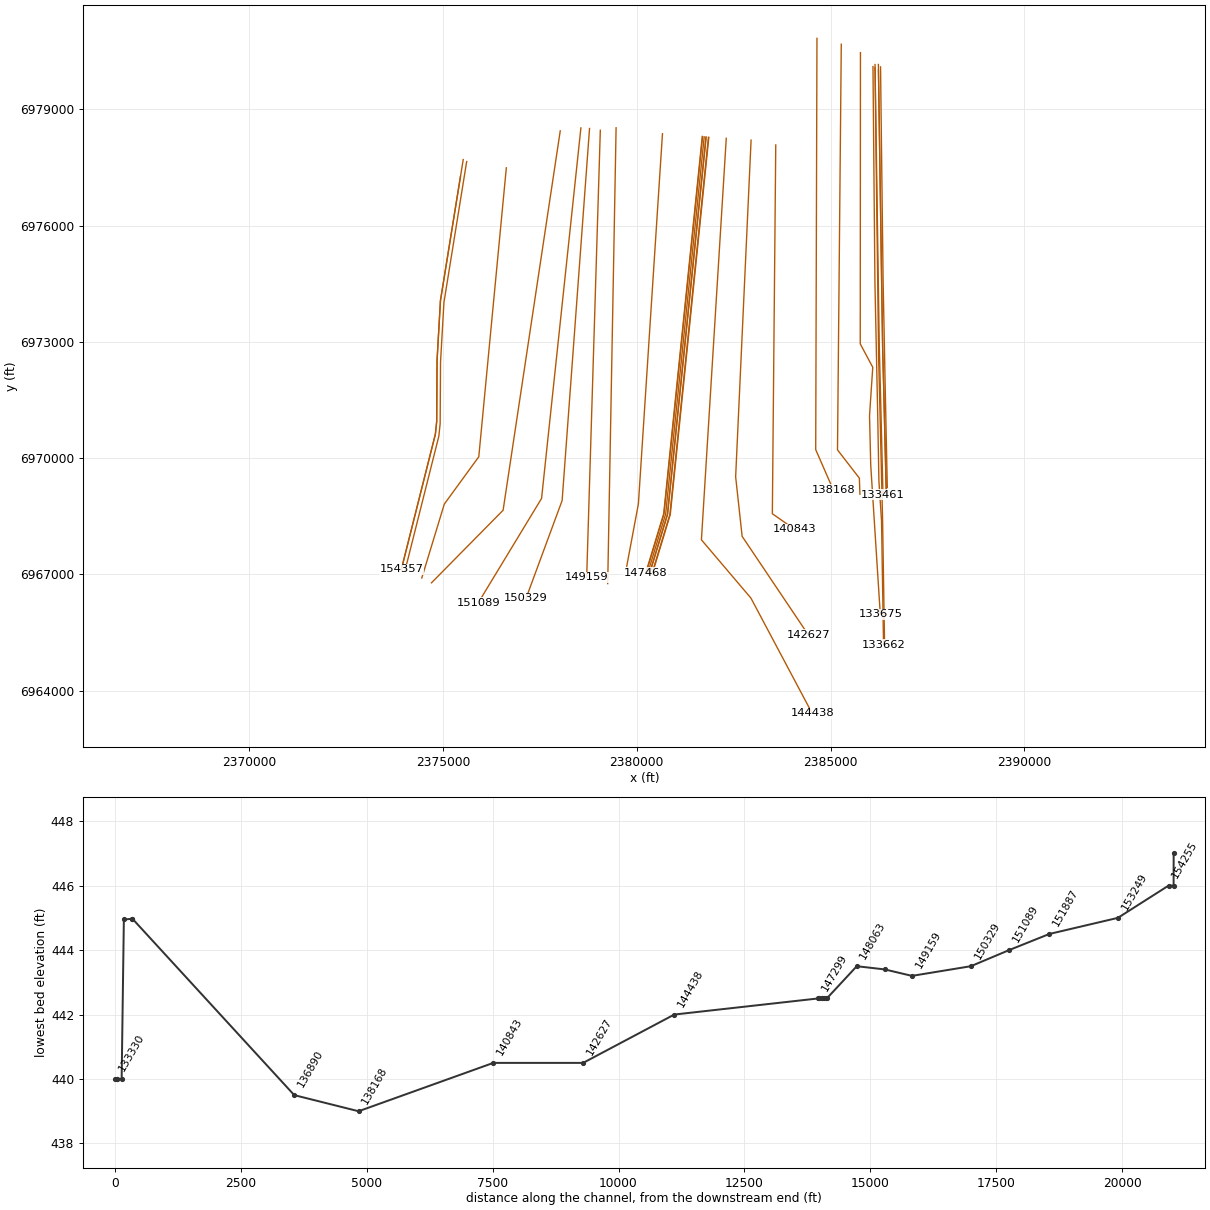
HEC-RAS study CDC_Consolidated_Model.prj: Upper Trinity CDC Consolidated Model

--- CDC_Consolidated_Model.g01 (geometry) --- (continued)

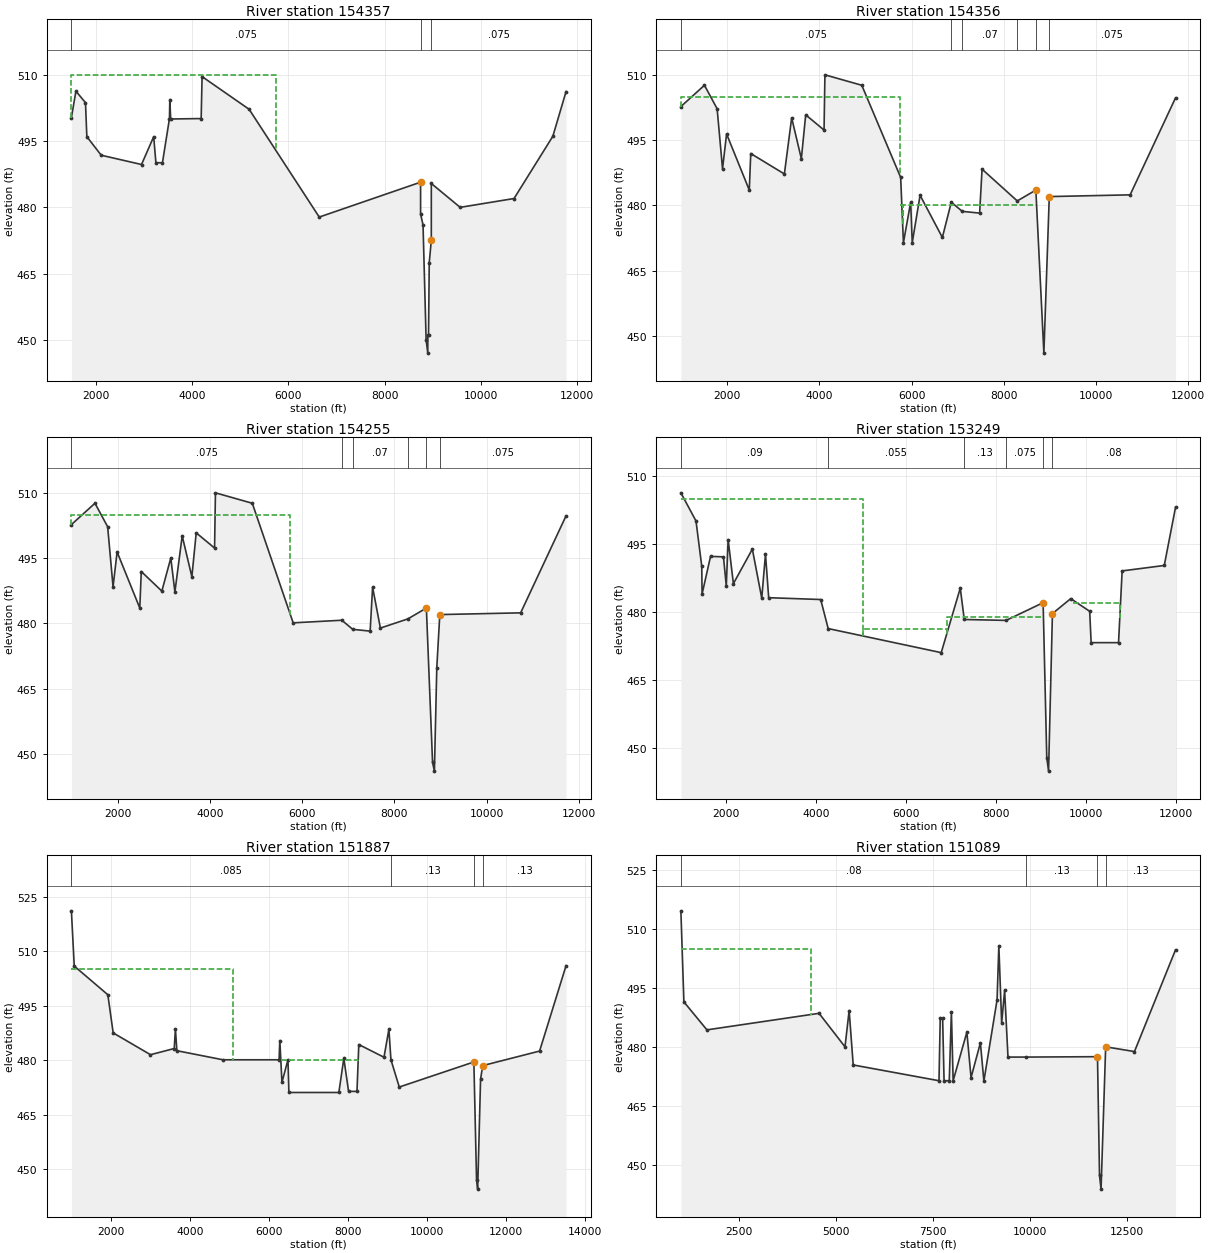
Type RM Length L Ch R = 1 ,154357  ,1,1,1
BEGIN DESCRIPTION:
This cross section corresponds to cross section 154404 of the non-georeferenced CDC model which was the source of this model.
END DESCRIPTION:
XS GIS Cut Line= 6
  2375453.266234 6977267.7661527 2374936.6153862 6974064.5278488
 2374849.1083362 6972528.2946988 2374839.3852662 6970943.4468188
 2374805.3551462 6970617.7269988 2373929.7502662 6967138.7227988
#Sta/Elev= 30
    1490   500.3    1584   506.3    1783   503.7    1811     496    2110   491.8
    2948   489.7    3201     496    3247   490.1    3383   490.1    3529   500.1
    3536   504.4    3554     500    4188   500.1    4207   509.6    5185   502.2
    6643   477.8    8750   485.7    8750   478.5    8801     476    8865     450
    8900     447    8900     451    8915     451    8930   467.5    8973   472.5
    8973   485.4    9573     480   10693     482   11500   496.1   11774   506.2
#Mann= 3 ,0,0
    1490    .075       0    8750    .055       0    8973    .075       0
#XS Ineff= 2 ,-1
    1490    5750     510    5750    8750   477.8
Permanent Ineff=
       F       F
Bank Sta=8750,8973
XS Rating Curve= 0 ,0
Exp/Cntr=0.3,0.1

Type RM Length L Ch R = 1 ,154356  ,101,101,101
BEGIN DESCRIPTION:
This cross section corresponds to cross section 154403 of the non-georeferenced CDC model which was the source of this model.
END DESCRIPTION:
XS GIS Cut Line= 6
    2375524.3271    6977702.0368      2374937.62      6974064.48
      2374850.14      6972528.37      2374840.39      6970943.44
      2374806.35      6970617.86      2373930.66      6967138.23
#Sta/Elev= 30
    1000   502.7    1511   507.6    1786   502.2    1903   488.4    1991   496.4
    2483   483.5    2515   491.9    3244   487.2    3402   500.1    3612   490.7
    3706   500.8    4104   497.3    4123     510    4922   507.6    5765   486.4
    5825   471.4    5982   480.7    6016   471.4    6186   482.3    6669   472.6
    6863   480.7    7101   478.6    7477   478.2    7530   488.3    8293     481
    8696   483.5    8870     446    8987     482   10740   482.4   11724   504.7
#Mann= 6 ,-1,0
    1000    .075       0    6863     .13       0    7101     .07       0
    8293     .12       0    8696    .055       0    8987    .075       0
#XS Ineff= 5 ,-1
    1000    5750     505    8987   11724     482    5750    5808   480.1
    7486    8696   480.1    5808    7486     480
Permanent Ineff=
       F       F       F       F       T
Bank Sta=8696,8987
XS Rating Curve= 0 ,0
Exp/Cntr=0.3,0.1

Type RM Length L Ch R = 1 ,154255  ,1198,1006,599
BEGIN DESCRIPTION:
This cross section corresponds to cross section 154301 of the non-georeferenced CDC model which was the source of this model.
END DESCRIPTION:
XS GIS Cut Line= 6
  2375613.267176 6977650.5554074   2375026.55412     6974012.931
   2374939.04707   6972476.69785     2374929.324   6970891.84997
   2374895.29388   6970566.13015     2374019.689   6967087.12595
#Sta/Elev= 30
    1000   502.7    1511   507.6    1786   502.2    1903   488.4    1991   496.4
    2483   483.5    2515   491.9    2961   487.4    3155     495    3244   487.2
    3402   500.1    3612   490.7    3706   500.8    4104   497.3    4123     510
    4922   507.6    5808   480.1    6863   480.7    7101   478.6    7477   478.2
    7530   488.3    7699   478.9    8293     481    8696   483.5    8830     448
    8870     446    8922   469.8    8987     482   10740   482.4   11724   504.7
#Mann= 6 ,-1,0
    1000    .075       0    6863     .13       0    7101     .07       0
    8293     .12       0    8696    .055       0    8987    .075       0
#XS Ineff= 3 ,-1
    1000    5750     505    8987   11724     482    5750    8696   480.1
Permanent Ineff=
       F       F       F
Bank Sta=8696,8987
XS Rating Curve= 0 ,0
Exp/Cntr=0.3,0.1

Type RM Length L Ch R = 1 ,153249  ,860,1362,950
BEGIN DESCRIPTION:
This cross section corresponds to cross section 153293 of the non-georeferenced CDC model which was the source of this model.
END DESCRIPTION:
XS GIS Cut Line= 6
  2376636.219919 6977489.5995078   2376636.19985   6977489.38894
   2375925.88992   6970036.66008    2375036.4291   6968815.61888
   2374455.51884   6966908.72014 2374455.4571995 6966908.5177987
#Sta/Elev= 30
    1000   506.3    1336   500.1    1464   490.1    1471     484    1659   492.3
    1946   492.2    2009   485.8    2050     496    2167   486.3    2588   493.9
    2797   483.1    2880   492.8    2951   483.2    4107   482.8    4273   476.4
    6785   471.1    7208   485.3    7297   478.4    8226   478.2    9049   482.1
    9130     448    9170     445    9256   479.7    9663     483   10084   480.2
   10116   473.3   10725   473.3   10805   489.1   11741   490.3   11991   503.1
#Mann= 6 ,-1,0
    1000     .09       0    4273    .055       0    7297     .13       0
    8226    .075       0    9049    .055       0    9256     .08       0
#XS Ineff= 5 ,-1
    1000    5050     505    9709   10752     482    9256    9709   479.7
    6908    9049     479    5050    6908   476.4
Permanent Ineff=
       F       T       F       F       T
Bank Sta=9049,9256
XS Rating Curve= 0 ,0
Exp/Cntr=0.3,0.1

Type RM Length L Ch R = 1 ,151887  ,802,798,1053
BEGIN DESCRIPTION:
This cross section corresponds to cross section 151932 of the non-georeferenced CDC model which was the source of this model.
END DESCRIPTION:
XS GIS Cut Line= 3
  2378026.881175 6978442.6706785   2376553.11898   6968657.02012
 2374705.7128756 6966785.1333997
#Sta/Elev= 30
    1000   521.1    1072   505.9    1923     498    2058   487.5    3003   481.5
    3604   483.2    3634   488.6    3671   482.6    4838   480.1    6259   480.1
    6278   485.4    6332   473.9    6484   480.1    6508   471.1    7773   471.1
    7899   480.5    8019   471.4    8232   471.4    8278   484.3    8916   480.8
    9040   488.5    9092   480.1    9303   472.6   11192   479.5   11260     447
   11288   444.5   11362   474.8   11416   478.5   12856   482.5   13526     506
#Mann= 4 ,-1,0
    1000    .085       0    9092     .13       0   11192     .05       0
   11416     .13       0
#XS Ineff= 5 ,-1
    1000    5100     505    6300    8260   480.1   11416   13526   477.5
    5100    6300   475.6    8260   11192   475.6
Permanent Ineff=
       F       T       F       F       F
Bank Sta=11192,11416
XS Rating Curve= 0 ,0
Exp/Cntr=0.3,0.1

Type RM Length L Ch R = 1 ,151089  ,429,760,898
BEGIN DESCRIPTION:
This cross section corresponds to cross section 151136 of the non-georeferenced CDC model which was the source of this model.
END DESCRIPTION:
XS GIS Cut Line= 6
  2378559.604136 6978518.6939663 2378062.9548674 6973839.7476156
 2377819.8549599 6971550.0546884 2377544.9998666 6968961.7101276
 2376505.2814736 6967247.5255638 2375911.1061527 6966268.0068536
#Sta/Elev= 30
    1000   514.6    1078   491.5    1672   484.4    4565   488.6    5234   480.1
    5341   489.3    5446   475.5    7659   471.5    7691   487.3    7753   487.3
    7790   471.5    7924   471.5    7979     489    8024   471.5    8378   483.8
    8486   472.3    8727   481.1    8817   471.4    9157     492    9203   505.7
    9276   486.2    9352   494.4    9439   477.5    9914   477.5   11748   477.6
   11800   447.5   11840     444   11959   480.1   12702   478.9   13761   504.7
#Mann= 4 ,-1,0
    1000     .08       0    9914     .13       0   11748     .05       0
   11959     .13       0
#XS Ineff= 5 ,-1
    1000    4350     505    5374    9416   480.1   11959   13761   478.9
    4350    5374     473    9416   11748     473
Permanent Ineff=
       F       T       F       F       F
Bank Sta=11748,11959
XS Rating Curve= 0 ,0
Exp/Cntr=0.3,0.1

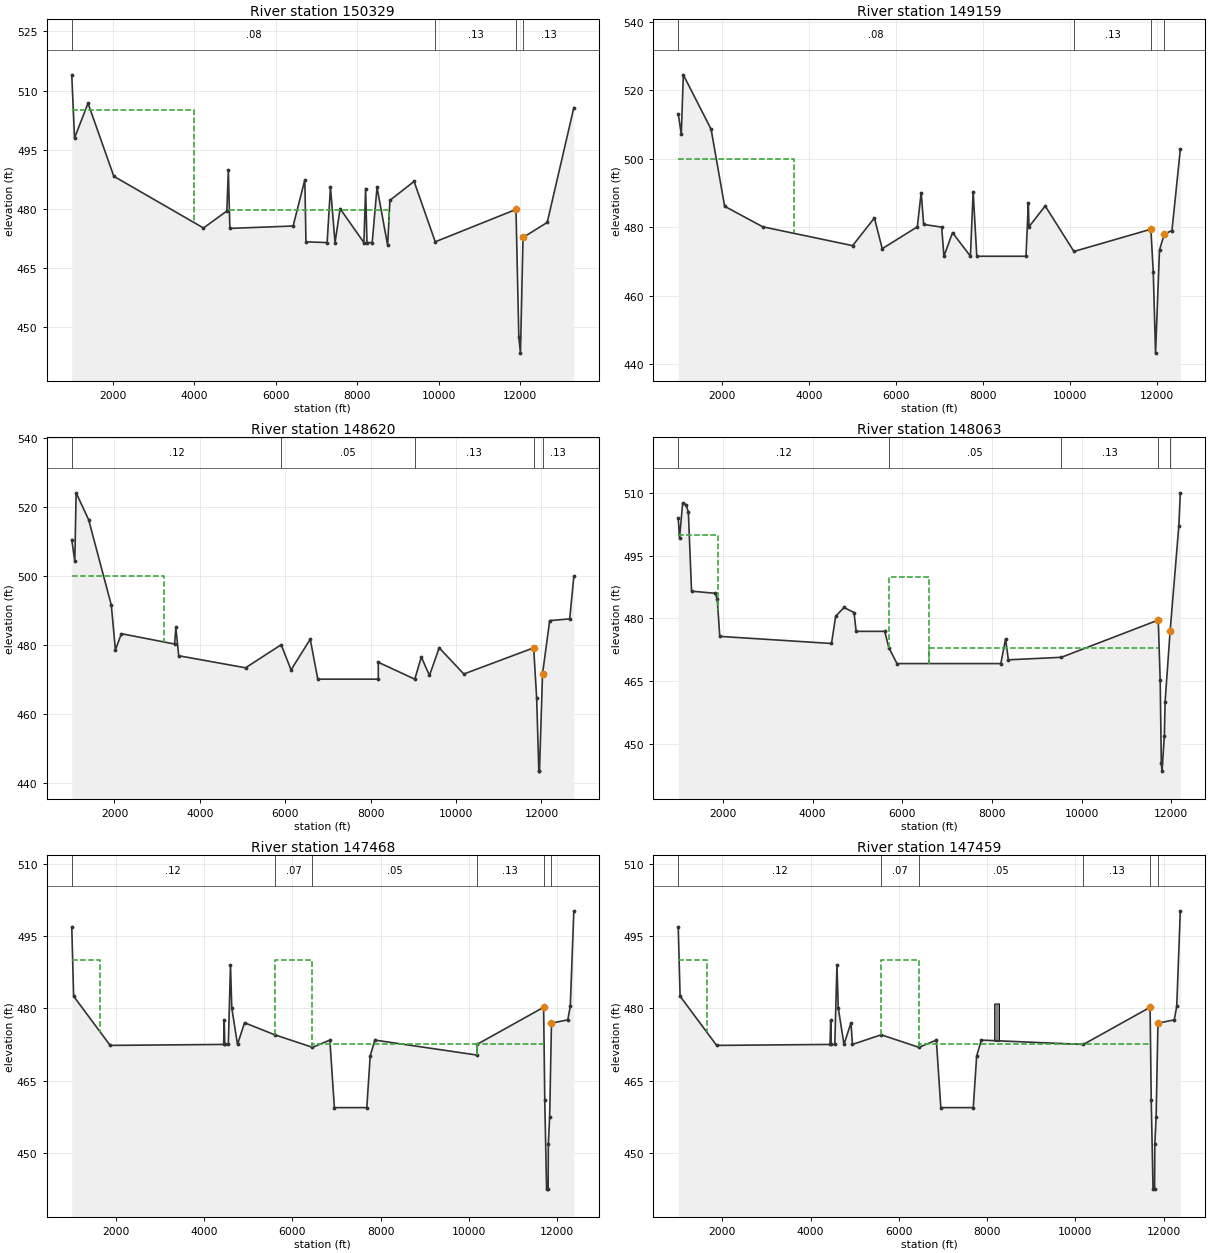
Type RM Length L Ch R = 1 ,150329  ,549,1170,1358
BEGIN DESCRIPTION:
This cross section corresponds to cross section 150374 of the non-georeferenced CDC model which was the source of this model.
END DESCRIPTION:
XS GIS Cut Line= 3
   2378782.41111   6978502.98599   2378075.32886       6968907.1
 2377143.8019386 6966383.4347682
#Sta/Elev= 30
    1000     514    1067     498    1399   506.8    2031   488.3    4230   475.2
    4803   479.5    4839   489.9    4877   475.1    6428   475.7    6715   487.4
    6743   471.7    7262   471.5    7344   485.5    7456   471.5    7580   480.1
    8164   471.5    8206   485.2    8239   471.5    8367   471.5    8486   485.5
    8746   470.8    8801   482.2    9394     487    9913   471.7   11893   479.9
   11963   447.5   12003   443.5   12066   472.8   12659   476.6   13312   505.7
#Mann= 4 ,-1,0
    1000     .08       0    9913     .13       0   11893     .05       0
   12066     .13       0
#XS Ineff= 5 ,-1
    1000    4000     505    4858    8774   479.8    4000    4858     473
    8774   11893     473   12066   13312   472.8
Permanent Ineff=
       F       T       F       F       F
Bank Sta=11893,12066
XS Rating Curve= 0 ,0
Exp/Cntr=0.3,0.1

Type RM Length L Ch R = 1 ,149159  ,480,539,550
BEGIN DESCRIPTION:
This cross section corresponds to cross section 149202 of the non-georeferenced CDC model which was the source of this model.
END DESCRIPTION:
XS GIS Cut Line= 2
  2379060.506912 6978457.0551653   2378708.55692   6966928.42614
#Sta/Elev= 30
    1000   513.1    1070   507.2    1117   524.5    1755   508.6    2066   486.1
    2943   480.1    5006   474.6    5507   482.7    5686   473.7    6492   480.1
    6581   490.1    6638   480.8    7052     480    7104   471.5    7301   478.4
    7712   471.5    7775   490.3    7859   471.5    8989   471.5    9043   487.1
    9057   480.1    9430   486.2   10090   472.9   11858   479.4   11913   466.8
   11965   443.2   12056   473.3   12165     478   12342     479   12534   502.7
#Mann= 4 ,-1,0
    1000     .08       0   10090     .13       0   11858     .05       0
   12165     .12       0
#XS Ineff= 5 ,-1
    1000    3650     500    6730    9023     479   12165   12534   476.5
    3650    6730     473    9023   11858     473
Permanent Ineff=
       F       T       F       F       F
Bank Sta=11858,12165
XS Rating Curve= 0 ,0
Exp/Cntr=0.3,0.1

Type RM Length L Ch R = 1 ,148620  ,899,557,500
BEGIN DESCRIPTION:
This cross section corresponds to cross section 148663 of the non-georeferenced CDC model which was the source of this model.
END DESCRIPTION:
XS GIS Cut Line= 3
  2379467.410259 6978522.3299658   2379466.17516   6978455.19901
   2379251.08208   6966764.31984
#Sta/Elev= 30
    1000   510.6    1071   504.4    1102   524.2    1395   516.4    1926   491.6
    2022   478.6    2162   483.3    3408   480.3    3438   485.1    3505   476.9
    5071   473.4    5905   480.1    6136   472.8    6586   481.7    6762   470.1
    8180   470.1    8180     475    9034   470.1    9187   476.5    9379   471.2
    9606   479.2   10183   471.6   11819   479.2   11889   464.6   11940   443.4
   11955   443.4   12027   471.7   12194   487.1   12663   487.6   12760     500
#Mann= 5 ,-1,0
    1000     .12       0    5905     .05       0    9034     .13       0
   11819     .05       0   12027     .13       0
#XS Ineff= 3 ,-1
    1000    3150     500    3150   11819   473.1   12027   12760   471.7
Permanent Ineff=
       F       F       F
Bank Sta=11819,12027
XS Rating Curve= 0 ,0
Exp/Cntr=0.3,0.1

Type RM Length L Ch R = 1 ,148063  ,801,595,551
BEGIN DESCRIPTION:
This cross section corresponds to cross section 148106 of the non-georeferenced CDC model which was the source of this model.
END DESCRIPTION:
XS GIS Cut Line= 3
  2380663.699414 6978369.1204873   2380042.69008   6968821.25011
 2379742.1518695 6967213.1374916
#Sta/Elev= 30
    1000   503.9    1029   499.2    1098   507.5    1173   507.2    1226   505.4
    1297   486.5    1819     486    1870   484.7    1927   475.7    4420     474
    4513   480.5    4699   482.6    4923   481.4    4970   476.9    5608   476.9
    5700     473    5881   469.2    8199   469.2    8304   475.1    8367   470.1
    9550   470.7   11712   479.6   11755   465.2   11780   445.5   11795   443.5
   11848   451.9   11864     460   11976   476.9   12171   502.1   12204     510
#Mann= 5 ,-1,0
    1000     .12       0    5700     .05       0    9550     .13       0
   11712     .05       0   11976     .13       0
#XS Ineff= 4 ,-1
    1000    1887     500    5700    6600     490    1887    5700     473
    6600   11712     473
Permanent Ineff=
       F       T       F       F
Bank Sta=11712,11976
XS Rating Curve= 0 ,0
Exp/Cntr=0.3,0.1

Type RM Length L Ch R = 1 ,147468  ,9,9,9
BEGIN DESCRIPTION:
This cross section corresponds to cross section 147512 of the non-georeferenced CDC model which was the source of this model.
END DESCRIPTION:
XS GIS Cut Line= 5
  2381689.690602 6978296.0682551   2381689.67596   6978295.92505
   2380694.93189   6968566.94484   2380231.07586   6967037.73793
  2380231.034075 6967037.6001762
#Sta/Elev= 30
    1000   496.9    1042   482.5    1870   472.3    4441   472.5    4455   477.5
    4468   472.5    4548   472.5    4597     489    4626   480.1    4756   472.5
    4915     477    5600   474.5    6454   471.9    6849   473.4    6951   459.4
    7686   459.4    7763   470.1    7869   473.4   10182   470.3   10182   472.5
   11693   480.2   11719     461   11760   442.5   11795   442.5   11800   451.8
   11830   457.5   11871   476.9   12241   477.6   12297   480.4   12378   500.2
#Mann= 6 ,-1,0
    1000     .12       0    5600     .07       0    6454     .05       0
   10182     .13       0   11693    .055       0   11871     .13       0
#XS Ineff= 7 ,-1
    1000    1650     490    5600    6450     490   11871   12378   476.9
    6450    8424   472.5    8424   10182   472.5   10182   11693   472.5
    1650    5600   472.5
Permanent Ineff=
       F       T       F       F       T       F       F
Bank Sta=11693,11871
XS Rating Curve= 0 ,0
Exp/Cntr=0.3,0.1

Type RM Length L Ch R = 1 ,147459  ,42,42,42
BEGIN DESCRIPTION:
This cross section corresponds to cross section 147496 of the non-georeferenced CDC model which was the source of this model.
THIS SECTION WAS COPIED FROM 1475+12
1) THE 110' BLOCKED OBSTRUCTION MODELS THE BERM THAT THE TANKS WILL BE ELEVATED ON
END DESCRIPTION:
XS GIS Cut Line= 5
  2381698.477657 6978294.5800697  2381698.463016 6978294.4368689
 2380703.7189428  6968565.456655 2380239.8629152 6967036.2497397
 2380239.8211315 6967036.1119901
#Sta/Elev= 30
    1000   496.9    1042   482.5    1870   472.3    4441   472.5    4455   477.5
    4468   472.5    4548   472.5    4597     489    4626   480.1    4756   472.5
    4915     477    4948   472.5    5600   474.5    6454   471.9    6849   473.4
    6951   459.4    7686   459.4    7763   470.1    7869   473.4   10182   472.5
   11693   480.2   11719     461   11760   442.5   11795   442.5   11800   451.8
   11830   457.5   11871   476.9   12241   477.6   12297   480.4   12378   500.2
#Mann= 6 ,-1,0
    1000     .12       0    5600     .07       0    6454     .05       0
   10182     .13       0   11693    .055       0   11871     .13       0
#XS Ineff= 5 ,-1
    1000    1650     490    5600    6450     490   11871   12378   476.9
    6450   11693   472.5    1650    5600   472.5
Permanent Ineff=
       F       T       F       F       F
#Block Obstruct= 2 ,-1
                            8160    8270     481
Bank Sta=11693,11871
XS Rating Curve= 0 ,0
Exp/Cntr=0.3,0.1

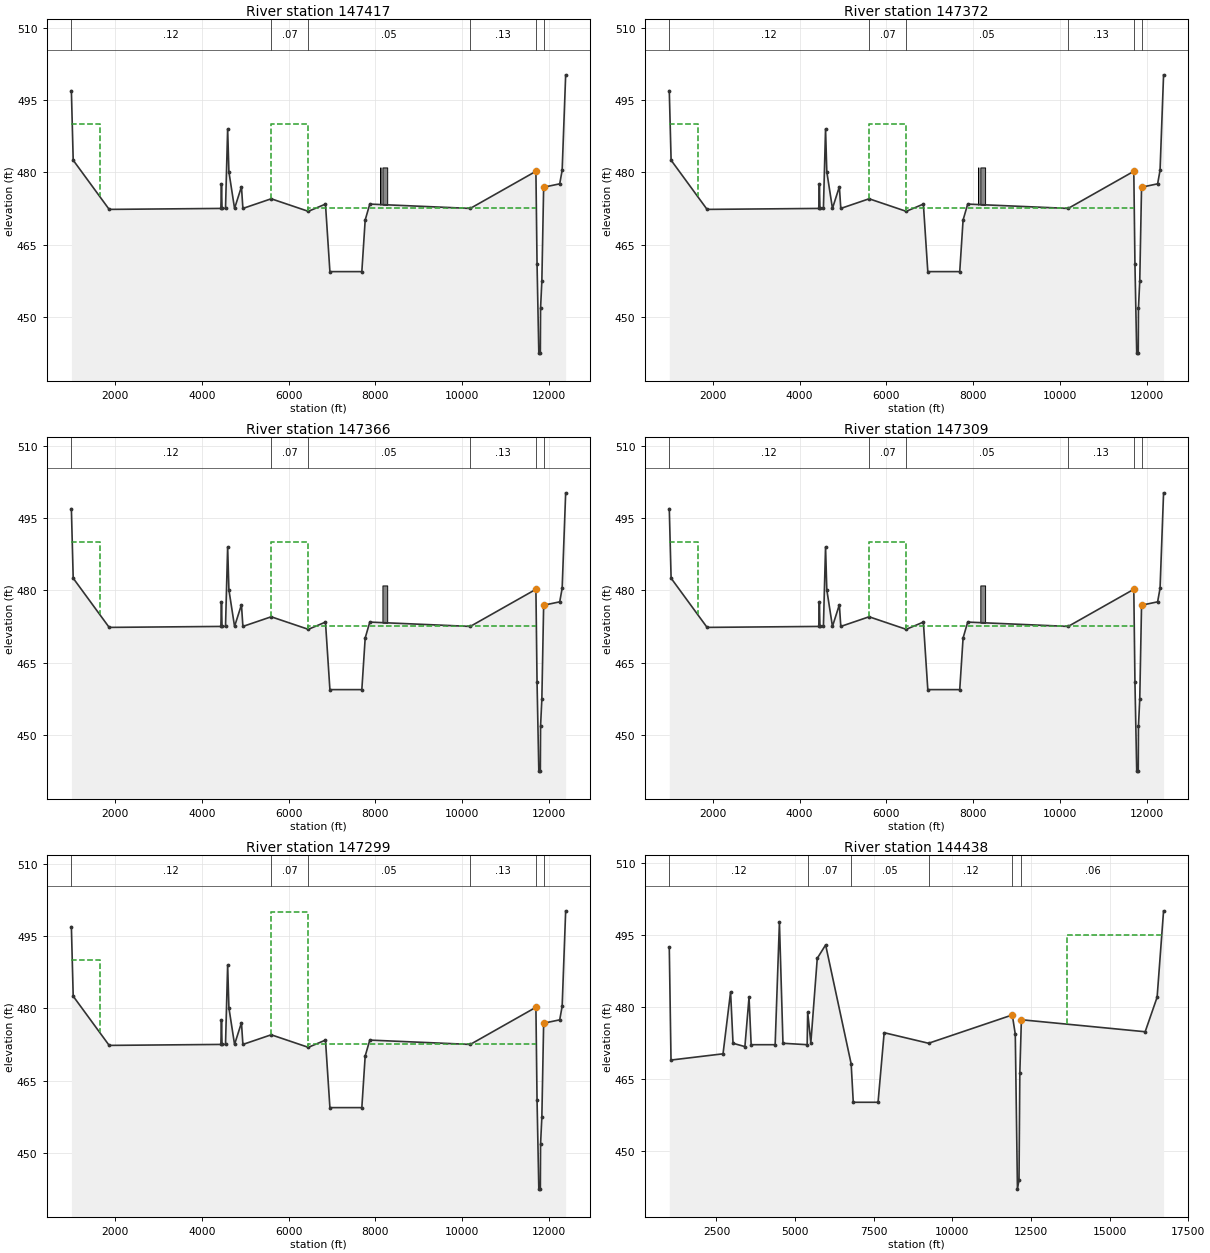
Type RM Length L Ch R = 1 ,147417  ,45,45,45
BEGIN DESCRIPTION:
This cross section corresponds to cross section 147424 of the non-georeferenced CDC model which was the source of this model.
THIS SECTION WAS COPIED FROM 1475+12
1) THE 10'  BLOCKED OBSTRUCTION REPRESENTS THE GAS WELL HEAD
2) THE 110' BLOCKED OBSTRUCTION MODELS THE BERM THAT THE TANKS WILL BE ELEVATED ON
END DESCRIPTION:
XS GIS Cut Line= 5
  2381740.376851 6978287.4849395   2381740.36221 6978287.3417387
 2380745.6181372 6968558.3615248 2380281.7621096 6967029.1546095
 2380281.7203258 6967029.0168598
#Sta/Elev= 30
    1000   496.9    1042   482.5    1870   472.3    4441   472.5    4455   477.5
    4468   472.5    4548   472.5    4597     489    4626   480.1    4756   472.5
    4915     477    4948   472.5    5600   474.5    6454   471.9    6849   473.4
    6951   459.4    7686   459.4    7763   470.1    7869   473.4   10182   472.5
   11693   480.2   11719     461   11760   442.5   11795   442.5   11800   451.8
   11830   457.5   11871   476.9   12241   477.6   12297   480.4   12378   500.2
#Mann= 6 ,-1,0
    1000     .12       0    5600     .07       0    6454     .05       0
   10182     .13       0   11693    .055       0   11871     .13       0
#XS Ineff= 5 ,-1
    1000    1650     490    5600    6450     490   11871   12378   476.9
    6450   11693   472.5    1650    5600   472.5
Permanent Ineff=
       F       T       F       F       F
#Block Obstruct= 3 ,-1
                            8107    8117     481    8160    8270     481
Bank Sta=11693,11871
XS Rating Curve= 0 ,0
Exp/Cntr=0.3,0.1

Type RM Length L Ch R = 1 ,147372  ,6,6,6
BEGIN DESCRIPTION:
This cross section corresponds to cross section 147414 of the non-georeferenced CDC model which was the source of this model.
THIS SECTION WAS COPIED FROM 1475+12
1) THE 10'  BLOCKED OBSTRUCTION REPRESENTS THE GAS WELL HEAD
2) THE 110' BLOCKED OBSTRUCTION MODELS THE BERM THAT THE TANKS WILL BE ELEVATED ON
END DESCRIPTION:
XS GIS Cut Line= 5
   2381785.09625  6978280.588956  2381785.081609 6978280.4457552
  2380790.337536 6968551.4655412 2380326.4815083 6967022.2586259
 2380326.4397246 6967022.1208763
#Sta/Elev= 30
    1000   496.9    1042   482.5    1870   472.3    4441   472.5    4455   477.5
    4468   472.5    4548   472.5    4597     489    4626   480.1    4756   472.5
    4915     477    4948   472.5    5600   474.5    6454   471.9    6849   473.4
    6951   459.4    7686   459.4    7763   470.1    7869   473.4   10182   472.5
   11693   480.2   11719     461   11760   442.5   11795   442.5   11800   451.8
   11830   457.5   11871   476.9   12241   477.6   12297   480.4   12378   500.2
#Mann= 6 ,-1,0
    1000     .12       0    5600     .07       0    6454     .05       0
   10182     .13       0   11693    .055       0   11871     .13       0
#XS Ineff= 5 ,-1
    1000    1650     490    5600    6450     490   11871   12378   476.9
    6450   11693   472.5    1650    5600   472.5
Permanent Ineff=
       F       T       F       F       F
#Block Obstruct= 3 ,-1
                            8107    8117     481    8160    8270     481
Bank Sta=11693,11871
XS Rating Curve= 0 ,0
Exp/Cntr=0.3,0.1

Type RM Length L Ch R = 1 ,147366  ,57,57,57
BEGIN DESCRIPTION:
This cross section corresponds to cross section 147404 of the non-georeferenced CDC model which was the source of this model.
THIS SECTION WAS COPIED FROM 1475+12
1) THE 110' BLOCKED OBSTRUCTION MODELS THE BERM THAT THE TANKS WILL BE ELEVATED ON
END DESCRIPTION:
XS GIS Cut Line= 5
  2381790.800307 6978279.7418448  2381790.785666  6978279.598644
 2380796.0415928 6968550.6184301 2380332.1855652 6967021.4115147
 2380332.1437815 6967021.2737651
#Sta/Elev= 30
    1000   496.9    1042   482.5    1870   472.3    4441   472.5    4455   477.5
    4468   472.5    4548   472.5    4597     489    4626   480.1    4756   472.5
    4915     477    4948   472.5    5600   474.5    6454   471.9    6849   473.4
    6951   459.4    7686   459.4    7763   470.1    7869   473.4   10182   472.5
   11693   480.2   11719     461   11760   442.5   11795   442.5   11800   451.8
   11830   457.5   11871   476.9   12241   477.6   12297   480.4   12378   500.2
#Mann= 6 ,-1,0
    1000     .12       0    5600     .07       0    6454     .05       0
   10182     .13       0   11693    .055       0   11871     .13       0
#XS Ineff= 5 ,-1
    1000    1650     490    5600    6450     490   11871   12378   476.9
    6450   11693   472.5    1650    5600   472.5
Permanent Ineff=
       F       T       F       F       F
#Block Obstruct= 2 ,-1
                            8160    8270     481
Bank Sta=11693,11871
XS Rating Curve= 0 ,0
Exp/Cntr=0.3,0.1

Type RM Length L Ch R = 1 ,147309  ,10,10,10
BEGIN DESCRIPTION:
This cross section corresponds to cross section 147346 of the non-georeferenced CDC model which was the source of this model.
THIS SECTION WAS COPIED FROM 1475+12
1) THE 110' BLOCKED OBSTRUCTION MODELS THE BERM THAT THE TANKS WILL BE ELEVATED ON
END DESCRIPTION:
XS GIS Cut Line= 3
      2381848.81       6978274.3      2380854.37      6968545.83
       2380389.6      6967014.01
#Sta/Elev= 30
    1000   496.9    1042   482.5    1870   472.3    4441   472.5    4455   477.5
    4468   472.5    4548   472.5    4597     489    4626   480.1    4756   472.5
    4915     477    4948   472.5    5600   474.5    6454   471.9    6849   473.4
    6951   459.4    7686   459.4    7763   470.1    7869   473.4   10182   472.5
   11693   480.2   11719     461   11760   442.5   11795   442.5   11800   451.8
   11830   457.5   11871   476.9   12241   477.6   12297   480.4   12378   500.2
#Mann= 6 ,-1,0
    1000     .12       0    5600     .07       0    6454     .05       0
   10182     .13       0   11693    .055       0   11871     .13       0
#XS Ineff= 5 ,-1
    1000    1650     490    5600    6450     490   11871   12378   476.9
    6450   11693   472.5    1650    5600   472.5
Permanent Ineff=
       F       T       F       F       F
#Block Obstruct= 2 ,-1
                            8160    8270     481
Bank Sta=11693,11871
XS Rating Curve= 0 ,0
Exp/Cntr=0.3,0.1

Type RM Length L Ch R = 1 ,147299  ,725,2861,2799
BEGIN DESCRIPTION:
This cross section corresponds to cross section 147336 of the non-georeferenced CDC model which was the source of this model.
THIS SECTION WAS COPIED FROM 1475+12 AND MODELS THE AREA IMMEDIATELY DOWNSTREAM OF THE BLOCKED OBSTRUCTION
---------------------------------------------------------------------
CDC FW122804-01 Gas Well Duck Lake No.1
Located in LOB.
Cross-sections 147336 - 147496
---------------------------------------------------------------------
END DESCRIPTION:
XS GIS Cut Line= 3
       2381859.3      6978272.91       2380864.8      6968545.85
      2380399.76      6967012.49
#Sta/Elev= 30
    1000   496.9    1042   482.5    1870   472.3    4441   472.5    4455   477.5
    4468   472.5    4548   472.5    4597     489    4626   480.1    4756   472.5
    4915     477    4948   472.5    5600   474.5    6454   471.9    6849   473.4
    6951   459.4    7686   459.4    7763   470.1    7869   473.4   10182   472.5
   11693   480.2   11719     461   11760   442.5   11795   442.5   11800   451.8
   11830   457.5   11871   476.9   12241   477.6   12297   480.4   12378   500.2
#Mann= 6 ,-1,0
    1000     .12       0    5600     .07       0    6454     .05       0
   10182     .13       0   11693    .055       0   11871     .13       0
#XS Ineff= 5 ,-1
    5600    6450     500    1000    1650     490   11871   12378   476.9
    6450   11693   472.5    1650    5600   472.5
Permanent Ineff=
       T       F       F       F       F
Bank Sta=11693,11871
XS Rating Curve= 0 ,0
Exp/Cntr=0.3,0.1

Type RM Length L Ch R = 1 ,144438  ,760,1810,760
BEGIN DESCRIPTION:
This cross section corresponds to cross section 144480 of the non-georeferenced CDC model which was the source of this model.
END DESCRIPTION:
XS GIS Cut Line= 6
  2382309.234191 6978250.7684955   2382309.22295   6978250.58689
   2381668.19011    6967894.5889   2382944.88999   6966391.44886
   2384525.29496   6963417.65101 2384525.3803485 6963417.4903373
#Sta/Elev= 30
    1000   492.4    1055   468.9    2709   470.2    2949   483.1    3027   472.4
    3404   471.7    3536     482    3603   472.1    4366   472.1    4502   497.6
    4615   472.4    5384   472.1    5400   478.9    5501   472.5    5705   490.1
    5971   492.9    6783   468.1    6850   460.1    7638   460.1    7832   474.6
    9244   472.4   11906   478.3   12001   474.3   12070     442   12120     444
   12146   466.3   12195   477.3   16131   474.8   16511     482   16716     500
#Mann= 6 ,-1,0
    1000     .12       0    5400     .07       0    6783     .05       0
    9244     .12       0   11906     .05       0   12195     .06       0
#XS Ineff= 6 ,-1
   13630   16716     495    3542    4405     479   12195   13630   475.3
    7881   10260   472.4    1000    3542   472.4    4405    7881   472.4
Permanent Ineff=
       T       T       F       T       F       F
Bank Sta=11906,12195
XS Rating Curve= 0 ,0
Exp/Cntr=0.3,0.1

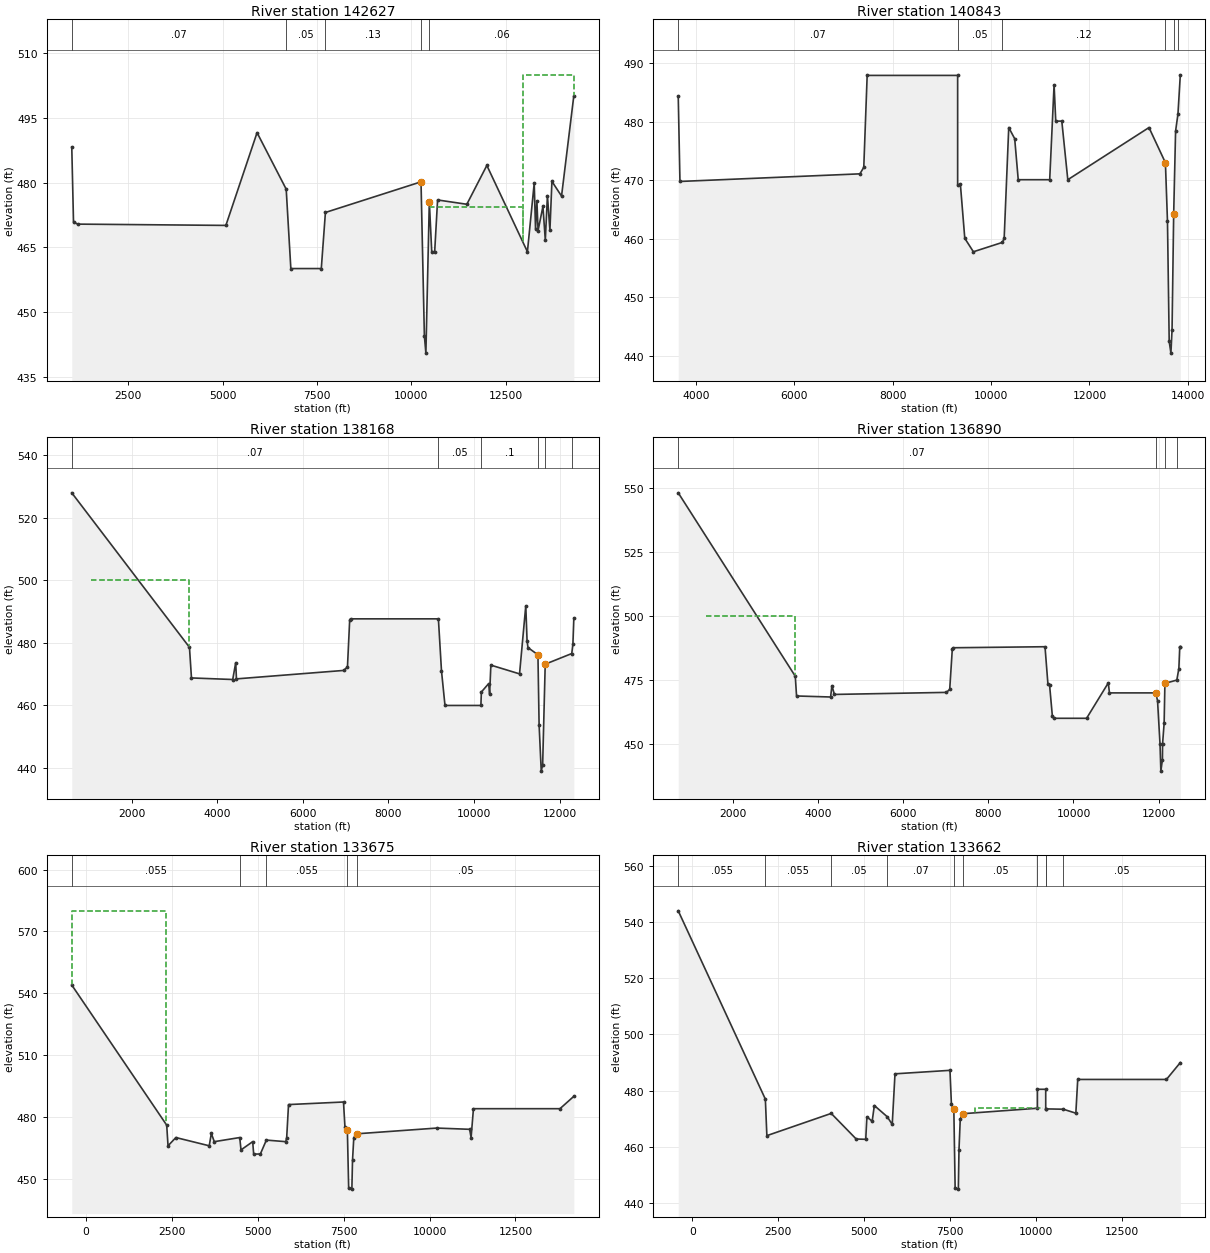
Type RM Length L Ch R = 1 ,142627  ,900,1784,1350
BEGIN DESCRIPTION:
This cross section corresponds to cross section 142669 of the non-georeferenced CDC model which was the source of this model.
---------------------------------------------------------------------
CDC FW070799-01 Links at Waterchase
Cross-section 142669 - 144480
Located in ROB.
---------------------------------------------------------------------
END DESCRIPTION:
XS GIS Cut Line= 4
  2382949.248654 6978203.3749724   2382551.17916   6969520.17915
   2382718.62994   6967983.55887 2384427.4746787  6965440.382665
#Sta/Elev= 30
    1003   488.3    1049   470.9    1157   470.4    5086   470.1    5912   491.6
    6684   478.5    6807   460.1    7614   460.1    7723   473.1   10256   480.2
   10345   444.5   10385   440.5   10476   475.6   10540     464   10618     464
   10695     476   11470     475   12000     484   13075     464   13255   479.9
   13290   469.3   13326   475.8   13357   468.9   13486   474.5   13549   466.7
   13605     477   13671     469   13724   480.3   13979   476.9   14305   500.2
#Mann= 5 ,-1,0
    1003     .07       0    6684     .05       0    7723     .13       0
   10256    .055       0   10476     .06       0
#XS Ineff= 3 ,-1
   12950   14305     505   10476   12950   474.4    1003   10256     471
Permanent Ineff=
       T       F       F
Bank Sta=10256,10476
XS Rating Curve= 0 ,0
Exp/Cntr=0.3,0.1

Type RM Length L Ch R = 1 ,140843  ,1159,2676,2399
BEGIN DESCRIPTION:
This cross section corresponds to cross section 140885 of the non-georeferenced CDC model which was the source of this model.
---------------------------------------------------------------------
CDC FW121505-1 Bell Station Tract
This project is located between cross-sections 140885 - 147512 and within ineffective flow area, therefore the model was not changed.
---------------------------------------------------------------------
END DESCRIPTION:
XS GIS Cut Line= 4
  2383585.617493 6978079.0141806  2383585.266537 6978041.0158013
   2383497.76388   6968567.02686 2384069.4795409 6968167.2810709
#Sta/Elev= 30
    3638   484.4    3673   469.8    7332   471.1    7411   472.2    7480   487.9
    9320   487.9    9320   469.2    9376   469.3    9465   460.1    9640   457.8
   10231   459.4   10266   460.1   10359     479   10480   477.1   10552   470.1
   11192   470.1   11281   486.3   11315   480.1   11438   480.1   11560   470.1
   13211     479   13545     473   13587     463   13622   442.5   13657   440.5
   13680   444.5   13713   464.2   13752   478.4   13800   481.3   13848     488
#Mann= 6 ,-1,0
    3638     .07       0    9320     .05       0   10231     .12       0
   13545    .055       0   13713     .12       0   13800     .03       0
#XS Ineff= 2 , 0
           13545   472.8   13713           464.2
Permanent Ineff=
       F       F
Bank Sta=13545,13713
XS Rating Curve= 0 ,0
Exp/Cntr=0.3,0.1

Type RM Length L Ch R = 1 ,138168  ,580,1278,800
BEGIN DESCRIPTION:
This cross section corresponds to cross section 138208 of the non-georeferenced CDC model which was the source of this model.
END DESCRIPTION:
XS GIS Cut Line= 6
2384648.456771846980829.016529662384647.088867926980379.01860873
  2384640.097359 6978079.0292351  2384637.847917  6977339.032654
   2384616.20915   6970220.55013 2385065.8238786 6969190.9559315
#Sta/Elev= 30
     602     528    3352   478.6    3399   468.8    4363   468.3    4433   473.7
    4450   468.5    6954   471.2    7044   472.3    7096   487.3    7116   487.7
    9169   487.7    9241   471.1    9323     460   10162     460   10173   464.3
   10344     467   10366   463.6   10395   472.9   11065   470.1   11211   491.9
   11241   480.6   11263   478.5   11495   476.2   11522   453.9   11572     439
   11605     441   11665   473.2   12285   476.6   12312   479.6   12334     488
#Mann= 6 ,-1,0
     602     .07       0    9169     .05       0   10173      .1       0
   11495     .05       0   11665     .08       0   12285     .03       0
#XS Ineff= 1 ,-1
    1052    3352     500
Permanent Ineff=
       F
Bank Sta=11495,11665
XS Rating Curve= 0 ,0
Exp/Cntr=0.3,0.1

Type RM Length L Ch R = 1 ,136890  ,822,3214,163
BEGIN DESCRIPTION:
This cross section corresponds to cross section 136930 of the non-georeferenced CDC model which was the source of this model.
---------------------------------------------------------------------
CDC FW020400-01 Lakeview Addition
Cross-sections 136930 - 138208
---------------------------------------------------------------------
Project located in LOB outside of effective flow limits, therefore not included in model.
END DESCRIPTION:
XS GIS Cut Line= 6
2385275.657742316980676.425658222385269.597392316980026.45391102
  2385249.169351 6977835.5491447   2385178.10894      6970214.33
   2385741.97002   6969485.02896   2385756.76204 6969072.7010796
#Sta/Elev= 30
     713     548    3463   476.5    3493   468.8    4293   468.4    4324   472.8
    4382   469.4    7016   470.2    7092   471.4    7153   487.2    7177   487.6
    9331     488    9400   473.3    9439   472.9    9503   461.1    9544   460.1
   10308   460.1   10818   473.9   10845     470   11932     470   11975     467
   12033   450.1   12053   439.5   12090     444   12093   450.1   12130   458.2
   12148   473.7   12428     475   12476   479.5   12497     488   12510     488
#Mann= 4 ,-1,0
     713     .07       0   11932    .055       0   12148    .075       0
   12428     .03       0
#XS Ineff= 1 ,-1
    1363    3462     500
Permanent Ineff=
       F
Bank Sta=11932,12148
XS Rating Curve= 0 ,0
Exp/Cntr=0.3,0.1

Type RM Length L Ch R = 1 ,133675  ,13,13,51
BEGIN DESCRIPTION:
This cross section corresponds to cross section 133780 of the non-georeferenced CDC model which was the source of this model.
END DESCRIPTION:
XS GIS Cut Line= 6
2385770.088200626980461.34365569     2385764.762     6972948.171
     2386087.679     6972344.004     2386004.346     6971094.004
     2386035.596     6969812.754 2386281.8520441 6965971.1535652
#Sta/Elev= 30
    -415     5442349.092     4762386.968     4662616.108     4703586.739     466
3647.913     4723733.838     4684474.462     4704511.788     4644851.551     468
4880.327     462 5074.39     462    5250 468.7645814.548     4685841.647     470
5895.139     486 7495.41 487.245 7537.46  475.13 7607.93 473.446 7645.97 445.307
 7739.03 444.973 7757.61  458.89 7795.31 469.982 7883.29 471.817 10210.8   474.6
 11167.2     47411209.74     470 11278.1     48413796.99     48414200.95     490
#Mann= 5 ,-1,0
    -415    .055       04474.462     .07       0    5250    .055       0
 7607.93     .05       0 7883.29     .05       0
#XS Ineff= 1 ,-1
    -4152334.997     580
Permanent Ineff=
       F
Bank Sta=7607.93,7883.29
XS Rating Curve= 0 ,0
Exp/Cntr=0.3,0.1

Type RM Length L Ch R = 1 ,133662  ,150,157,245
BEGIN DESCRIPTION:
This cross section corresponds to cross section 133770 of the non-georeferenced CDC model which was the source of this model.
---------------------------------------------------------------------
CDC FW121713-1 Revised West Village Creek Quicksilver Pad Site. Cross-section 133537 - 133770.  Modification of CDC FW022811-1
LOMR 17-06-2291P
---------------------------------------------------------------------
END DESCRIPTION:
XS GIS Cut Line= 6
  2386093.2429116980100.065709472386143.589591786974532.85135654
2386214.986206166971139.016547492386246.232170186969415.28086414
2386313.941151736968384.020991912386365.50764199 6965190.8051483
#Sta/Elev= 30
    -415     544 2121.03     477 2165.14     464  4038.3  471.91 4765.89   462.8
 5043.55   462.7 5076.88   470.7 5230.58  469.12  5293.6  474.72 5666.69  470.76
 5814.55     468 5895.14     486 7495.41  487.24 7537.46  475.13 7607.93  473.45
 7645.97  445.31 7739.03  444.97 7757.61  458.89 7795.31  469.98 7883.29  471.82
10040.44  473.7510040.45   480.510282.75   480.510282.76  473.56   10297  473.52
   10795   473.411159.66     47211214.69     48413796.99     48414200.95     490
#Mann= 10 ,-1,0
    -415    .055       0 2121.03    .055       0  4038.3     .05       0
 5666.69     .07       0 7607.93     .05       0 7883.29     .05       0
10040.44    .023       010282.76    .045       0   10297    .023       0
   10795     .05       0
#XS Ineff= 2 ,-1
    8210 10210.9  473.75    4300    5100     468
Permanent Ineff=
       T       T
Bank Sta=7607.93,7883.29
XS Rating Curve= 0 ,0
Exp/Cntr=0.3,0.1

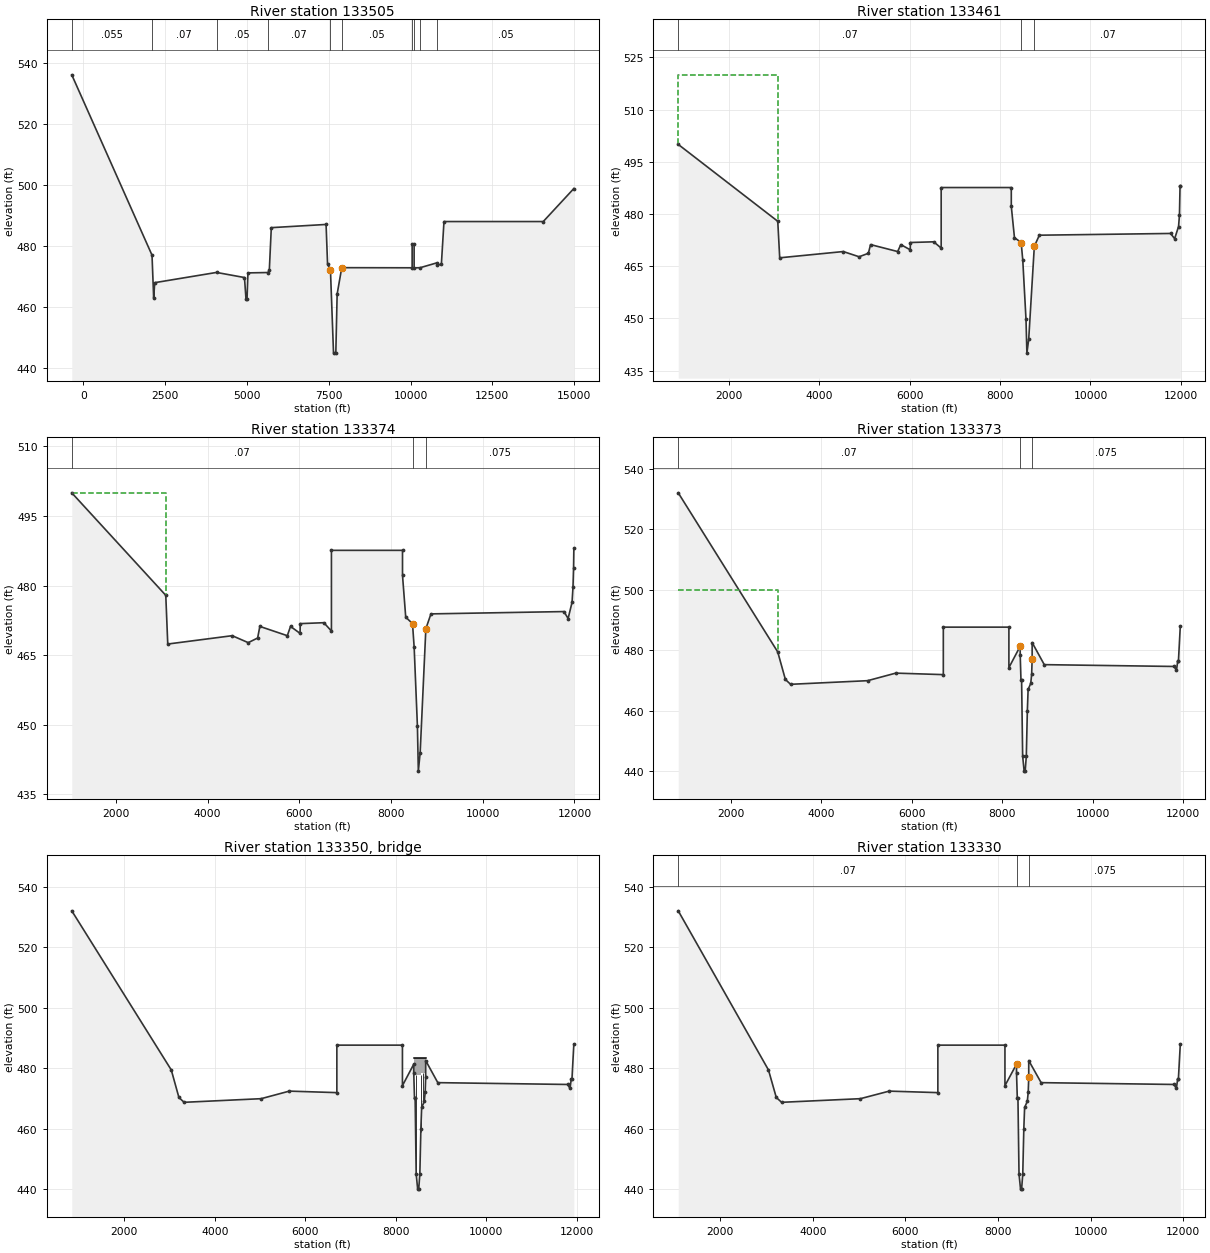
Type RM Length L Ch R = 1 ,133505  ,261,44,24
BEGIN DESCRIPTION:
This cross section corresponds to cross section 133537 of the non-georeferenced CDC model which was the source of this model.
---------------------------------------------------------------------
CDC FW121713-1 Revised West Village Creek Quicksilver Pad Site. Cross-section 133537 - 133770.  Modification of CDC FW022811-1
LOMR 17-06-2291P
---------------------------------------------------------------------
END DESCRIPTION:
XS GIS Cut Line= 4
  2386145.7230666980069.963704692386239.47306603 6972601.4307186
2386341.469593766968393.531413032386393.552927146965107.94113527
#Sta/Elev= 30
    -354     536 2098.35     477 2148.92     463 2180.87     468  4069.8  471.35
 4923.96  469.68 4970.97  462.59 5002.53  462.77 5029.26   471.2 5639.77  471.32
 5682.87     472 5744.07     486 7417.95  487.05 7462.83  474.12 7551.79  472.05
 7645.48  444.97 7715.47  444.95 7756.01  464.27 7897.13  472.91 10048.5  472.87
10048.51   480.5 10108.5   480.510108.51  472.85   10293   472.9   10805  474.49
   10805   473.710941.07     47411021.15     48814055.12     48814989.83   498.8
#Mann= 10 ,-1,0
    -354    .055       0 2098.35     .07       0  4069.8     .05       0
 5639.77     .07       0 7551.79     .05       0 7897.13     .05       0
 10048.5    .023       010108.51    .045       0   10293    .023       0
   10805     .05       0
#XS Ineff= 1 ,-1
    4900    5050     468
Permanent Ineff=
       T
Bank Sta=7551.79,7897.13
XS Rating Curve= 0 ,0
Exp/Cntr=0.3,0.1

Type RM Length L Ch R = 1 ,133461  ,87,87,87
BEGIN DESCRIPTION:
This cross section corresponds to cross section 133499 of the non-georeferenced CDC model which was the source of this model.
END DESCRIPTION:
XS GIS Cut Line= 6
2386146.418972256980152.44936526   2386231.66688   6974492.05996
   2386256.92109   6972842.08393   2386282.17596   6971882.40311
   2386349.52196   6969146.47288 2386351.0024642 6969056.4576885
#Sta/Elev= 30
     888     500    3088   477.9    3131   467.4    4536   469.2    4886   467.7
    5091   468.7    5139   471.2    5738   469.2    5808   471.2    6016   469.7
    6020   471.8    6535     472    6700   470.2    6700   487.6    8250   487.6
    8250   482.2    8320   473.2    8468   471.8    8504   466.7    8575   449.7
    8595     440    8635     444    8759   470.7    8870   473.9   11770   474.4
   11861   472.9   11947   476.4   11967   479.6   11980     488   11986     488
#Mann= 3 ,0,0
     888     .07       0    8468     .05       0    8759     .07       0
#XS Ineff= 1 ,-1
     888    3088     520
Permanent Ineff=
       F
Bank Sta=8468,8759
XS Rating Curve= 0 ,0
Exp/Cntr=0.3,0.1

Type RM Length L Ch R = 1 ,133374  ,1,1,1
BEGIN DESCRIPTION:
This cross section corresponds to cross section 133413 of the non-georeferenced CDC model which was the source of this model.
END DESCRIPTION:
XS GIS Cut Line= 6
2386234.260153036980003.39464063 2386317.1890151 6974496.9877709
 2386342.4432297 6972847.0117402 2386367.6981004 6971887.3309167
 2386435.0440943 6969151.4006931 2386436.5903789 6969057.3860427
#Sta/Elev= 30
    1038     500    3088   477.9    3131   467.4    4536   469.2    4886   467.7
    5091   468.7    5139   471.2    5738   469.2    5808   471.2    6016   469.7
    6020   471.8    6535     472    6700   470.2    6700   487.6    8250   487.6
    8250   482.2    8320   473.2    8468   471.8    8504   466.7    8575   449.7
    8595     440    8635     444    8759   470.7    8870   473.9   11770   474.4
   11861   472.9   11947   476.4   11967   479.6   11980   483.8   11986     488
#Mann= 3 ,0,0
    1038     .07       0    8468    .055       0    8759    .075       0
#XS Ineff= 1 ,-1
    1038    3088     500
Permanent Ineff=
       F
Bank Sta=8468,8759
XS Rating Curve= 0 ,0
Exp/Cntr=0.3,0.1

Type RM Length L Ch R = 1 ,133373  ,43,43,43
BEGIN DESCRIPTION:
This cross section corresponds to cross section 133412 of the non-georeferenced CDC model which was the source of this model.
END DESCRIPTION:
XS GIS Cut Line= 6
 2386232.96956946980154.93454859 2386318.1798267 6974497.0448574
 2386343.4340413 6972847.0688267 2386368.6889121 6971887.3880032
  2386436.034906 6969151.4577796 2386437.6058582  6969055.943332
#Sta/Elev= 30
     839     532    3039   479.4    3208   470.3    3323   468.7    5026   469.9
    5649   472.4    6700   471.9    6700   487.6    8150   487.6    8150   474.2
    8400   481.3    8400   478.5    8417     470    8431     470    8454     445
    8487     440    8510     440    8535     445    8558     460    8575     467
    8633     469    8653     472    8664     477    8664   482.5    8932   475.2
   11802   474.6   11855   473.3   11883   476.4   11898   476.3   11940     488
#Mann= 3 ,0,0
     839     .07       0    8400    .055       0    8664    .075       0
#XS Ineff= 1 ,-1
     839    3039     500
Permanent Ineff=
       F
Bank Sta=8400,8664
XS Rating Curve= 0 ,0
Exp/Cntr=0.3,0.1

Type RM Length L Ch R = 3 ,133350  ,,,
BEGIN DESCRIPTION:
Arlington-Bedford Road
END DESCRIPTION:
Node Name=Arl-Bedford Road
Bridge Culvert--1,0,-1,-1, 0
Deck Dist Width WeirC Skew NumUp NumDn MinLoCord MaxHiCord MaxSubmerge Is_Ogee
1,40,2.6,0, 11, 11, , , 0.95, 0, ,,,
    8400    8454    8454    8457    8487    8535    8555    8558    8558    8610
    8664
   483.3   483.3   483.3   483.3   483.3   483.3   483.3   483.3   483.3   483.3
   483.3
   478.5   478.5   477.6   477.6   477.6   477.6   477.6   477.6   478.5   478.5
   478.5
    8400    8454    8454    8457    8487    8535    8555    8558    8558    8610
    8664
   483.3   483.3   483.3   483.3   483.3   483.3   483.3   483.3   483.3   483.3
   483.3
   478.5   478.5   477.6   477.6   477.6   477.6   477.6   477.6   478.5   478.5
   478.5
Pier Skew, UpSta & Num, DnSta & Num=  ,8456.5, 2 ,8456.5, 2 , 0 , 0 , 0 ,,
       3       3
     440     480
       3       3
     440     480
Pier Skew, UpSta & Num, DnSta & Num=  ,8556.5, 2 ,8556.5, 2 , 0 , 0 , 0 ,,
       3       3
     440     480
       3       3
     440     480
Pier Skew, UpSta & Num, DnSta & Num=  ,8612.5, 2 ,8612.5, 2 , 0 , 0 , 0 ,,
       3       3
     440     480
       3       3
     440     480
BR Coef= 1 , 0 , 0 ,1.05, 0 ,,,0.8,-1,0.5,1,
WSPro=,,,, 1 ,,,, 0 ,,,, 0 ,,,,-1 ,-1 ,-1 , 0 , 0 , 0 , 0 , 0
BC Design=,, 0 ,, 0 ,,,,,,
BC HTab HWMax=488
BC Use User HTab Curves=0
BC User HTab FreeFlow(D)= 0

Type RM Length L Ch R = 1 ,133330  ,1,1,1
BEGIN DESCRIPTION:
This cross section corresponds to cross section 133370 of the non-georeferenced CDC model which was the source of this model.
END DESCRIPTION:
XS GIS Cut Line= 6
  2386288.662539 6980091.7464354 2386321.7441241 6977273.9897628
 2386355.4159727 6974529.6409208 2386389.0891337 6972845.9907448
 2386405.9260423 6971962.0748617 2386462.9288174 6969242.2414974
#Sta/Elev= 30
    1089     532    3039   479.4    3208   470.3    3323   468.7    5026   469.9
    5649   472.4    6700   471.9    6700   487.6    8150   487.6    8150   474.2
    8400   481.3    8400   478.5    8417     470    8431     470    8454     445
    8487     440    8510     440    8535     445    8558     460    8575     467
    8633     469    8653     472    8664     477    8664   482.5    8932   475.2
   11802   474.6   11855   473.3   11883   476.4   11898   476.3   11940     488
#Mann= 3 ,0,0
    1089     .07       0    8400    .055       0    8664    .075       0
#XS Ineff= 2 , 0
       0    8400   468.6    8664       0   473.3
Permanent Ineff=
       F       F
Bank Sta=8400,8664
XS Rating Curve= 0 ,0
Exp/Cntr=0.3,0.1