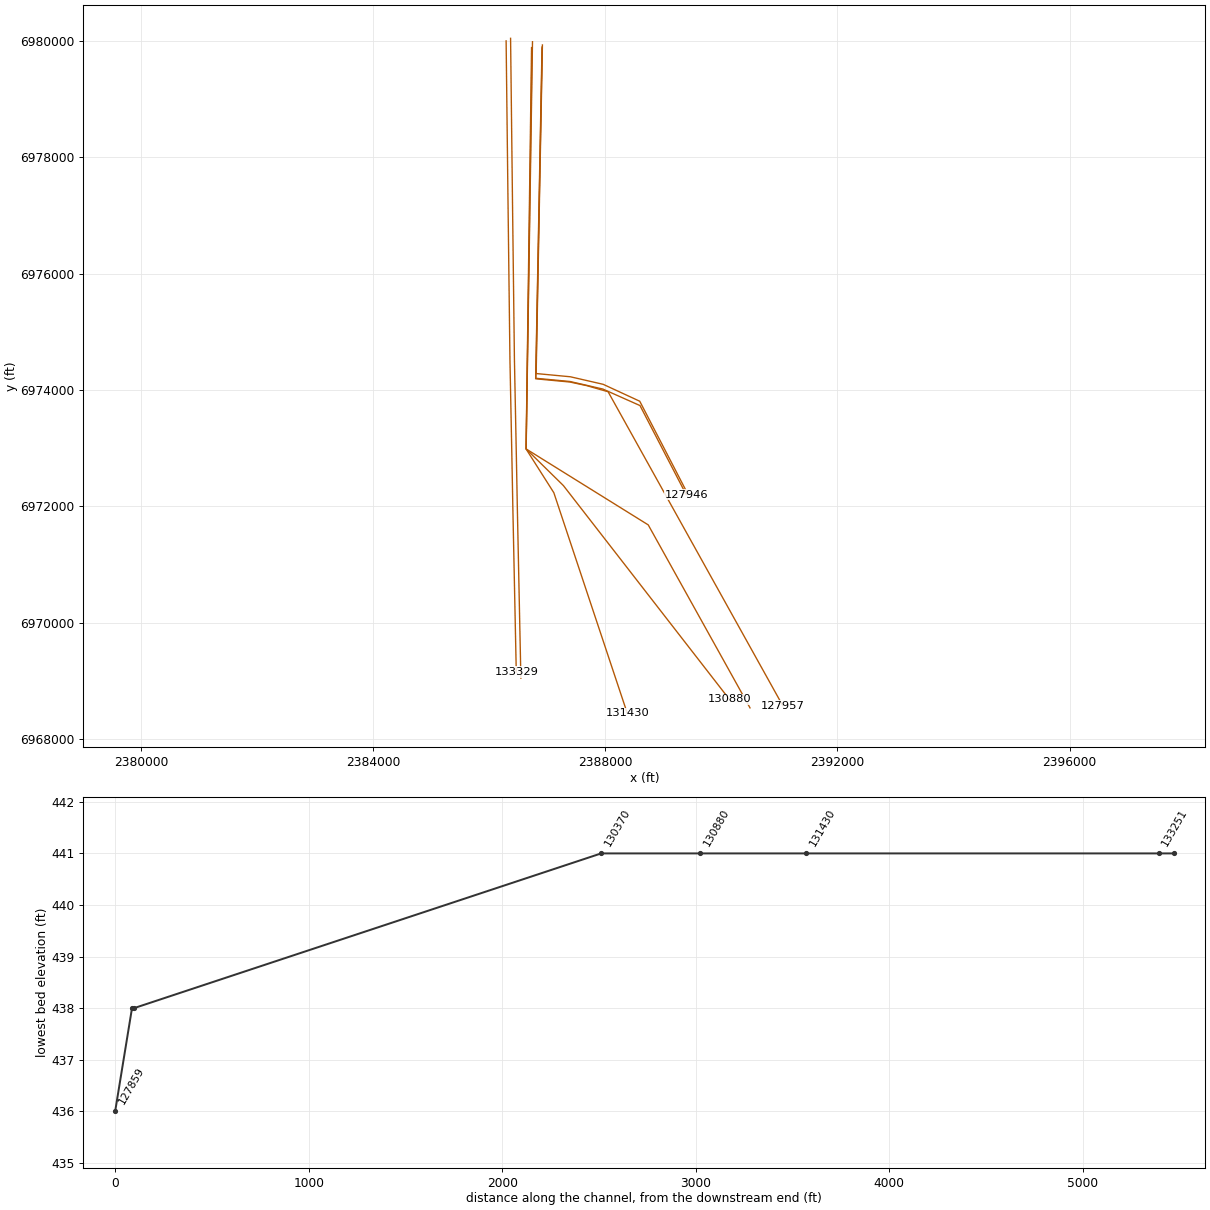
HEC-RAS study CDC_Consolidated_Model.prj: Upper Trinity CDC Consolidated Model

--- CDC_Consolidated_Model.g01 (geometry) --- (continued)

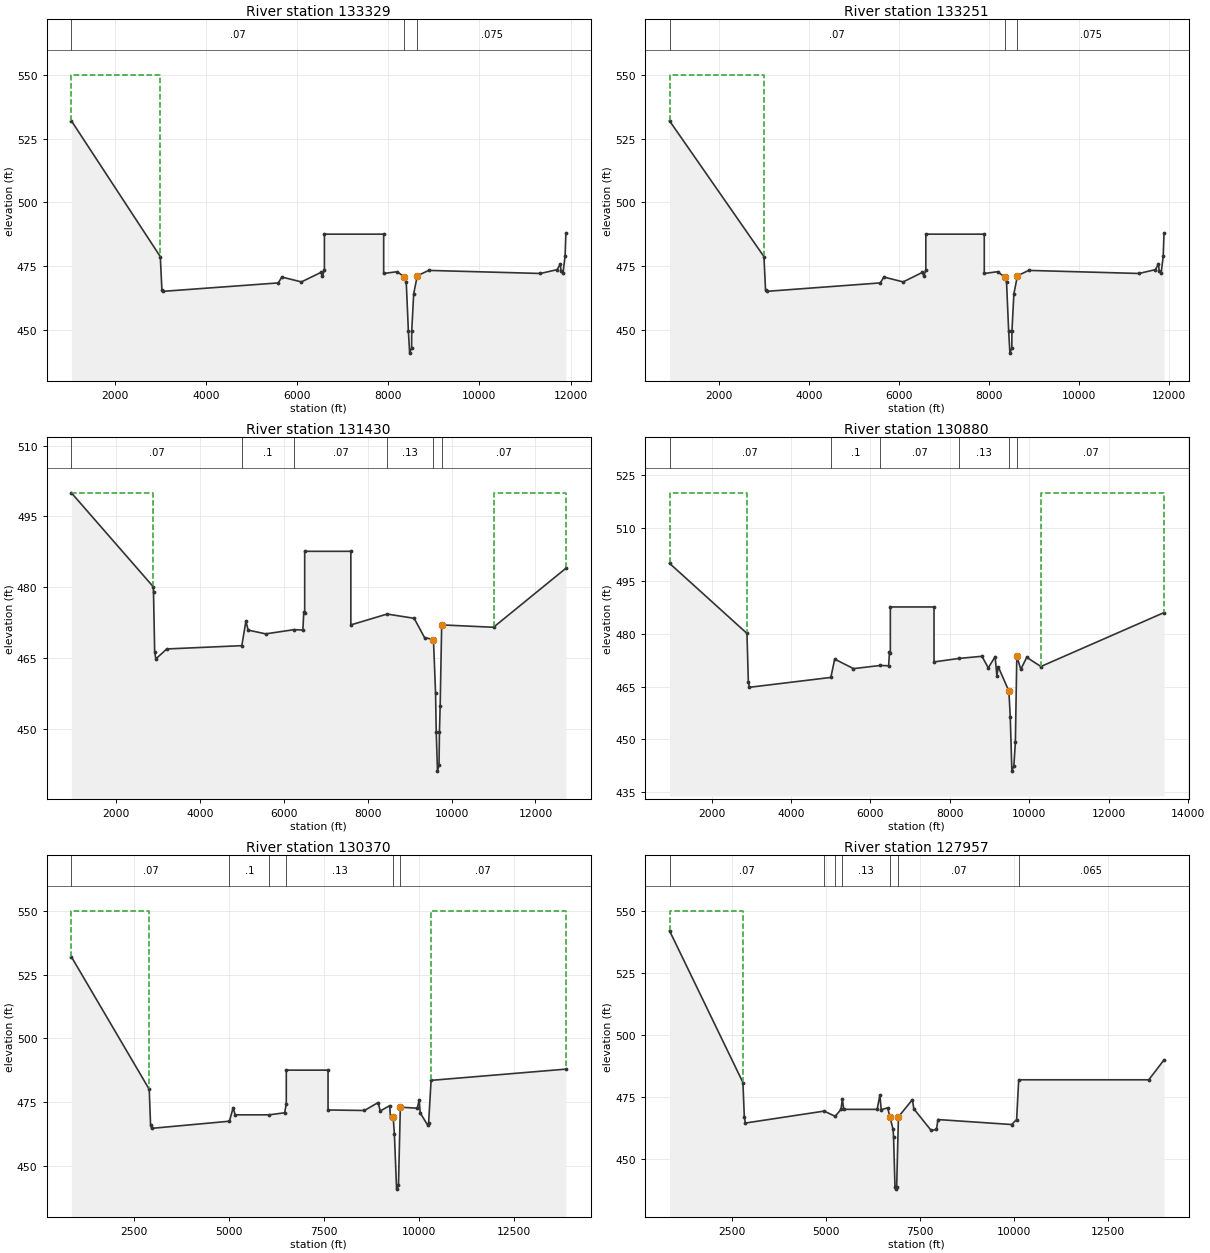
Type RM Length L Ch R = 1 ,133329  ,77,77,77
BEGIN DESCRIPTION:
This cross section corresponds to cross section 133369 of the non-georeferenced CDC model which was the source of this model.
END DESCRIPTION:
XS GIS Cut Line= 6
      2386290.73      6979999.41    2386320.8194    6977437.5493
      2386356.68      6974516.49    2386390.0285     6972849.742
    2386406.9144    6971962.66062386465.649630056969155.91562197
#Sta/Elev= 30
    1051     532    3001   478.8    3036   465.9    3060   465.2    5588   468.5
    5666   470.8    6096   468.9    6522   472.6    6557   471.1    6600   473.6
    6600   487.6    7900   487.6    7900   472.2    8199   472.9    8351   470.8
    8395   468.8    8442   449.6    8470     441    8512     443    8515   449.6
    8558   464.2    8637   471.3    8888   473.4   11338   472.2   11704   473.7
   11773   475.9   11790   473.2   11833   472.4   11879   479.1   11896     488
#Mann= 3 ,0,0
    1051     .07       0    8351    .055       0    8637    .075       0
#XS Ineff= 1 ,-1
    1051    3001     550
Permanent Ineff=
       F
Bank Sta=8351,8637
XS Rating Curve= 0 ,0
Exp/Cntr=0.3,0.1

Type RM Length L Ch R = 1 ,133251  ,250,1822,1239
BEGIN DESCRIPTION:
This cross section corresponds to cross section 133290 of the non-georeferenced CDC model which was the source of this model.
END DESCRIPTION:
XS GIS Cut Line= 6
2386367.572646156980043.26123349   2386400.03203   6977278.50091
   2386433.70387   6974534.15207   2386467.37703   6972850.50189
   2386484.21394   6971966.58601  2386545.141148 6969049.7918282
#Sta/Elev= 30
     901     532    3001   478.8    3036   465.9    3060   465.2    5588   468.5
    5666   470.8    6096   468.9    6522   472.6    6557   471.1    6600   473.6
    6600   487.6    7900   487.6    7900   472.2    8199   472.9    8351   470.8
    8395   468.8    8442   449.6    8470     441    8512     443    8515   449.6
    8558   464.2    8637   471.3    8888   473.4   11338   472.2   11704   473.7
   11773   475.9   11790   473.2   11833   472.4   11879   479.1   11896     488
#Mann= 3 ,0,0
     901     .07       0    8351    .055       0    8637    .075       0
#XS Ineff= 1 ,-1
     901    3001     550
Permanent Ineff=
       F
Bank Sta=8351,8637
XS Rating Curve= 0 ,0
Exp/Cntr=0.3,0.1

Type RM Length L Ch R = 1 ,131430  ,1,549,721
BEGIN DESCRIPTION:
This cross section corresponds to cross section 131467 of the non-georeferenced CDC model.
--------------------------------------------
CDC ARL021511-1 GREENMAN GAS WELL SITE
LOCATED ADJACENT TO VILLAGE CREEK STP IN INEFFECTIVE FLOW AREA.  SITE LOCATED BETWEEN
CROSS-SECTION 131467 AND 133290.
----------------------------------------
CDC ARL071405-1 SVC Park Highlands, LTD.
In ROB beyond eff. flow line - storage mitigation area d/s SH 360 d/s cross-sect 78083.
----------------------------------------
END DESCRIPTION:
XS GIS Cut Line= 6
2386728.967360536979883.18641281      2386702.21      6977933.37
   2386634.33897   6972987.58889   2387112.96203   6972235.61303
  2387832.762971 6970080.24911782388379.175582096968444.07728745
#Sta/Elev= 30
     940     500    2890   480.1    2897   478.9    2925   466.3    2953   464.8
    3213   466.9    5002   467.6    5099   472.8    5153   470.9    5571   470.1
    6252     471    6457   470.9    6478   474.7    6500   474.5    6500   487.6
    7600   487.6    7600     472    8464   474.3    9109   473.4    9357   469.3
    9569   468.9    9619   457.6    9635   449.4    9665     441    9702   442.4
    9712   449.4    9729   454.9    9765     472   11000   471.5   12725     484
#Mann= 6 ,-1,0
     940     .07       0    5002      .1       0    6252     .07       0
    8464     .13       0    9569     .05       0    9765     .07       0
#XS Ineff= 2 ,-1
   11000   12725     500     940    2890     500
Permanent Ineff=
       F       F
Bank Sta=9569,9765
XS Rating Curve= 0 ,0
Exp/Cntr=0.3,0.1

Type RM Length L Ch R = 1 ,130880  ,1,510,699
BEGIN DESCRIPTION:
This cross section corresponds to cross section 130918 of the non-georeferenced CDC model which was the source of this model.
END DESCRIPTION:
XS GIS Cut Line= 6
2386737.563770176979884.22088967  2386708.564787 6977934.4365275
      2386634.99      6972987.54   2387277.15396   6972359.02584
 2388232.0335648 6971133.00825722390136.877769836968687.28371127
#Sta/Elev= 30
     940     500    2890   480.1    2925   466.3    2953   464.8    5002   467.6
    5099   472.8    5571   470.1    6252     471    6457   470.9    6478   474.7
    6500   474.5    6500   487.6    7600   487.6    7600     472    8235     473
    8806   473.6    8966   470.3    9138   473.5    9182   468.1    9218   470.6
    9485   463.7    9519   456.4    9560     441    9610   442.5    9648   449.2
    9684   473.6    9785   469.9    9934   473.3   10290   470.7   13390     486
#Mann= 6 ,-1,0
     940     .07       0    5002      .1       0    6252     .07       0
    8235     .13       0    9485     .05       0    9684     .07       0
#XS Ineff= 2 ,-1
     940    2890     520   10290   13390     520
Permanent Ineff=
       F       F
Bank Sta=9485,9684
XS Rating Curve= 0 ,0
Exp/Cntr=0.3,0.1

Type RM Length L Ch R = 1 ,130370  ,170,2413,1045
BEGIN DESCRIPTION:
This cross section corresponds to cross section 130407 of the non-georeferenced CDC model which was the source of this model.
END DESCRIPTION:
XS GIS Cut Line= 6
 2386745.2528624 6979985.0510182  2386713.211418 6977935.3014369
      2386635.87      6972987.63    2388739.7511   6971682.79392
  2388739.781465 6971682.7421996      2390493.47      6968538.86
#Sta/Elev= 30
     840     532    2890   480.1    2925   466.3    2953   464.8    5002   467.6
    5099   472.8    5153   470.1    6047   470.1    6457   470.9    6500   474.5
    6500   487.6    7600   487.6    7600     472    8558   471.8    8918   474.9
    8975   471.6    9223   473.7    9245     469    9315   469.3    9347   462.7
    9405     441    9455   442.5    9504   473.1    9949   472.7   10000   475.8
   10029   470.8   10226     466   10249     467   10314   483.6   13864     488
#Mann= 6 ,-1,0
     840     .07       0    5002      .1       0    6047     .07       0
    6500     .13       0    9315    .055       0    9504     .07       0
#XS Ineff= 2 ,-1
     840    2890     550   10314   13864     550
Permanent Ineff=
       F       F
Bank Sta=9315,9504
XS Rating Curve= 0 ,0
Exp/Cntr=0.3,0.1

Type RM Length L Ch R = 1 ,127957  ,11,11,384
BEGIN DESCRIPTION:
This cross section corresponds to cross section 127999 of the non-georeferenced CDC model which was the source of this model.
END DESCRIPTION:
XS GIS Cut Line= 6
2386908.972737256979877.95741094   2386799.79894   6974193.06089
   2387388.91489   6974137.69387   2387682.10492   6974075.23107
      2388048.19      6973970.41 2391057.2090427 6968578.4097208
#Sta/Elev= 30
     852     542    2802   480.9    2839   466.9    2869   464.6    4958   469.4
    5252   467.3    5407   470.1    5441   474.2    5481   470.1    6367   470.1
    6440   475.9    6474     470    6647   470.7    6702   467.2    6790   462.1
    6803     459    6840     439    6860     438    6885     439    6932   467.1
    7302     474    7342   470.3    7802   461.6    7942     462    7982     466
    9940     464   10071     466   10126     482 13580.5     482   13985     490
#Mann= 7 ,-1,0
     852     .07       0    4958      .1       0    5252     .07       0
    5441     .13       0    6702    .055       0    6932     .07       0
   10126    .065       0
#XS Ineff= 1 ,-1
     852    2802     550
Permanent Ineff=
       F
Bank Sta=6702,6932
XS Rating Curve= 0 ,0
Exp/Cntr=0.3,0.1

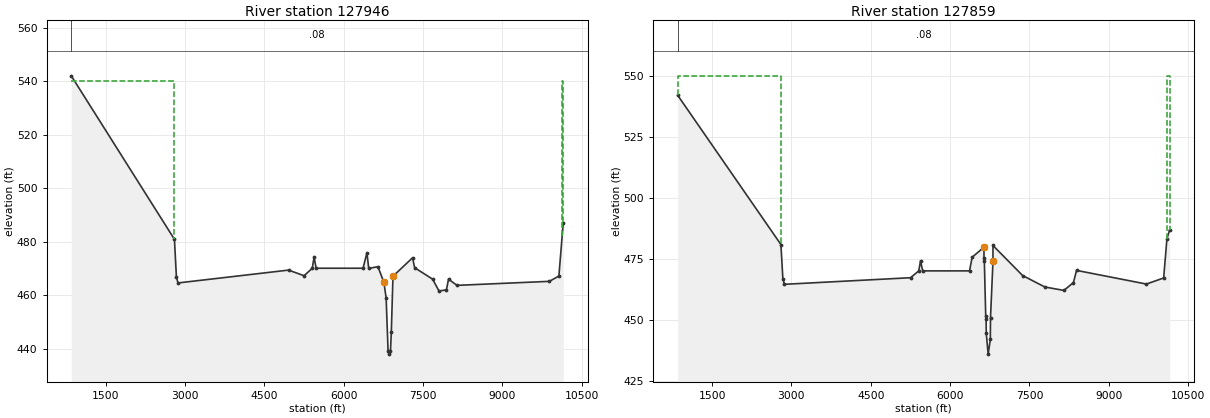
Type RM Length L Ch R = 1 ,127946  ,1,87,87
BEGIN DESCRIPTION:
This cross section corresponds to cross section 127989 of the non-georeferenced CDC model which was the source of this model.
END DESCRIPTION:
XS GIS Cut Line= 6
2386912.758688216979897.78156203 2386803.0685215  6974202.068684
 2387392.1844715  6974146.701664 2387957.8024315  6974016.957834
 2388597.7926215  6973733.117844 2389395.2365872  6972200.747429
#Sta/Elev= 30
     852     542    2802   480.9    2839   466.9    2869   464.6    4958   469.4
    5252   467.3    5407   470.1    5441   474.2    5481   470.1    6367   470.1
    6440   475.9    6474     470    6647   470.7    6760   464.9    6803     459
    6840     439    6860     438    6885     439    6901   446.3    6932   467.1
    7302     474    7342   470.3    7682     466    7802   461.6    7942     462
    7982     466    8142   463.7    9890   465.2   10068   467.2   10150     487
#Mann= 1 ,-1,0
     852     .08       0
#XS Ineff= 2 ,-1
     852    2802     540   10130   10150     540
Permanent Ineff=
       F       F
Bank Sta=6760,6932
XS Rating Curve= 0 ,0
Exp/Cntr=0.3,0.1

Type RM Length L Ch R = 1 ,127859  ,12,12,12
BEGIN DESCRIPTION:
This cross section corresponds to cross section 127889 of the non-georeferenced CDC model which was the source of this model.
END DESCRIPTION:
XS GIS Cut Line= 6
2386916.379855826979929.47035304 2386808.3232034 6974283.3612296
 2387397.4391512 6974227.9942144 2387963.0571144 6974098.2503794
      2388593.48      6973807.73 2389415.0239103 6972226.4769247
#Sta/Elev= 30
     852     542    2802   480.9    2839   466.9    2869   464.6    5252   467.3
    5407   470.1    5441   474.2    5481   470.1    6367   470.1    6417   475.7
    6640   479.8    6640   475.5    6647     474    6673   451.5    6680   450.5
  6683.5   444.5    6719     436    6760     442  6763.5     451    6810     474
    6810   480.5    7370   468.2    7790   463.5    8150   462.1    8330   465.3
    8390   470.3    9710   464.7   10036   467.2   10098   483.3   10150     487
#Mann= 1 ,-1,0
     852     .08       0
#XS Ineff= 2 ,-1
     852    2802     550   10098   10150     550
Permanent Ineff=
       F       F
Bank Sta=6640,6810
XS Rating Curve= 0 ,0
Exp/Cntr=0.3,0.1