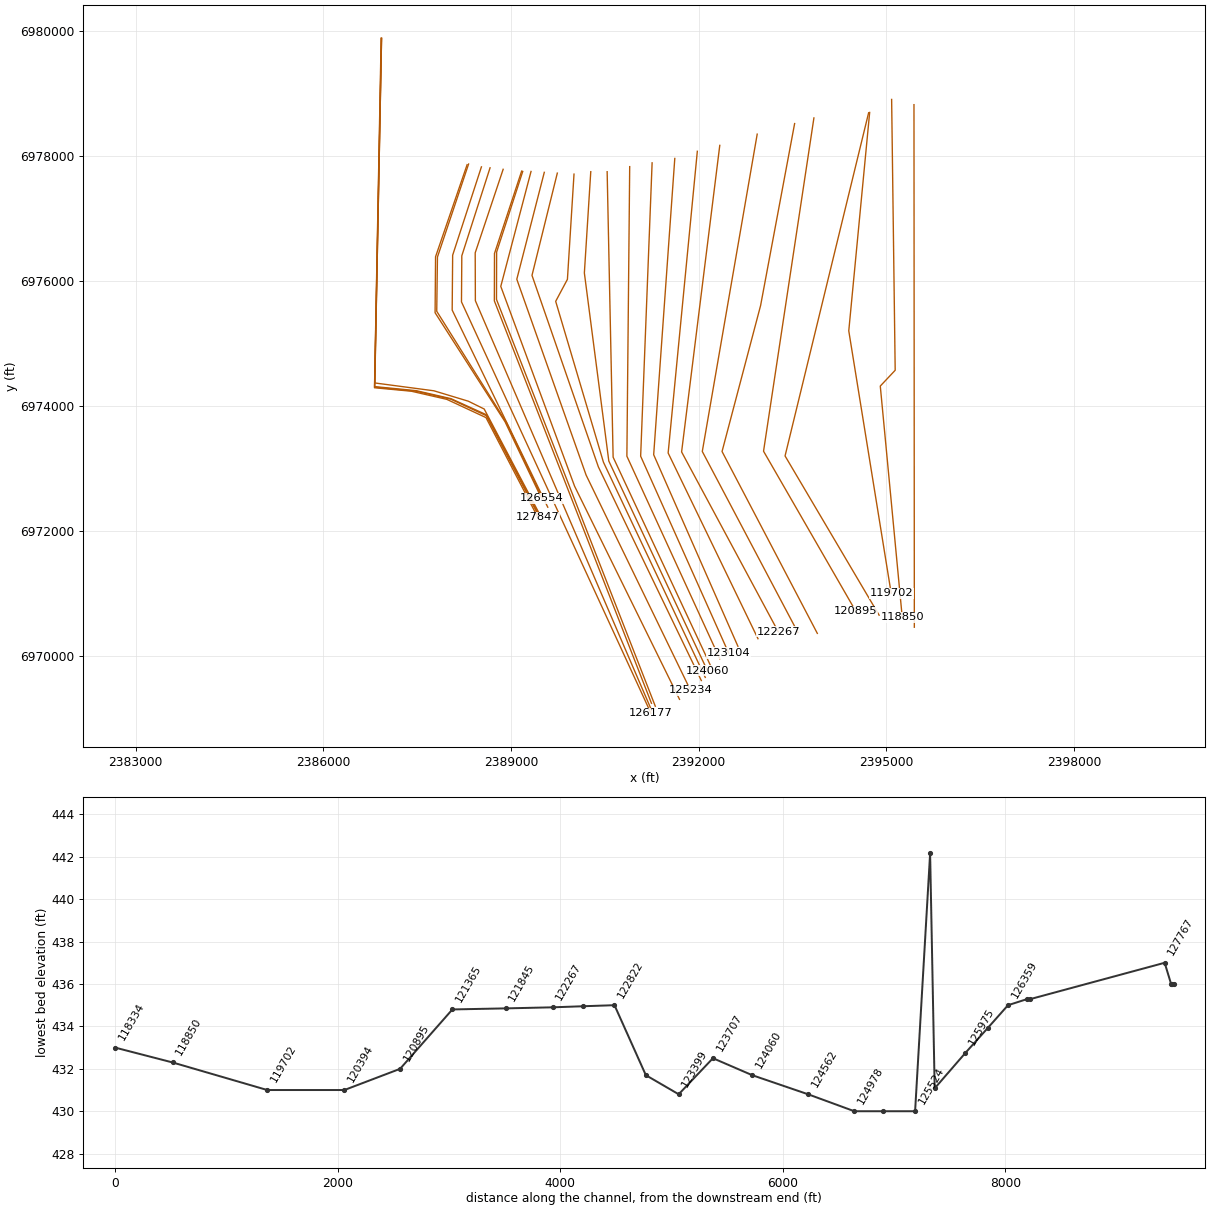
HEC-RAS study CDC_Consolidated_Model.prj: Upper Trinity CDC Consolidated Model

--- CDC_Consolidated_Model.g01 (geometry) --- (continued)

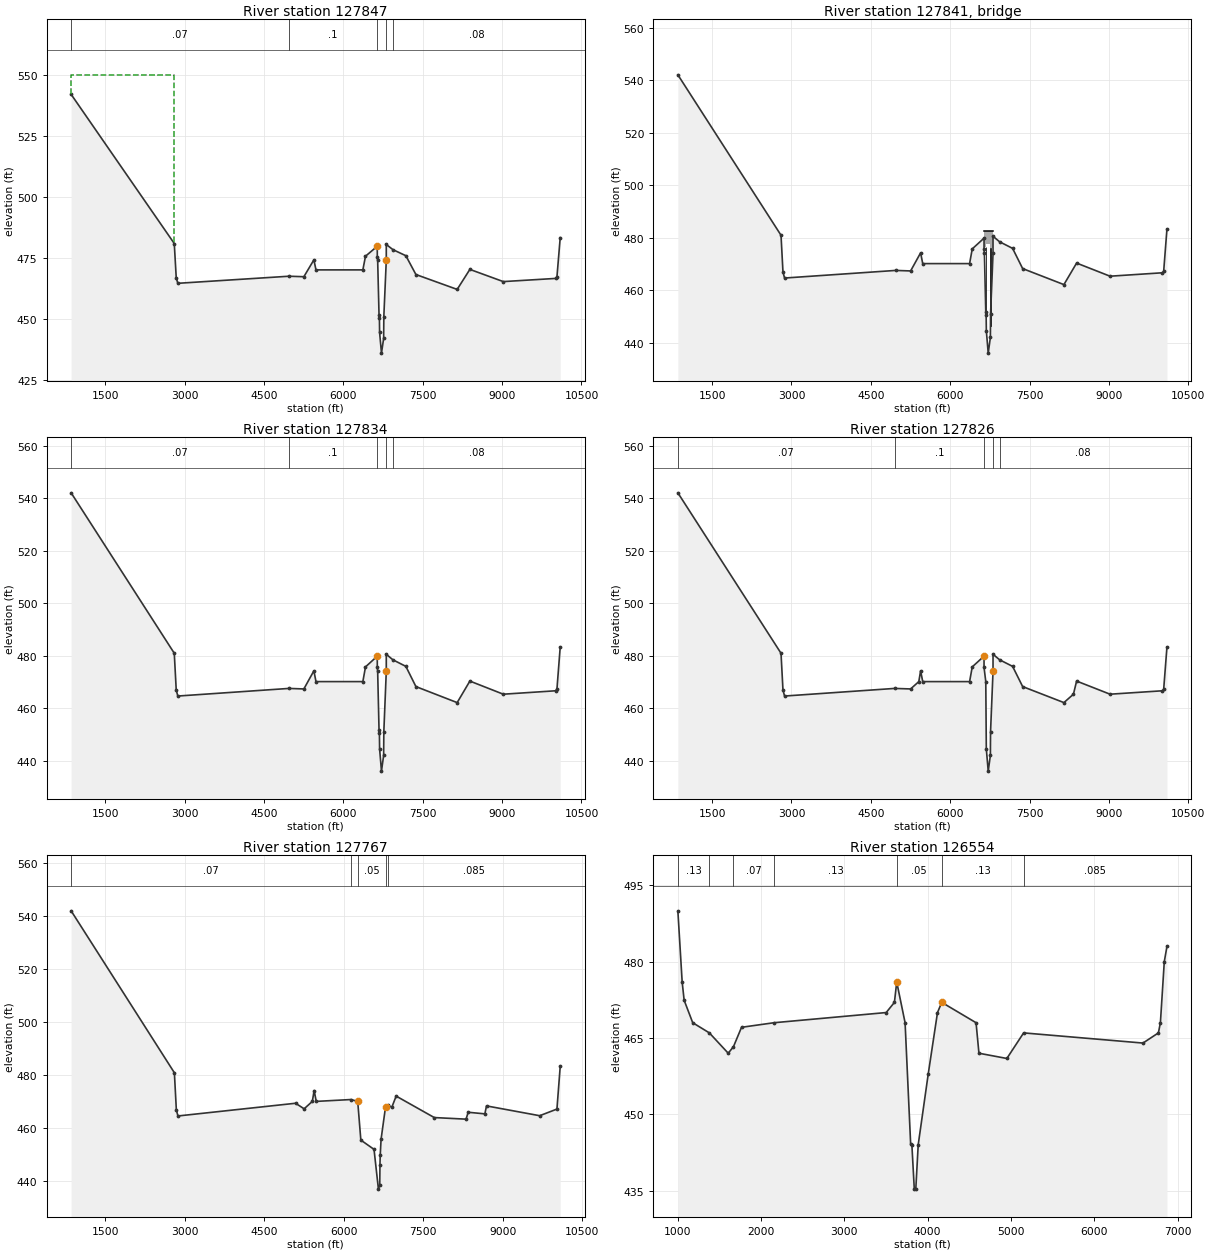
Type RM Length L Ch R = 1 ,127847  ,1,14,14
BEGIN DESCRIPTION:
This cross section corresponds to cross section 127888 of the non-georeferenced CDC model which was the source of this model.
END DESCRIPTION:
XS GIS Cut Line= 6
2386925.189568136979877.72399945 2386818.9094683 6974293.7191486
 2387408.0254161 6974238.3521333 2387973.6433793 6974108.6082983
      2388600.73      6973817.03   2389428.01232 6972224.8172006
#Sta/Elev= 30
     852     542    2802   480.9    2839   466.9    2869   464.6    4970   467.5
    5252   467.3    5441   474.2    5481   470.1    6367   470.1    6417   475.7
    6640   479.8    6640   475.5    6647     474    6673   451.5    6680   450.5
  6683.5   444.5    6719     436    6760     442  6763.5     451    6810     474
    6810   480.5    6935   478.4    7180   475.9    7370   468.2    8150   462.1
    8390   470.3    9022   465.3   10011   466.6   10036   467.2   10098   483.3
#Mann= 5 ,-1,0
     852     .07       0    4970      .1       0    6640    .055       0
    6810     .13       0    6935     .08       0
#XS Ineff= 1 ,-1
     852    2802     550
Permanent Ineff=
       F
Bank Sta=6640,6810
XS Rating Curve= 0 ,0
Exp/Cntr=0.3,0.1

Type RM Length L Ch R = 3 ,127841  ,,,
BEGIN DESCRIPTION:
Trammel-Davis Road
END DESCRIPTION:
Node Name=Trammel-Davis Ro
Bridge Culvert--1,0,-1,-1, 0
Deck Dist Width WeirC Skew NumUp NumDn MinLoCord MaxHiCord MaxSubmerge Is_Ogee
0.5,13,2.6,0, 8, 8, , , 0.95, 0, ,,,
    6640    6680  6683.5  6683.5    6760    6760  6763.5    6810
   482.7   482.7   482.7   482.7   482.7   482.7   482.7   482.7
   476.4   476.4   476.4   477.5   477.5   476.1   476.1   476.1
    6640    6680  6683.5  6683.5    6760    6760  6763.5    6810
   482.7   482.7   482.7   482.7   482.7   482.7   482.7   482.7
   476.4   476.4   476.4   477.5   477.5   476.1   476.1   476.1
Pier Skew, UpSta & Num, DnSta & Num=  ,6681.75, 2 ,6681.75, 2 , 0 , 0 , 0 ,,
     3.5     3.5
     440     480
     3.5     3.5
     440     480
Pier Skew, UpSta & Num, DnSta & Num=  ,6761.75, 2 ,6761.75, 2 , 0 , 0 , 0 ,,
     3.5     3.5
     440     480
     3.5     3.5
     440     480
BR Coef= 1 , 0 , 0 ,1.05, 0 ,,,0.8,-1,0.5,1,
WSPro=,,,, 1 ,,,, 0 ,,,, 0 ,,,,-1 ,-1 ,-1 , 0 , 0 , 0 , 0 , 0
BC Design=,, 0 ,, 0 ,,,,,,
BC HTab HWMax=483.3
BC Use User HTab Curves=0
BC User HTab FreeFlow(D)= 0

Type RM Length L Ch R = 1 ,127834  ,9,9,9
BEGIN DESCRIPTION:
This cross section corresponds to cross section 127873 of the non-georeferenced CDC model which was the source of this model.
END DESCRIPTION:
XS GIS Cut Line= 6
2386929.299360276979877.70600843      2386820.11      6974303.42
  2387483.115489 6974238.5142065 2388039.0025006 6974110.8425458
       2388605.3      6973847.92 2389442.3030819 6972248.2352131
#Sta/Elev= 30
     852     542    2802   480.9    2839   466.9    2869   464.6    4970   467.5
    5252   467.3    5441   474.2    5481   470.1    6367   470.1    6417   475.7
    6640   479.8    6640   475.5    6647     474    6673   451.5    6680   450.5
  6683.5   444.5    6719     436    6760     442  6763.5     451    6810     474
    6810   480.5    6935   478.4    7180   475.9    7370   468.2    8150   462.1
    8390   470.3    9022   465.3   10011   466.6   10036   467.2   10098   483.3
#Mann= 5 ,-1,0
     852     .07       0    4970      .1       0    6640    .055       0
    6810     .13       0    6935     .08       0
#XS Ineff= 2 , 0
            6640   470.8    6810           462.1
Permanent Ineff=
       F       F
Bank Sta=6640,6810
XS Rating Curve= 0 ,0
Exp/Cntr=0.3,0.1

Type RM Length L Ch R = 1 ,127826  ,1,58,58
BEGIN DESCRIPTION:
This cross section corresponds to cross section 127872 of the non-georeferenced CDC model which was the source of this model.
END DESCRIPTION:
XS GIS Cut Line= 6
2386932.10906372 6979877.4587316      2386822.04      6974312.16
 2387484.9901572 6974247.1218008 2388040.8771687 6974119.4501402
      2388609.57      6973861.05 2389452.4008471 6972253.4061766
#Sta/Elev= 30
     852     542    2802   480.9    2839   466.9    2869   464.6    4950   467.5
    5252   467.3    5407   470.1    5441   474.2    5481   470.1    6367   470.1
    6417   475.7    6640   479.8    6640   475.5    6673   470.1    6683   444.5
    6719     436    6760     442    6763     451    6810     474    6810   480.5
    6935   478.4    7180   475.9    7370   468.2    8150   462.1    8330   465.3
    8390   470.3    9022   465.3   10011   466.6   10036   467.2   10098   483.3
#Mann= 5 ,-1,0
     852     .07       0    4950      .1       0    6640     .05       0
    6810     .13       0    6935     .08       0
#XS Ineff= 2 , 0
       0    6640   470.8    6810       0   462.1
Permanent Ineff=
       F       F
Bank Sta=6640,6810
XS Rating Curve= 0 ,0
Exp/Cntr=0.3,0.1

Type RM Length L Ch R = 1 ,127767  ,1017,1213,31
BEGIN DESCRIPTION:
This cross section corresponds to cross section 127781 of the non-georeferenced CDC model which was the source of this model.
END DESCRIPTION:
XS GIS Cut Line= 6
2386931.618928986979877.45992418  2386824.310376 6974370.2773944
 2387769.0867018 6974245.0112407 2388318.2667058 6974078.9124916
 2388571.9568152 6973954.1630691 2389464.9938425 6972259.0895225
#Sta/Elev= 30
     852     542    2802   480.9    2839   466.9    2869   464.6    5091   469.4
    5252   467.3    5407   470.1    5441   474.2    5481   470.1    6135   470.8
    6264   470.1    6323   455.5    6572     452    6655     437    6680   438.5
    6684   446.1    6689   449.7    6705   455.8    6790   468.1    6838   468.6
    6908   467.9    6990   472.1    7710     464    8310   463.4    8350     466
    8665   465.4    8696   468.4    9700   464.7   10026   467.2   10088   483.3
#Mann= 5 ,-1,0
     852     .07       0    6135     .13       0    6264     .05       0
    6790     .13       0    6838    .085       0
#XS Ineff= 2 , 0
            6264   470.1    6790           468.1
Permanent Ineff=
       F       F
Bank Sta=6264,6790
XS Rating Curve= 0 ,0
Exp/Cntr=0.3,0.1

Type RM Length L Ch R = 1 ,126554  ,28,28,28
BEGIN DESCRIPTION:
This cross section corresponds to cross section 126600 of the non-georeferenced CDC model which was the source of this model.
END DESCRIPTION:
XS GIS Cut Line= 6
  2388299.036303 6977858.0265513  2388294.313669 6977844.2533861
 2387794.7766111 6976387.3957355 2387787.2940145 6975492.7790864
 2388906.0437455 6973749.0292931      2389487.45      6972528.08
#Sta/Elev= 30
    1000     490 1051.69     476 1075.57  472.41 1178.35     468 1378.09     466
 1604.92     462 1667.97   463.3 1764.61   467.1 2155.82     468 3501.74     470
  3600.6     472 3628.33     476 3728.64     468 3795.53  444.11 3810.14     444
  3839.2  435.28  3857.2  435.28 3886.29     444 4007.36     458 4117.83     470
 4169.13     472 4580.92     468 4615.57     462 4950.74  460.97 5152.15     466
 6585.31     464 6770.58     466 6794.69     468  6841.3     480 6873.42     483
#Mann= 7 ,-1,0
    1000     .13       0 1378.09     .04       0 1667.97     .07       0
 2155.82     .13       0 3628.33     .05       0 4169.13     .13       0
 5152.15    .085       0
Bank Sta=3628.33,4169.13
XS Rating Curve= 0 ,0
Exp/Cntr=0.3,0.1

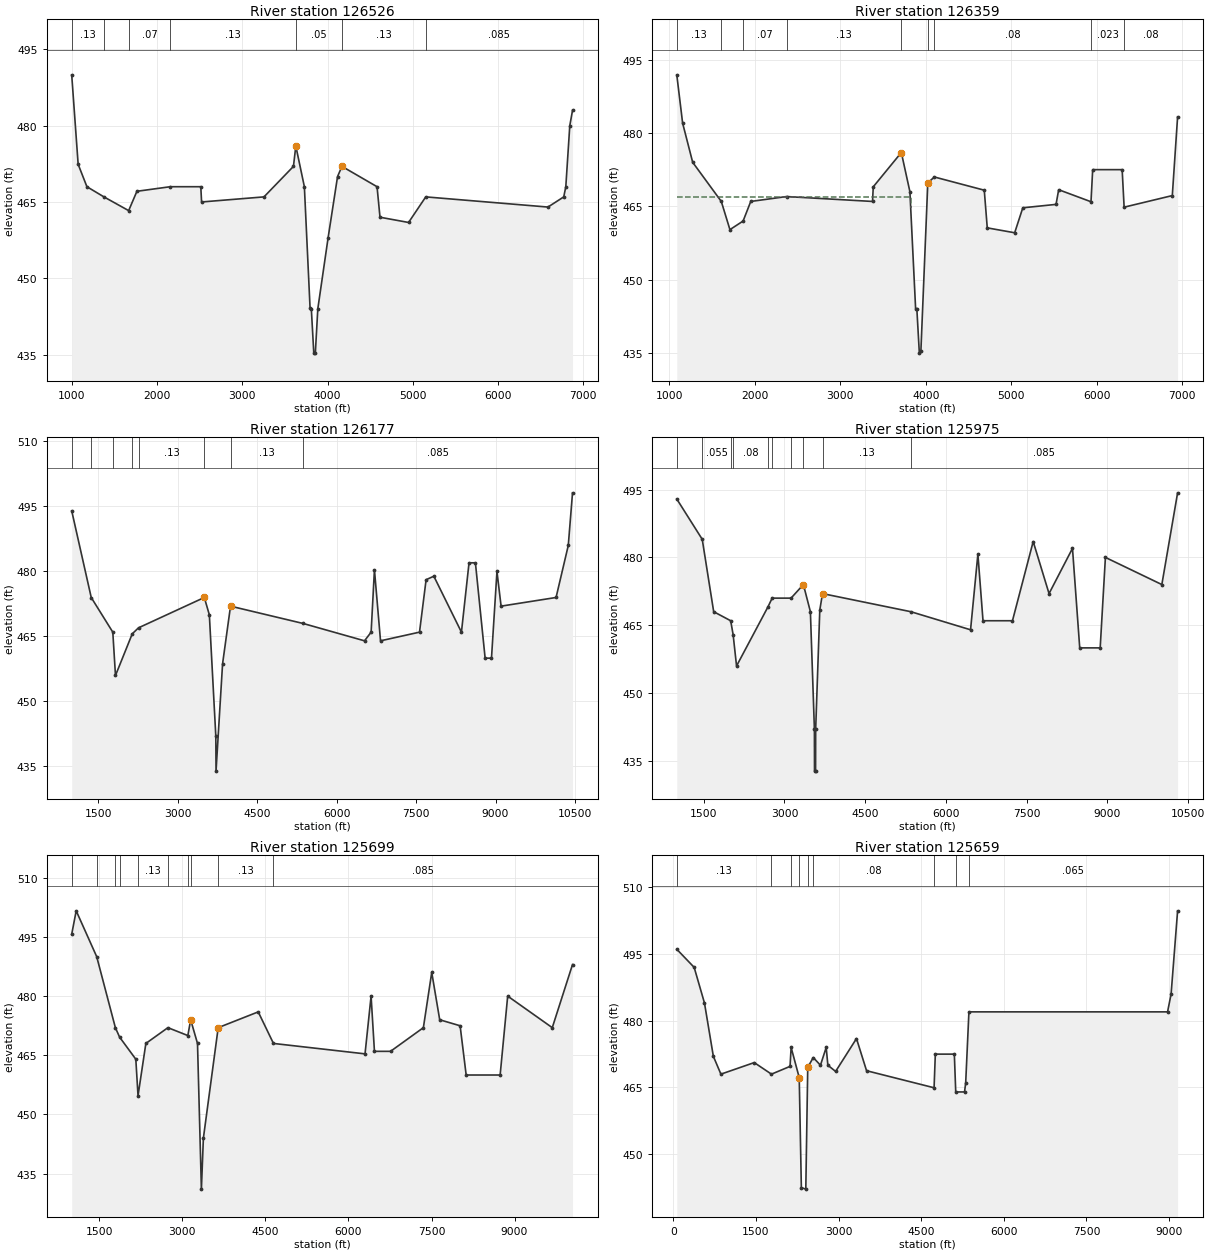
Type RM Length L Ch R = 1 ,126526  ,167,167,167
BEGIN DESCRIPTION:
This cross section corresponds to cross section 126590 of the non-georeferenced CDC model which was the source of this model.
END DESCRIPTION:
XS GIS Cut Line= 6
  2388322.501575 6977868.8919064  2388312.181088 6977838.0683591
  2387824.984884 6976382.9902325 2387813.5528202 6975516.0424913
 2388931.2175797 6973731.4945512      2389503.27      6972526.64
#Sta/Elev= 30
    1000     490 1075.57  472.41 1178.35     468 1378.09     466 1667.97   463.3
 1764.61   467.1 2155.82     468    2514     468    2523     465    3255     466
  3600.6     472 3628.33     476 3728.64     468 3795.53  444.11 3810.14     444
  3839.2  435.28  3857.2  435.28 3886.29     444 4007.36     458 4117.83     470
 4169.13     472 4580.92     468 4615.57     462 4950.74  460.97 5152.15     466
 6585.31     464 6770.58     466 6794.69     468  6841.3     480 6873.42     483
#Mann= 7 ,-1,0
    1000     .13       0 1378.09     .04       0 1667.97     .07       0
 2155.82     .13       0 3628.33     .05       0 4169.13     .13       0
 5152.15    .085       0
Bank Sta=3628.33,4169.13
XS Rating Curve= 0 ,0
Exp/Cntr=0.3,0.1

Type RM Length L Ch R = 1 ,126359  ,181,181,181
BEGIN DESCRIPTION:
This cross section corresponds to cross section 126400 of the non-georeferenced CDC model which was the source of this model.
Contains proposed pad site by BHB July 2011
END DESCRIPTION:
XS GIS Cut Line= 4
     2388527.595     6977823.304     2388068.022     6976412.168
     2388060.395     6975534.975 2389588.1119266 6972385.0073918
#Sta/Elev= 30
  1085.8  491.88 1154.19     482 1271.87     474 1606.85     466 1707.85  460.24
 1862.07     462  1951.6     466  2370.8     467  3376.8     466  3385.8     469
 3714.13     476 3814.44     468 3881.33  444.11 3895.94     444    3925     435
    3943   435.4    4024   469.8    4101     471    4685   468.3    4720   460.6
    5041   459.6    5136   464.7    5525   465.4    5556   468.4 5934.31  465.94
 5953.99   472.5 6298.99   472.5    6322  464.83    6886   467.2    6948   483.3
#Mann= 9 ,-1,0
  1085.8     .13       0 1606.85     .04       0 1862.07     .07       0
  2370.8     .13       0 3714.13     .05       0    4024     .13       0
    4101     .08       0 5934.31    .023       0    6322     .08       0
#XS Ineff= 2 , 0
            3824   466.9    4024           469.8
Permanent Ineff=
       F       F
Bank Sta=3714.13,4024
XS Rating Curve= 0 ,0
Exp/Cntr=0.3,0.1

Type RM Length L Ch R = 1 ,126177  ,202,202,202
BEGIN DESCRIPTION:
This cross section corresponds to cross section 126217 of the non-georeferenced CDC model which was the source of this model.
END DESCRIPTION:
XS GIS Cut Line= 5
  2388665.624278 6977808.5402029 2388214.2354178 6976402.2900627
 2388209.0270949 6975666.1790021 2389854.8604174 6972092.9151512
 2391237.9856779 6969090.0159956
#Sta/Elev= 30
    1000     494  1368.7  473.99 1775.74     466 1826.27     456 2142.74  465.61
    2261     467    3503     474    3598     470 3720.07     442 3724.24  433.93
 3847.75   458.7 3997.76     472 5368.98     468 6526.97     464 6651.85     466
 6714.22   480.4    6829     464 7564.98     466 7689.44   478.1 7835.41  478.91
 8356.56     466 8499.93     482 8620.16     482 8803.73     460 8923.64     460
 9026.94     480 9105.03     47210142.62     47410373.07     48610453.25  498.15
#Mann= 8 ,-1,0
    1000     .08       0  1368.7    .055       0 1775.74     .04       0
 2142.74     .08       0    2261     .13       0    3503     .05       0
 3997.76     .13       0 5368.98    .085       0
Bank Sta=3503,3997.76
XS Rating Curve= 0 ,0
Exp/Cntr=0.3,0.1

Type RM Length L Ch R = 1 ,125975  ,276,276,276
BEGIN DESCRIPTION:
This cross section corresponds to cross section 126020 of the non-georeferenced CDC model which was the source of this model.
END DESCRIPTION:
XS GIS Cut Line= 5
  2388874.970316 6977784.8132162 2388428.3557245 6976450.1777622
   2388430.96005 6975684.5529811 2390177.4877249 6971625.0909556
 2391249.2213574 6969134.0557175
#Sta/Elev= 30
    1000  492.91 1472.77     484 1685.46     468 2001.02     466 2046.58  462.94
 2110.24     456    2691     469    2772     471    3123     471    3352     474
 3482.03     468 3556.67     442 3558.44  432.75 3578.44  432.75  3580.2     442
  3656.7  468.36 3707.28     472 5347.81     468 6457.58     464 6593.87  480.72
 6688.92     466  7236.3     466 7621.13  483.51 7915.76     472 8351.17     482
 8485.75     460 8865.87     460 8962.86     480 10011.3     47410304.04  494.28
#Mann= 10 ,-1,0
    1000     .08       0 1472.77    .055       0 2001.02     .04       0
 2046.58     .08       0    2691     .13       0    2772     .06       0
    3123     .13       0    3352     .05       0 3707.28     .13       0
 5347.81    .085       0
Bank Sta=3352,3707.28
XS Rating Curve= 0 ,0
Exp/Cntr=0.3,0.1

Type RM Length L Ch R = 1 ,125699  ,41,41,41
BEGIN DESCRIPTION:
This cross section corresponds to cross section 125742 of the non-georeferenced CDC model which was the source of this model.
---------------------------------------------------------------------
CDC FW041812-01 XTO-BASS ARLINGTON PAD SITE
CROSS-SECTION 125742 - 126600
LOCATED IN LOB.
---------------------------------------------------------------------
END DESCRIPTION:
XS GIS Cut Line= 5
  2389170.543216 6977755.9504131 2388736.5155413 6976439.7611163
   2388734.34527 6975682.3827098 2390466.1160847 6971246.6189436
 2391245.1213645 6969251.2721202
#Sta/Elev= 30
    1000  495.67 1081.02  501.61 1451.33     490 1788.79     472 1865.14   469.6
 2158.22     464 2198.04  454.75 2339.61     468    2738     472    3098     470
    3149     474 3272.48     468 3342.83  431.08 3378.71     444 3646.36     472
 4369.45     476 4644.66     468 6298.87  465.36 6408.27     480 6468.96     466
 6759.63     466 7352.94     472 7503.87     486 7647.94     474 8016.48  472.48
 8125.92     460 8739.59     460 8875.92     480 9681.33     47210047.14     488
#Mann= 10 ,-1,0
    1000     .08       0 1451.33    .055       0 1788.79     .04       0
 1865.14     .08       0 2198.04     .13       0    2738     .06       0
    3098     .13       0    3149     .05       0 3646.36     .13       0
 4644.66    .085       0
Bank Sta=3149,3646.36
XS Rating Curve= 0 ,0
Exp/Cntr=0.3,0.1

Type RM Length L Ch R = 1 ,125659  ,218,135,58
BEGIN DESCRIPTION:
This cross section corresponds to cross section 125701 of the non-georeferenced CDC model which was the source of this model.
---------------------------------------------------------------------
CDC FW022811-01 QUICKSILVER EAST AND WEST VILLAGE CREEK PAD SITES
CROSS-SECTION 125701 - 133770
DOWNSTREAM END
---------------------------------------------------------------------
Contains proposed pad site by BHB July 2011
END DESCRIPTION:
XS GIS Cut Line= 6
       2389187.7      6977750.24 2388770.6871038 6976462.3259077
 2388768.5168325 6975704.9475012 2390500.2876472  6971269.183735
 2391295.0475516 6969233.4829617 2391306.4841294 6969204.1892718
#Sta/Elev= 30
   63.22  496.07  378.73     492   565.6     484  727.09     472  864.14     468
  1469.5   470.6 1781.81     468 2119.09469.7464 2138.73 474.001 2285.66467.2199
 2324.26442.4988 2405.04442.1572 2440.27469.5142 2540.09471.7369 2670.93     470
 2775.19     474 2805.71     470 2946.22  468.61  3324.9     476 3507.86  468.77
  4733.4  464.94 4756.08   472.5 5101.08   472.5 5126.58     464    5286     464
    5307     466    5366     482 8971.49     482 9035.63     486 9153.68  504.71
#Mann= 9 ,-1,0
   63.22     .13       0 1781.81     .07       0 2138.73     .13       0
 2285.66     .05       0 2440.27     .13       0 2540.09     .08       0
  4733.4    .023       0 5126.58     .08       0    5366    .065       0
Bank Sta=2285.66,2440.27
XS Rating Curve= 0 ,0
Exp/Cntr=0.3,0.1

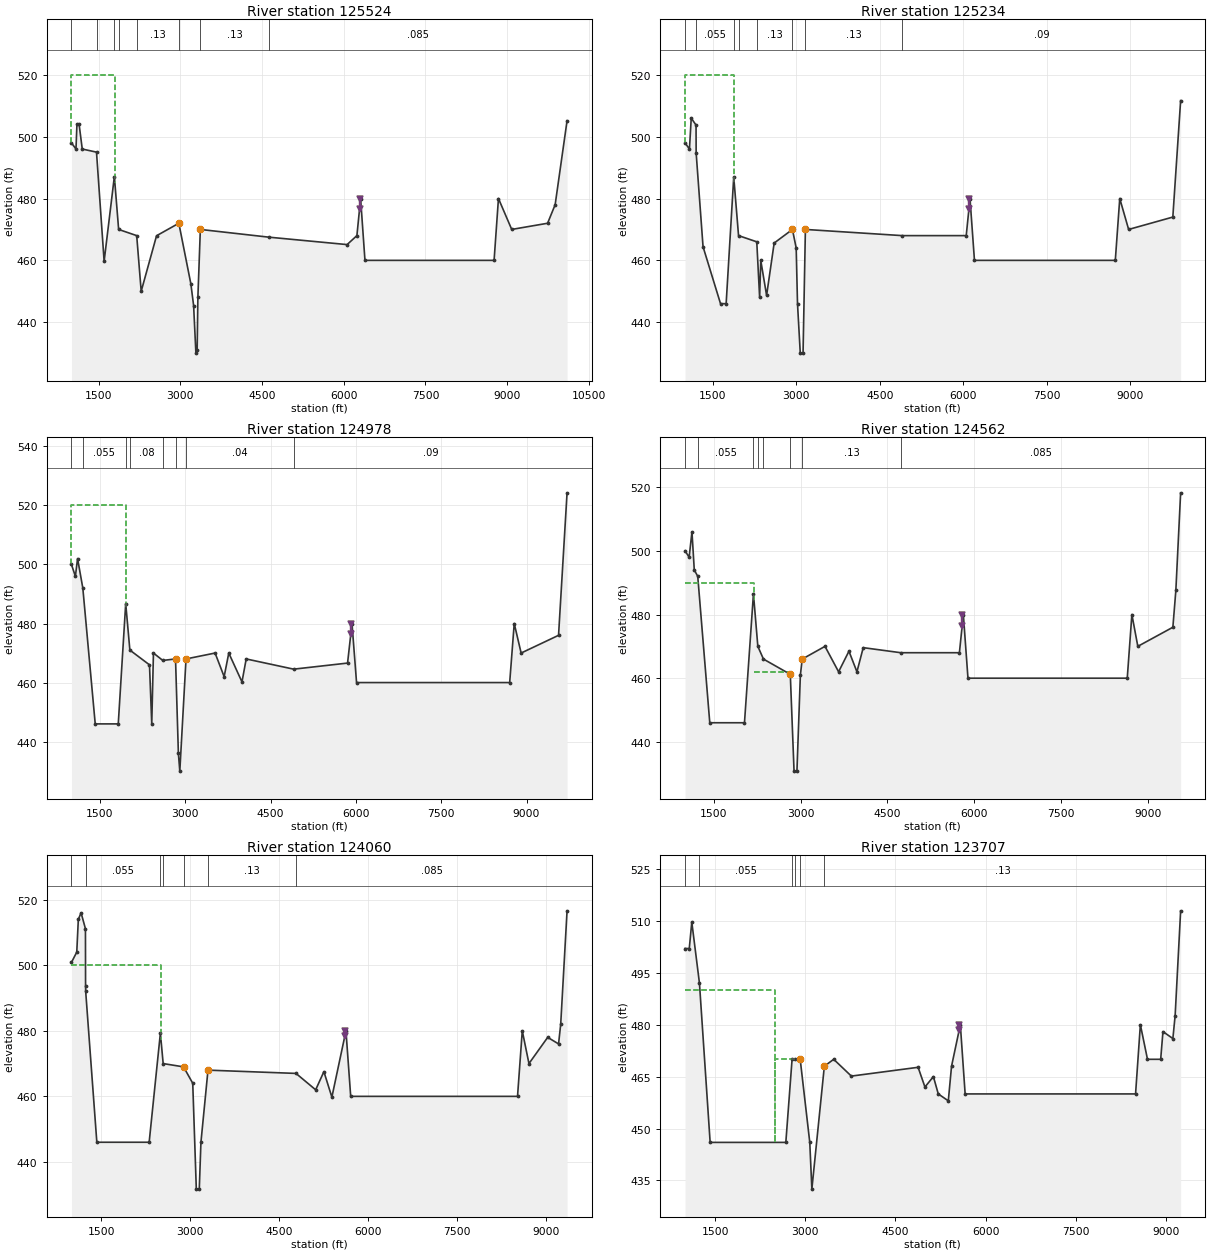
Type RM Length L Ch R = 1 ,125524  ,229,290,259
BEGIN DESCRIPTION:
This cross section corresponds to cross section 125562 of the non-georeferenced CDC model which was the source of this model.
---------------------------------------------------------------------
CDC ARL021910-1 ARLINGTON LANDFILL
CROSS-SECTION 116053-125562
UPSTREAM END
---------------------------------------------------------------------
END DESCRIPTION:
XS GIS Cut Line= 4
   2389320.42513   6977750.35397   2388837.06685   6975913.59485
   2390016.65209   6972720.08614   2391693.30097    6969314.4381
#Sta/Elev= 30
    1000     498 1083.35     496 1100.88     504 1140.48     504 1198.36     496
    1460     495    1600   459.7    1788  487.11  1866.4     470 2198.02     468
 2280.55     450 2562.57  467.96 2971.77     472 3192.28  452.43    3243   445.4
    3285     430    3308     431 3321.39     448 3366.58     470    4624   467.5
    6061   465.1    6241     468    6309     480    6389     460    8760     460
    8840     480 9083.57     470 9742.17     472 9881.03     47810099.69  505.15
#Mann= 8 ,-1,0
    1000     .08       0    1460    .055       0    1788     .04       0
  1866.4     .08       0 2198.02     .13       0 2971.77     .05       0
 3366.58     .13       0    4624    .085       0
Levee=0,,,-1,6289,480,,Levee 1
#XS Ineff= 3 ,-1
    1000    1798     520    1798 2971.77     472 3366.58   10000     470
Permanent Ineff=
       T       F       F
Bank Sta=2971.77,3366.58
XS Rating Curve= 0 ,0
Exp/Cntr=0.3,0.1

Type RM Length L Ch R = 1 ,125234  ,210,256,240
BEGIN DESCRIPTION:
This cross section corresponds to cross section 125286 of the non-georeferenced CDC model which was the source of this model.
END DESCRIPTION:
XS GIS Cut Line= 5
  2389532.435209 6977736.3198749  2389093.198883 6976027.9866774
 2390200.8377438 6972897.7780428 2391837.9906375 6969522.7782311
 2391868.7784544 6969459.3089751
#Sta/Elev= 30
    1000     498 1079.56     496 1111.79     506 1198.18  503.74    1200  494.75
    1324   464.4    1638     446    1739     446  1875.5  486.96 1961.84     468
 2289.23     466 2340.82     448 2360.83     460 2465.96  448.67 2601.92   465.6
 2930.17     470 2997.66     464 3021.26     446    3071     430    3121     430
 3163.15     470    4905     468    6053     468    6121     480    6201     460
    8732     460    8812     480 8971.53     470 9765.72     474 9905.96  511.66
#Mann= 8 ,-1,0
    1000     .08       0    1200    .055       0  1875.5     .04       0
 1961.84     .08       0 2289.23     .13       0 2930.17     .05       0
 3163.15     .13       0    4905     .09       0
Levee=0,,,-1,6101,480,,Levee 1
#XS Ineff= 3 ,-1
    1000  1885.5     520  1885.5 2930.17     470 3163.15 9905.96     470
Permanent Ineff=
       T       F       F
Bank Sta=2930.17,3163.15
XS Rating Curve= 0 ,0
Exp/Cntr=0.3,0.1

Type RM Length L Ch R = 1 ,124978  ,311,416,173
BEGIN DESCRIPTION:
This cross section corresponds to cross section 125016 of the non-georeferenced CDC model which was the source of this model.
END DESCRIPTION:
XS GIS Cut Line= 4
   2389740.61786   6977723.96393   2389335.93396   6976089.66602
   2390396.79011   6973028.61111   2392041.61687   6969614.79084
#Sta/Elev= 30
    1000     500  1069.3     496 1107.65     502    1200     492    1418     446
    1823     446    1954  486.75    2027     471 2371.99     466 2411.78     446
 2441.59     470 2605.96  467.49 2829.58     468    2880     436    2905     430
 3014.16     468 3525.19     470 3684.32     462 3765.78     470  3997.8  460.22
 4072.17     468 4906.75  464.54    5854   466.6    5932     480    6012     460
    8704     460    8784     480 8905.23     470 9563.03     476 9712.74  524.27
#Mann= 8 ,-1,0
    1000     .08       0    1200    .055       0    1954     .04       0
    2027     .08       0 2605.96     .13       0 2829.58     .05       0
 3014.16     .04       0 4906.75     .09       0
Levee=0,,,-1,5912,480,,Levee 1
#XS Ineff= 3 ,-1
    1000    1964     520    1964 2829.58     468 3014.16 9712.74     468
Permanent Ineff=
       T       F       F
Bank Sta=2829.58,3014.16
XS Rating Curve= 0 ,0
Exp/Cntr=0.3,0.1

Type RM Length L Ch R = 1 ,124562  ,362,502,201
BEGIN DESCRIPTION:
This cross section corresponds to cross section 124600 of the non-georeferenced CDC model which was the source of this model.
END DESCRIPTION:
XS GIS Cut Line= 6
  2390007.276951 6977707.8241858   2390003.57239 6977648.6461657
 2389902.0099294 6976026.2504604 2389714.5096482 6975674.6878433
   2390477.53076 6973104.3753987 2392104.4494757 6969665.3599211
#Sta/Elev= 30
    1000  500.02  1071.3     498 1120.11     506 1160.02     494    1220     492
    1428     446    2028     446    2183  486.48  2258.9     470 2356.09     466
 2820.15  461.21    2885   430.8    2935   430.8 2994.24  460.96  3026.5     466
 3420.17     470 3655.25     462 3834.14  468.48 3972.35     462 4081.23  469.59
 4730.99     468    5744     468    5812     480    5892     460    8646     460
    8726     480 8828.71     470 9434.72     476 9486.23  487.57 9568.91  518.23
#Mann= 8 ,-1,0
    1000     .08       0    1220    .055       0    2183     .04       0
  2258.9     .08       0 2356.09     .13       0 2820.15     .05       0
  3026.5     .13       0 4730.99    .085       0
Levee=0,,,-1,5792,480,,Levee 1
#XS Ineff= 3 ,-1
    1000    2193     490    2193 2820.15     462  3026.5 9568.91     466
Permanent Ineff=
       T       F       F
Bank Sta=2820.15,3026.5
XS Rating Curve= 0 ,0
Exp/Cntr=0.3,0.1

Type RM Length L Ch R = 1 ,124060  ,401,353,223
BEGIN DESCRIPTION:
This cross section corresponds to cross section 124110 of the non-georeferenced CDC model which was the source of this model.
END DESCRIPTION:
XS GIS Cut Line= 5
  2390275.190328 6977746.9998931   2390274.40551 6977734.5836579
 2390172.8430492 6976127.8129213 2390563.4682522 6973122.6046929
 2392138.9890513 6969773.6461677
#Sta/Elev= 30
    1000  500.86  1089.7     504 1115.98  513.99  1162.2     516 1235.94  511.14
    1238  493.61    1240     492    1428     446    2310     446    2499  479.28
  2546.1     470 2889.38     469 3044.48     464  3104.7   431.7  3154.7   431.7
 3182.63     446 3301.52     468    4785     467 5116.51     462 5255.23  467.54
 5389.68  459.76    5627     480    5707     460    8519     460    8599     480
 8711.62     470 9027.49     478  9210.5     476 9246.82     482 9353.96   516.6
#Mann= 7 ,-1,0
    1000     .08       0    1240    .055       0    2499     .04       0
  2546.1     .13       0 2889.38     .05       0 3301.52     .13       0
    4785    .085       0
Levee=0,,,-1,5607,480,,Levee 1
#XS Ineff= 3 ,-1
    1000    2509     500    2509 2889.38     469 3301.52 9353.96     468
Permanent Ineff=
       T       F       F
Bank Sta=2889.38,3301.52
XS Rating Curve= 0 ,0
Exp/Cntr=0.3,0.1

Type RM Length L Ch R = 1 ,123707  ,311,308,243
BEGIN DESCRIPTION:
This cross section corresponds to cross section 123744 of the non-georeferenced CDC model which was the source of this model.
END DESCRIPTION:
XS GIS Cut Line= 4
  2390536.929823 6977746.1725683   2390536.92992   6977746.16795
   2390632.39889   6973184.36704   2392191.04111   6969848.53184
#Sta/Elev= 30
    1000     502 1070.69     502 1112.73  509.64    1240     492    1418     446
    2677     446    2781     470    2831     470    2916     470 3075.36     446
    3110   432.5 3317.83     468 3473.31     470    3767  465.15 4877.43  467.69
 4991.06     462 5131.87     465 5212.93     460 5379.95     458 5433.71     468
    5580     480    5660     460    8495     460    8575     480 8693.39     470
 8912.84     470 8950.77     478 9115.76     476 9153.48  482.64 9244.81  512.89
#Mann= 6 ,-1,0
    1000     .09       0    1240    .055       0    2781     .04       0
    2831     .09       0    2916     .05       0 3317.83     .13       0
Levee=0,,,-1,5560,480,,Levee 1
#XS Ineff= 3 ,-1
    1000    2493     490    2493 2915.61     470 3317.83 9244.81     468
Permanent Ineff=
       T       F       F
Bank Sta=2916,3317.83
XS Rating Curve= 0 ,0
Exp/Cntr=0.3,0.1

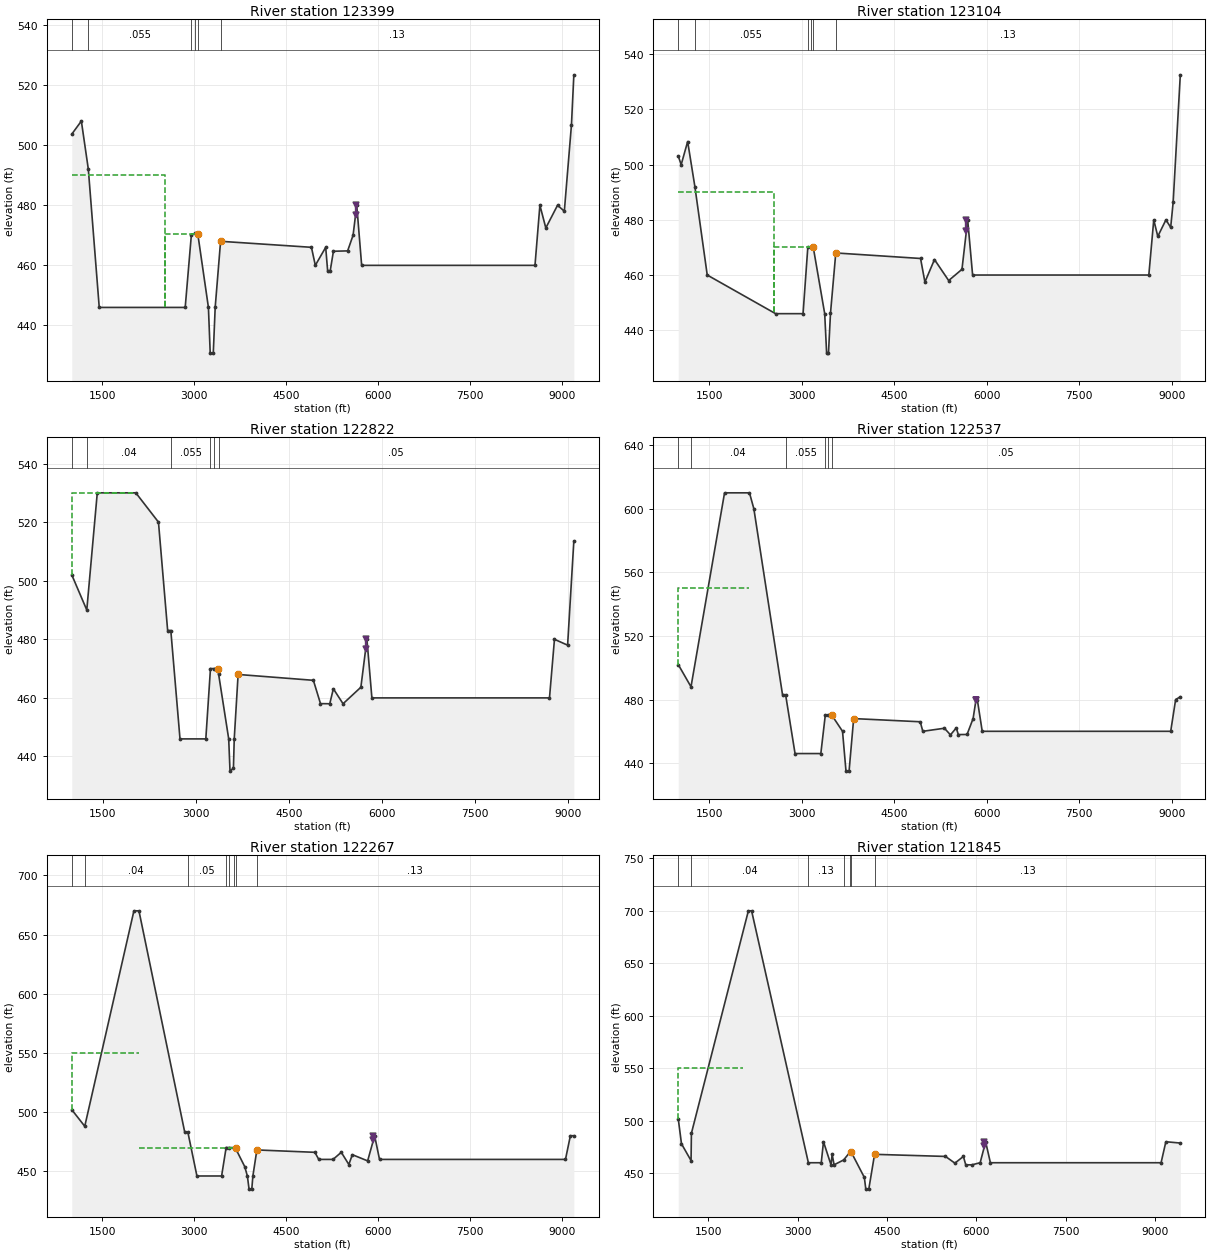
Type RM Length L Ch R = 1 ,123399  ,335,295,261
BEGIN DESCRIPTION:
This cross section corresponds to cross section 123437 of the non-georeferenced CDC model which was the source of this model.
END DESCRIPTION:
XS GIS Cut Line= 4
   2390897.30131 6977827.4877882  2390897.203477 6977817.4279804
 2390852.2960866 6973199.8007327 2392336.8275663 6969963.2035314
#Sta/Elev= 30
    1000  503.64  1156.4     508    1270     492    1448     446    2850     446
    2950     470  3005.4  470.65  3054.8  470.54 3228.73     446    3258   430.8
    3308   430.8 3339.01     446 3427.18     468 4908.99     466 4972.34     460
 5141.47     466  5173.9     458 5213.76     458 5267.44  464.69 5499.29  464.81
    5588     470    5648     480    5728     460    8555     460    8635     480
  8731.6  472.44 8923.06     480 9033.48     478 9149.88  506.77 9188.72  523.38
#Mann= 6 ,-1,0
    1000     .09       0    1270    .055       0    2950     .04       0
  3005.4     .09       0  3054.8     .05       0 3427.18     .13       0
Levee=0,,,-1,5628,480,,Levee 1
#XS Ineff= 3 ,-1
    1000    2518     490    2518  3054.8  470.54 3427.18 9188.72     468
Permanent Ineff=
       T       F       F
Bank Sta=3054.8,3427.18
XS Rating Curve= 0 ,0
Exp/Cntr=0.3,0.1

Type RM Length L Ch R = 1 ,123104  ,313,282,245
BEGIN DESCRIPTION:
This cross section corresponds to cross section 123144 of the non-georeferenced CDC model which was the source of this model.
END DESCRIPTION:
XS GIS Cut Line= 4
  2391255.473889 6977888.0837214  2391253.685047 6977842.3124451
 2391072.2615259 6973200.2114931 2392478.5116662 6970054.3782178
#Sta/Elev= 30
    1000  503.15 1047.68     500 1152.74  508.37    1270     492    1470     460
    2578     446    3023     446    3100     470    3150     470  3187.4     470
 3191.03  469.72 3373.82     446    3405   431.7    3435   431.7  3467.5   446.1
 3553.36     468 4927.28     466 4997.89  457.45 5152.81  465.61 5383.05     458
  5598.6  462.07    5691     480    5771     460    8627     460    8707     480
 8772.14     474 8904.24     480  8981.2  477.27  9021.2  486.34 9137.29  532.55
#Mann= 6 ,-1,0
    1000     .09       0    1270    .055       0    3100     .04       0
    3150     .09       0 3191.03     .05       0 3553.36     .13       0
Levee=0,,,-1,5671,480,,Levee 1
#XS Ineff= 3 ,-1
    1000    2544     490    2544  3187.4     470 3553.36 9137.29     468
Permanent Ineff=
       T       F       F
Bank Sta=3187.4,3553.36
XS Rating Curve= 0 ,0
Exp/Cntr=0.3,0.1

Type RM Length L Ch R = 1 ,122822  ,302,285,227
BEGIN DESCRIPTION:
This cross section corresponds to cross section 122858 of the non-georeferenced CDC model which was the source of this model.
END DESCRIPTION:
XS GIS Cut Line= 3
   2391617.86411   6977958.18787   2391280.48289   6973223.82103
   2392626.45002   6970162.66015
#Sta/Elev= 30
    1000     502    1242     490    1411     530    2032     530    2397     520
    2545     483    2596     483    2744     446    3160     446    3235     470
    3285     470 3352.13     470 3366.89     468  3528.8     446    3550     435
    3605     436 3618.01     446 3680.43     468 4893.27     466 5007.89  458.04
 5157.14     458 5215.15  463.11 5371.34     458 5658.63  463.64    5756     480
    5836     460    8698     460    8778     480  8989.8     478 9090.37  513.58
#Mann= 6 ,-1,0
    1000     .09       0    1242     .04       0    2596    .055       0
    3235     .04       0    3285     .13       0 3366.89     .05       0
Levee=0,,,-1,5736,480,,Levee 1
#XS Ineff= 3 ,-1
    1000    2032     530    2032 3352.13     470 3680.43 9090.37     468
Permanent Ineff=
       F       F       F
Bank Sta=3352.13,3680.43
XS Rating Curve= 0 ,0
Exp/Cntr=0.3,0.1

Type RM Length L Ch R = 1 ,122537  ,299,270,224
BEGIN DESCRIPTION:
This cross section corresponds to cross section 122578 of the non-georeferenced CDC model which was the source of this model.
END DESCRIPTION:
XS GIS Cut Line= 4
  2391978.100513 6978072.7867457  2391977.137012  6978062.827424
 2391511.6422088  6973251.195315 2392947.2613848 6970283.5450823
#Sta/Elev= 30
    1000     502    1207     488    1751     610    2155     610    2226     600
    2691     483    2741     483    2894     446    3312     446    3384     470
    3434     470 3492.52     470 3663.85     460    3720  434.95    3770  434.95
 3844.38     468 4924.04     466 4965.29     460 5316.36  461.93  5413.7  457.75
 5508.21  462.12 5541.14  457.94 5682.84     458    5781     468    5829     480
    5849     480    5929     460    8985     460    9065     480 9140.76  481.67
#Mann= 6 ,-1,0
    1000     .09       0    1207     .04       0    2741    .055       0
    3384     .04       0    3434     .09       0 3492.52     .05       0
Levee=0,,,-1,5829,480,,Levee 1
#XS Ineff= 3 ,-1
    1000    2155     550    2155 3492.52     470 3844.38 9140.76     468
Permanent Ineff=
       F       F       F
Bank Sta=3492.52,3844.38
XS Rating Curve= 0 ,0
Exp/Cntr=0.3,0.1

Type RM Length L Ch R = 1 ,122267  ,539,422,405
BEGIN DESCRIPTION:
This cross section corresponds to cross section 122304 of the non-georeferenced CDC model which was the source of this model.
END DESCRIPTION:
XS GIS Cut Line= 3
   2392336.84397   6978167.12807   2391726.70805   6973268.33111
   2393271.58488   6970394.21907
#Sta/Elev= 30
    1000     502    1212     488    2015     670    2097     670    2845     483
    2896     483    3044     446    3447     446    3521     470    3571     470
 3649.85     470 3675.17  469.31 3823.93     454 3867.94     446    3895     435
    3940   434.9 3957.83     446 4023.01     468 4969.97     466 5033.93     460
  5266.5     460 5401.55     466 5524.94   455.7 5582.02     464 5832.03  458.76
    5946     480    6026     460    9063     460    9143     480 9199.65     480
#Mann= 8 ,-1,0
    1000     .09       0    1212     .04       0    2896     .05       0
    3521     .04       0    3571     .09       0 3649.85     .13       0
 3675.17     .05       0 4023.01     .13       0
Levee=0,,,-1,5926,480,,Levee 1
#XS Ineff= 3 ,-1
    1000    2097     550    2097 3675.17   469.4 4023.01 9199.65     468
Permanent Ineff=
       F       F       F
Bank Sta=3675.17,4023.01
XS Rating Curve= 0 ,0
Exp/Cntr=0.3,0.1

Type RM Length L Ch R = 1 ,121845  ,460,480,345
BEGIN DESCRIPTION:
This cross section corresponds to cross section 121885 of the non-georeferenced CDC model which was the source of this model.
END DESCRIPTION:
XS GIS Cut Line= 4
  2392934.922293 6978346.7119413   2392933.73418 6978339.8455707
 2392057.4321277 6973275.5010407 2393585.4271033 6970382.4887821
#Sta/Elev= 30
    1000     502 1054.54  478.03 1215.04     462  1220.7     488    2176     700
    2230     700    3182     460 3398.05     460 3435.39     480 3561.52     458
 3580.61     468 3613.07     458 3773.31  462.65 3878.42     470  3901.4     470
  4120.4     446    4145  434.85    4195  434.85 4292.05     468 5481.06     466
 5638.54   459.6 5781.26     466 5820.54     458 5924.02     458 6062.45     460
    6154     480    6234     460    9096     460    9176     480 9418.31  478.75
#Mann= 7 ,-1,0
    1000     .09       0  1220.7     .04       0    3182     .13       0
 3773.31     .09       0 3878.42     .13       0  3901.4     .05       0
 4292.05     .13       0
Levee=0,,,-1,6134,480,,Levee 1
#XS Ineff= 3 ,-1
    1000    2081     550    2081 3901.39     470 4292.05 9418.31     468
Permanent Ineff=
       F       F       F
Bank Sta=3901.4,4292.05
XS Rating Curve= 0 ,0
Exp/Cntr=0.3,0.1

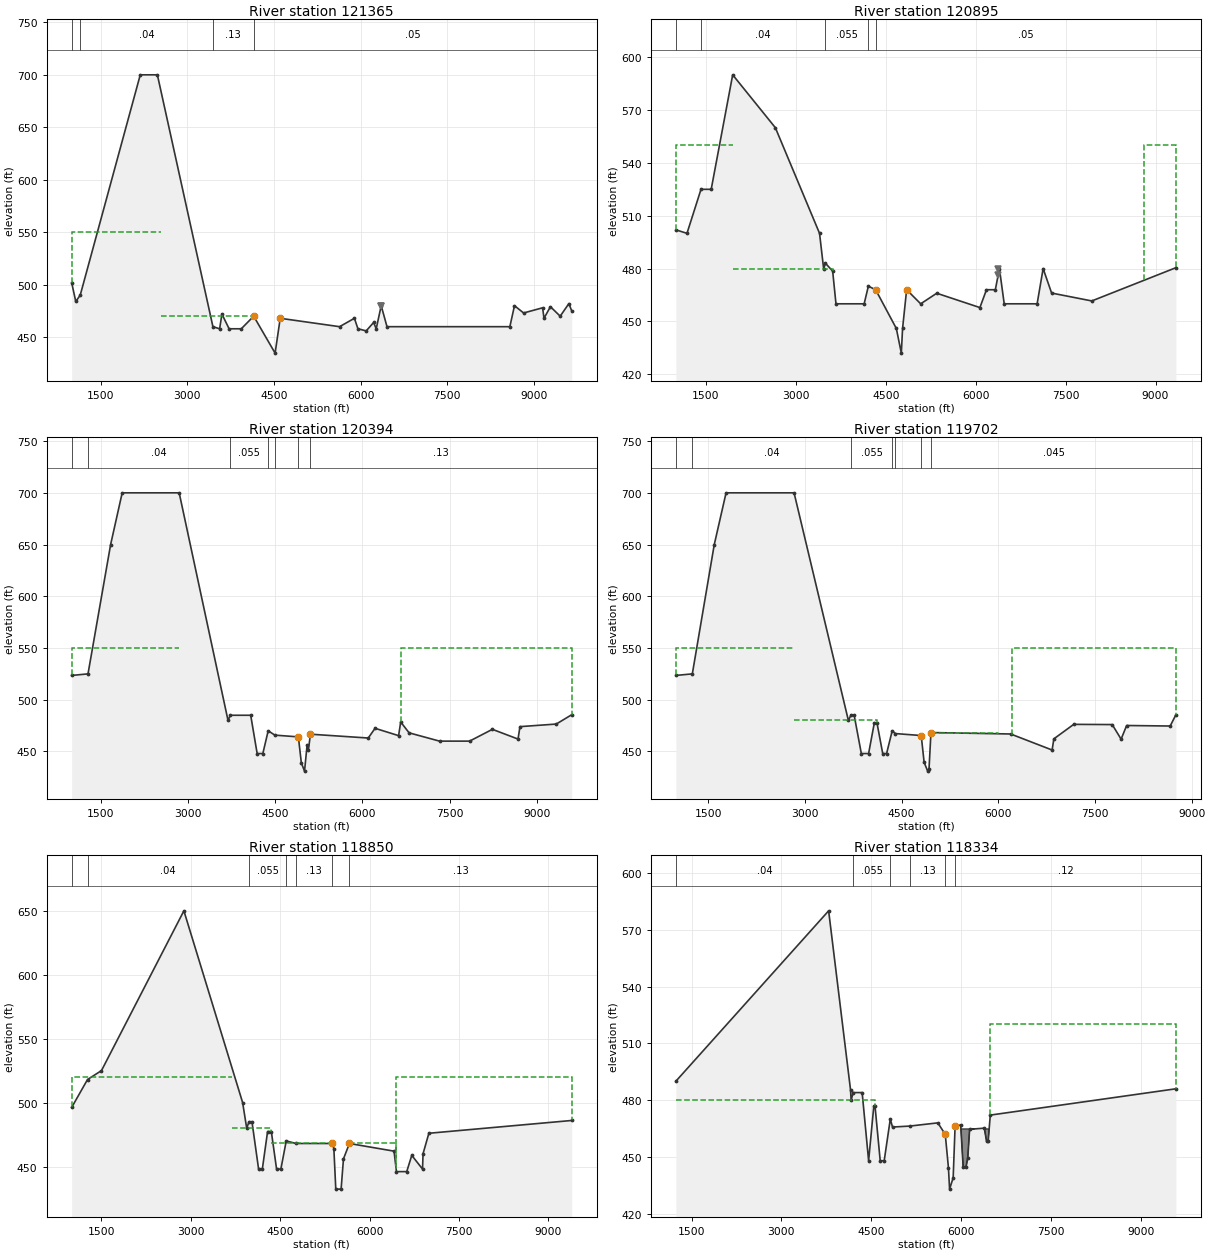
Type RM Length L Ch R = 1 ,121365  ,389,470,599
BEGIN DESCRIPTION:
This cross section corresponds to cross section 121401 of the non-georeferenced CDC model which was the source of this model.
END DESCRIPTION:
XS GIS Cut Line= 4
   2393532.90785   6978515.49187   2392989.30887   6975608.10005
   2392373.15394   6973274.88293   2393895.63514   6970368.50784
#Sta/Elev= 30
    1000     502 1070.87     484  1147.9     490    2187     700    2483     700
    3444     460 3560.38     458  3599.8     472 3724.17     458 3934.87     458
 4149.42     470    4520   434.8 4608.69     468 5635.51     460 5892.36     468
 5953.27     458 6096.46     456 6224.52     464 6269.53     458    6356     480
    6456     460    8582     460    8662     480 8820.05  473.06 9148.57     478
  9172.7     468 9283.87  479.04 9452.94     470 9603.19     482 9651.98  475.13
#Mann= 4 ,-1,0
    1000     .09       0  1147.9     .04       0    3444     .13       0
 4149.42     .05       0
Levee=0,,,-1,6356,480,,Levee 1
#XS Ineff= 3 ,-1
    1000 2540.01     550 2540.01 4149.41     470 4608.69 9651.98     468
Permanent Ineff=
       F       F       F
Bank Sta=4149.42,4608.69
XS Rating Curve= 0 ,0
Exp/Cntr=0.3,0.1

Type RM Length L Ch R = 1 ,120895  ,599,501,399
BEGIN DESCRIPTION:
This cross section corresponds to cross section 120930 of the non-georeferenced CDC model which was the source of this model.
END DESCRIPTION:
XS GIS Cut Line= 4
   2393841.16806   6978605.57207   2393036.23594   6973279.50694
   2394241.37297   6971189.00095 2394511.0941755 6970721.1256947
#Sta/Elev= 30
    1000     502    1185     500    1419     525    1589     525  1947.4     590
 2658.72     560    3396     500    3464     480    3495     483  3614.8  478.56
    3670     460    4140     460    4210     470 4331.52     468  4676.8     446
    4760     432  4780.7     446 4848.52     468 5083.05     460 5350.68     466
 6070.55  457.86 6180.38     468    6328     468    6396     480    6476     460
    7025     460    7125     480  7266.5   466.1 7936.78  461.63  9339.6   480.5
#Mann= 5 ,-1,0
    1000     .09       0    1419     .04       0    3495    .055       0
    4210     .13       0 4331.52     .05       0
Levee=0,,,-1,6376,480,,Levee 1
#XS Ineff= 5 ,-1
    1000  1947.4     550  1947.4  3614.8     480  3614.8 4331.52     468
 4848.52 8799.56     468 8799.56  9339.6     550
Permanent Ineff=
       F       F       F       F       F
Bank Sta=4331.52,4848.52
XS Rating Curve= 0 ,0
Exp/Cntr=0.3,0.1

Type RM Length L Ch R = 1 ,120394  ,453,693,1087
BEGIN DESCRIPTION:
This cross section corresponds to cross section 120428 of the non-georeferenced CDC model which was the source of this model.
Cross-section WF113.  Effective flow limit set at Arlington Landfill, at sta 6659 in ROB at top of Village Creek STP Drying Beds Levee.
Channel data from 1975 USACOE field survey.
END DESCRIPTION:
XS GIS Cut Line= 5
      2394715.55       6978688.4      2393380.09     6973203.916
     2394405.682     6971467.403 2394755.9137868 6970874.3971548
2394882.945671866970659.30916676
#Sta/Elev= 30
    1000  523.49    1281     525    1670     650    1869     700    2849     700
  3689.1     480 3728.15     485 4079.18     485 4190.18     448    4288     448
    4380     470    4494   465.8    4899   464.1    4950     439    5005     431
    5050   456.5    5072   451.7    5107   466.7    6101     463    6218   472.4
    6623   465.3    6659   478.5  6803.8     468  7326.7     460  7843.9     460
  8235.8   471.4    8677     462  8710.6     474  9334.4   476.5    9600   485.5
#Mann= 7 ,-1,0
    1000     .09       0    1281     .04       0 3728.15    .055       0
    4380     .09       0    4494     .13       0    4899    .055       0
    5107     .13       0
#XS Ineff= 5 ,-1
    1000    2849     550    6659    9600     550    2849 4079.18     480
    5107    6659   466.7 4079.18    4899   464.1
Permanent Ineff=
       F       F       F       F       F
Bank Sta=4899,5107
XS Rating Curve= 0 ,0
Exp/Cntr=0.3,0.1

Type RM Length L Ch R = 1 ,119702  ,559,851,527
BEGIN DESCRIPTION:
This cross section corresponds to cross section 119740 of the non-georeferenced CDC model which was the source of this model.
Cross-section WF112.  Effective flow limit set at Arlington Landfill, at sta 6220 in ROB due to Village Creek STP Drying Beds Levee.  River Legacy Park in ROB.
Channel data from 1975 USACOE field survey.
END DESCRIPTION:
XS GIS Cut Line= 4
   2394732.16201   6978693.19165   2394398.25553   6975203.13695
   2395075.41986   6971013.03903 2395076.1449639 6971008.5522956
#Sta/Elev= 30
    1000  523.49    1255     525  1595.4     650  1778.4     700  2832.9     700
  3675.2     480  3714.2     485    3765     485    3876     448    3989     448
    4078  477.76 4118.51  477.76 4207.78     448    4268     448    4355     470
    4405   467.3    4805   465.4    4850   439.5    4905     431    4926   433.2
    4956   468.3    6192   466.9    6835   451.4    6862   462.2    7170   476.2
    7767     476    7905   461.9    7991   475.1    8666   474.6    8755   485.5
#Mann= 7 ,-1,0
    1000     .08       0    1255     .04       0  3714.2    .055       0
    4355     .08       0    4405     .13       0    4805    .055       0
    4956    .045       0
#XS Ineff= 5 ,-1
    1000  2832.9     550    6220    8755     550  2832.9 4118.51     480
    4956    6000   468.3 4118.51    4805   465.4
Permanent Ineff=
       F       F       F       F       F
Bank Sta=4805,4956
XS Rating Curve= 0 ,0
Exp/Cntr=0.3,0.1

Type RM Length L Ch R = 1 ,118850  ,338,516,320
BEGIN DESCRIPTION:
This cross section corresponds to cross section 118883 of the non-georeferenced CDC model which was the source of this model.
END DESCRIPTION:
XS GIS Cut Line= 5
  2395083.250572  6978901.396929  2395083.604225 6978874.4376774
 2395140.0276686 6974573.2221985 2394901.8765701  6974320.704987
 2395252.8748838 6970623.5696647
#Sta/Elev= 30
    1000  496.19 1266.19  518.05 1499.98     525  2882.8     650  3868.4     500
  3936.4     480  3975.6     485 4025.26     485 4136.26     448    4199     448
    4287  477.34 4349.93  477.34    4438     448    4510     448    4600     470
 4763.26     468    5370     468    5399     464 5431.33   432.3 5520.52   432.3
 5560.42     456 5660.13     468 6408.77     462 6449.24     446 6621.78     446
 6706.18   458.7 6886.76     448 6895.43     460 6993.17     476 9389.41     486
#Mann= 7 ,-1,0
    1000     .08       0 1266.19     .04       0  3975.6    .055       0
    4600     .08       0 4763.26     .13       0    5370     .06       0
 5660.13     .13       0
#XS Ineff= 5 ,-1
    1000    3682     520    6444 9389.41     520    3682 4349.93     480
 5660.13    6444  468.17 4349.93    5370  468.17
Permanent Ineff=
       T       T       F       F       F
#Block Obstruct= 2 , 0
       0                    6000       0   464.8
Bank Sta=5370,5660.13
XS Rating Curve= 0 ,0
Exp/Cntr=0.3,0.1

Type RM Length L Ch R = 1 ,118334  ,257,265,61
BEGIN DESCRIPTION:
This cross section corresponds to cross section 118369 of the non-georeferenced CDC model which was the source of this model.
END DESCRIPTION:
XS GIS Cut Line= 4
  2395440.313041 6978817.8179206 2395443.7717583 6973819.8191173
 2395443.9468394 6973566.81917792395446.092101896970466.81992018
#Sta/Elev= 30
    1239     490    3790     580  4155.6   485.5  4165.6     480 4200.75     484
 4349.89     484 4457.89     448 4544.62  476.91 4564.62  476.91  4651.4     448
    4718     448    4820     470    4857   465.8    5144   466.3    5614     468
    5738   461.9    5791   444.3    5810     433    5870     439    5902   466.1
    5996   466.9    6037   444.6    6085   444.7    6114   449.6    6145   464.6
    6390   465.2    6428   458.2    6454   458.2    6490   472.1    9590     486
#Mann= 6 ,-1,0
    1239     .04       0 4200.75    .055       0    4820     .08       0
    5144     .13       0    5738     .06       0    5902     .12       0
#XS Ineff= 4 ,-1
    6490    9590     520    1239 4564.62     480    5902    6490   466.1
 4564.62    5738   461.9
Permanent Ineff=
       F       F       F       F
#Block Obstruct= 1 ,-1
    5996 6489.99   464.8
Bank Sta=5738,5902
XS Rating Curve= 0 ,0
Exp/Cntr=0.3,0.1