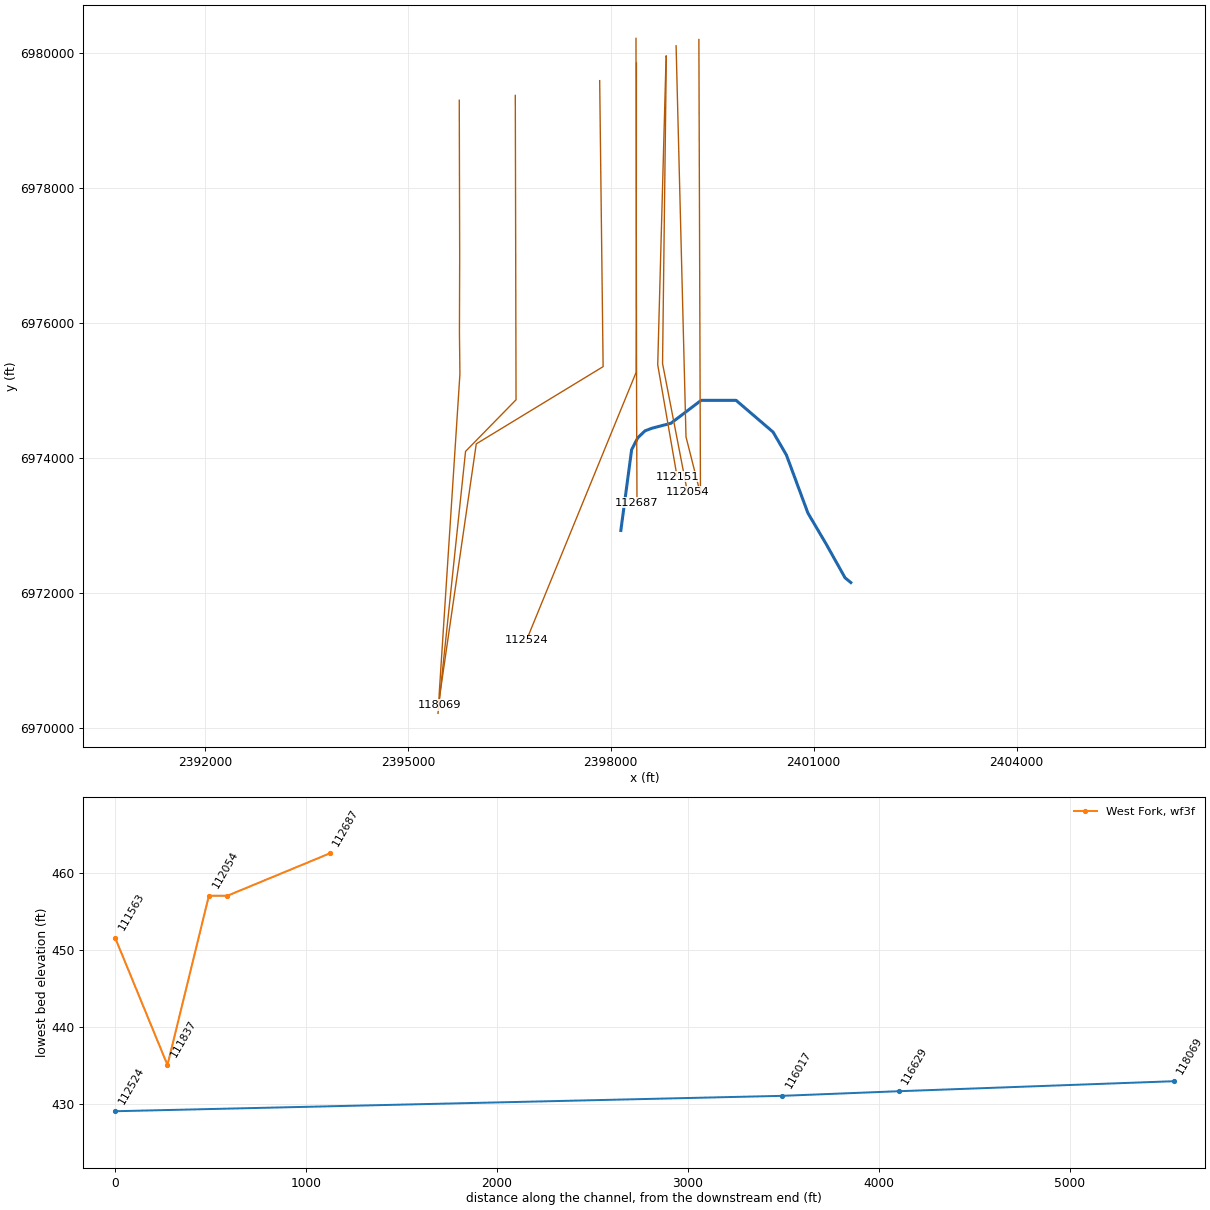
HEC-RAS study CDC_Consolidated_Model.prj: Upper Trinity CDC Consolidated Model

--- CDC_Consolidated_Model.g01 (geometry) --- (continued)

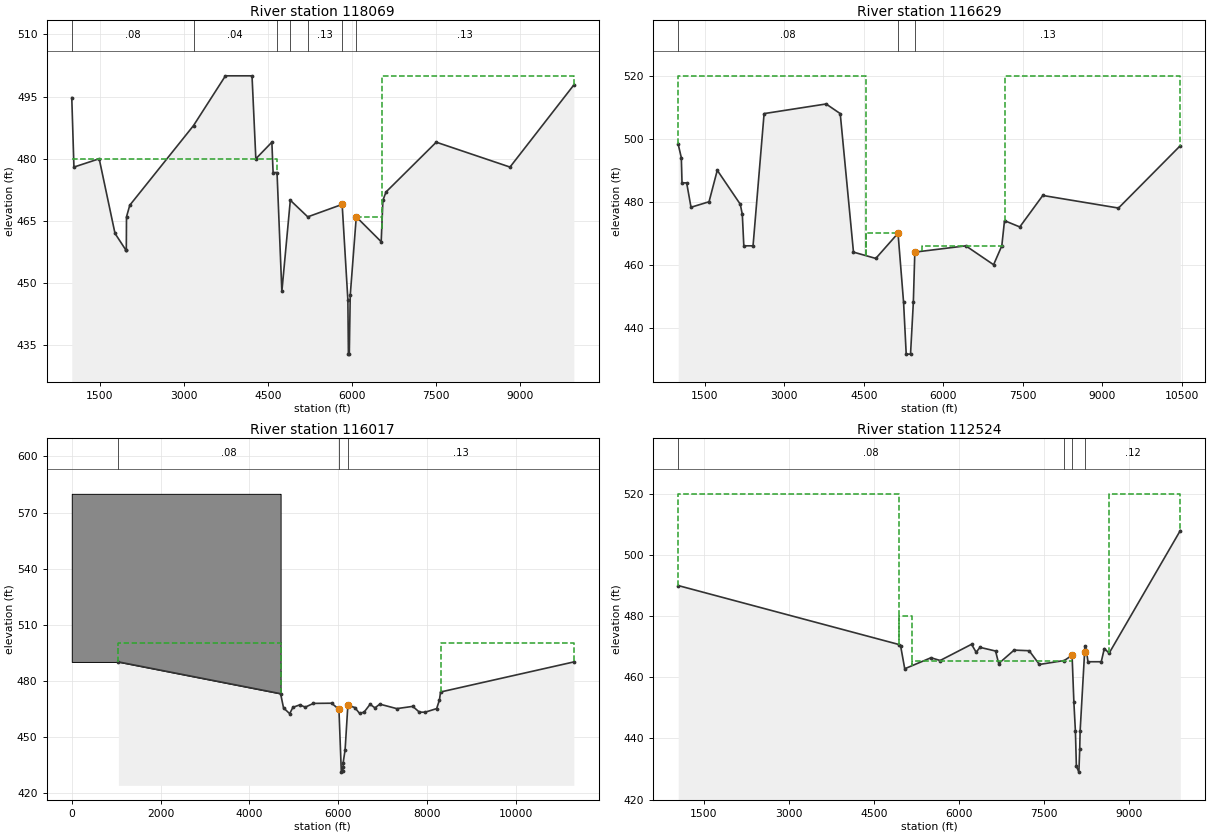
Type RM Length L Ch R = 1 ,118069  ,1399,1440,330
BEGIN DESCRIPTION:
This cross section corresponds to cross section 118100 of the non-georeferenced CDC model which was the source of this model.
END DESCRIPTION:
XS GIS Cut Line= 6
  2395760.713111 6979297.4298475 2395766.7639479 6976982.2934958
 2395763.2915139 6975860.7658832 2395770.2360538 6975242.7103608
 2395463.3783998 6970505.2969354 2395463.3783998 6970347.9293564
#Sta/Elev= 30
    1000  494.75 1038.75     478 1489.33     480 1771.69     462 1965.04     458
 1973.14     458 1976.69     466 2035.09   468.8  3172.3     488  3742.2     500
  4216.6     500  4284.6     480  4570.7     484 4592.66  476.68  4662.9  476.68
    4749     448    4900     470    5211     466    5825     469 5927.01     446
 5936.54   432.9 5952.36   432.9 5969.27  447.08 6076.95     466  6521.7     460
 6552.17     470 6608.18     472    7504     484 8820.07     478 9959.48   497.8
#Mann= 7 ,-1,0
    1000     .08       0  3172.3     .04       0  4662.9    .055       0
    4900     .08       0    5211     .13       0    5825     .06       0
 6076.95     .13       0
#XS Ineff= 4 ,-1
    6531 9959.48     500    1000  4662.9     480  4662.9    5825     469
 6076.95    6531     466
Permanent Ineff=
       T       F       F       F
Bank Sta=5825,6076.95
XS Rating Curve= 0 ,0
Exp/Cntr=0.3,0.1

Type RM Length L Ch R = 1 ,116629  ,595,612,140
BEGIN DESCRIPTION:
This cross section corresponds to cross section 116664 of the non-georeferenced CDC model which was the source of this model.
END DESCRIPTION:
XS GIS Cut Line= 6
  2396589.172152 6979368.8317334  2396589.255085  6979334.663463
 2396600.1057852 6974864.1773252 2395853.5780788 6974100.2884331
 2395449.8452904 6970257.0592429 2395446.2755323 6970223.0778597
#Sta/Elev= 30
    1000  498.22 1058.29     494 1071.33     486 1159.07     486 1240.91  478.25
 1581.06     480  1736.4     490 2170.07  479.22 2208.81     476 2237.19     466
 2411.38     466 2619.58     508 3789.23  511.06 4055.85     508 4305.89     464
 4726.63     462 5146.23     470 5251.18     448 5300.52   431.6 5382.09   431.6
    5435     448    5463     464    6425     466    6949     460 7104.06     466
 7154.89     474 7443.08     472 7877.16     482 9305.03     47810471.31  497.81
#Mann= 3 ,-1,0
    1000     .08       0 5146.23     .06       0    5463     .13       0
#XS Ineff= 4 ,-1
    1000    4550     520    716310471.31     520    4550 5146.23     470
 5604.21    7163     466
Permanent Ineff=
       T       T       F       F
Bank Sta=5146.23,5463
XS Rating Curve= 0 ,0
Exp/Cntr=0.3,0.1

Type RM Length L Ch R = 1 ,116017  ,502,3493,1757
BEGIN DESCRIPTION:
This cross section corresponds to cross section 116053 of the non-georeferenced CDC model which was the source of this model.
---------------------------------------------------------------------
CDC ARL021910-1 ARLINGTON LANDFILL
CROSS-SECTION 116053-125562
DOWNSTREAM END
---------------------------------------------------------------------
END DESCRIPTION:
XS GIS Cut Line= 6
2397836.821699946979587.40309086  2397880.633662 6975937.6660439
   2397887.63011   6975354.82989   2396011.94784   6974211.57791
 2395928.6605288 6973637.09795172395463.789906646970430.62086545
#Sta/Elev= 30
    1050     490    4700     473    4766   465.4    4904   462.3    4978   465.7
    5130     467    5256   465.8    5438   467.8    5849   467.9    6013   464.6
    6067     431    6097   431.4    6106   433.7    6108     436    6152     443
    6214   466.8    6369   465.6    6476   462.5    6578   463.1    6714   467.3
    6825   465.4    6932   467.4    7315     465    7675   466.2    7824   463.1
    7954   463.1    8212     465    8275   469.6    8300   473.9   11300     490
#Mann= 3 ,0,0
    1050     .08       0    6013    .055       0    6214     .13       0
#XS Ineff= 2 ,-1
    1050    4700     500    8300   11300     500
Permanent Ineff=
       F       F
#Block Obstruct= 2 , 0
       0 4700.01     580 8299.99       0     580
Bank Sta=6013,6214
XS Rating Curve= 0 ,0
Exp/Cntr=0.3,0.1

Type RM Length L Ch R = 1 ,112524  ,0,0,0
BEGIN DESCRIPTION:
This cross section corresponds to cross section 112574 of the non-georeferenced CDC model which was the source of this model.
Flow limit due to d/s fill.  Cross Section Truncated due to Ineffective Flow Areas
END DESCRIPTION:
XS GIS Cut Line= 6
      2398380.17      6979849.15      2398377.95      6975948.18
     2398375.625     6975269.703 2397355.0711938 6972774.1297082
 2397228.1415286 6972463.7469723  2396754.994459 6971306.7543835
#Sta/Elev= 30
    1050     490    4950   470.7    4976   470.1    5047   462.8    5510   466.4
    5672   465.5    6226   470.8    6307   468.2    6375   469.8    6650   468.6
    6705   464.5    6977   468.9    7243   468.7    7423   464.2    7863   465.5
    8000   467.2    8032   451.8    8059   442.3    8076   430.9    8120     429
    8135   436.6    8142   442.4    8221   468.2    8225   470.3    8253   468.9
    8280   465.1    8515   465.1    8569   469.4    8654   467.9    9910     508
#Mann= 4 ,-1,0
    1050     .08       0    7863     .12       0    8000     .05       0
    8221     .12       0
#XS Ineff= 5 ,-1
    1050    4950     520    4950    5180     480    5180    8000   465.5
    8221    8660   465.5    8660    9910     520
Permanent Ineff=
       F       F       F       F       F
Bank Sta=8000,8221
XS Rating Curve= 0 ,0
Exp/Cntr=0.3,0.1

River Reach=West Fork       ,wf3f
Reach XY= 14
      2398149.68       6972930.3      2398309.17      6974125.01
       2398399.5      6974301.37      2398507.03       6974404.6
      2398610.27      6974443.32      2398889.86      6974516.44
      2399337.21      6974856.26      2399853.39      6974856.26
      2400399.67       6974387.4      2400597.54      6974047.58
      2400915.85      6973187.29      2401186.84      6972727.04
      2401464.92      6972229.44      2401550.25       6972159.5

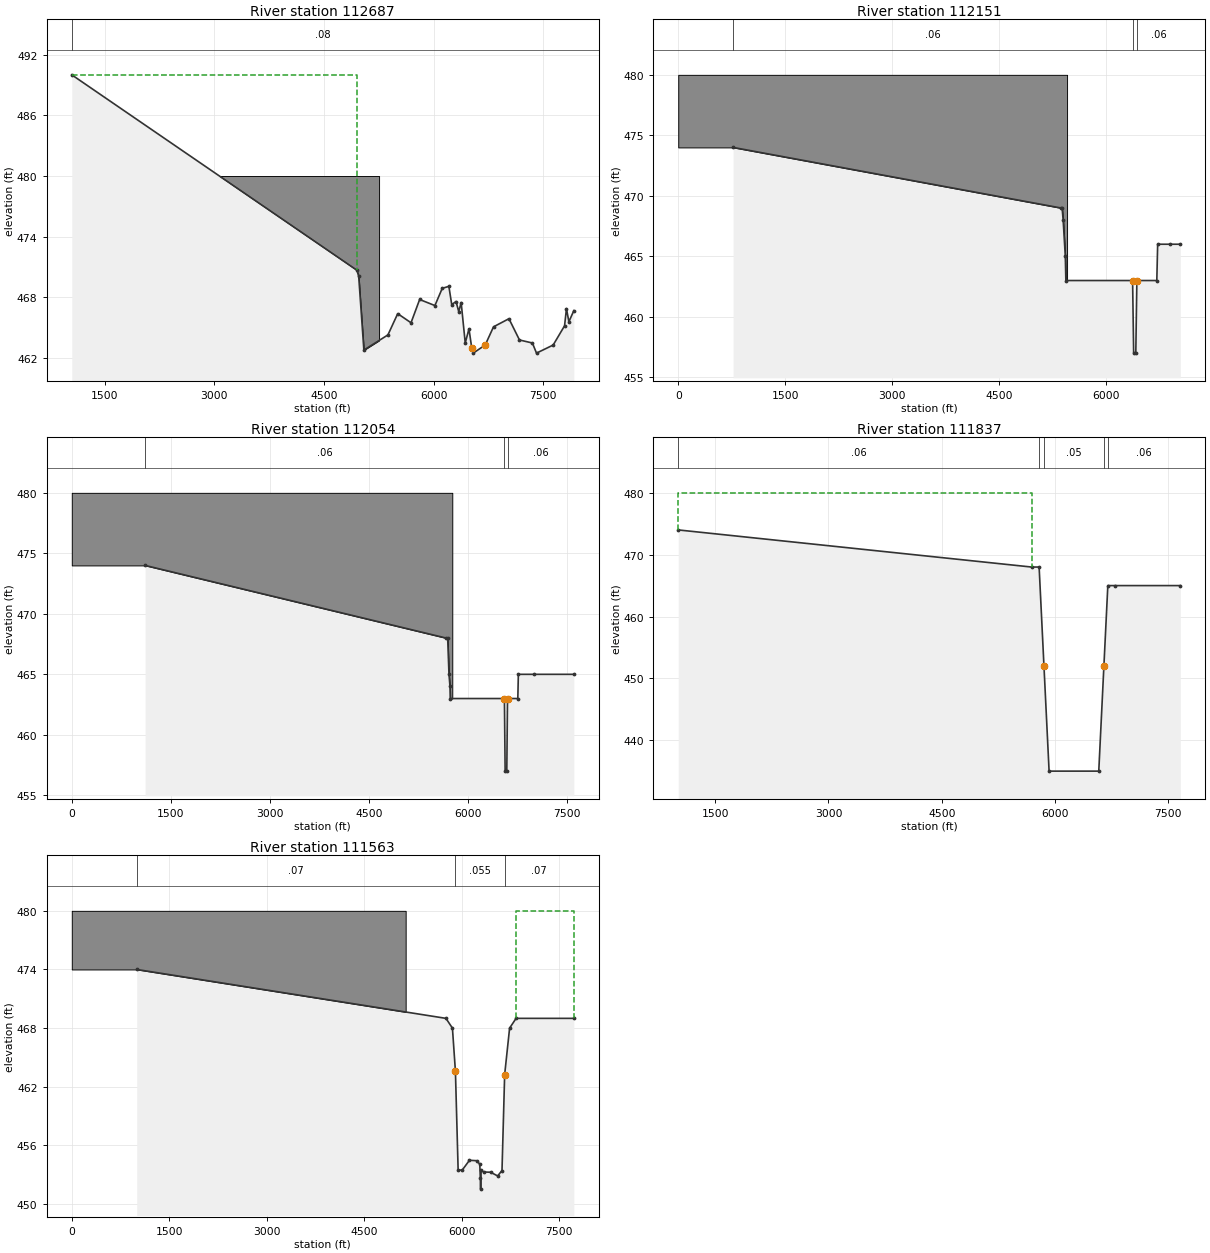
Type RM Length L Ch R = 1 ,112687  ,417,536,775
BEGIN DESCRIPTION:
This cross section corresponds to cross section 111680 of the non-georeferenced CDC model which was the source of this model.
Cross Section Truncated due to Ineffective Flow Areas
END DESCRIPTION:
XS GIS Cut Line= 5
2398373.658956566980213.55459825      2398380.15      6976313.56
      2398382.81      6974715.36      2398386.71      6973771.74
2398388.479685916973343.55768674
#Sta/Elev= 30
    1050     490    4950   470.7    4976   470.1    5047   462.8    5376   464.3
    5510   466.4    5692   465.5    5810   467.8    6019   467.2    6119   468.9
    6210   469.1    6249   467.3    6308   467.6    6345   466.6    6378   467.5
    6434   463.5    6485   464.9    6523     463    6543   462.5    6707   463.3
    6821   465.1    7032   465.9    7176   463.8    7353   463.5    7409   462.5
    7637   463.3    7793   465.2    7819   466.9    7852   465.6    7920   466.7
#Mann= 1 ,-1,0
    1050     .08       0
#XS Ineff= 2 , 0
       0    4950     490               0
Permanent Ineff=
       F       F
#Block Obstruct= 2 , 0
       0    5255     480    7155       0     480
Bank Sta=6523,6707
XS Rating Curve= 0 ,0
Exp/Cntr=0.3,0.1

Type RM Length L Ch R = 1 ,112151  ,87,97,97
BEGIN DESCRIPTION:
This cross section corresponds to cross section 110516 of the non-georeferenced CDC model which was the source of this model.
Old roadway embankment lowered from 466 to 463.  Section just upstream of old Collins St. alignment.  Section based on 2006 topography.
END DESCRIPTION:
XS GIS Cut Line= 6
     2398818.978     6979950.345     2398818.957     6979950.612
  2398694.954069 6975382.0308141      2398794.94        6974804.
 2398955.7359303  6973874.419186 2398981.3027794 6973726.6141244
#Sta/Elev= 14
     770     474    5370     469    5390     469    5405     468    5435     465
    5443     463    6380     463    6395     457    6425     457    6440     463
    6720     463    6732     466    6900     466    7050     466
#Mann= 3 ,0,0
     770     .06       0    6380    .055       0    6440     .06       0
#Block Obstruct= 2 , 0
       0    5460     480    6800       0     480
Bank Sta=6380,6440
XS Rating Curve= 0 ,0
Exp/Cntr=0.5,0.3

Type RM Length L Ch R = 1 ,112054  ,276,217,197
BEGIN DESCRIPTION:
This cross section corresponds to cross section 110211of the non-georeferenced CDC model which was the source of this model.
Old roadway embankment lowered to 463.  END RELIEF CHANNEL CUT  Section along old Collins St. alignment.  Section based on 2006 topography.
END DESCRIPTION:
XS GIS Cut Line= 6
     2398822.329     6979951.664  2398766.326591 6975401.9177591
      2398835.47        6975044.       2398950.4      6974449.07
 2399019.5434086 6974091.15224092399133.348719726973502.04414287
#Sta/Elev= 14
    1110     474    5665     468    5690     468    5710     465    5725     464
    5729     463    6549     463    6560     457    6585     457    6596     463
    6752     463    6760     465    7000     465    7600     465
#Mann= 3 ,0,0
    1110     .06       0    6549    .055       0    6596     .06       0
#Block Obstruct= 2 , 0
       0    5760     480    6925       0     480
Bank Sta=6549,6596
XS Rating Curve= 0 ,0
Exp/Cntr=0.5,0.3

Type RM Length L Ch R = 1 ,111837  ,262,274,251
BEGIN DESCRIPTION:
This cross section corresponds to cross section 109696 of the non-georeferenced CDC model which was the source of this model.
Proposed fill & lake.
END DESCRIPTION:
XS GIS Cut Line= 6
2398966.652370336980103.23848301      2399088.99      6975270.48
      2399109.27      6974469.35 2399113.1749059 6974315.0927396
     2399302.364     6973566.7692399323.96551022 6973481.3257931
#Sta/Elev= 10
    1010     474    5690     468    5790     468    5854     452    5922     435
    6580     435    6648     452    6700     465    6800     465    7660     465
#Mann= 5 ,-1,0
    1010     .06       0    5790     .08       0    5854     .05       0
    6648     .08       0    6700     .06       0
#XS Ineff= 2 ,-1
    1010    5690     480    5700    6800     451
Permanent Ineff=
       F       T
#Block Obstruct= 2 , 0
       0                    6790       0     470
Bank Sta=5854,6648
XS Rating Curve= 0 ,0
Exp/Cntr=0.5,0.3

Type RM Length L Ch R = 1 ,111563  ,32,32,32
BEGIN DESCRIPTION:
This cross section corresponds to cross section 109586 of the non-georeferenced CDC model which was the source of this model.
35 FT U/S OF F.M. 157 ROADWAY EMBANKMENT
END DESCRIPTION:
XS GIS Cut Line= 6
2399303.552761076980196.19362542 2399307.3414275 6979103.3941244
     2399323.557     6974426.189  2399323.705268 6974383.4224906
 2399326.4757117 6973584.3140952      2399340.28      6973468.05
#Sta/Elev= 20
    1000     474    5760     469    5860     468    5906  463.58    5948  453.44
    6014  453.51    6122  454.48    6231  454.44    6281  454.09    6289  452.66
    6294  451.53    6302  453.49    6339  453.28    6447  453.26    6556  452.88
    6623  453.43    6664  463.25    6740     468    6840     469    7729     469
#Mann= 3 ,-1,0
    1000     .07       0    5906    .055       0    6664     .07       0
#XS Ineff= 2 , 0
       0                    6840       0     480
Permanent Ineff=
       F       F
#Block Obstruct= 2 , 0
       0    5140     480               0
Bank Sta=5906,6664
XS Rating Curve= 0 ,0
Exp/Cntr=0.5,0.3