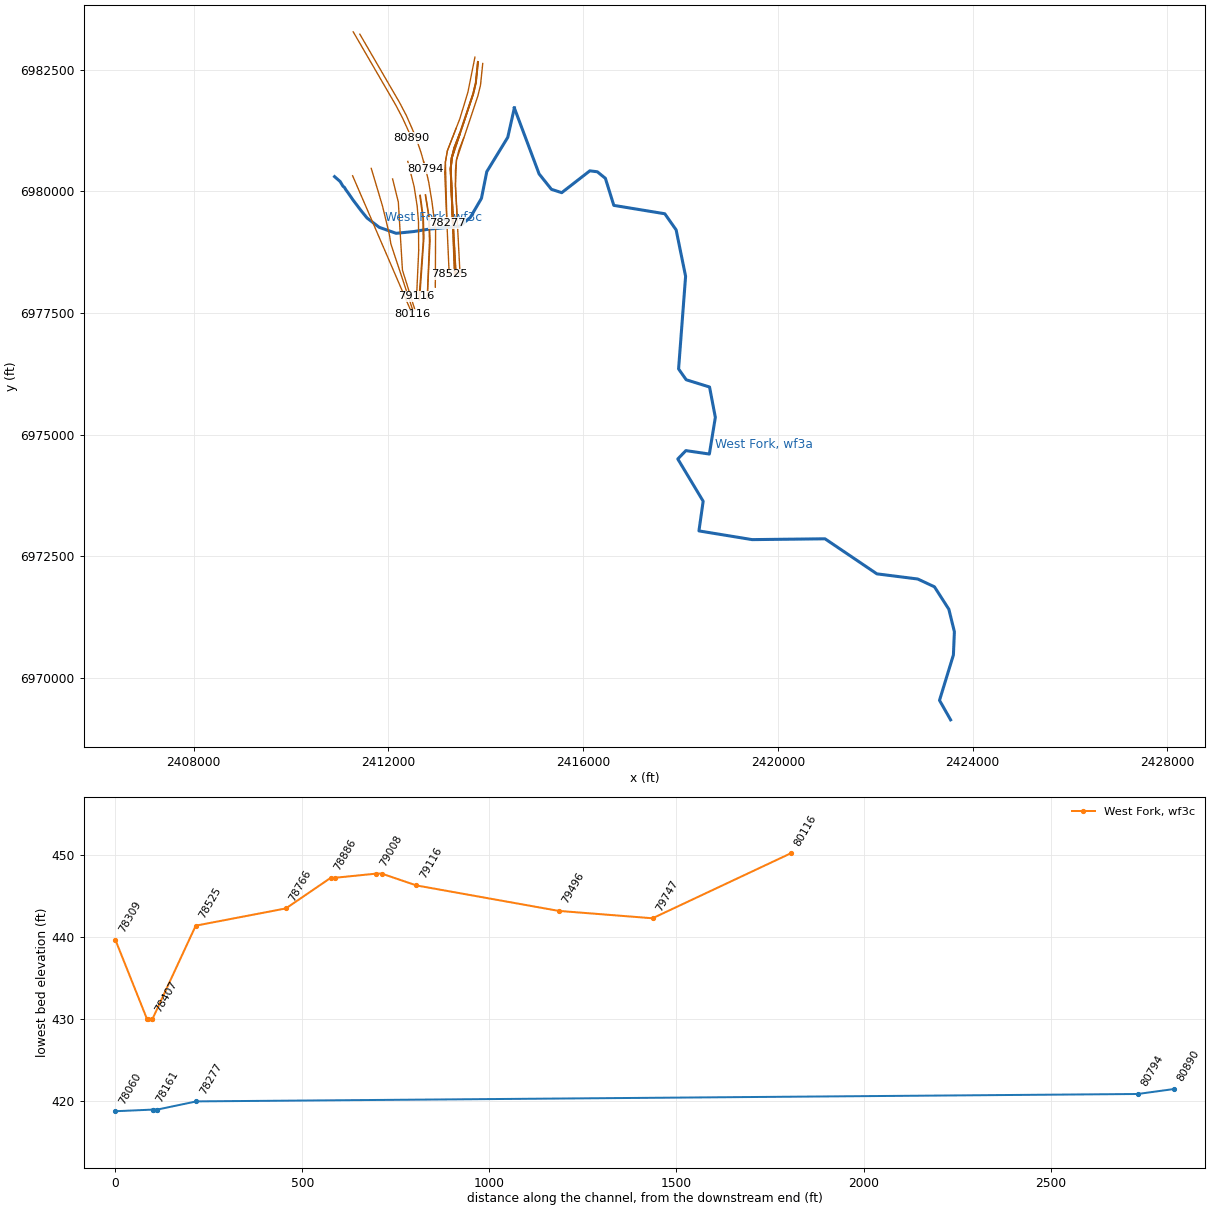
HEC-RAS study CDC_Consolidated_Model.prj: Upper Trinity CDC Consolidated Model

--- CDC_Consolidated_Model.g01 (geometry) --- (continued)

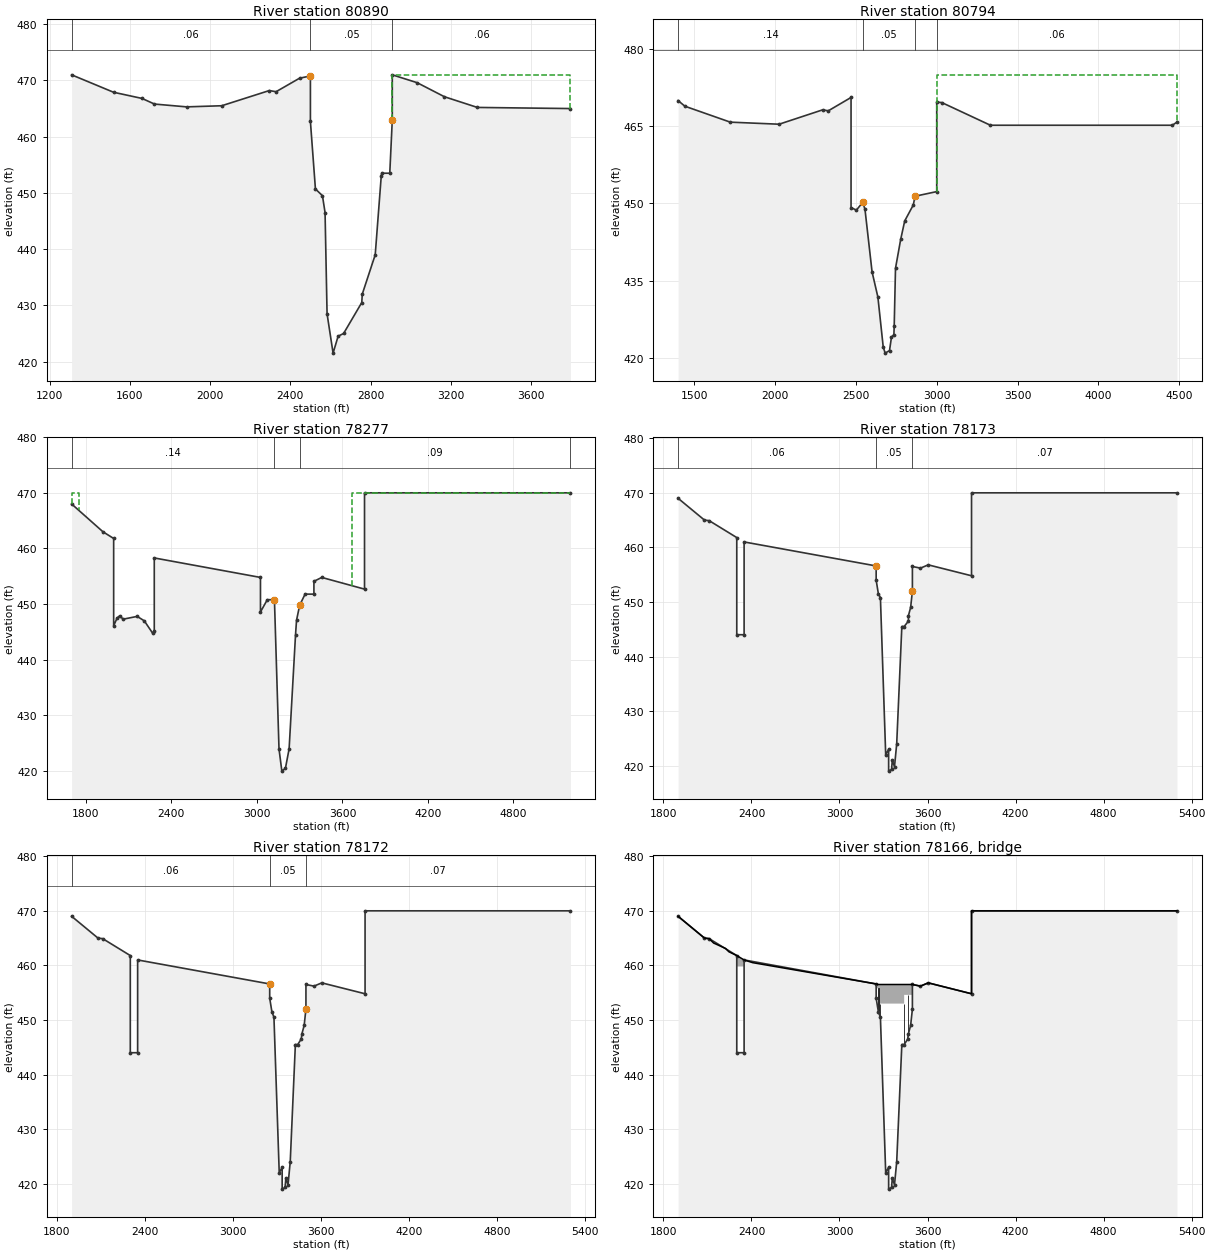
Type RM Length L Ch R = 1 ,80890   ,96,96,96
BEGIN DESCRIPTION:
This cross section corresponds to cross section 80912 of the non-georeferenced CDC model which was the source of this model.
Copy of 80913
END DESCRIPTION:
XS GIS Cut Line= 6
2411277.416279926983274.14288345 2412152.2009932 6981768.4387792
 2412292.6410011 6981500.5239607 2412417.9557111 6981226.1258874
 2412438.2630852 6981176.0347802      2412463.66      6981093.43
#Sta/Elev= 30
    1310     471    1519   467.9    1661   466.8    1723   465.8    1883   465.3
    2058   465.5    2295   468.2    2329     468    2446   470.4    2500   470.8
    2500   462.7    2525   450.7    2560   449.5    2573   446.5    2583   428.5
    2613   421.5    2638   424.5  2665.5     425    2756   430.5  2758.5     432
    2823     439    2853     453  2855.5   453.5  2895.5   453.5    2908     463
    2908     471    3032   469.6    3168   467.1    3332   465.2    3796     465
#Mann= 3 ,0,0
    1310     .06       0    2500     .05       0    2908     .06       0
#XS Ineff= 2 , 0
       0                    2908       0     471
Permanent Ineff=
       F       T
Bank Sta=2500,2908
XS Rating Curve= 0 ,0
Exp/Cntr=0.5,0.3

Type RM Length L Ch R = 1 ,80794   ,2199,2516,1590
BEGIN DESCRIPTION:
This cross section corresponds to cross section 80816 of the non-georeferenced CDC model which was the source of this model.
'n' value lowered in ROB to be consistent.
END DESCRIPTION:
XS GIS Cut Line= 6
  2411413.125043 6983226.9089593 2412229.3481487 6981822.0078977
 2412369.7881565 6981554.0930792 2412559.9209783 6981119.8101552
 2412672.2731158 6980787.0768967 2412763.5671592  6980466.485415
#Sta/Elev= 30
    1400     470    1442   468.9    1723   465.8    2025   465.4    2295   468.2
    2329     468    2470   470.6    2470   449.2    2503   448.7    2542   450.2
    2556   448.9    2600   436.7    2636   431.8    2669   422.1    2681   420.9
    2708   421.4    2720     424    2735   424.5    2737   426.2    2745   437.4
    2777     443    2802   446.6    2855   449.7    2866   451.4    3000   452.3
    3000   469.7    3032   469.6    3332   465.2    4457   465.2    4486   465.8
#Mann= 4 ,-1,0
    1400     .14       0    2542     .05       0    2866     .09       0
    3000     .06       0
#XS Ineff= 3 ,-1
    3000    4486     475    2866    3000   451.4    1400    2542     450
Permanent Ineff=
       T       F       F
Bank Sta=2542,2866
XS Rating Curve= 0 ,0
Exp/Cntr=0.5,0.3

Type RM Length L Ch R = 1 ,78277   ,105,105,105
BEGIN DESCRIPTION:
This cross section corresponds to cross section 78299 of the non-georeferenced CDC model which was the source of this model.
LOB lowered 2' below railroad.  Right flow limit adjusted due to SH 360 and flow over railroad.  LOB 'n' value corrected from 0.014 to 0.14.
END DESCRIPTION:
XS GIS Cut Line= 6
2413777.517136776982755.92061994 2413632.3000672 6982032.7138412
 2413467.6439004 6981491.1801473 2413211.5141633 6980832.5590892
    2413171.2649 6980605.6999629 2413201.7204611 6979348.0385658
#Sta/Elev= 30
    1700     468    1920     463    1995   461.8    1995   446.1    2019   447.5
    2037   447.9    2062   447.3    2160   447.8    2210     447    2268   444.8
    2280   445.2    2280   458.3    3025   454.8    3025   448.6    3073   450.8
    3123   450.8    3155     424    3175     420    3200   420.5    3226     424
    3271   444.5    3278   447.1    3300   449.8    3338   451.8    3400   451.8
    3400   454.1    3455   454.8    3755   452.7    3755     470    5200     470
#Mann= 4 ,-1,0
    1700     .14       0    3123     .05       0    3300     .09       0
    5200    .065       0
#XS Ineff= 4 ,-1
    3670    5200     470    1700    1750     470    1750    3123     450
    3300    3670   449.8
Permanent Ineff=
       F       F       F       F
Bank Sta=3123,3300
XS Rating Curve= 0 ,0
Exp/Cntr=0.5,0.3

Type RM Length L Ch R = 1 ,78173   ,1,1,1
BEGIN DESCRIPTION:
This cross section corresponds to cross section 78195 of the non-georeferenced CDC model which was the source of this model.
Right flow limit adjusted due to SH 360 and flow over railroad.  'n' value raised in ROB  to be consistent.
END DESCRIPTION:
XS GIS Cut Line= 6
  2413833.478142 6982662.7444052 2413788.9933233 6982225.4155555
  2413734.573812 6982000.4803098 2413295.1006103 6980685.3123365
 2413272.9149592 6980463.4548406 2413318.8902609 6979349.8438788
#Sta/Elev= 30
    1900     469    2080     465    2112   464.9    2300   461.8    2300     444
    2350     444    2350     461    3250   456.6    3250     454    3265   451.5
    3279   450.8    3315     422    3335     423    3335     419    3355   419.3
    3360     421    3375   419.8    3390     424    3425   445.5    3441   445.5
    3470   446.5    3470   447.5    3485     449    3497     452    3497   456.5
    3552   456.2    3605   456.8    3900   454.8    3900     470    5300     470
#Mann= 3 ,0,0
    1900     .06       0    3250     .05       0    3497     .07       0
#XS Ineff= 2 , 0
       0    3250     450               0
Permanent Ineff=
       F       F
Bank Sta=3250,3497
XS Rating Curve= 0 ,0
Exp/Cntr=0,0

Type RM Length L Ch R = 1 ,78172   ,10,10,10
BEGIN DESCRIPTION:
This cross section corresponds to cross section 78194 of the non-georeferenced CDC model which was the source of this model.
U/S face of railroad.  Right flow limit adjusted due to SH 360 and flow over railroad. 'n' value raised in ROB  to be consistent.
END DESCRIPTION:
XS GIS Cut Line= 6
  2413834.519479 6982662.7444052 2413790.0887936 6982225.6786783
  2413735.614493 6982000.5170552 2413296.1872223 6980685.5354331
 2413274.0288021 6980463.9505745 2413320.0277258 6979349.8763591
#Sta/Elev= 30
    1900     469    2080     465    2112   464.9    2300   461.8    2300     444
    2350     444    2350     461    3250   456.6    3250     454    3265   451.5
    3279   450.5    3315     422    3335     423    3335     419    3355   419.3
    3360     421    3375   419.8    3390     424    3425   445.5    3441   445.5
    3465   446.5    3470   447.5    3485     449    3497     452    3497   456.5
    3552   456.2    3605   456.8    3900   454.8    3900     470    5300     470
#Mann= 3 ,0,0
    1900     .06       0    3250     .05       0    3497     .07       0
#XS Ineff= 2 , 0
       0    3250     450               0
Permanent Ineff=
       F       F
Bank Sta=3250,3497
XS Rating Curve= 0 ,0
Exp/Cntr=0.5,0.3

Type RM Length L Ch R = 3 ,78166   ,,,
BEGIN DESCRIPTION:
Union Pacific Railroad
END DESCRIPTION:
Node Name=Union Pacific Ra
Bridge Culvert--1,0,-1,-1, 0
Deck Dist Width WeirC Skew NumUp NumDn MinLoCord MaxHiCord MaxSubmerge Is_Ogee
1,8,2.6,0, 30, 30, , , 0.95, 0, 0,0,,
    1900    2080    2112    2142    2224    2246    2300    2300    2350    2350
    2408    3250    3250    3265    3266    3275    3275    3279    3437    3441
    3441    3465    3470    3497    3497    3552    3605    3900    3900    5300
     469     465   464.9   464.1   463.1   462.5   461.8   461.8     461     461
   460.5   456.6   456.6   456.5   456.5   456.5   456.5   456.5   456.5   456.5
   456.5   456.5   456.5   456.5   456.5   456.2   456.8   454.8     470     470
     469     465   464.9   464.1   463.1   462.5   461.8   459.8   459.8     461
   460.5   456.6   455.8   455.8   455.8   455.8     453     453     453     453
   454.6   454.6   454.6   454.6   456.5   456.2   456.8   454.8     470     470
    1900    2080    2112    2142    2224    2246    2300    2300    2350    2350
    2408    3250    3250    3265    3266    3275    3275    3279    3437    3441
    3441    3465    3470    3497    3497    3552    3605    3900    3900    5300
     469     465   464.9   464.1   463.1   462.5   461.8   461.8     461     461
   460.5   456.6   456.6   456.5   456.5   456.5   456.5   456.5   456.5   456.5
   456.5   456.5   456.5   456.5   456.5   456.2   456.8   454.8     470     470
     469     465   464.9   464.1   463.1   462.5   461.8   459.8   459.8     461
   460.5   456.6   455.8   455.8   455.8   455.8     453     453     453     453
   454.6   454.6   454.6   454.6   456.5   456.2   456.8   454.8     470     470
Pier Skew, UpSta & Num, DnSta & Num=  ,3265.5, 2 ,3265.5, 2 , 0 , 0 , 0 ,,
       1       1
     450     456
       1       1
     450     456
Pier Skew, UpSta & Num, DnSta & Num=  ,3277, 2 ,3277, 2 , 0 , 0 , 0 ,,
       4       4
     450     456
       4       4
     450     456
Pier Skew, UpSta & Num, DnSta & Num=  ,3439, 2 ,3439, 2 , 0 , 0 , 0 ,,
       4       4
     450     456
       4       4
     450     456
Pier Skew, UpSta & Num, DnSta & Num=  ,3467.5, 2 ,3467.5, 2 , 0 , 0 , 0 ,,
       5       5
     450     456
       5       5
     450     456
BR Coef=-1 , 0 , 0 ,1.05, 0 ,,,0.8,-1,0.5,0,
WSPro=,,,, 1 ,,,, 0 ,,,, 0 ,,,,-1 ,-1 ,-1 , 0 , 0 , 0 , 0 , 0
BC Design=,, 0 ,, 0 ,,,,,,
BC Use User HTab Curves=0
BC User HTab FreeFlow(D)= 0

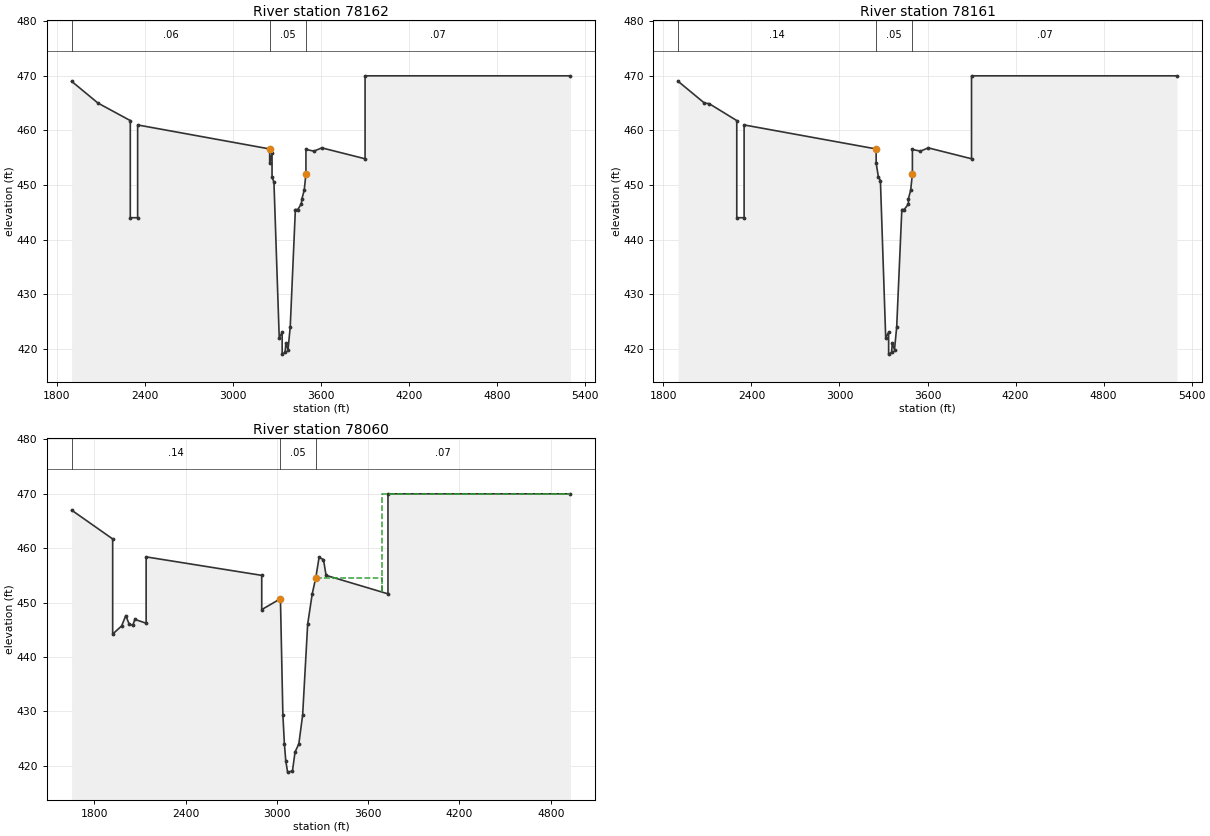
Type RM Length L Ch R = 1 ,78162   ,1,1,1
BEGIN DESCRIPTION:
This cross section corresponds to cross section 78184 of the non-georeferenced CDC model which was the source of this model.
D/S face of railroad.  Right flow limit adjusted due to SH 360 and flow over railroad.  'n' value raised in ROB  to be consistent.
END DESCRIPTION:
XS GIS Cut Line= 6
  2413844.069656 6982659.5531386 2413799.6717797 6982222.9270434
   2413745.06034 6981997.1998046  2413305.748883 6980682.6840609
  2413283.658376 6980461.7806313 2413329.7104493 6979346.6647513
#Sta/Elev= 30
    1900     469    2080     465    2300   461.8    2300     444    2350     444
    2350     461    3250   456.6    3250     454    3266   455.8    3266   451.5
    3279   450.5    3315     422    3335     423    3335     419    3355   419.3
    3360     421    3375   419.8    3390     424    3425   445.5    3441   445.5
    3465   446.5    3470   447.5    3485     449    3497     452    3497   456.5
    3552   456.2    3605   456.8    3900   454.8    3900     470    5300     470
#Mann= 3 ,0,0
    1900     .06       0    3250     .05       0    3497     .07       0
#XS Ineff= 2 , 0
       0    3250     450               0
Permanent Ineff=
       F       F
Bank Sta=3250,3497
XS Rating Curve= 0 ,0
Exp/Cntr=0.5,0.3

Type RM Length L Ch R = 1 ,78161   ,100,100,100
BEGIN DESCRIPTION:
This cross section corresponds to cross section 78183 of the non-georeferenced CDC model which was the source of this model.
Cont/Exp raised due to railroad.   Right flow limit adjusted due to SH 360 and flow over railroad.
END DESCRIPTION:
XS GIS Cut Line= 6
  2413846.168405 6982662.2860728  2413801.724269 6982225.8099117
 2413746.8392082 6981998.9511134 2413307.7583934 6980685.3671264
  2413285.804369 6980465.8268831   2413331.93551 6979349.2175677
#Sta/Elev= 30
    1900     469    2080     465    2112   464.9    2300   461.8    2300     444
    2350     444    2350     461    3250   456.6    3250     454    3265   451.5
    3279   450.8    3315     422    3335     423    3335     419    3355   419.3
    3360     421    3375   419.8    3390     424    3425   445.5    3441   445.5
    3470   446.5    3470   447.5    3485     449    3497     452    3497   456.5
    3552   456.2    3605   456.8    3900   454.8    3900     470    5300     470
#Mann= 3 ,0,0
    1900     .14       0    3250     .05       0    3497     .07       0
#XS Ineff= 2 , 0
       0    3250     450               0
Permanent Ineff=
       F       F
Bank Sta=3250,3497
XS Rating Curve= 0 ,0
Exp/Cntr=0.5,0.3

Type RM Length L Ch R = 1 ,78060   ,0,0,0
BEGIN DESCRIPTION:
This cross section corresponds to cross section 78083 of the non-georeferenced CDC model which was the source of this model.
Cont/Exp raised due to railroad.  LOB lowered 2' below railroad.  Right flow limit adjusted due to SH 360 and flow over railroad.  'n' value lowered in ROB  to be consistent.
END DESCRIPTION:
XS GIS Cut Line= 6
  2413937.828791 6982624.6001787 2413892.0889177 6982182.7328981
 2413837.2038568 6981955.8740998 2413398.1230421 6980642.2901128
 2413376.8800154  6980114.603588  2413416.718014 6979433.0853638
#Sta/Elev= 30
    1650     467    1920   461.7    1920   444.2    1979   445.7    2006   447.6
    2029     446    2052   445.8    2066   446.9    2140   446.2    2140   458.4
    2900     455    2900   448.7    3023   450.7    3039   429.4    3049     424
    3058   420.9    3070   418.8    3102     419    3119   422.5    3144     424
    3169   429.3    3202     446    3232   451.6    3255   454.5    3277   458.3
    3306   457.9    3323     455    3730   451.6    3730     470    4930     470
#Mann= 3 ,0,0
    1650     .14       0    3023     .05       0    3255     .07       0
#XS Ineff= 3 ,-1
    3691    4930     470    3255    3691   454.5    1650    3023     450
Permanent Ineff=
       F       F       F
Bank Sta=3023,3255
XS Rating Curve= 0 ,0
Exp/Cntr=0.5,0.3

River Reach=West Fork       ,wf3c
Reach XY= 20
      2410893.83      6980300.642411009.799980066980199.28184701
2411064.54082648 6980106.22240812411097.385334336980078.85198489
2411130.229842186980024.111138472411163.074350036979980.31846134
2411201.392942526979925.577614922411272.556042866979821.57000673
2411442.252666766979597.132536422411562.682528876979449.33225109
2411810.844781246979259.772956742412158.459847696979136.65928738
2412520.558875246979172.869190132412839.206019496979223.56305399
2413462.01634688 6979281.49889842413681.153285226979460.28042037
2413911.064840186979854.414514582414020.546533016980401.82297875
2414451.630698556981107.979897532414587.114293436981711.49772928

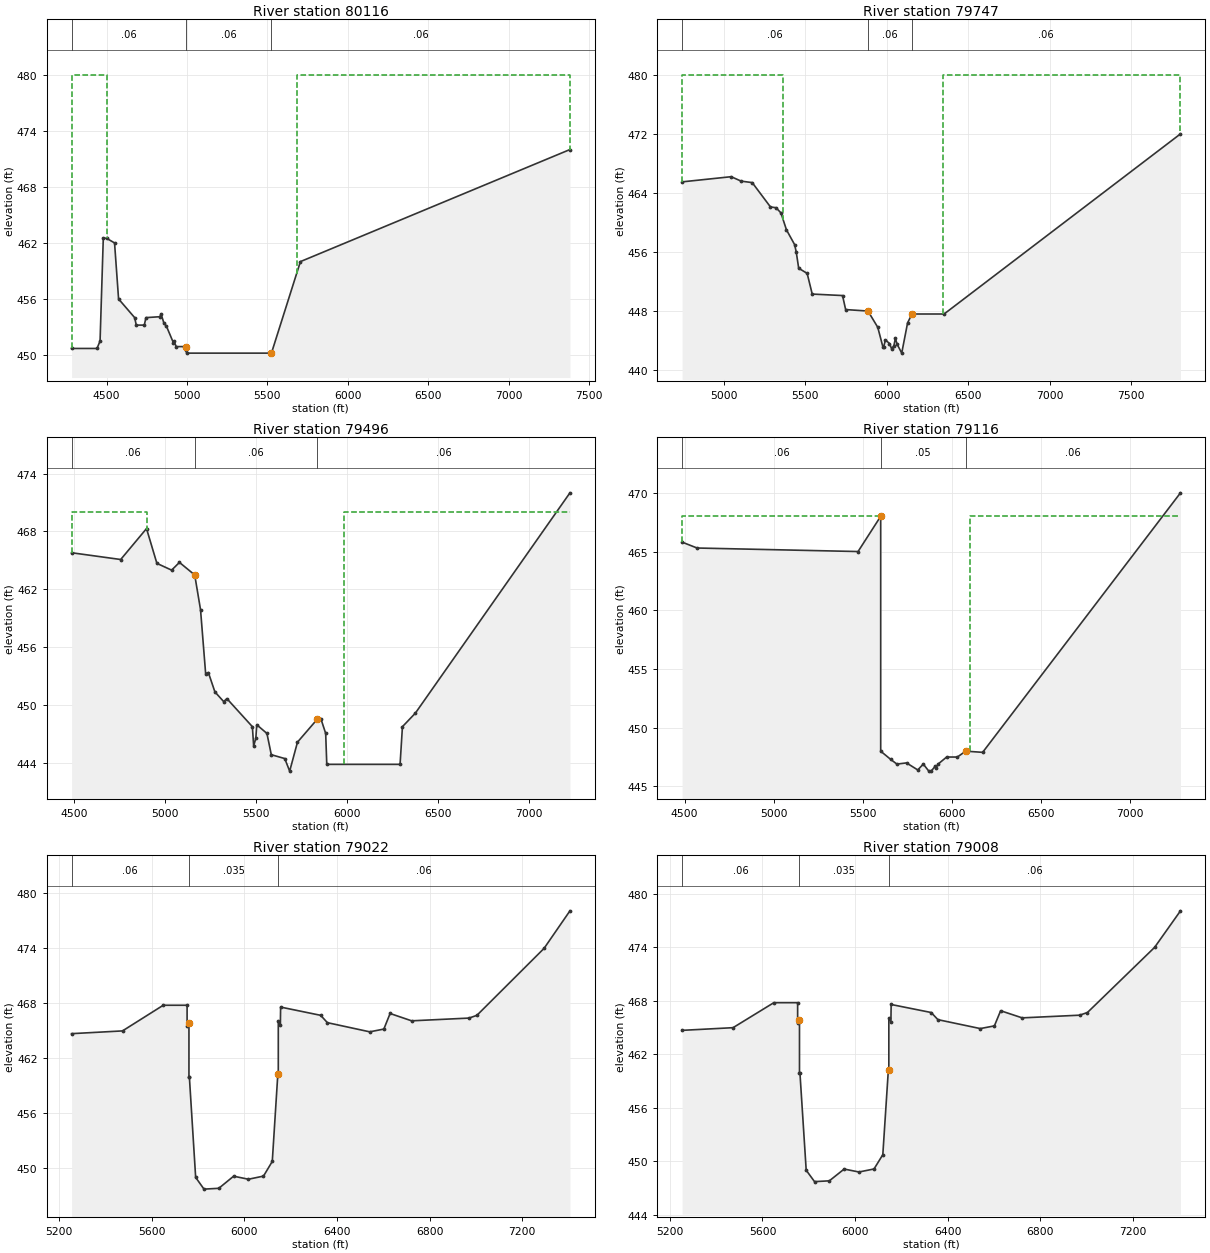
Type RM Length L Ch R = 1 ,80116   ,359,369,252
BEGIN DESCRIPTION:
This cross section corresponds to cross section 84549 of the non-georeferenced CDC model which was the source of this model.
High ground added from 1991 topo map (4500-4800).  Far ROB is a projection of Riverside Dr.  Section realigned to be perpindicular to flow, effectively moving left flow limit.  Boyd Branch channel added.
END DESCRIPTION:
XS GIS Cut Line= 3
       2411264.8      6980319.332411827.802612026979013.53060543
 2412490.97376196977475.40543953
#Sta/Elev= 24
    4283   450.7    4441   450.7    4460   451.5    4480   462.5    4500   462.5
    4550     462    4575     456    4675     454    4685   453.2    4735   453.2
    4745     454    4832   454.1    4839   454.4    4857   453.4    4872   453.1
    4916   451.3    4919   451.5    4933   450.9    4992   450.9    4996   450.5
    4998   450.2    5525   450.2    5705     460    7380     472
#Mann= 3 ,0,0
    4283     .06       0    4992     .06       0    5525     .06       0
#XS Ineff= 2 , 0
       0    4500     480    5681       0     480
Permanent Ineff=
       T       T
Bank Sta=4992,5525
XS Rating Curve= 0 ,0
Exp/Cntr=0.3,0.1

Type RM Length L Ch R = 1 ,79747   ,348,251,187
BEGIN DESCRIPTION:
This cross section corresponds to cross section 83837 of the non-georeferenced CDC model which was the source of this model.
High ground near station 5000 added from storage model.  ROB flow limit moved to match effective hydraulic map.  Cont/Exp raised due to influences from SH 360.
END DESCRIPTION:
XS GIS Cut Line= 6
 2411646.8945143 6980470.9838194  2411740.866186 6980157.1598495
 2411878.9489151 6979696.0360998 2412017.4013941 6979123.5083735
      2412050.86      6978917.18     2412507.066     6977539.208
#Sta/Elev= 30
    4745   465.5    5046   466.2    5107   465.6    5175   465.4    5287   462.1
    5321     462    5351   461.3    5385     459    5435     457    5445     456
    5460   453.8    5512   453.1    5543   450.3    5729   450.1    5748   448.2
    5885     448    5945   445.8    5977   443.1    5981   443.1    5992   444.1
    6017   443.6    6030   442.9    6044   443.3    6053   444.3    6064   443.5
    6092   442.3    6128   446.4    6155   447.6    6352   447.6    7802     472
#Mann= 3 ,0,0
    4745     .06       0    5885     .06       0    6155     .06       0
#XS Ineff= 2 , 0
       0    5365     480    6348       0     480
Permanent Ineff=
       T       T
Bank Sta=5885,6155
XS Rating Curve= 0 ,0
Exp/Cntr=0.3,0.1

Type RM Length L Ch R = 1 ,79496   ,400,380,365
BEGIN DESCRIPTION:
This cross section corresponds to cross section 82019 of the non-georeferenced CDC model which was the source of this model.
Data added to relief from CORPS data.  ROB flow limit added to match effective hydraulic map.  Cont/Exp raised due to influences from SH 360 and fill.
END DESCRIPTION:
XS GIS Cut Line= 6
 2412086.4429227 6980252.7715349 2412133.1964381 6980063.2991448
 2412203.3278595 6979779.0910518 2412239.6542304 6979181.6703306
 2412288.4289207  6978379.5646392412543.199527736977568.64421268
#Sta/Elev= 30
    4486   465.8    4756   465.1    4898   468.3    4955   464.7    5036     464
    5079   464.8    5163   463.5    5195   459.9    5223   453.3    5238   453.4
    5274   451.4    5322   450.4    5340   450.7    5480   447.8    5487   445.8
    5499   446.6    5504     448    5560   447.1    5584   444.9    5658   444.5
    5685   443.2    5728   446.2    5838   448.6    5857   448.6    5883   447.1
    5889   443.9    6292   443.9    6305   447.8    6376   449.2    7226     472
#Mann= 3 ,0,0
    4486     .06       0    5163     .06       0    5838     .06       0
#XS Ineff= 2 , 0
       0    4900     470    5985       0     470
Permanent Ineff=
       T       T
Bank Sta=5163,5838
XS Rating Curve= 0 ,0
Exp/Cntr=0.3,0.1

Type RM Length L Ch R = 1 ,79116   ,93,93,93
BEGIN DESCRIPTION:
This cross section corresponds to cross section 81131 of the non-georeferenced CDC model which was the source of this model.
Data added to relief from CORPS data.  Cont/Exp raised due to influences from SH 360.  'n' value lowered to reflect irregular pavement section and short vegetation.
---------------------------------------------------------------------
CDC ARL062007-1 Viridian Project
Cross-section 81131 - 109405
Located in LOB.
----------------------------------------------------------------
END DESCRIPTION:
XS GIS Cut Line= 6
2412398.619294976980612.95437977 2412527.5119224 6980100.0031396
 2412590.1699336 6979700.2910126  2412618.258132  6979367.557098
      2412621.75      6978774.16       2412578.6      6977840.07
#Sta/Elev= 20
    4486   465.8    4570   465.3    5473     465    5600     468    5600     448
    5656   447.3    5691   446.9    5745     447    5808   446.4    5839   446.9
    5870   446.3    5883   446.3    5905   446.7    5911   446.6    5922   446.9
    5970   447.5    6030   447.5    6077     448    6172   447.9    7282     470
#Mann= 3 ,0,0
    4486     .06       0    5600     .05       0    6077     .06       0
#XS Ineff= 2 , 0
       0    5600     468    6100       0     468
Permanent Ineff=
       T       T
Bank Sta=5600,6077
XS Rating Curve= 0 ,0
Exp/Cntr=0.5,0.3

Type RM Length L Ch R = 1 ,79022   ,14,14,14
BEGIN DESCRIPTION:
This cross section corresponds to cross section 81006 of the non-georeferenced CDC model which was the source of this model.
'n' value lowered to reflect normal high grass and regular pavement section.  Relief bridge surveyed 10-06.
END DESCRIPTION:
XS GIS Cut Line= 6
       2412644.4      6979914.21     2412708.227     6979450.879
     2412714.873     6978965.676     2412661.701     6978254.488
 2412643.5823659 6978012.14700922412625.401314386977768.97117072
#Sta/Elev= 30
    5253   464.7    5473     465    5649   467.8    5752   467.8    5752  465.51
    5760  465.88    5760  459.92    5762  459.92    5789  449.02    5825  447.74
    5889  447.83    5953  449.15    6017  448.82    6082  449.16    6120  450.76
    6144  460.29    6146  460.29    6146  466.04    6155  465.69    6156   467.6
    6329   466.7    6358   465.9    6541   464.9    6602   465.2    6629   466.9
    6722   466.1    6970   466.4    7004   466.7    7294     474    7406   478.1
#Mann= 3 ,0,0
    5253     .06       0    5760    .035       0    6146     .06       0
Bank Sta=5760,6146
XS Rating Curve= 0 ,0
Exp/Cntr=0.5,0.3

Type RM Length L Ch R = 1 ,79008   ,111,111,111
BEGIN DESCRIPTION:
This cross section corresponds to cross section 81005 of the non-georeferenced CDC model which was the source of this model.
'n' value lowered to reflect normal high grass and regular pavement section.  Relief bridge surveyed 10-06.
END DESCRIPTION:
XS GIS Cut Line= 6
      2412654.95      6979916.92      2412717.47      6979461.45
      2412730.71      6979057.63      2412674.45      6978256.62
 2412659.9244304 6978049.81007242412640.382298656977771.57610539
#Sta/Elev= 30
    5253   464.7    5473     465    5649   467.8    5752   467.8    5752  465.51
    5760  465.88    5760  459.92    5762  459.92    5789  449.02    5825  447.74
    5889  447.83    5953  449.15    6017  448.82    6082  449.16    6120  450.76
    6144  460.29    6146  460.29    6146  466.04    6155  465.69    6156   467.6
    6329   466.7    6358   465.9    6541   464.9    6602   465.2    6629   466.9
    6722   466.1    6970   466.4    7004   466.7    7294     474    7406   478.1
#Mann= 3 ,0,0
    5253     .06       0    5760    .035       0    6146     .06       0
#Block Obstruct= 1 ,-1
  5822.5    6099   446.9
Bank Sta=5760,6146
XS Rating Curve= 0 ,0
Exp/Cntr=0.5,0.3

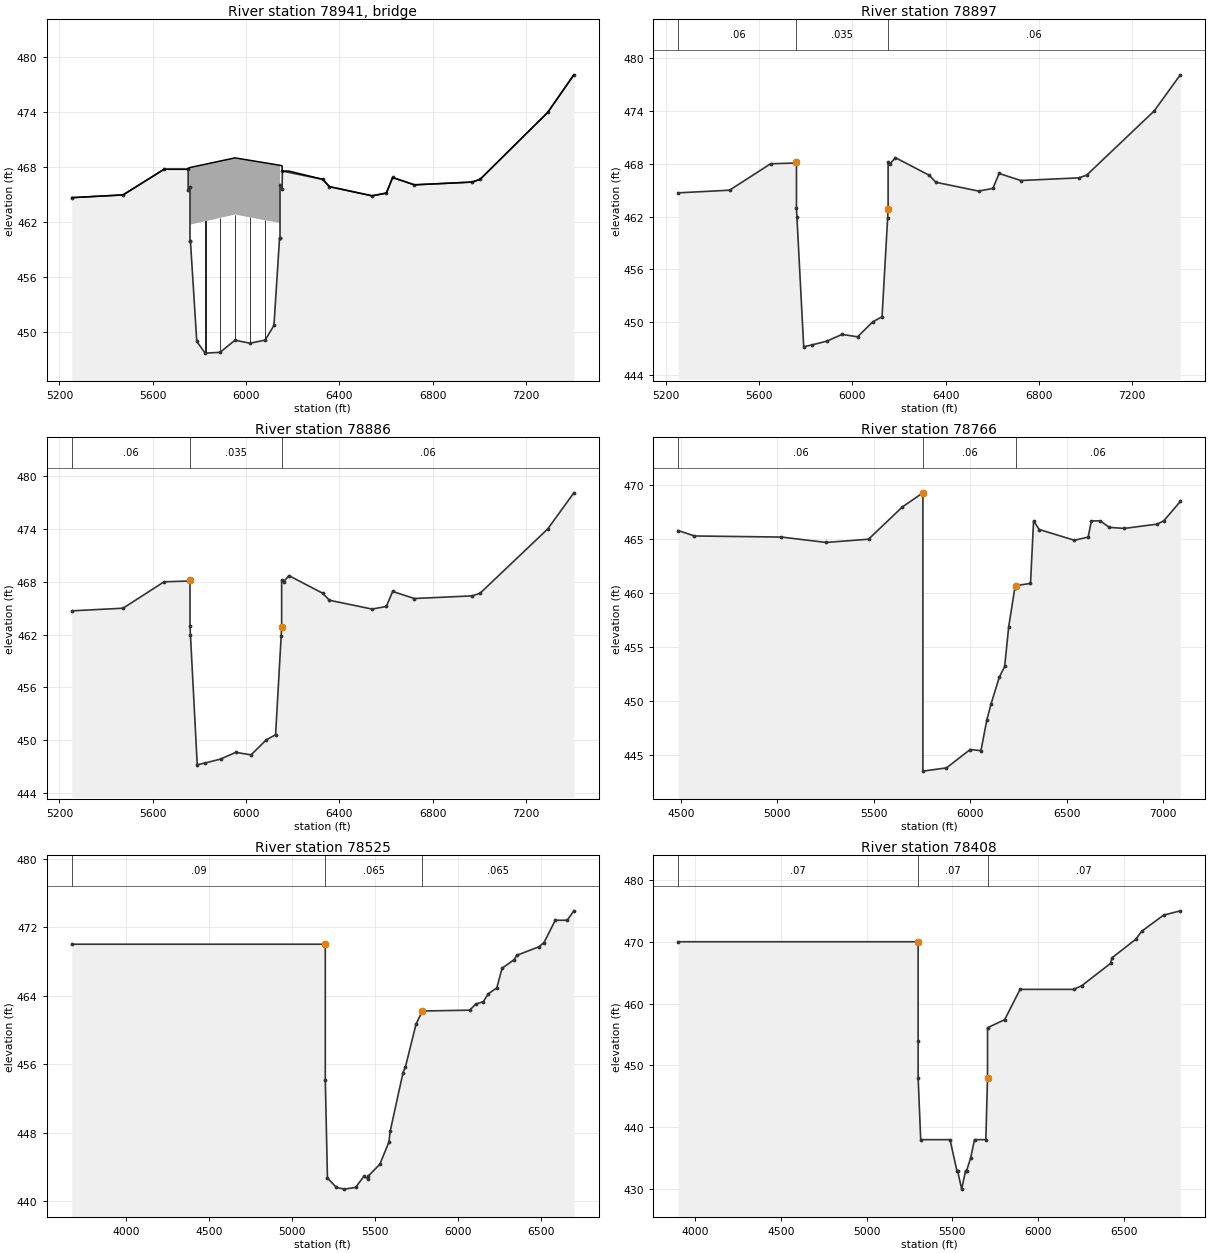
Type RM Length L Ch R = 3 ,78941   ,,,
BEGIN DESCRIPTION:
SH 360
Bridge superelevated.  D/S sided higher.  Relief bridge surveyed 10-06.
END DESCRIPTION:
Node Name=SH 360 Relief
Bridge Culvert--1,0,-1,-1, 0
Deck Dist Width WeirC Skew NumUp NumDn MinLoCord MaxHiCord MaxSubmerge Is_Ogee
1,88,2.6,0, 21, 21, , , 0.95, 0, ,,,
    5253    5473    5649    5752    5752    5760    5953    6146    6155    6155
    6184    6329    6358    6541    6602    6629    6722    6970    7004    7294
    7406
   464.7     465   467.8   467.8  467.89  467.99  469.04  468.23  468.17   467.6
   467.6   466.7   465.9   464.9   465.2   466.9   466.1   466.4   466.7     474
   478.1
                                          461.75  462.86  461.93
    5253    5473    5649    5751    5751    5760    5956    6153    6161    6161
    6184    6329    6358    6541    6602    6629    6722    6970    7004    7294
    7406
   464.7     465     468   468.9  470.78  470.89  472.11  470.89  470.79     469
   468.7   466.7   465.9   464.9   465.2   466.9   466.1   466.4   466.7     474
   478.1
                                          464.04  465.24  464.06
Pier Skew, UpSta & Num, DnSta & Num=  ,5825, 2 ,5825, 2 , 0 , 0 , 0 ,,
       3       3
     420     467
       3       3
     420     467
Pier Skew, UpSta & Num, DnSta & Num=  ,5889, 2 ,5891, 2 , 0 , 0 , 0 ,,
       3       3
     420     467
       3       3
     420     467
Pier Skew, UpSta & Num, DnSta & Num=  ,5953, 2 ,5956, 2 , 0 , 0 , 0 ,,
       3       3
     420     467
       3       3
     420     467
Pier Skew, UpSta & Num, DnSta & Num=  ,6017, 2 ,6022, 2 , 0 , 0 , 0 ,,
       3       3
     420     467
       3       3
     420     467
Pier Skew, UpSta & Num, DnSta & Num=  ,6082, 2 ,6087, 2 , 0 , 0 , 0 ,,
       3       3
     420     467
       3       3
     420     467
BR Coef= 1 , 0 , 0 ,1.05, 0 ,,,0.8,-1,1.2,1,
WSPro=,,,, 1 ,,,, 0 ,,,, 0 ,,,,-1 ,-1 ,-1 , 0 , 0 , 0 , 0 , 0
BC Design=,, 0 ,, 0 ,,,,,,
BC HTab HWMax=478.1
BC Use User HTab Curves=0
BC User HTab FreeFlow(D)= 0

Type RM Length L Ch R = 1 ,78897   ,11,11,11
BEGIN DESCRIPTION:
This cross section corresponds to cross section 80915 of the non-georeferenced CDC model which was the source of this model.
'n' value lowered to reflect normal high grass and regular pavement section.  Relief bridge surveyed 10-06.
END DESCRIPTION:
XS GIS Cut Line= 6
      2412758.07      6979923.71      2412827.27      6979490.87
      2412843.25      6978974.88      2412815.04      6978260.59
 2412806.9977956 6978056.95773662412795.956521646977777.38767166
#Sta/Elev= 29
    5253   464.7    5473     465    5649     468    5751  468.08    5760  468.19
    5760  462.97    5762  461.93    5791  447.23    5825  447.42    5891  447.87
    5956  448.63    6022  448.35    6087  450.05    6127  450.63    6151  461.85
    6153  462.81    6153  468.15    6161  467.98    6184   468.7    6329   466.7
    6358   465.9    6541   464.9    6602   465.2    6629   466.9    6722   466.1
    6970   466.4    7004   466.7    7294     474    7406   478.1
#Mann= 3 ,0,0
    5253     .06       0    5760    .035       0    6153     .06       0
#Block Obstruct= 1 ,-1
  5822.5    6099   446.5
Bank Sta=5760,6153
XS Rating Curve= 0 ,0
Exp/Cntr=0.5,0.3

Type RM Length L Ch R = 1 ,78886   ,120,120,120
BEGIN DESCRIPTION:
This cross section corresponds to cross section 80914 of the non-georeferenced CDC model which was the source of this model.
'n' value lowered to reflect normal high grass and regular pavement section.  Relief bridge surveyed 10-06.
END DESCRIPTION:
XS GIS Cut Line= 6
       2412763.5      6979923.71      2412834.06      6979488.16
      2412856.49      6978994.74      2412820.08      6978256.62
  2412809.851402 6978049.2612306      2412802.31      6977780.27
#Sta/Elev= 29
    5253   464.7    5473     465    5649     468    5751  468.08    5760  468.19
    5760  462.97    5762  461.93    5791  447.23    5825  447.42    5891  447.87
    5956  448.63    6022  448.35    6087  450.05    6127  450.63    6151  461.85
    6153  462.81    6153  468.15    6161  467.98    6184   468.7    6329   466.7
    6358   465.9    6541   464.9    6602   465.2    6629   466.9    6722   466.1
    6970   466.4    7004   466.7    7294     474    7406   478.1
#Mann= 3 ,0,0
    5253     .06       0    5760    .035       0    6153     .06       0
#Block Obstruct= 2 ,-1
                            5700    6200   446.5
Bank Sta=5760,6153
XS Rating Curve= 0 ,0
Exp/Cntr=0.5,0.3

Type RM Length L Ch R = 1 ,78766   ,294,241,253
BEGIN DESCRIPTION:
This cross section corresponds to cross section 80817 of the non-georeferenced CDC model which was the source of this model.
Data added to relief from CORPS data.  'n' value lowered in ROB  to be consistent.
END DESCRIPTION:
XS GIS Cut Line= 6
2412722.729137936980609.89264244  2412765.179098 6980460.8249246
 2412827.8371092 6980188.5879362 2412892.6548929 6979797.5178522
 2412969.4158942 6979204.0249447      2412963.34      6978029.25
#Sta/Elev= 30
    4486   465.8    4570   465.3    5021   465.2    5253   464.7    5473     465
    5649     468    5755   469.3    5755   443.5    5877   443.8    6000   445.5
    6056   445.4    6086   448.2    6108   449.7    6151   452.2    6179   453.2
    6200   456.9    6232   460.5    6237   460.7    6313   460.9    6329   466.7
    6358   465.9    6541   464.9    6612   465.2    6629   466.7    6674   466.7
    6722   466.1    6799     466    6970   466.4    7004   466.7    7090   468.5
#Mann= 3 ,0,0
    4486     .06       0    5755     .06       0    6237     .06       0
#Block Obstruct= 2 , 0
       0    5755            6245       0
Bank Sta=5755,6237
XS Rating Curve= 0 ,0
Exp/Cntr=0.5,0.3

Type RM Length L Ch R = 1 ,78525   ,116,116,116
BEGIN DESCRIPTION:
This cross section corresponds to cross section 78300 of the non-georeferenced CDC model which was the source of this model.
'n' value changed in ROB  to transition from RR to 360 'n' value.
END DESCRIPTION:
XS GIS Cut Line= 6
 2413388.9547187 6981288.8327938 2413211.5141633 6980832.5590892
    2413171.2649 6980605.6999629 2413156.6291025 6980386.1600477
 2413167.6061147 6980115.39287272413248.394251466978298.16845541
#Sta/Elev= 30
    3670     470    5200     470    5200   454.2    5213   442.7    5267   441.6
    5315   441.4    5383   441.6    5433   442.9    5457   442.6    5458   442.9
    5529   444.3    5584   446.9    5592   448.2    5669     455    5684   455.7
    5748   460.7    5786   462.2    6071   462.3    6108     463    6154   463.3
    6183   464.2    6235   464.9    6267   467.2    6340   468.2    6355   468.7
    6489   469.7    6520   470.2    6588   472.8    6660   472.8    6700   473.9
#Mann= 3 ,0,0
    3670     .09       0    5200    .065       0    5786    .065       0
#Block Obstruct= 2 , 0
       0    5200                       0
Bank Sta=5200,5786
XS Rating Curve= 0 ,0
Exp/Cntr=0.5,0.3

Type RM Length L Ch R = 1 ,78408   ,2,2,2
BEGIN DESCRIPTION:
This cross section corresponds to cross section 78197 of the non-georeferenced CDC model which was the source of this model.
High ground from u/s added to ROB.  'n' value raised in ROB  to be consistent.
END DESCRIPTION:
XS GIS Cut Line= 6
2413466.628258756981200.64056297 2413346.8859398 6980892.4546387
 2413295.1006103 6980685.3123365 2413272.9149592 6980463.4548406
 2413318.8902609 6979349.8438788      2413355.15      6978302.17
#Sta/Elev= 26
    3900     470    5300     470    5300   453.9    5300     448    5315     438
    5486     438    5526     433    5530     433    5554     430    5577     433
    5583     433    5606     435    5629     438    5695     438    5705     448
    5705   456.1    5805   457.4    5895   462.3    6208   462.3    6255   462.9
    6423   466.5    6431   467.4    6570   470.4    6605   471.7    6732   474.3
    6830     475
#Mann= 3 ,0,0
    3900     .07       0    5300     .07       0    5705     .07       0
#Block Obstruct= 2 , 0
       0    5300                       0
Bank Sta=5300,5705
XS Rating Curve= 0 ,0
Exp/Cntr=0.5,0.3

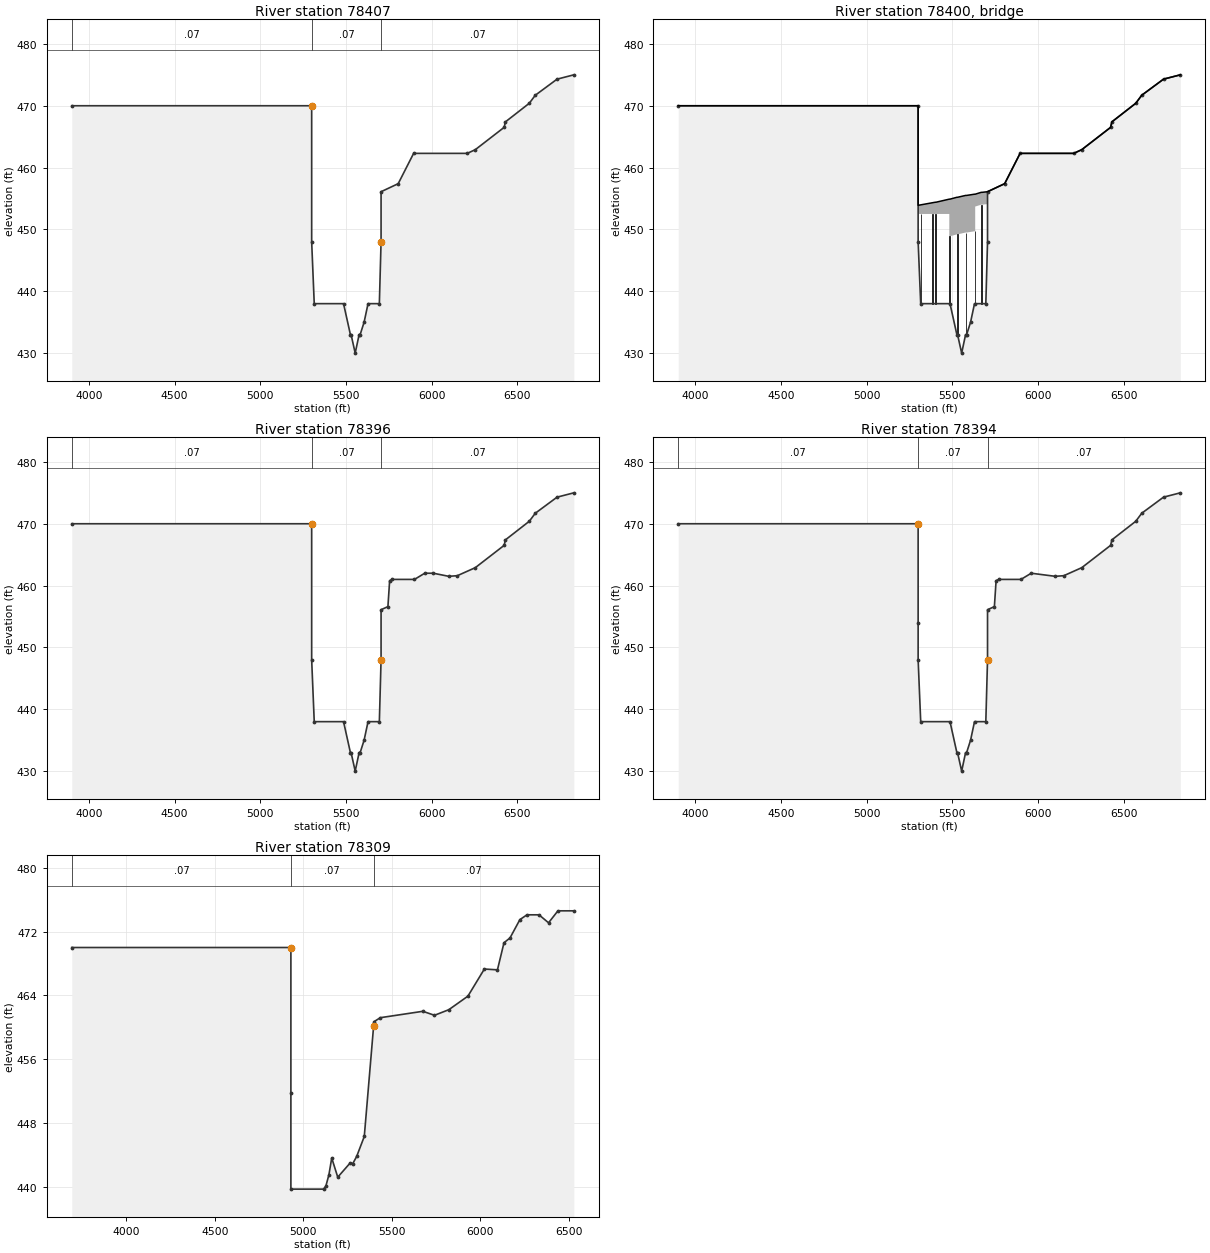
Type RM Length L Ch R = 1 ,78407   ,10,10,10
BEGIN DESCRIPTION:
This cross section corresponds to cross section 78196 of the non-georeferenced CDC model which was the source of this model.
High ground from u/s added to ROB.  'n' value raised in ROB  to be consistent.
END DESCRIPTION:
XS GIS Cut Line= 6
2413466.43976223 6981197.4878061 2413347.9069352 6980892.4146126
 2413296.1872223 6980685.5354331 2413274.0288021 6980463.9505745
 2413281.3778687 6980206.7335692      2413364.38      6978299.09
#Sta/Elev= 25
    3900     470    5300     470    5300     448    5315     438    5486     438
    5526     433    5530     433    5554     430    5577     433    5583     433
    5606     435    5629     438    5695     438    5705     448    5705   456.1
    5805   457.4    5895   462.3    6208   462.3    6255   462.9    6423   466.5
    6431   467.4    6570   470.4    6605   471.7    6732   474.3    6830     475
#Mann= 3 ,0,0
    3900     .07       0    5300     .07       0    5705     .07       0
#Block Obstruct= 2 , 0
       0    5300                       0
Bank Sta=5300,5705
XS Rating Curve= 0 ,0
Exp/Cntr=0.5,0.3

Type RM Length L Ch R = 3 ,78400   ,,,
BEGIN DESCRIPTION:
Union Pacific Railroad
END DESCRIPTION:
Node Name=Union Pacific Ra
Bridge Culvert--1,0,-1,-1, 0
Deck Dist Width WeirC Skew NumUp NumDn MinLoCord MaxHiCord MaxSubmerge Is_Ogee
1,8,2.6,0, 30, 35, , , 0.95, 0, ,,,
    3900    5300    5300    5300    5400    5404    5482    5482    5486    5526
    5530    5577    5583    5629    5633    5633    5668    5673    5705    5705
    5805    5895    6208    6255    6423    6431    6570    6605    6732    6830
     470     470   453.9   453.9   454.4   454.4   454.9   454.9   454.9   455.2
   455.2   455.5   455.5   455.7   455.7   455.7     456     456   456.1   456.1
   457.4   462.3   462.3   462.9   466.5   467.4   470.4   471.7   474.3     475
                           452.5   452.5   452.5   452.5   448.9   448.9   449.2
   449.2   449.5   449.5   449.7   449.7   453.7     454     454   454.1
    3900    5300    5300    5300    5400    5404    5482    5482    5486    5526
    5530    5577    5583    5629    5633    5633    5668    5673    5705    5705
    5745    5755    5770    5900    5960    6010    6100    6150    6255    6423
    6431    6570    6605    6732    6830
     470     470   453.9   453.9   454.4   454.4   454.9   454.9   454.9   455.2
   455.2   455.5   455.5   455.7   455.7   455.7     456     456   456.1   456.1
   456.6   460.8     461     461     462     462   461.5   461.6   462.9   466.5
   467.4   470.4   471.7   474.3     475
                           452.5   452.5   452.5   452.5   448.9   448.9   449.2
   449.2   449.5   449.5   449.7   449.7   453.7     454     454   454.1
Pier Skew, UpSta & Num, DnSta & Num=  ,5317, 2 ,5317, 2 , 0 , 0 , 0 ,,
       4       4
     430     453
       4       4
     430     453
Pier Skew, UpSta & Num, DnSta & Num=  ,5382, 2 ,5382, 2 , 0 , 0 , 0 ,,
       4       4
     430     453
       4       4
     430     453
Pier Skew, UpSta & Num, DnSta & Num=  ,5402, 2 ,5402, 2 , 0 , 0 , 0 ,,
       4       4
     430     453
       4       4
     430     453
Pier Skew, UpSta & Num, DnSta & Num=  ,5484, 2 ,5484, 2 , 0 , 0 , 0 ,,
       4       4
     430     453
       4       4
     430     453
Pier Skew, UpSta & Num, DnSta & Num=  ,5528, 2 ,5528, 2 , 0 , 0 , 0 ,,
       4       4
     430     453
       4       4
     430     453
Pier Skew, UpSta & Num, DnSta & Num=  ,5579, 2 ,5579, 2 , 0 , 0 , 0 ,,
       4       4
     430     453
       4       4
     430     453
Pier Skew, UpSta & Num, DnSta & Num=  ,5631, 2 ,5631, 2 , 0 , 0 , 0 ,,
       4       4
     430     453
       4       4
     430     453
Pier Skew, UpSta & Num, DnSta & Num=  ,5670.5, 2 ,5670.5, 2 , 0 , 0 , 0 ,,
       4       4
     430     455
       4       4
     430     455
BR Coef= 1 , 0 , 0 ,1.05, 0 ,,,0.8,-1,0.5,1,
WSPro=,,,, 1 ,,,, 0 ,,,, 0 ,,,,-1 ,-1 ,-1 , 0 , 0 , 0 , 0 , 0
BC Design=,, 0 ,, 0 ,,,,,,
BC HTab HWMax=475
BC Use User HTab Curves=0
BC User HTab FreeFlow(D)= 0

Type RM Length L Ch R = 1 ,78396   ,2,2,2
BEGIN DESCRIPTION:
This cross section corresponds to cross section 78186 of the non-georeferenced CDC model which was the source of this model.
High ground from d/s added to ROB.  'n' value raised in ROB  to be consistent.
END DESCRIPTION:
XS GIS Cut Line= 6
2413470.972939996981181.45964027  2413357.303898 6980888.9047771
  2413305.748883 6980682.6840609  2413283.658376 6980461.7806313
 2413329.7104493 6979346.6647513      2413387.49      6978282.76
#Sta/Elev= 30
    3900     470    5300     470    5300     448    5315     438    5486     438
    5526     433    5530     433    5554     430    5577     433    5583     433
    5606     435    5629     438    5695     438    5705     448    5705   456.1
    5745   456.6    5755   460.8    5770     461    5900     461    5960     462
    6010     462    6100   461.5    6150   461.6    6255   462.9    6423   466.5
    6431   467.4    6570   470.4    6605   471.7    6732   474.3    6830     475
#Mann= 3 ,0,0
    3900     .07       0    5300     .07       0    5705     .07       0
#Block Obstruct= 2 , 0
       0    5300                       0
Bank Sta=5300,5705
XS Rating Curve= 0 ,0
Exp/Cntr=0.5,0.3

Type RM Length L Ch R = 1 ,78394   ,85,85,85
BEGIN DESCRIPTION:
This cross section corresponds to cross section 78185 of the non-georeferenced CDC model which was the source of this model.
Cont/Exp raised due to railroad.   GR point 5300, 448.0 missing but found in SPF model.  High ground from d/s added to ROB.
END DESCRIPTION:
XS GIS Cut Line= 6
2413471.973174376981181.07579034 2413358.9843408 6980890.2719003
 2413307.7583934 6980685.3671264  2413285.804369 6980465.8268831
   2413331.93551 6979349.2175677      2413390.29      6978282.23
#Sta/Elev= 30
    3900     470    5300     470    5300   453.9    5300     448    5315     438
    5486     438    5526     433    5530     433    5554     430    5577     433
    5583     433    5606     435    5629     438    5695     438    5705     448
    5705   456.1    5745   456.6    5755   460.8    5770     461    5900     461
    5960     462    6100   461.5    6150   461.6    6255   462.9    6423   466.5
    6431   467.4    6570   470.4    6605   471.7    6732   474.3    6830     475
#Mann= 3 ,0,0
    3900     .07       0    5300     .07       0    5705     .07       0
#Block Obstruct= 2 , 0
       0    5300                       0
Bank Sta=5300,5705
XS Rating Curve= 0 ,0
Exp/Cntr=0.5,0.3

Type RM Length L Ch R = 1 ,78309   ,0,0,0
BEGIN DESCRIPTION:
This cross section corresponds to cross section 78084 of the non-georeferenced CDC model which was the source of this model.
Cont/Exp raised due to railroad.  GR point 4930, 439.7 missing but found in original CORPS data.  'n' value lowered in ROB  to be consistent.
END DESCRIPTION:
XS GIS Cut Line= 6
  2413545.007262 6981093.3935413 2413449.3489895 6980847.1948867
 2413398.1230421 6980642.2901128 2413376.1690177 6980422.7498695
 2413376.8800154  6980114.6035882413472.026387846978283.58504234
#Sta/Elev= 30
    3691     470    4930     470    4930   451.7    4930   439.7    5115   439.7
    5128   440.1    5145   441.5    5161   443.6    5195   441.2    5266     443
    5280   442.9    5302   443.8    5345   446.3    5398   460.2    5400   460.7
    5436   461.2    5676     462    5742   461.5    5823   462.2    5931   463.9
    6024   467.3    6098   467.2    6135   470.6    6169   471.2    6225   473.5
    6265   474.1    6333   474.1    6387   473.1    6440   474.6    6530   474.6
#Mann= 3 ,0,0
    3691     .07       0    4930     .07       0    5398     .07       0
#Block Obstruct= 2 , 0
       0    4930                       0
Bank Sta=4930,5398
XS Rating Curve= 0 ,0
Exp/Cntr=0.5,0.3

River Reach=West Fork       ,wf3a
Reach XY= 30
2414587.114293436981711.49772928      2415095.79      6980356.26
      2415348.65      6980040.22      2415560.52      6979971.31
      2416137.64      6980419.88      2416290.72      6980400.93
      2416457.15      6980266.27      2416630.25      6979710.19
      2417677.43       6979538.2      2417910.47      6979207.07
      2418104.96      6978253.96      2417960.81       6976350.3
      2418117.37      6976127.97       2418596.8      6975979.13
       2418715.9       6975355.4      2418593.03      6974602.07
      2418110.59      6974672.59      2417944.69      6974501.13
      2418465.89      6973632.95       2418378.9      6973023.19
      2419471.64      6972844.23      2420968.71      6972861.03
      2422034.45      6972140.98      2422873.92      6972035.06
      2423217.19      6971874.82      2423513.09      6971412.87
      2423626.57      6970950.85      2423606.25      6970475.53
      2423320.83      6969542.83      2423548.65      6969142.43