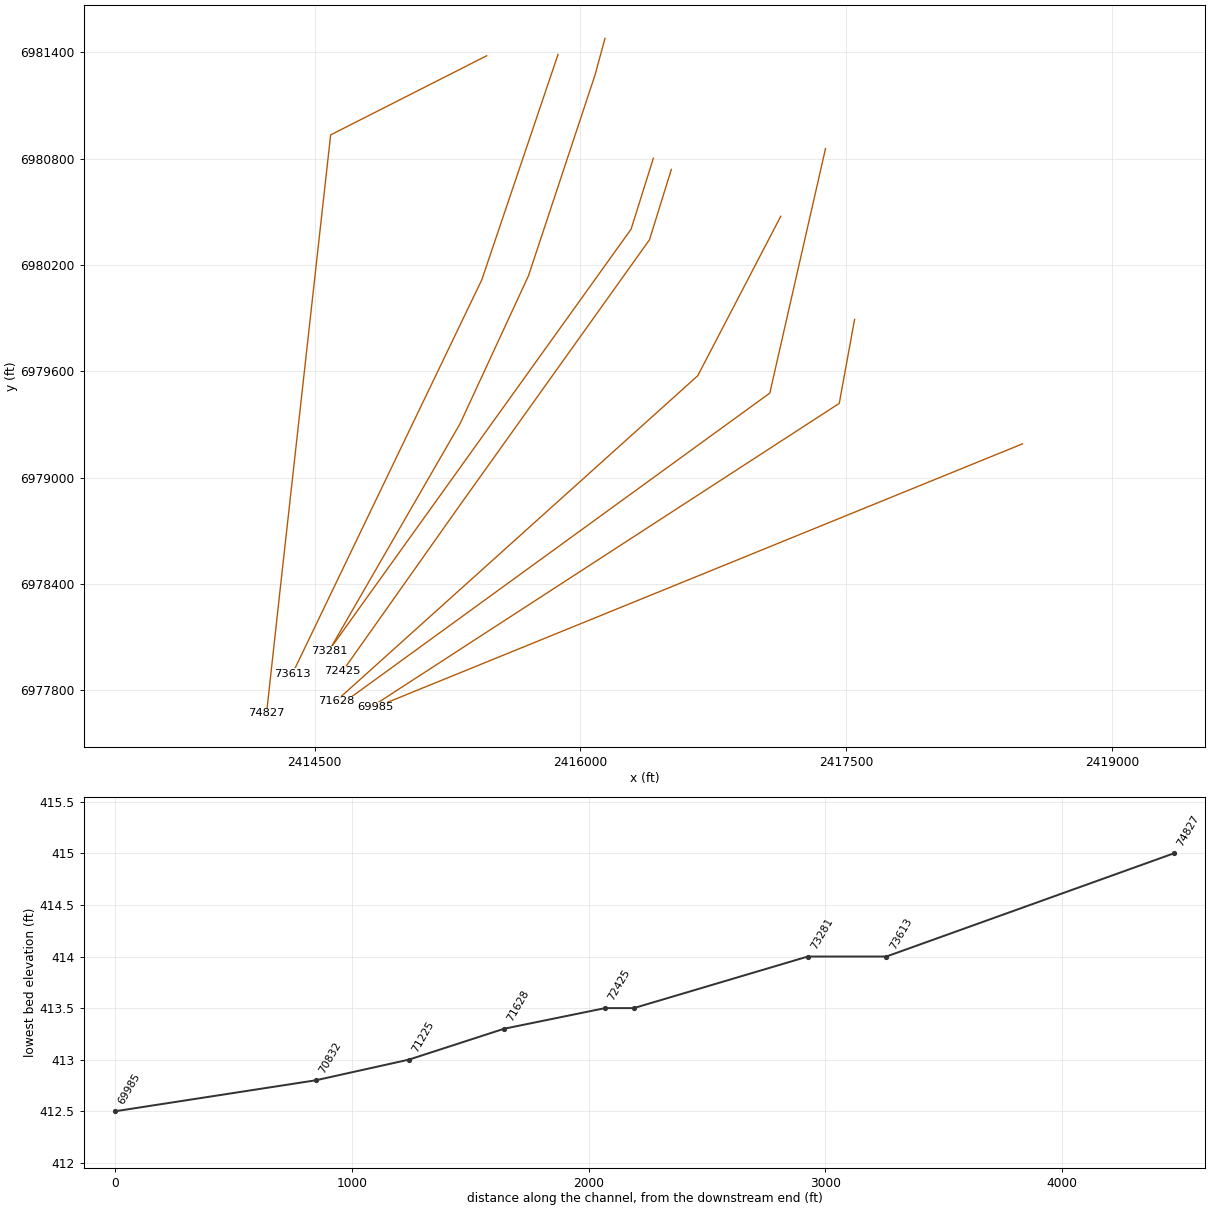
HEC-RAS study CDC_Consolidated_Model.prj: Upper Trinity CDC Consolidated Model

--- CDC_Consolidated_Model.g01 (geometry) --- (continued)

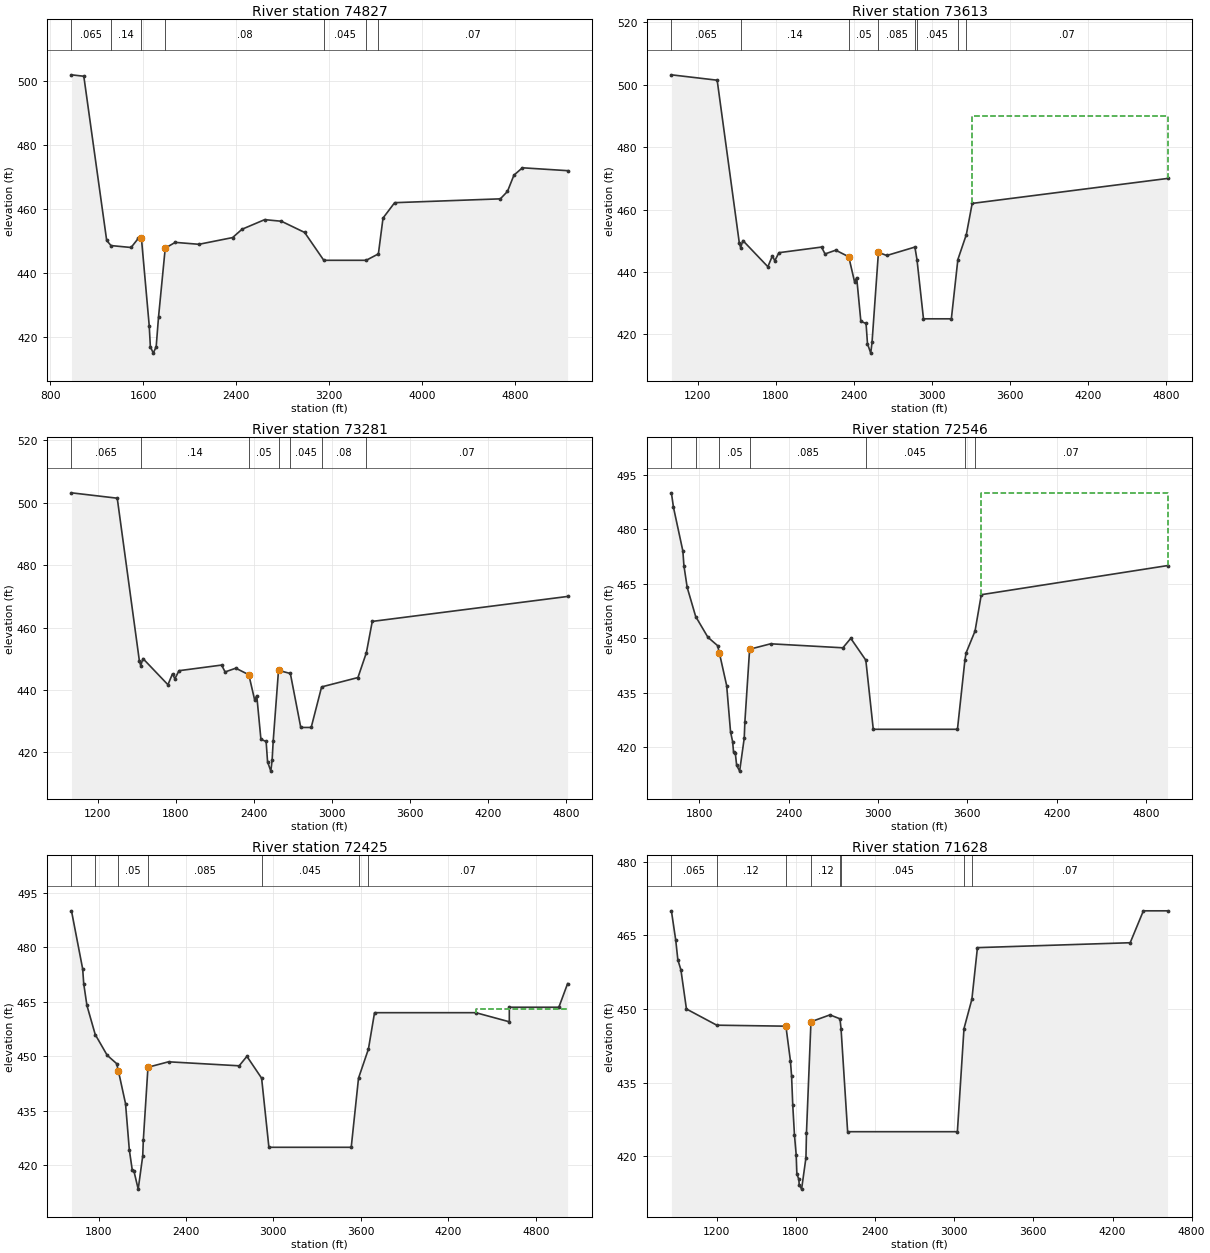
Type RM Length L Ch R = 1 ,74827   ,869,1214,1352
BEGIN DESCRIPTION:
This cross section corresponds to cross section 74891 of the non-georeferenced CDC model which was the source of this model.
END DESCRIPTION:
XS GIS Cut Line= 6
  2415471.004723 6981381.1974277 2414978.3492123 6981131.3980585
 2414590.3768912 6980934.6858535 2414446.0609068 6979635.9505901
 2414301.7314711 6978337.2163109 2414228.4960533 6977670.7035363
#Sta/Elev= 30
 980.741501.94171086.999   501.51283.878450.2066    1321   448.6    1494     448
    1557   450.9    1583   450.9    1650   423.6    1660     417    1685     415
    1710     417    1730   426.2    1788   447.8    1874   449.6    2078     449
    2368   451.1    2449   453.7    2644   456.7    2788   456.2    2988   452.7
    3153     444    3518     444    3623     446    3663   457.2    3763     462
    4673   463.2    4734   465.5    4790   470.6    4863   472.9    5252     472
#Mann= 7 ,-1,0
 980.741    .065       0    1321     .14       0    1583    .055       0
    1788     .08       0    3153    .045       0    3518     .08       0
    3623     .07       0
#XS Ineff= 2 , 0
            1583   450.9    1788           447.8
Permanent Ineff=
       F       F
Bank Sta=1583,1788
XS Rating Curve= 0 ,0
Exp/Cntr=0.3,0.1

Type RM Length L Ch R = 1 ,73613   ,332,332,332
BEGIN DESCRIPTION:
This cross section corresponds to cross section 73634 of the non-georeferenced CDC model which was the source of this model.
END DESCRIPTION:
XS GIS Cut Line= 6
2415873.831364286981388.68945158 2415683.3592852 6980825.8635646
 2415443.5021534 6980117.1418849   2415154.41054 6979516.0082447
 2414906.6088702 6979000.75271352414374.07874039  6977893.522057
#Sta/Elev= 30
  999.19503.22311350.739   501.51520.912 449.257    1531   447.8    1548   450.1
    1740   441.7    1775   445.2    1793   443.6    1825   446.2    2152     448
    2179   445.8    2261     447    2361   444.9    2406   436.8    2422   438.2
    2454   424.2    2494   423.5    2505     417    2530     414    2540   417.5
    2589   446.3    2653   445.3    2869     448    2885     444    2935     425
    3149     425    3199     444    3264     452    3309     462    4809     470
#Mann= 8 ,-1,0
  999.19    .065       0    1531     .14       0    2361     .05       0
    2589    .085       0    2869     .08       0    2885    .045       0
    3199     .08       0    3264     .07       0
#XS Ineff= 4 ,-1
    2589    2869   446.3  999.19    2361   444.9    2869    3199     444
    3309    4809     490
Permanent Ineff=
       F       F       T       F
Bank Sta=2361,2589
XS Rating Curve= 0 ,0
Exp/Cntr=0.3,0.1

Type RM Length L Ch R = 1 ,73281   ,735,735,735
BEGIN DESCRIPTION:
This cross section corresponds to cross section 73460 of the non-georeferenced CDC model which was the source of this model.
Copy of 73634
END DESCRIPTION:
XS GIS Cut Line= 6
2416138.895952446981479.54136839 2416109.5634853  6981371.966475
 2416083.0920816 6981274.3898985 2415706.7854195 6980139.3275361
 2415321.4941953 6979306.59068452414579.87805403  6978021.374127
#Sta/Elev= 30
  999.19503.22311350.739   501.51520.912 449.257    1531   447.8    1548   450.1
    1740   441.7    1775   445.2    1793   443.6    1825   446.2    2152     448
    2179   445.8    2261     447    2361   444.9    2406   436.8    2422   438.2
    2454   424.2    2494   423.5    2505     417    2530     414    2540   417.5
    2548   423.5    2589   446.3    2680   445.3    2760     428    2840     428
    2920     441    3199     444    3264     452    3309     462    4809     470
#Mann= 7 ,-1,0
  999.19    .065       0    1531     .14       0    2361     .05       0
    2589    .085       0    2680    .045       0    2920     .08       0
    3264     .07       0
#XS Ineff= 2 ,-1
    2589    3584     444  999.19    2361   444.9
Permanent Ineff=
       T       F
Bank Sta=2361,2589
XS Rating Curve= 0 ,0
Exp/Cntr=0.3,0.1

Type RM Length L Ch R = 1 ,72546   ,121,121,121
BEGIN DESCRIPTION:
This cross section corresponds to cross section 72628 of the non-georeferenced CDC model which was the source of this model.
Copy of 72500
END DESCRIPTION:
XS GIS Cut Line= 4
  2416411.804022 6980803.2500927 2416286.0418069 6980402.6304871
 2415316.5450583 6979051.0803687  2414587.956632 6978035.3742567
#Sta/Elev= 30
    1614     490    1628     486    1691     474    1698     470    1720     464
    1777     456    1859   450.3    1924     448    1936     446    1985     437
    2011   424.3    2025   421.6    2031   418.8    2043   418.4    2052   415.1
    2072   413.5    2103   422.6    2107   426.9    2139     447    2280   448.5
    2765   447.4    2818     450    2919     444    2969     425    3534     425
    3584     444    3592     446    3652     452    3694     462    4944     470
#Mann= 7 ,-1,0
    1614    .065       0    1777     .12       0    1936     .05       0
    2139    .085       0    2919    .045       0    3584     .08       0
    3652     .07       0
#XS Ineff= 2 ,-1
    2919    3584     444    3694    4944     490
Permanent Ineff=
       T       F
Bank Sta=1936,2139
XS Rating Curve= 0 ,0
Exp/Cntr=0.3,0.1

Type RM Length L Ch R = 1 ,72425   ,363,427,277
BEGIN DESCRIPTION:
This cross section corresponds to cross section 72500 of the non-georeferenced CDC model which was the source of this model.
END DESCRIPTION:
XS GIS Cut Line= 4
  2416513.265761 6980739.9887363 2416390.0452078 6980343.0594121
 2415317.8967616 6978842.4525052 2414656.4571396 6977906.9881687
#Sta/Elev= 30
    1614     490    1691     474    1698     470    1720     464    1777     456
    1859   450.3    1924     448    1936     446    1985     437    2011   424.3
    2031   418.8    2043   418.4    2072   413.5    2103   422.6    2107   426.9
    2139     447    2280   448.5    2765   447.4    2818     450    2919     444
    2969     425    3534     425    3584     444    3652     452    3694     462
    4389     462    4619   459.5    4619   463.5    4959   463.5    5019     470
#Mann= 7 ,-1,0
    1614    .065       0    1777     .12       0    1936     .05       0
    2139    .085       0    2919    .045       0    3584     .08       0
    3652     .07       0
#XS Ineff= 2 ,-1
    2919    3584     444    4389    5019     463
Permanent Ineff=
       T       F
Bank Sta=1936,2139
XS Rating Curve= 0 ,0
Exp/Cntr=0.3,0.1

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
Type RM Length L Ch R = 1 ,71628   ,301,403,284
BEGIN DESCRIPTION:
This cross section corresponds to cross section 71700 of the non-georeferenced CDC model which was the source of this model.
END DESCRIPTION:
XS GIS Cut Line= 4
  2417130.693332 6980475.3380189 2416662.2543091 6979575.7860122
 2415691.3449517 6978702.62307122414619.898482086977739.04460385
#Sta/Elev= 30
     856     470     889     464     905     460     928     458     970     450
    1200   446.7    1724   446.5    1758   439.5    1767   436.4    1776   430.4
    1789   424.3    1802   420.3    1807   416.4    1822   415.3    1825   414.2
    1843   413.3    1876   419.7    1880   424.8    1914   447.4    2058   448.8
    2134     448    2142     446    2192     425    3024     425    3074     446
    3134     452    3176   462.5    4334   463.5    4434     470    4617     470
#Mann= 8 ,-1,0
     856    .065       0    1200     .12       0    1724     .05       0
    1914     .12       0    2134     .08       0    2142    .045       0
    3074     .08       0    3134     .07       0
#XS Ineff= 1 ,-1
    2142    3074     446
Permanent Ineff=
       T
Bank Sta=1724,1914
XS Rating Curve= 0 ,0
Exp/Cntr=0.3,0.1

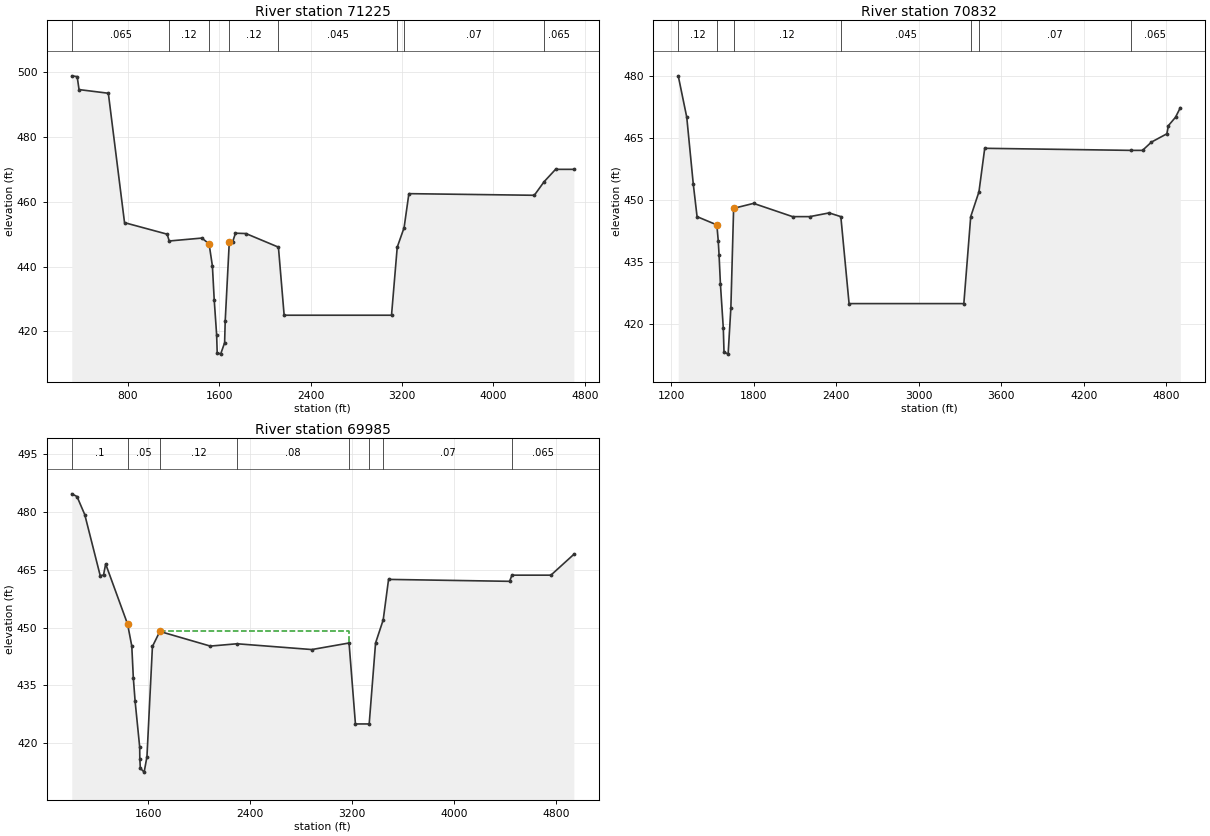
Type RM Length L Ch R = 1 ,71225   ,380,393,241
BEGIN DESCRIPTION:
This cross section corresponds to cross section 71246 of the non-georeferenced CDC model which was the source of this model.
---------------------------------------------------------------------
CDC FW020105-01 Riverpark Addition
Cross-section 71246 - 74891
Located in LOB.
---------------------------------------------------------------------
END DESCRIPTION:
XS GIS Cut Line= 4
     2417383.365     6980857.409     2417068.926     6979477.766
2415825.941552736978575.404959822414657.399211596977727.08615361
#Sta/Elev= 30
 309.988498.8458357.3073   498.6 373.718   494.6630.1356493.4716771.8537453.5542
1144.922     450    1163   447.9    1449   448.8    1512     447    1541   440.2
    1557   429.7    1578     419    1583   413.5    1613     413    1648   416.5
    1653   423.1    1689   447.7    1717   447.5    1743   450.3    1834   450.2
    2119     446    2169     425    3109     425    3159     446    3219     452
    3261   462.5    4359     462    4445   466.2    4545     470    4705     470
#Mann= 8 ,-1,0
 309.988    .065       0    1163     .12       0    1512     .05       0
    1689     .12       0    2119    .045       0    3159     .08       0
    3219     .07       0    4445    .065       0
#XS Ineff= 1 ,-1
    2119    3159     446
Permanent Ineff=
       T
Bank Sta=1512,1689
XS Rating Curve= 0 ,0
Exp/Cntr=0.3,0.1

Type RM Length L Ch R = 1 ,70832   ,1077,847,406
BEGIN DESCRIPTION:
This cross section corresponds to cross section 70832 of the non-georeferenced CDC model which was the source of this model.
END DESCRIPTION:
XS GIS Cut Line= 4
  2417547.578325 6979894.0199558 2417460.8819769 6979419.8174921
 2415994.4300846 6978468.6054099 2414800.58818956977694.22144216
#Sta/Elev= 30
    1250     480    1312     470    1359     454    1387     446    1531     444
    1541   440.2    1547   436.8    1557   429.7    1578     419    1583   413.3
    1613   412.8    1633     424    1653     448    1798   449.2    2082     446
    2207     446    2348   446.9    2433     446    2493     425    3328     425
    3378     446    3438     452    3480   462.5    4541     462    4628     462
    4693     464    4805     466    4817     468    4868     470    4903   472.3
#Mann= 7 ,-1,0
    1250     .12       0    1531     .05       0    1653     .12       0
    2433    .045       0    3378     .08       0    3438     .07       0
    4541    .065       0
#XS Ineff= 1 ,-1
    2433    3378     446
Permanent Ineff=
       T
Bank Sta=1531,1653
XS Rating Curve= 0 ,0
Exp/Cntr=0.3,0.1

Type RM Length L Ch R = 1 ,69985   ,228,228,228
BEGIN DESCRIPTION:
This cross section corresponds to cross section 70006 of the non-georeferenced CDC model which was the source of this model.
END DESCRIPTION:
XS GIS Cut Line= 6
  2418494.785092 6979191.3750356 2417704.1078684 6978869.5475953
 2417308.7635148  6978708.641093 2416913.4152241 6978547.7395119
  2416201.778524 6978258.12887072414845.433627836977706.17004218
#Sta/Elev= 30
    1000   484.7    1041     484    1102   479.3    1223   463.5    1249   463.6
    1266   466.5    1438   450.9    1471   445.2    1483     437    1497   430.9
    1533     419    1534     416    1538   413.5    1568   412.5    1590   416.5
    1633   445.1    1691     449    2087   445.2    2297   445.8    2884   444.3
    3176     446    3226     425    3334     425    3384     446    3444     452
    3486   462.5    4436     462    4454   463.6    4760   463.6    4940     469
#Mann= 8 ,-1,0
    1000      .1       0    1438     .05       0    1691     .12       0
    2297     .08       0    3176    .045       0    3334     .08       0
    3444     .07       0    4454    .065       0
#XS Ineff= 2 ,-1
    1691    3176     449    3176    3384     446
Permanent Ineff=
       F       T
Bank Sta=1438,1691
XS Rating Curve= 0 ,0
Exp/Cntr=0.3,0.1