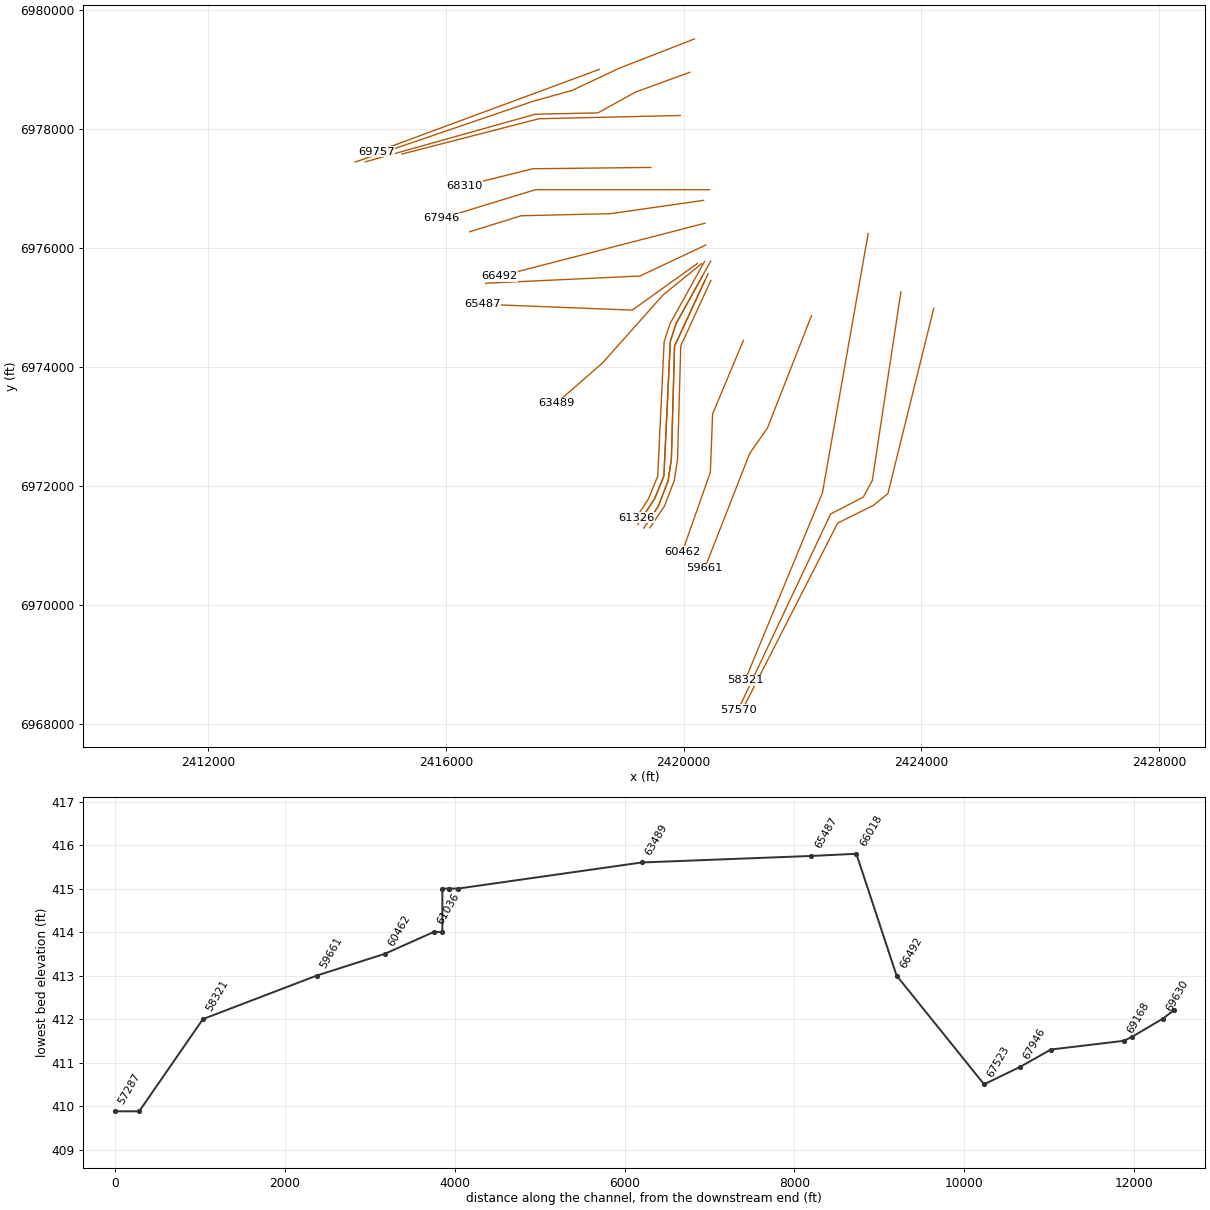
HEC-RAS study CDC_Consolidated_Model.prj: Upper Trinity CDC Consolidated Model

--- CDC_Consolidated_Model.g01 (geometry) --- (continued)

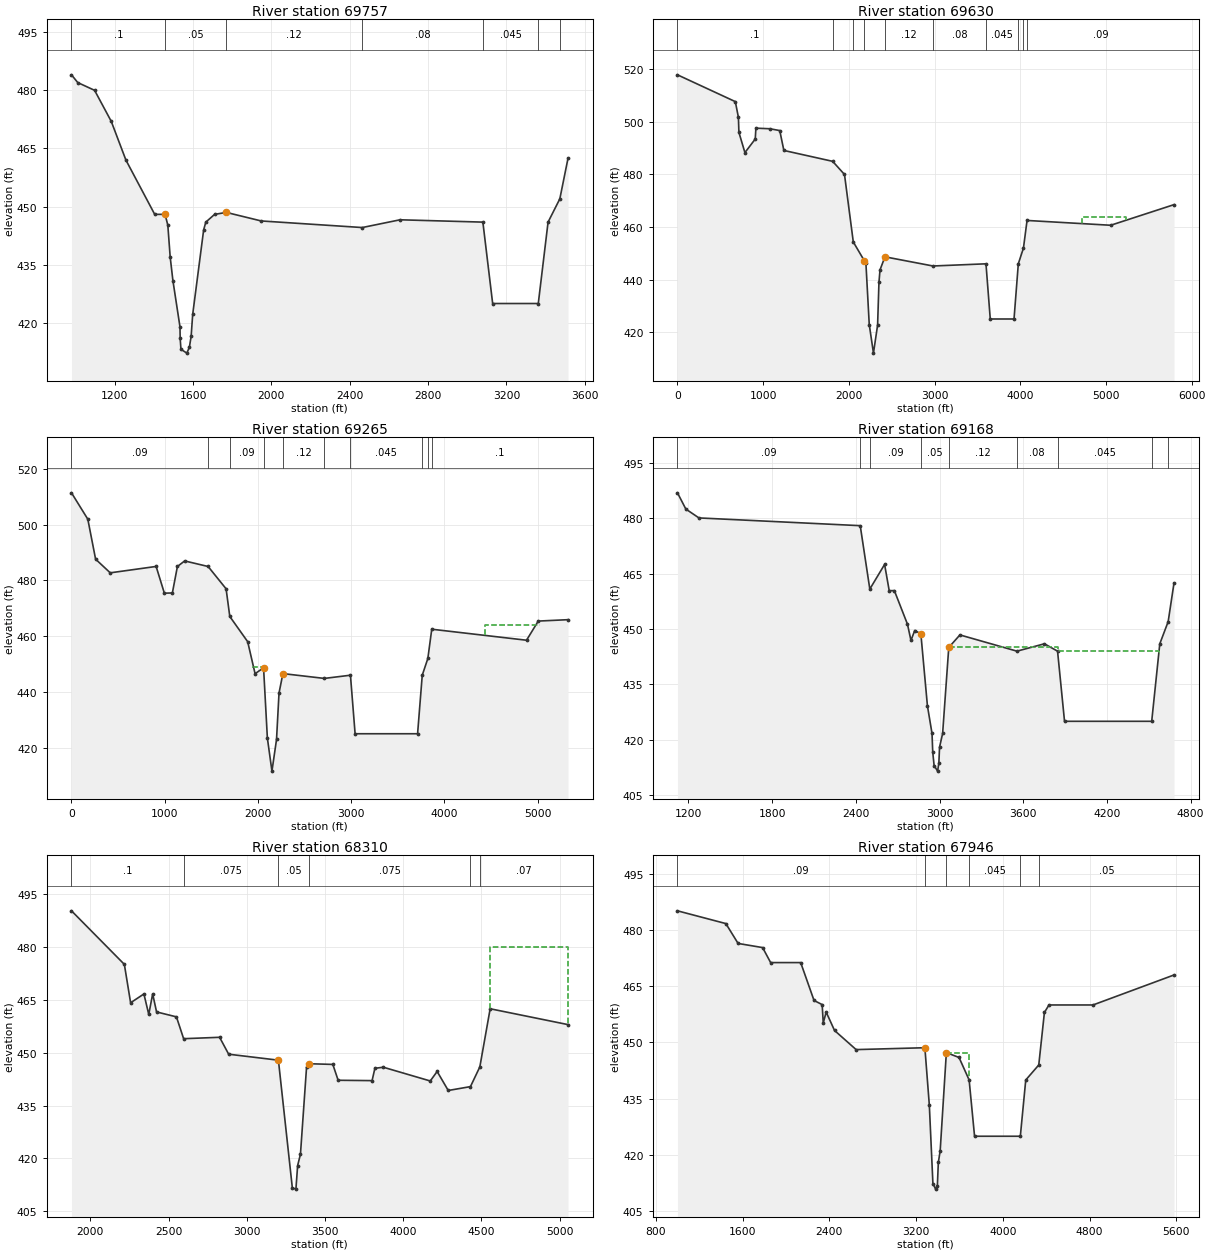
Type RM Length L Ch R = 1 ,69757   ,166,127,109
BEGIN DESCRIPTION:
69798
END DESCRIPTION:
XS GIS Cut Line= 2
  2418583.8709296978996.755135862414833.43700001     6977612.207
#Sta/Elev= 30
     979     484    1011     482    1097     480    1182     472    1257     462
    1404     448    1457     448    1471   445.2    1483     437    1497   430.9
    1533     419    1534     416    1538   413.2    1568   412.2    1581   413.7
    1590   416.5    1598   422.2    1654     444    1665     446    1710     448
    1770   448.5    1948   446.3    2464   444.6    2657   446.6    3080     446
    3130     425    3363     425    3413     446    3473     452    3515   462.5
#Mann= 7 ,-1,0
     979      .1       0    1457     .05       0    1770     .12       0
    2464     .08       0    3080    .045       0    3363     .08       0
    3473     .07       0
#XS Ineff= 1 ,-1
    3080    3413     446
Permanent Ineff=
       T
Bank Sta=1457,1770
XS Rating Curve= 0 ,0
Exp/Cntr=0.3,0.1

Type RM Length L Ch R = 1 ,69630   ,425,365,210
BEGIN DESCRIPTION:
69630
2009 LiDAR - LOB Includes Pettigrew Fill.
END DESCRIPTION:
XS GIS Cut Line= 5
  2420181.3521216979505.819805952418915.727122046979014.50036153
2418125.796566436978642.972583742417472.071161366978461.55258952
2414474.024286366977440.01034415
#Sta/Elev= 30
       0  517.92  675.07  507.72  711.01  501.76  716.97  496.01  786.99  488.32
  907.71   493.5  915.19  497.62 1077.64   497.4 1193.47  496.71 1241.54  489.14
 1810.87     485 1948.99     480 2051.75  454.31 2179.17  447.24 2198.94  446.23
 2237.89   422.9    2287  412.01 2335.36  422.68  2351.1  438.91 2363.59  443.69
 2421.06  448.66  2981.7  445.17    3600     446    3650     425 3927.34     425
 3977.34     446 4037.34     452 4079.34   462.5 5055.06  460.67  5794.4  468.52
#Mann= 10 ,-1,0
       0      .1       0 1810.87     .07       0 2051.75      .1       0
 2179.17     .05       0 2421.06     .12       0  2981.7     .08       0
    3600    .045       0 3977.34     .08       0 4037.34     .07       0
 4079.34     .09       0
#XS Ineff= 2 ,-1
    3600 3977.34     446 4715.94 5235.39  463.64
Permanent Ineff=
       T       F
Bank Sta=2179.17,2421.06
XS Rating Curve= 0 ,0
Exp/Cntr=0.3,0.1

Type RM Length L Ch R = 1 ,69265   ,78,97,80
BEGIN DESCRIPTION:
69265
2009 LiDAR - LOB Includes Pettigrew Fill.
END DESCRIPTION:
XS GIS Cut Line= 5
  2420106.5098186978947.835141612419193.749402116978615.80389161
2418559.634818736978265.543474962417505.815374346978243.69741014
2414644.270000046977443.35000001
#Sta/Elev= 30
       0  511.43  175.08  501.97  258.55  487.63   415.5  482.73  907.77  485.02
  996.08  475.43 1082.03  475.51    1136     485    1214     487 1465.46     485
 1658.23     477 1697.95  467.07 1889.67  458.03 1969.17  446.55 2060.18  448.66
    2101  423.46    2150  411.59 2199.25  422.95 2225.88  439.59 2267.44  446.58
 2712.06  444.85 2992.02     446 3042.02     425 3712.25     425 3762.25     446
 3822.25     452 3864.25   462.5 4880.77  458.55 5006.35  465.42 5326.06  465.92
#Mann= 10 ,-1,0
       0     .09       0 1465.46     .07       0 1697.95     .09       0
 2060.18     .05       0 2267.44     .12       0 2712.06     .08       0
 2992.02    .045       0 3762.25     .08       0 3822.25     .07       0
 3864.25      .1       0
#XS Ineff= 4 ,-1
  164.38    1214     487  1934.3 2055.48     449 2992.02 3762.25     446
 4437.25 5027.87  463.98
Permanent Ineff=
       F       F       T       F
Bank Sta=2060.18,2267.44
XS Rating Curve= 0 ,0
Exp/Cntr=0.3,0.1

Type RM Length L Ch R = 1 ,69168   ,850,857,800
BEGIN DESCRIPTION:
69186
---------------------------------------------------------------------
LOMR#17-06-0659P & CDC FW050115-01 Pettigrew Development
Cross-sections 69186 - 69630
---------------------------------------------------------------------
LOB includes Pettigrew Fill.
END DESCRIPTION:
XS GIS Cut Line= 6
  2419943.983309 6978221.9225782 2419339.5317629 6978208.0065956
  2418749.186815 6978194.4262421 2417568.4959349 6978167.2980156
  2416741.462484 6977954.59207622415259.73833976 6977573.5434931
#Sta/Elev= 30
    1121   486.9    1181   482.5    1275   480.1 2431.28     478    2500  460.82
    2606   467.5    2639   460.4    2676   460.4    2770   451.3    2795   446.9
    2822   449.6    2866   448.7    2913   429.2    2946   421.7    2951   416.7
    2961     413    2986   411.5    2995   413.7    3000     418    3022   421.7
    3066     445    3146   448.4    3555     444    3752     446    3846     444
    3896     425    4521     425    4579     446    4639     452    4681   462.5
#Mann= 9 ,-1,0
    1121     .09       0 2431.28     .07       0    2500     .09       0
    2866     .05       0    3066     .12       0    3555     .08       0
    3846    .045       0    4521     .08       0    4639     .07       0
#XS Ineff= 3 ,-1
    2000    2866   448.7    3066    3846     445    3846    4571     444
Permanent Ineff=
       F       F       T
Bank Sta=2866,3066
XS Rating Curve= 0 ,0
Exp/Cntr=0.3,0.1

Type RM Length L Ch R = 1 ,68310   ,339,364,334
BEGIN DESCRIPTION:
This cross section corresponds to cross section 68329 of the non-georeferenced CDC model which was the source of this model.
END DESCRIPTION:
XS GIS Cut Line= 6
2419451.021301856977349.46259518 2418555.6301155 6977339.7366786
 2417968.6099641 6977333.3741585 2417465.4498812 6977327.9289594
 2416881.8818226 6977183.58410372416310.928618726977042.37117316
#Sta/Elev= 30
    1879   490.3    2217   475.1    2257   464.2    2342   466.7    2373   460.9
    2398   466.7    2423   461.6    2550   460.2    2596     454    2826   454.4
    2884   449.6    3202   447.9    3291   411.7    3314   411.3    3325     418
    3343   421.2    3382   445.9    3395   446.9    3550   446.7    3584   442.2
    3801   442.1    3819   445.6    3873   445.9    4173     442    4217   444.7
    4288   439.3    4430   440.4    4490     446    4556   462.5    5054     458
#Mann= 6 ,-1,0
    1879      .1       0    2596    .075       0    3202     .05       0
    3395    .075       0    4430     .08       0    4490     .07       0
#XS Ineff= 3 ,-1
    4556    5054     480    1879    3202   447.9    3395    4556   446.9
Permanent Ineff=
       F       F       F
Bank Sta=3202,3395
XS Rating Curve= 0 ,0
Exp/Cntr=0.3,0.1

Type RM Length L Ch R = 1 ,67946   ,454,423,449
BEGIN DESCRIPTION:
This cross section corresponds to cross section 67950 of the non-georeferenced CDC model which was the source of this model.
END DESCRIPTION:
XS GIS Cut Line= 3
  2420433.972159 6976976.2410145 2417508.6249917 6976976.2410145
  2415928.247575 6976492.8486086
#Sta/Elev= 30
    1000   485.1    1446   481.7    1559   476.4    1785   475.3    1859   471.3
    2136   471.3    2259   461.2    2334   460.1    2344   455.2    2371   458.1
    2448   453.2    2647   448.1    3281   448.6    3322   433.3    3355   412.4
    3380   410.9    3396   411.7    3405     418    3422   421.1    3479   447.3
    3596     446    3689     440    3739     425    4161     425    4211     440
    4331     444    4383     458    4425     460    4831     460    5578     468
#Mann= 6 ,-1,0
    1000     .09       0    3281    .055       0    3479     .07       0
    3689    .045       0    4161     .07       0    4331     .05       0
#XS Ineff= 3 ,-1
    2000    3281   448.6    3479    3684   447.3    3684    4211     440
Permanent Ineff=
       F       F       T
Bank Sta=3281,3479
XS Rating Curve= 0 ,0
Exp/Cntr=0.3,0.1

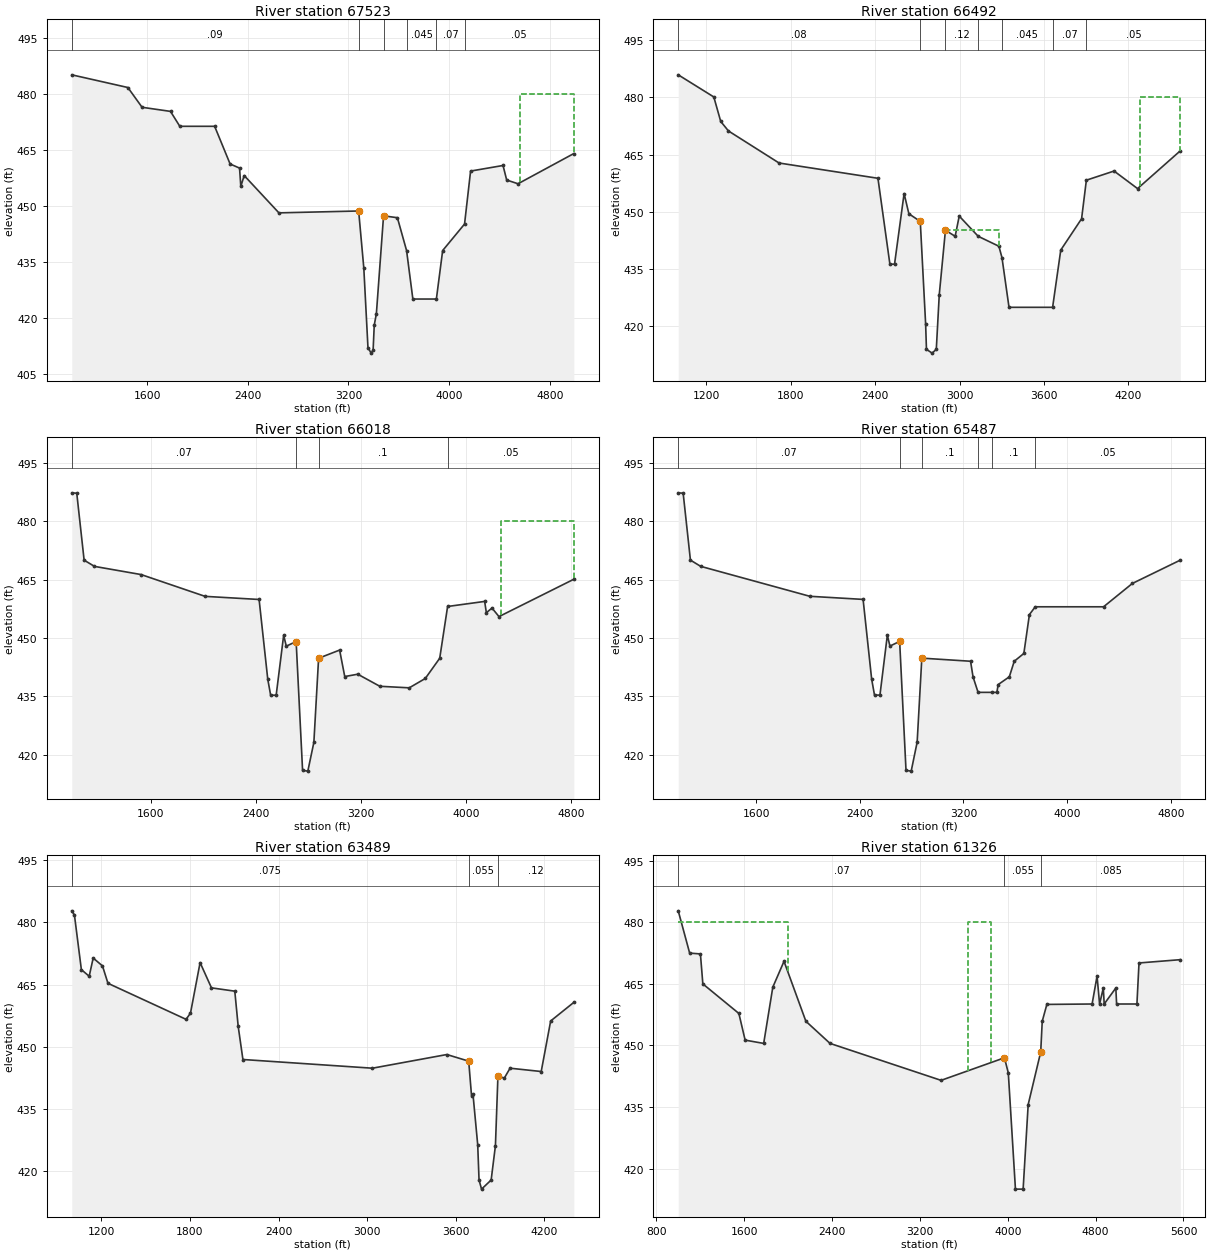
Type RM Length L Ch R = 1 ,67523   ,522,1031,853
BEGIN DESCRIPTION:
This cross section corresponds to cross section 67543 of the non-georeferenced CDC model which was the source of this model.
END DESCRIPTION:
XS GIS Cut Line= 6
    2420337.2381 6976797.2948501 2419597.4981105 6976691.3432903
 2418775.5591376 6976573.6391294 2417937.7222306 6976554.0158091
 2417267.4519176 6976538.33309772416402.437933516976269.79467283
#Sta/Elev= 30
    1000   485.1    1446   481.7    1559   476.4    1785   475.3    1859   471.3
    2136   471.3    2259   461.2    2334   460.1    2344   455.2    2371   458.1
    2647   448.1    3281   448.6    3322   433.3    3355     412    3380   410.5
    3396   411.3    3405     418    3422   421.1    3479   447.3    3589   446.8
    3662     438    3712     425    3899     425    3949     438    4123   445.1
    4171   459.3    4429   460.8    4458   456.9    4548   455.9    4992     464
#Mann= 6 ,-1,0
    1000     .09       0    3281    .055       0    3479     .07       0
    3662    .045       0    3899     .07       0    4123     .05       0
#XS Ineff= 3 ,-1
    4567    4992     480    2000    3281   448.6    3662    4567     438
Permanent Ineff=
       F       F       T
Bank Sta=3281,3479
XS Rating Curve= 0 ,0
Exp/Cntr=0.3,0.1

Type RM Length L Ch R = 1 ,66492   ,526,474,298
BEGIN DESCRIPTION:
This cross section corresponds to cross section 66515 of the non-georeferenced CDC model which was the source of this model.
END DESCRIPTION:
XS GIS Cut Line= 6
  2420357.846983 6976412.1230482 2419529.0172763 6976198.6093677
 2419114.5981577 6976091.8605654 2418617.2920657 6975963.7689581
 2417871.3253818 6975771.64598272416900.677700116975521.68416544
#Sta/Elev= 30
    1000   485.9    1253   480.1    1302   473.7    1357   471.2    1717   462.8
    2420   458.8    2505   436.3    2538   436.3    2606   454.8    2640   449.5
    2721   447.5    2759   420.7    2765     414    2805     413    2835     414
    2856   428.3    2900   445.2    2969   443.6    2998   448.9    3133   443.6
    3280     441    3302     438    3352     425    3662     425    3720     440
    3868   448.2    3902   458.3    4099   460.7    4266   456.1    4570     466
#Mann= 7 ,-1,0
    1000     .08       0    2721     .05       0    2900     .12       0
    3133     .07       0    3302    .045       0    3662     .07       0
    3902     .05       0
#XS Ineff= 5 ,-1
    4285    4570     480    2420    2606   454.5    2606    2721   447.5
    2900    3280   445.2    3280    3750     438
Permanent Ineff=
       F       T       F       F       T
Bank Sta=2721,2900
XS Rating Curve= 0 ,0
Exp/Cntr=0.3,0.1

Type RM Length L Ch R = 1 ,66018   ,209,530,426
BEGIN DESCRIPTION:
This cross section corresponds to cross section 66037
 of the non-georeferenced CDC model which was the source of this model.
END DESCRIPTION:
XS GIS Cut Line= 6
  2420373.650101 6976046.3809976 2419819.9149885 6975786.3592079
 2419266.1710172 6975526.3469327 2418596.2547062 6975495.1635961
 2417926.3370827  6975463.994039 2416670.4752935 6975405.5967403
#Sta/Elev= 30
    1000   487.3    1038   487.2    1094     470    1173   468.4    1528   466.3
    2015   460.7    2426   459.9    2492   439.4    2514   435.3    2556   435.3
    2613   450.7    2633   447.9    2708   449.1    2757     416    2797   415.8
    2843   423.2    2879   444.8    3039   446.9    3078   440.1    3177   440.7
    3345   437.6    3569   437.2    3691   439.6    3801   444.8    3861   458.1
    4143   459.4    4156   456.5    4199   457.7    4252   455.5    4822   465.1
#Mann= 4 ,-1,0
    1000     .07       0    2708    .055       0    2879      .1       0
    3861     .05       0
#XS Ineff= 3 ,-1
    4271    4822     480    2426    2708   449.1    2879    4271   444.8
Permanent Ineff=
       F       T       F
Bank Sta=2708,2879
XS Rating Curve= 0 ,0
Exp/Cntr=0.3,0.1

Type RM Length L Ch R = 1 ,65487   ,790,1998,1603
BEGIN DESCRIPTION:
This cross section corresponds to cross section 65500 of the non-georeferenced CDC model which was the source of this model.
END DESCRIPTION:
XS GIS Cut Line= 3
  2420232.389229 6975737.3304346  2419136.229348 6974953.6715688
 2416615.2927888 6975052.3741273
#Sta/Elev= 30
    1000   487.3    1038   487.2    1094     470    1173   468.4    2015   460.7
    2426   459.9    2492   439.4    2514   435.3    2556   435.3    2613   450.7
    2633   447.9    2708   449.1    2757  415.95    2797  415.75    2843   423.2
    2879   444.8    3255     444    3274     440    3313     436    3420     436
    3458     436    3468     438    3554     440    3592     444    3666     446
    3709     456    3754     458    4281     458    4503     464    4873     470
#Mann= 6 ,-1,0
    1000     .07       0    2708    .055       0    2879      .1       0
    3313    .045       0    3420      .1       0    3754     .05       0
#XS Ineff= 4 ,-1
    1000    2000   449.1    2000    2613   449.1    2613    2708   449.1
    2879    4873   444.8
Permanent Ineff=
       F       T       F       F
Bank Sta=2708,2879
XS Rating Curve= 0 ,0
Exp/Cntr=0.3,0.1

Type RM Length L Ch R = 1 ,63489   ,1000,2164,2351
BEGIN DESCRIPTION:
This cross section corresponds to cross section 63507 of the non-georeferenced CDC model which was the source of this model.
---------------------------------------------------------------------
Great Southwestern Development CDC GP120299-01
Located in ROB.
Cross-sections 65500 - 74891
---------------------------------------------------------------------
END DESCRIPTION:
XS GIS Cut Line= 6
   2420304.03049 6975732.7746694 2419661.9809212 6975215.3531321
 2419118.1667201 6974606.6660292 2418634.7588942  6974065.618883
 2418189.0412817 6973677.5852102 2417855.1623563 6973386.9269989
#Sta/Elev= 30
    1000   482.8    1018   481.8    1065   468.6    1118     467    1145   471.4
    1208   469.5    1245   465.3    1774   456.6    1804   458.1    1869   470.3
    1946   464.2    2104   463.4    2127   454.9    2159   446.9    3036   444.8
    3540   448.1    3688   446.5    3707   438.2    3717   438.5    3749   426.3
    3758   417.8    3775   415.6    3840   417.8    3869   426.1    3886     443
    3929   442.4    3968   444.8    4179     444    4243   456.2    4400   460.7
#Mann= 3 ,0,0
    1000    .075       0    3688    .055       0    3886     .12       0
#XS Ineff= 2 , 0
            3688   446.5    3886             443
Permanent Ineff=
       F       F
Bank Sta=3688,3886
XS Rating Curve= 0 ,0
Exp/Cntr=0.3,0.1

Type RM Length L Ch R = 1 ,61326   ,103,103,103
BEGIN DESCRIPTION:
This cross section corresponds to cross section 61344 of the non-georeferenced CDC model which was the source of this model.
END DESCRIPTION:
XS GIS Cut Line= 6
  2420353.863326 6975773.0377739 2419772.2940207 6974727.1129668
 2419673.1288647 6974425.1109462 2419564.9499472  6972166.854964
 2419411.6950044 6971788.2251438 2419202.5428637 6971467.2021638
#Sta/Elev= 30
    1000   482.8    1104   472.5    1202   472.3    1224     465    1552   457.8
    1609   451.3    1778   450.5    1861   464.2    1963   470.5    2162   455.9
    2382   450.5    3393   441.5    3970     447    4005   443.3    4070     415
    4140     415    4186   435.6    4300   448.4    4314   455.9    4356     460
    4768   460.1    4813   466.9    4836   460.1    4870     464    4878   460.1
    4984     464    4991   460.1    5176   460.1    5195   470.1    5571   470.9
#Mann= 3 ,0,0
    1000     .07       0    3970    .055       0    4300    .085       0
#XS Ineff= 3 ,-1
    1000    2000     480    3640    3850     480    2000    3640     441
Permanent Ineff=
       T       T       F
Bank Sta=3970,4300
XS Rating Curve= 0 ,0
Exp/Cntr=0.3,0.1

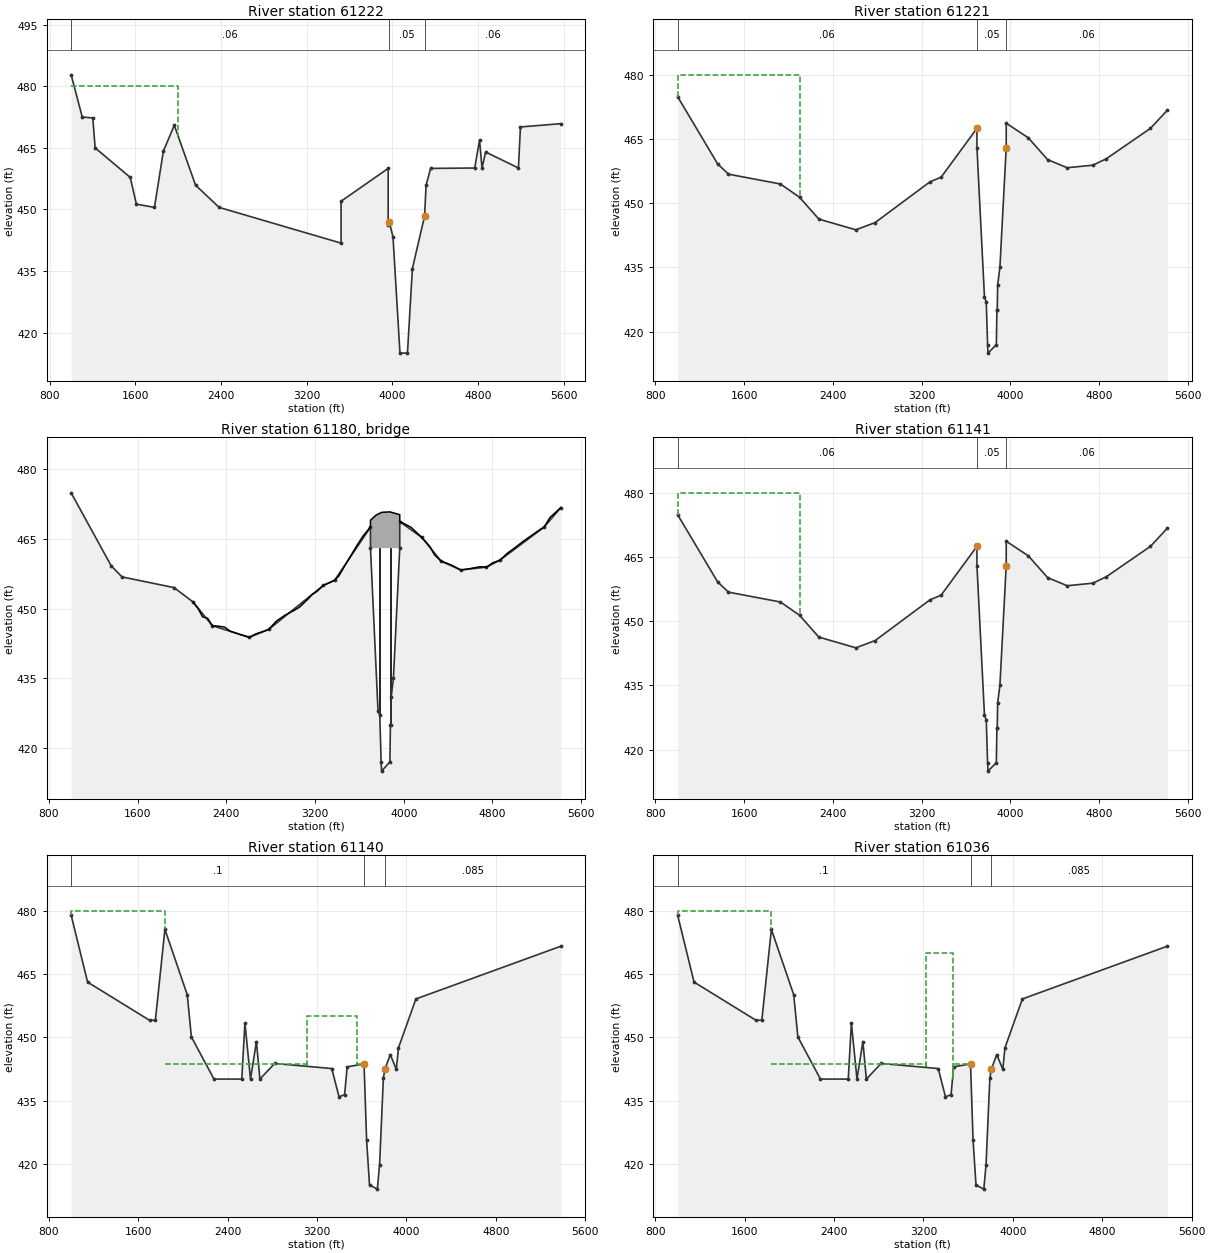
Type RM Length L Ch R = 1 ,61222   ,1,1,1
BEGIN DESCRIPTION:
This cross section corresponds to cross section 61239
 of the non-georeferenced CDC model which was the source of this model.
END DESCRIPTION:
XS GIS Cut Line= 6
  2420457.213843 6975777.6361889 2419875.6445358 6974731.7113828
 2419776.4793798 6974429.7093622 2419668.3004623   6972171.45338
 2419515.0455195 6971792.8235598 2419305.8933787 6971471.8005798
#Sta/Elev= 30
    1000   482.8    1104   472.5    1202   472.3    1224     465    1552   457.8
    1609   451.3    1778   450.5    1861   464.2    1963   470.5    2162   455.9
    2382   450.5    3520   441.8    3520     452    3960     460    3960   446.3
    3970     447    4005   443.3    4070     415    4140     415    4186   435.6
    4300   448.4    4314   455.9    4356     460    4768   460.1    4813   466.9
    4836   460.1    4870     464    5176   460.1    5195   470.1    5571   470.9
#Mann= 3 ,0,0
    1000     .06       0    3970     .05       0    4300     .06       0
#XS Ineff= 2 , 0
       0    2000     480    4300       0   448.4
Permanent Ineff=
       T       F
Bank Sta=3970,4300
XS Rating Curve= 0 ,0
Exp/Cntr=0.5,0.3

Type RM Length L Ch R = 1 ,61221   ,80,80,80
BEGIN DESCRIPTION:
This cross section corresponds to cross section 61238 of the non-georeferenced CDC model which was the source of this model.
END DESCRIPTION:
XS GIS Cut Line= 6
  2420314.953696  6975521.336444 2419876.5254396 6974731.3990475
 2419777.4774093 6974429.7536534 2419669.2984918 6972171.4976712
  2419516.043549 6971792.8678511 2419231.2531081 6971355.7558644
#Sta/Elev= 30
    1000   474.9    1361   459.2    1459   456.8    1928   454.5    2100   451.4
    2274   446.3    2608   443.8    2782   445.5    3276     455    3377   456.1
    3700   467.5    3700     463    3768     428    3784     427    3796     417
    3800     415    3875     417    3880     425    3883     425    3887     431
    3907     435    3964     463    3964   468.7    4163   465.3    4337   460.2
    4514   458.3    4746   458.9    4867   460.4    5265   467.5    5416   471.7
#Mann= 3 ,0,0
    1000     .06       0    3700     .05       0    3964     .06       0
#XS Ineff= 2 , 0
       0    2100     480    3964       0   458.3
Permanent Ineff=
       T       F
Bank Sta=3700,3964
XS Rating Curve= 0 ,0
Exp/Cntr=0.3,0.1

Type RM Length L Ch R = 3 ,61180   ,,,
BEGIN DESCRIPTION:
Roy Orr Boulevard/NW 19th Street
END DESCRIPTION:
Node Name=NW 19th Street
Bridge Culvert--1,0,-1,-1, 0
Deck Dist Width WeirC Skew NumUp NumDn MinLoCord MaxHiCord MaxSubmerge Is_Ogee
1,78,2.6,0, 57, 57, , , 0.95, 0, ,,,
    2100    2142    2186    2231    2274    2328    2384    2437    2524    2608
    2661    2749    2782    2852    2931    3004    3060    3143    3173    3219
    3276    3354    3377    3414    3503    3576    3633    3698    3700    3700
    3750    3800    3875    3964    3964    3967    4065    4163    4237    4276
    4337    4426    4514    4578    4645    4690    4746    4800    4867    4935
    5004    5080    5158    5229    5265    5320    5416
   451.4   450.1   448.2   447.9   446.3   446.2     446   445.1   444.4   443.8
   444.5   445.2   445.5   447.3   448.6   449.5   450.3   452.2     453   453.7
     455   455.8   456.1     457   460.6   463.5   465.6   467.5   467.5     469
   470.1   470.7   470.8   470.2   468.7   468.7   467.5   465.3   463.3   461.6
   460.2   459.4   458.3   458.5   458.8     459   458.9   459.8   460.4   461.9
   463.1   464.5   465.8     467   467.5   469.6   471.7
   451.4   450.1   448.2   447.9   446.3   446.2     446   445.1   444.4   443.8
   444.5   445.2   445.5   447.3   448.6   449.5   450.3   452.2     453   453.7
     455   455.8   456.1     457   460.6   463.5   465.6   467.5   467.5     463
     463     463     463     463   468.7   468.7   467.5   465.3   463.3   461.6
   460.2   459.4   458.3   458.5   458.8     459   458.9   459.8   460.4   461.9
   463.1   464.5   465.8     467   467.5   469.6   471.7
    2100    2142    2186    2231    2274    2328    2384    2437    2524    2608
    2661    2749    2782    2852    2931    3004    3060    3143    3173    3219
    3276    3354    3377    3414    3503    3576    3633    3698    3700    3700
    3750    3800    3875    3964    3964    3967    4065    4163    4237    4276
    4337    4426    4514    4578    4645    4690    4746    4800    4867    4935
    5004    5080    5158    5229    5265    5320    5416
   451.4   450.1   448.2   447.9   446.3   446.2     446   445.1   444.4   443.8
   444.5   445.2   445.5   447.3   448.6   449.5   450.3   452.2     453   453.7
     455   455.8   456.1     457   460.6   463.5   465.6   467.5   467.5     469
   470.1   470.7   470.8   470.2   468.7   468.7   467.5   465.3   463.3   461.6
   460.2   459.4   458.3   458.5   458.8     459   458.9   459.8   460.4   461.9
   463.1   464.5   465.8     467   467.5   469.6   471.7
   451.4   450.1   448.2   447.9   446.3   446.2     446   445.1   444.4   443.8
   444.5   445.2   445.5   447.3   448.6   449.5   450.3   452.2     453   453.7
     455   455.8   456.1     457   460.6   463.5   465.6   467.5   467.5     463
     463     463     463     463   468.7   468.7   467.5   465.3   463.3   461.6
   460.2   459.4   458.3   458.5   458.8     459   458.9   459.8   460.4   461.9
   463.1   464.5   465.8     467   467.5   469.6   471.7
Pier Skew, UpSta & Num, DnSta & Num=  ,3782.5, 2 ,3782.5, 2 , 0 , 0 , 0 ,,
       3       3
     400     464
       3       3
     400     464
Pier Skew, UpSta & Num, DnSta & Num=  ,3881.5, 2 ,3881.5, 2 , 0 , 0 , 0 ,,
       3       3
     400     464
       3       3
     400     464
BR Coef= 1 , 0 , 0 ,1.05, 0 ,,,0.8,-1,0.5,1,
WSPro=,,,, 1 ,,,, 0 ,,,, 0 ,,,,-1 ,-1 ,-1 , 0 , 0 , 0 , 0 , 0
BC Design=,, 0 ,, 0 ,,,,,,
BC HTab HWMax=471.7
BC Use User HTab Curves=0
BC User HTab FreeFlow(D)= 0

Type RM Length L Ch R = 1 ,61141   ,1,1,1
BEGIN DESCRIPTION:
This cross section corresponds to cross section 61158 of the non-georeferenced CDC model which was the source of this model.
END DESCRIPTION:
XS GIS Cut Line= 6
  2420411.951534 6975562.1680552 2419847.8857331 6974348.3325564
 2419793.7959462 6972446.1683817 2419739.7058313 6972090.0765742
 2419573.0805084 6971657.7516515 2419379.3362925 6971369.8189847
#Sta/Elev= 30
    1000   474.9    1361   459.2    1459   456.8    1928   454.5    2100   451.4
    2274   446.3    2608   443.8    2782   445.5    3276     455    3377   456.1
    3700   467.5    3700     463    3768     428    3784     427    3796     417
    3800     415    3875     417    3880     425    3883     425    3887     431
    3907     435    3964     463    3964   468.7    4163   465.3    4337   460.2
    4514   458.3    4746   458.9    4867   460.4    5265   467.5    5416   471.7
#Mann= 3 ,0,0
    1000     .06       0    3700     .05       0    3964     .06       0
#XS Ineff= 2 , 0
       0    2100     480    3964       0   458.3
Permanent Ineff=
       T       F
Bank Sta=3700,3964
XS Rating Curve= 0 ,0
Exp/Cntr=0.3,0.1

Type RM Length L Ch R = 1 ,61140   ,104,104,104
BEGIN DESCRIPTION:
This cross section corresponds to cross section 61157 of the non-georeferenced CDC model which was the source of this model.
END DESCRIPTION:
XS GIS Cut Line= 6
  2420356.356172 6975448.9612607 2419848.8840907 6974348.3768477
 2419794.7943038  6972446.212673 2419740.7041889 6972090.1208655
 2419573.9272915 6971657.4019147 2419329.7361788 6971293.5089417
#Sta/Elev= 30
    1000     479    1147   463.1    1704     454    1754   454.1    1839   475.6
    2039   460.1    2076   450.1    2278   440.1    2527   440.1    2555   453.4
    2605   440.1    2658     449    2689   440.1    2821   443.8    3332   442.6
    3397   435.9    3447   436.4    3470     443    3621   443.7    3644   425.6
    3670     415    3740     414    3760   419.8    3794   440.3    3807   442.4
    3856   445.9    3910   442.4    3929   447.5    4085   459.1    5381   471.6
#Mann= 3 ,0,0
    1000      .1       0    3621     .05       0    3807    .085       0
#XS Ineff= 5 ,-1
    1000    1839     480    3110    3560     455    1839    3110   443.7
    3560    3621   443.7    3807    5381   442.4
Permanent Ineff=
       T       T       F       F       F
Bank Sta=3621,3807
XS Rating Curve= 0 ,0
Exp/Cntr=0.3,0.1

Type RM Length L Ch R = 1 ,61036   ,851,574,550
BEGIN DESCRIPTION:
This cross section corresponds to cross section 61054 of the non-georeferenced CDC model which was the source of this model.
END DESCRIPTION:
XS GIS Cut Line= 6
  2420460.065865 6975453.5752782  2419952.593857 6974352.9910117
 2419898.5040702  6972450.826837 2419844.4139552 6972094.7350295
 2419677.6370578 6971662.0160787 2419433.4459452 6971298.1231057
#Sta/Elev= 30
    1000     479    1147   463.1    1704     454    1754   454.1    1839   475.6
    2039   460.1    2076   450.1    2278   440.1    2527   440.1    2555   453.4
    2605   440.1    2658     449    2689   440.1    2821   443.8    3332   442.6
    3397   435.9    3447   436.4    3470     443    3621   443.7    3644   425.6
    3670     415    3740     414    3760   419.8    3794   440.3    3807   442.4
    3856   445.9    3910   442.4    3929   447.5    4085   459.1    5381   471.6
#Mann= 3 ,0,0
    1000      .1       0    3621     .05       0    3807    .085       0
#XS Ineff= 5 ,-1
    1000    1839     480    3220    3460     470    3460    3621   443.7
    1839    3220   443.7    3807    5381   442.4
Permanent Ineff=
       T       T       F       F       F
Bank Sta=3621,3807
XS Rating Curve= 0 ,0
Exp/Cntr=0.3,0.1

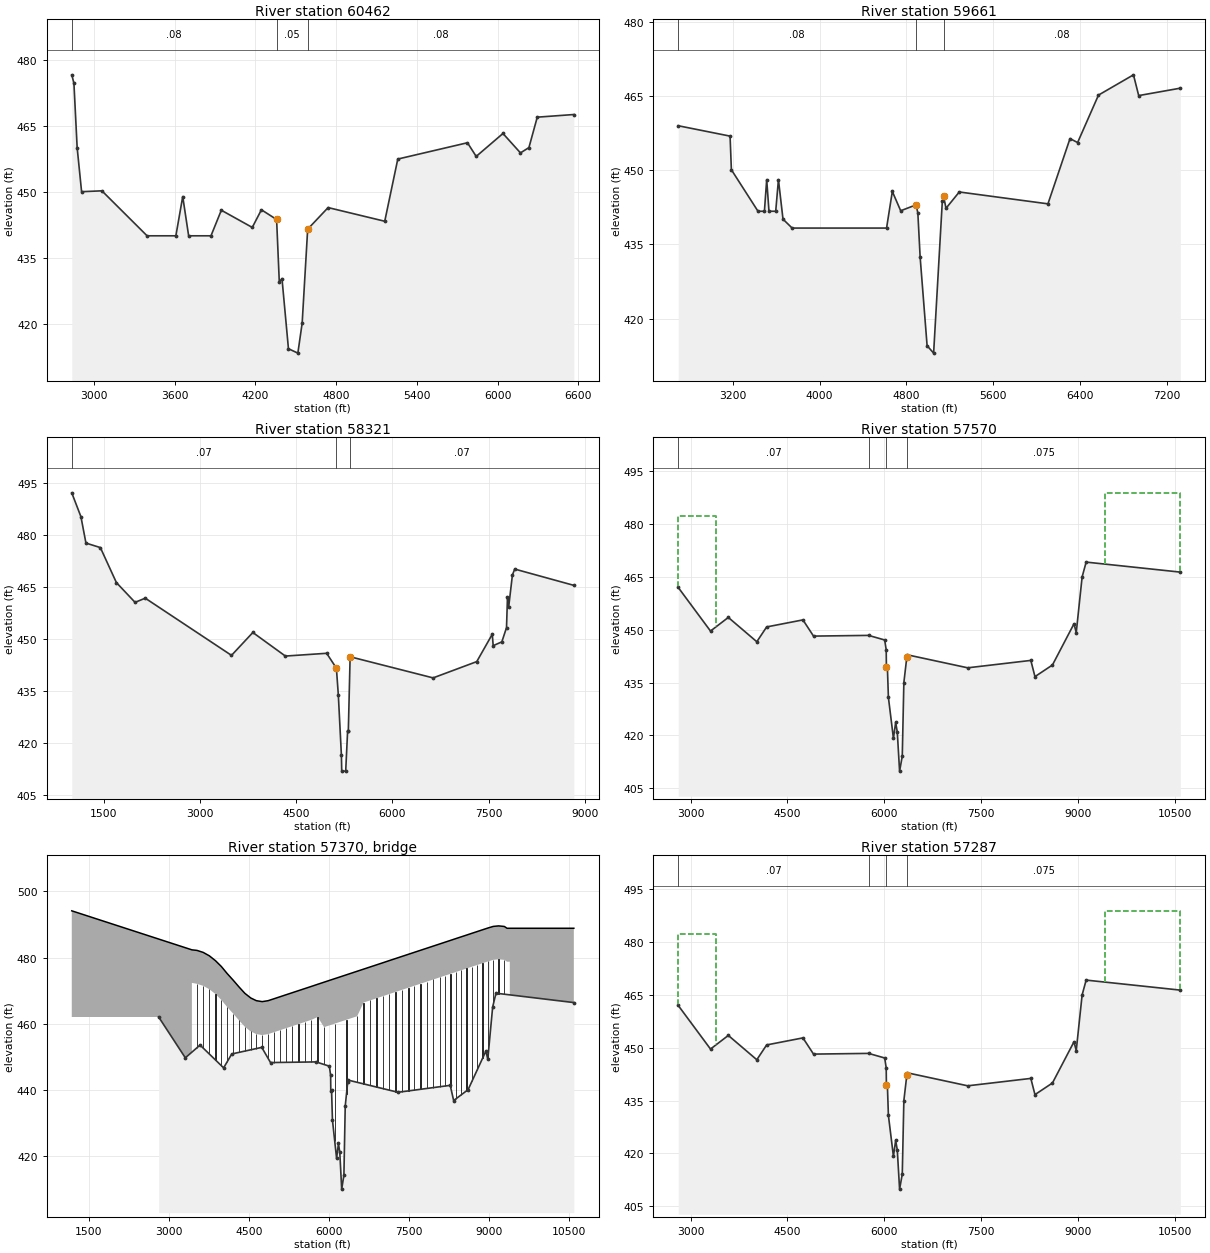
Type RM Length L Ch R = 1 ,60462   ,951,801,550
BEGIN DESCRIPTION:
This cross section corresponds to cross section 60480 of the non-georeferenced CDC model which was the source of this model.
END DESCRIPTION:
XS GIS Cut Line= 6
  2421007.528426   6974447.43308  2420749.167067  6973832.761081
 2420488.2978381 6973212.1491332 2420450.6020473 6972232.0470908
  2420200.416196 6971521.6413594 2419981.4940617 6970900.0379438
#Sta/Elev= 30
    2834   476.6    2850   474.7    2874   460.1    2907   450.1    3058   450.3
    3394   440.1    3608   440.1    3659     449    3703   440.1    3869   440.1
    3946   445.9    4176     442    4244     446    4357   443.8    4377   429.6
    4397   430.4    4445   414.5    4515   413.5    4547   420.3    4588   441.6
    4740   446.5    5161   443.4    5258   457.5    5776   461.2    5841   458.1
    6040   463.3    6170   458.9    6233   460.1    6295     467    6567   467.6
#Mann= 3 ,0,0
    2834     .08       0    4357     .05       0    4588     .08       0
#XS Ineff= 2 , 0
            4357   443.8    4588           441.6
Permanent Ineff=
       F       F
Bank Sta=4357,4588
XS Rating Curve= 0 ,0
Exp/Cntr=0.3,0.1

Type RM Length L Ch R = 1 ,59661   ,948,1341,1597
BEGIN DESCRIPTION:
This cross section corresponds to cross section 59680
 of the non-georeferenced CDC model which was the source of this model.
END DESCRIPTION:
XS GIS Cut Line= 6
  2422152.102581 6974861.3945224  2421770.165025  6973888.859394
 2421411.8550461 6972976.5478984 2421110.2860954 6972543.0408914
 2420767.5013479 6971668.2998587 2420356.1340604 6970618.6159345
#Sta/Elev= 30
    2700     459    3177   456.9    3189   450.1    3434   441.7    3493   441.7
    3514   448.1    3535   441.7    3597   441.7    3622   448.1    3664   440.1
    3748   438.3    4617   438.3    4670   445.7    4747   441.8    4889     443
    4905   441.3    4926   432.4    4990   414.5    5050     413    5130   443.7
    5142   444.7    5164   442.3    5286   445.6    6102   443.2    6305   456.4
    6375   455.6    6567   465.2    6889   469.3    6937   465.1    7320   466.6
#Mann= 3 ,0,0
    2700     .08       0    4889     .05       0    5142     .08       0
#XS Ineff= 3 ,-1
    2700    3622   448.1    5142    7320   444.7    3622    4659   440.1
Permanent Ineff=
       T       F       T
Bank Sta=4889,5142
XS Rating Curve= 0 ,0
Exp/Cntr=0.3,0.1

Type RM Length L Ch R = 1 ,58321   ,714,751,739
BEGIN DESCRIPTION:
This cross section corresponds to cross section 58337 of the non-georeferenced CDC model which was the source of this model.
END DESCRIPTION:
XS GIS Cut Line= 6
  2423105.205005 6976239.6250337 2422745.9967347 6974206.6970129
 2422335.4129103 6971883.3568433 2421702.9167999 6970353.5770945
 2421368.0408292 6969543.6991211 2421033.8754871 6968735.5845956
#Sta/Elev= 30
    1000   492.3    1143   485.4    1221   477.8    1446   476.5    1696   466.4
    1987   460.7    2146   461.9    3491   445.4    3824     452    4331   445.2
    4975     446    5127   441.7    5157     434    5205   416.6    5210     412
    5272     412    5302   423.6    5313   423.6    5341     445    6635   438.9
    7316   443.6    7558   451.5    7572   448.2    7707   449.3    7780   453.4
    7795   462.2    7814   459.4    7872   468.6    7908   470.3    8830   465.6
#Mann= 3 ,0,0
    1000     .07       0    5127     .05       0    5341     .07       0
#XS Ineff= 2 , 0
       0    5127   441.7    5341       0     445
Permanent Ineff=
       F       F
Bank Sta=5127,5341
XS Rating Curve= 0 ,0
Exp/Cntr=0.3,0.1

Type RM Length L Ch R = 1 ,57570   ,354,283,357
BEGIN DESCRIPTION:
This cross section corresponds to cross section 57586 of the non-georeferenced CDC model which was the source of this model.
Upstream bounding cross-section.
Section data is generated through the TXdot's topo file.
END DESCRIPTION:
XS GIS Cut Line= 6
  2423656.005413 6975259.9862449 2423174.4397755  6972091.859051
 2423098.6620399 6971952.4134637 2423022.8846324 6971812.9675484
 2422474.5373039 6971531.5150273 2420915.9629932 6968239.1420189
#Sta/Elev= 30
    2807     462    3307  449.63    3583   453.5 4024.62   446.6 4177.12   450.8
 4739.32   452.8 4903.42   448.2 5756.12   448.4 6006.02   447.1 6029.82   444.3
 6032.72  439.46 6047.22   439.8 6063.82   430.8 6141.52   419.2 6176.42   423.7
 6201.42     421 6237.12  409.88 6278.62   414.1 6303.32     435 6350.22   442.4
6353.921   442.9 7292.62   439.2 8270.82   441.3 8334.92   436.7 8605.92     440
 8939.92   451.7 8974.52   449.2 9065.82     465 9128.12   469.210587.26  466.36
#Mann= 4 ,-1,0
    2807     .07       0 5756.12    .075       0 6032.72     .05       0
6353.921    .075       0
#XS Ineff= 2 , 0
       0 3393.12  482.33 9422.26       0  488.86
Permanent Ineff=
       F       F
Bank Sta=6032.72,6350.22
XS Rating Curve= 0 ,0
Exp/Cntr=0.5,0.3

Type RM Length L Ch R = 3 ,57370   ,,,
BEGIN DESCRIPTION:
SH 161
---------------------
CDC GP011404-1 SH 161
---------------------
END DESCRIPTION:
Node Name=SH 161
Bridge Culvert--1,0,-1,-1, 0
Deck Dist Width WeirC Skew NumUp NumDn MinLoCord MaxHiCord MaxSubmerge Is_Ogee
47,166,2.6,0, 57, 57, , , 0.95, 0, 3,3,,
 1179.12 3430.12 3430.12 3525.12 3641.12 3757.12 3872.12 3982.12 4092.12 4202.12
 4312.12 4422.12 4532.12 4637.12 4747.12 4857.12 4967.12 5077.12 5187.12 5307.12
 5427.12 5547.12 5667.12 5787.12 5907.12 6107.12 6327.12 6527.12 6647.12 6767.12
 6887.12 7007.12 7127.12 7247.12 7367.12 7487.12 7595.26 7715.26 7835.26 7955.26
 8075.26 8176.26 8277.26 8377.26 8477.26 8577.26 8677.26 8777.26 8877.26 8977.26
 9077.26 9177.26 9285.26    9335 9387.26 9387.2610587.26
  494.14  482.33  482.33  482.16  481.56  480.52  479.04  477.28  475.13  473.17
  471.11  469.17  467.76  466.94  466.65  466.93  467.51   468.1  468.69  469.33
  469.97  470.61  471.25   471.9  472.54  473.61  474.78  475.85  476.49  477.13
  477.77  478.41  479.06   479.7  480.34  480.98  481.56   482.2  482.84  483.48
  484.12  484.66   485.2  485.74  486.27   486.8  487.34  487.87  488.41  488.94
  489.42  489.58   489.4  488.86  488.86  488.86  488.86
       0       0  472.33  472.04  471.44   470.4  468.95  467.16  465.01  463.05
  460.99  459.05  457.64  456.82  456.53  456.81  457.39  457.98  458.57  459.21
  459.85  460.49  461.13  461.98  458.92  459.99  461.16  462.23  466.37  467.01
  467.65  468.29  468.94  469.58  470.22  470.86  471.44  472.08  472.72  473.36
     474  474.54  475.08  475.62  476.15  476.68  477.22  477.75  478.29  478.82
   479.3  479.46  479.28  478.74  478.74       0       0
 1179.12 3430.12 3430.12 3525.12 3641.12 3757.12 3872.12 3982.12 4092.12 4202.12
 4312.12 4422.12 4532.12 4637.12 4747.12 4857.12 4967.12 5077.12 5187.12 5307.12
 5427.12 5547.12 5667.12 5787.12 5907.12 6107.12 6327.12 6527.12 6647.12 6767.12
 6887.12 7007.12 7127.12 7247.12 7367.12 7487.12 7595.26 7715.26 7835.26 7955.26
 8075.26 8176.26 8277.26 8377.26 8477.26 8577.26 8677.26 8777.26 8877.26 8977.26
 9077.26 9177.26 9285.26    9335 9387.26 9387.2610587.26
  494.14  482.33  482.33  482.16  481.56  480.52  479.04  477.28  475.13  473.17
  471.11  469.17  467.76  466.94  466.65  466.93  467.51   468.1  468.69  469.33
  469.97  470.61  471.25   471.9  472.54  473.61  474.78  475.85  476.49  477.13
  477.77  478.41  479.06   479.7  480.34  480.98  481.56   482.2  482.84  483.48
  484.12  484.66   485.2  485.74  486.27   486.8  487.34  487.87  488.41  488.94
  489.42  489.58   489.4  488.86  488.86  488.86  488.86
       0       0  472.33  472.04  471.44   470.4  468.95  467.16  465.01  463.05
  460.99  459.05  457.64  456.82  456.53  456.81  457.39  457.98  458.57  459.21
  459.85  460.49  461.13  461.98  458.92  459.99  461.16  462.23  466.37  467.01
  467.65  468.29  468.94  469.58  470.22  470.86  471.44  472.08  472.72  473.36
     474  474.54  475.08  475.62  476.15  476.68  477.22  477.75  478.29  478.82
   479.3  479.46  479.28  478.74  478.74       0       0
Pier Skew, UpSta & Num, DnSta & Num=  ,3525.12, 2 ,3525.12, 2 , 0 , 0 , 0 ,,
       4       4
     440  482.33
       4       4
     440  482.33
Pier Skew, UpSta & Num, DnSta & Num=  ,3641.12, 2 ,3641.12, 2 , 0 , 0 , 0 ,,
       4       4
     440  482.33
       4       4
     440  482.33
Pier Skew, UpSta & Num, DnSta & Num=  ,3757.12, 2 ,3757.12, 2 , 0 , 0 , 0 ,,
       4       4
     440  482.33
       4       4
     440  482.33
Pier Skew, UpSta & Num, DnSta & Num=  ,3872.12, 2 ,3872.12, 2 , 0 , 0 , 0 ,,
       4       4
     440  482.33
       4       4
     440  482.33
Pier Skew, UpSta & Num, DnSta & Num=  ,3982.12, 2 ,3982.12, 2 , 0 , 0 , 0 ,,
       4       4
     440  482.33
       4       4
     440  482.33
Pier Skew, UpSta & Num, DnSta & Num=  ,4092.12, 2 ,4092.12, 2 , 0 , 0 , 0 ,,
       4       4
     440  482.33
       4       4
     440  482.33
Pier Skew, UpSta & Num, DnSta & Num=  ,4202.12, 2 ,4202.12, 2 , 0 , 0 , 0 ,,
       4       4
     440  482.33
       4       4
     440  482.33
Pier Skew, UpSta & Num, DnSta & Num=  ,4312.12, 2 ,4312.12, 2 , 0 , 0 , 0 ,,
       4       4
     440  482.33
       4       4
     440  482.33
Pier Skew, UpSta & Num, DnSta & Num=  ,4422.12, 2 ,4422.12, 2 , 0 , 0 , 0 ,,
       4       4
     440  482.33
       4       4
     440  482.33
Pier Skew, UpSta & Num, DnSta & Num=  ,4532.12, 2 ,4532.12, 2 , 0 , 0 , 0 ,,
       4       4
     440  482.33
       4       4
     440  482.33
Pier Skew, UpSta & Num, DnSta & Num=  ,4632.12, 2 ,4632.12, 2 , 0 , 0 , 0 ,,
       4       4
     440  482.33
       4       4
     440  482.33
Pier Skew, UpSta & Num, DnSta & Num=  ,4747.12, 2 ,4747.12, 2 , 0 , 0 , 0 ,,
       4       4
     440  479.46
       4       4
     440  479.46
Pier Skew, UpSta & Num, DnSta & Num=  ,4857.12, 2 ,4857.12, 2 , 0 , 0 , 0 ,,
       4       4
     440  482.33
       4       4
     440  482.33
Pier Skew, UpSta & Num, DnSta & Num=  ,4967.12, 2 ,4967.12, 2 , 0 , 0 , 0 ,,
       4       4
     440  482.33
       4       4
     440  482.33
Pier Skew, UpSta & Num, DnSta & Num=  ,5077.12, 2 ,5077.12, 2 , 0 , 0 , 0 ,,
       4       4
     440  482.33
       4       4
     440  482.33
Pier Skew, UpSta & Num, DnSta & Num=  ,5187.12, 2 ,5187.12, 2 , 0 , 0 , 0 ,,
       4       4
     440  482.33
       4       4
     440  482.33
Pier Skew, UpSta & Num, DnSta & Num=  ,5307.12, 2 ,5307.12, 2 , 0 , 0 , 0 ,,
       4       4
     440  479.46
       4       4
     440  479.46
Pier Skew, UpSta & Num, DnSta & Num=  ,5427.12, 2 ,5427.12, 2 , 0 , 0 , 0 ,,
       8       8
     440  482.33
       8       8
     440  482.33
Pier Skew, UpSta & Num, DnSta & Num=  ,5547.12, 2 ,5547.12, 2 , 0 , 0 , 0 ,,
       8       8
     440  482.33
       8       8
     440  482.33
Pier Skew, UpSta & Num, DnSta & Num=  ,5667.12, 2 ,5667.12, 2 , 0 , 0 , 0 ,,
       8       8
     440  482.33
       8       8
     440  482.33
Pier Skew, UpSta & Num, DnSta & Num=  ,5787.12, 2 ,5787.12, 2 , 0 , 0 , 0 ,,
       8       8
     440  482.33
       8       8
     440  482.33
Pier Skew, UpSta & Num, DnSta & Num=  ,5907.12, 2 ,5907.12, 2 , 0 , 0 , 0 ,,
       8       8
     440  482.33
       8       8
     440  482.33
Pier Skew, UpSta & Num, DnSta & Num=  ,6107.12, 2 ,6107.12, 2 , 0 , 0 , 0 ,,
       8       8
     440  482.33
       8       8
     440  482.33
Pier Skew, UpSta & Num, DnSta & Num=  ,6327.12, 2 ,6327.12, 2 , 0 , 0 , 0 ,,
       8       8
     440  482.33
       8       8
     440  482.33
Pier Skew, UpSta & Num, DnSta & Num=  ,6527.12, 2 ,6527.12, 2 , 0 , 0 , 0 ,,
       8       8
     440  482.33
       8       8
     440  482.33
Pier Skew, UpSta & Num, DnSta & Num=  ,6647.12, 2 ,6647.12, 2 , 0 , 0 , 0 ,,
       8       8
     440  482.33
       8       8
     440  482.33
Pier Skew, UpSta & Num, DnSta & Num=  ,6767.12, 2 ,6767.12, 2 , 0 , 0 , 0 ,,
       8       8
     440  482.33
       8       8
     440  482.33
Pier Skew, UpSta & Num, DnSta & Num=  ,6887.12, 2 ,6887.12, 2 , 0 , 0 , 0 ,,
       8       8
     440  482.33
       8       8
     440  482.33
Pier Skew, UpSta & Num, DnSta & Num=  ,7007.12, 2 ,7007.12, 2 , 0 , 0 , 0 ,,
       4       4
     440  482.33
       4       4
     440  482.33
Pier Skew, UpSta & Num, DnSta & Num=  ,7127.12, 2 ,7127.12, 2 , 0 , 0 , 0 ,,
       4       4
     440  482.33
       4       4
     440  482.33
Pier Skew, UpSta & Num, DnSta & Num=  ,7247.12, 2 ,7247.12, 2 , 0 , 0 , 0 ,,
       4       4
     440  482.33
       4       4
     440  482.33
Pier Skew, UpSta & Num, DnSta & Num=  ,7367.12, 2 ,7367.12, 2 , 0 , 0 , 0 ,,
       4       4
     440  482.33
       4       4
     440  482.33
Pier Skew, UpSta & Num, DnSta & Num=  ,7487.12, 2 ,7487.12, 2 , 0 , 0 , 0 ,,
       4       4
     440  482.33
       4       4
     440  482.33
Pier Skew, UpSta & Num, DnSta & Num=  ,7595.26, 2 ,7595.26, 2 , 0 , 0 , 0 ,,
       4       4
     440  482.33
       4       4
     440  482.33
Pier Skew, UpSta & Num, DnSta & Num=  ,7715.26, 2 ,7715.26, 2 , 0 , 0 , 0 ,,
       4       4
     440  482.33
       4       4
     440  482.33
Pier Skew, UpSta & Num, DnSta & Num=  ,7835.26, 2 ,7835.26, 2 , 0 , 0 , 0 ,,
       4       4
     440  482.33
       4       4
     440  482.33
Pier Skew, UpSta & Num, DnSta & Num=  ,7955.26, 2 ,7955.26, 2 , 0 , 0 , 0 ,,
       4       4
     440  482.33
       4       4
     440  482.33
Pier Skew, UpSta & Num, DnSta & Num=  ,8075.26, 2 ,8075.26, 2 , 0 , 0 , 0 ,,
       4       4
     440  482.33
       4       4
     440  482.33
Pier Skew, UpSta & Num, DnSta & Num=  ,8176.26, 2 ,8176.26, 2 , 0 , 0 , 0 ,,
       4       4
     440  482.33
       4       4
     440  482.33
Pier Skew, UpSta & Num, DnSta & Num=  ,8277.26, 2 ,8277.26, 2 , 0 , 0 , 0 ,,
       4       4
     440  482.33
       4       4
     440  482.33
Pier Skew, UpSta & Num, DnSta & Num=  ,8377.26, 2 ,8377.26, 2 , 0 , 0 , 0 ,,
       4       4
     440  482.33
       4       4
     440  482.33
Pier Skew, UpSta & Num, DnSta & Num=  ,8477.26, 2 ,8477.26, 2 , 0 , 0 , 0 ,,
       4       4
     440  482.33
       4       4
     440  482.33
Pier Skew, UpSta & Num, DnSta & Num=  ,8577.26, 2 ,8577.26, 2 , 0 , 0 , 0 ,,
       4       4
     440  482.33
       4       4
     440  482.33
Pier Skew, UpSta & Num, DnSta & Num=  ,8677.26, 2 ,8677.26, 2 , 0 , 0 , 0 ,,
       4       4
     440  482.33
       4       4
     440  482.33
Pier Skew, UpSta & Num, DnSta & Num=  ,8777.26, 2 ,8777.26, 2 , 0 , 0 , 0 ,,
       4       4
     440  482.33
       4       4
     440  482.33
Pier Skew, UpSta & Num, DnSta & Num=  ,8877.26, 2 ,8877.26, 2 , 0 , 0 , 0 ,,
       4       4
     440  482.33
       4       4
     440  482.33
Pier Skew, UpSta & Num, DnSta & Num=  ,8977.26, 2 ,8977.26, 2 , 0 , 0 , 0 ,,
       4       4
     440  482.33
       4       4
     440  482.33
Pier Skew, UpSta & Num, DnSta & Num=  ,9077.26, 2 ,9077.26, 2 , 0 , 0 , 0 ,,
       4       4
     440  482.33
       4       4
     440  482.33
Pier Skew, UpSta & Num, DnSta & Num=  ,9177.26, 2 ,9177.26, 2 , 0 , 0 , 0 ,,
       4       4
     440  482.33
       4       4
     440  482.33
Pier Skew, UpSta & Num, DnSta & Num=  ,9282.26, 2 ,9282.26, 2 , 0 , 0 , 0 ,,
       4       4
     440  482.33
       4       4
     440  482.33
Abutment Skew #Up #Dn= , 2 , 2
 3430.12    3465
  482.33     440
 3430.12    3465
  482.33     440
Abutment Skew #Up #Dn= , 2 , 2
    9335 9387.26
     440  488.86
    9335 9387.26
     440  488.86
BR Coef=-1 , 1 , 1 ,0.9, 0 ,,,0.8,-1,1.33,0,
WSPro=,,,, 1 ,,,, 0 ,,,, 0 ,,,,-1 ,-1 ,-1 , 0 , 0 , 0 , 0 , 0
BC Design=,, 0 ,, 0 ,,,,,,
BC Use User HTab Curves=0
BC User HTab FreeFlow(D)= 0

Type RM Length L Ch R = 1 ,57287   ,926,204,183
BEGIN DESCRIPTION:
This cross section corresponds to cross section 57303 of the non-georeferenced CDC model which was the source of this model.
Downstream bounding cross-section.
Copied from cross-section 57586
END DESCRIPTION:
XS GIS Cut Line= 6
  2424208.296303 6974983.5566797 2423436.3326244 6971871.1475502
 2423312.4001295 6971772.0109374 2423188.4676346 6971672.8743247
 2422592.5928421 6971377.8693372 2420957.5370571  6968184.162142
#Sta/Elev= 30
    2807     462    3307  449.63    3583   453.5 4024.62   446.6 4177.12   450.8
 4739.32   452.8 4903.42   448.2 5756.12   448.4 6006.02   447.1 6029.82   444.3
 6032.72  439.46 6047.22   439.8 6063.82   430.8 6141.52   419.2 6176.42   423.7
 6201.42     421 6237.12  409.88 6278.62   414.1 6303.32     435 6350.22   442.4
6353.921   442.9 7292.62   439.2 8270.82   441.3 8334.92   436.7 8605.92     440
 8939.92   451.7 8974.52   449.2 9065.82     465 9128.12   469.210587.26  466.36
#Mann= 4 ,-1,0
    2807     .07       0 5756.12    .075       0 6032.72     .05       0
6353.921    .075       0
#XS Ineff= 2 , 0
       0 3393.12  482.33 9422.26       0  488.86
Permanent Ineff=
       F       F
Bank Sta=6032.72,6350.22
XS Rating Curve= 0 ,0
Exp/Cntr=0.5,0.3