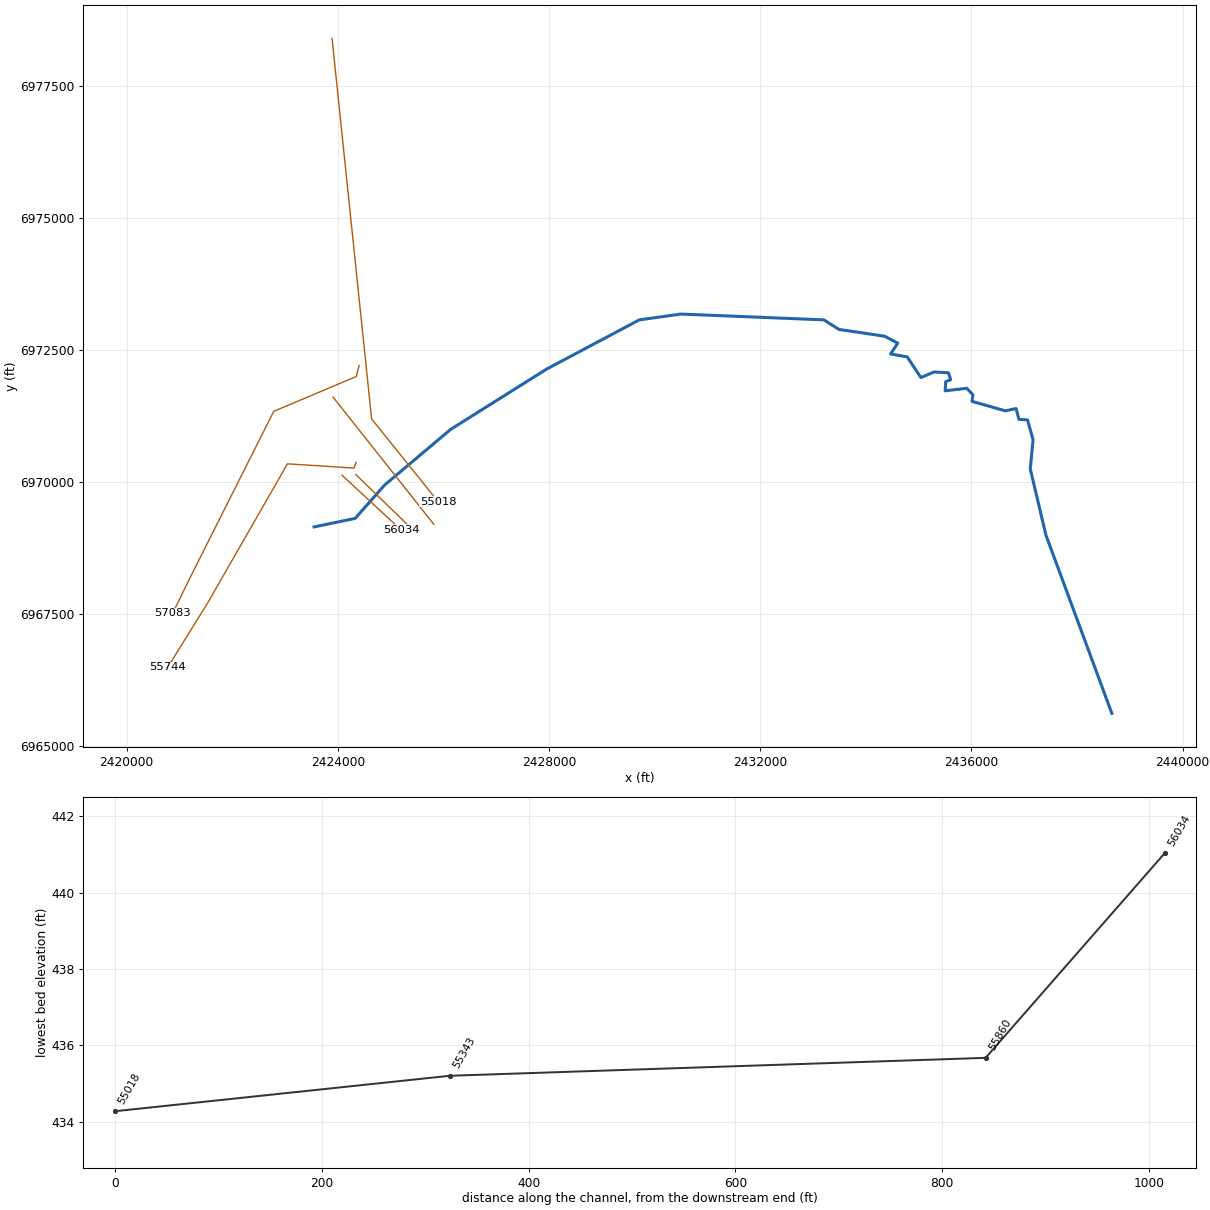
HEC-RAS study CDC_Consolidated_Model.prj: Upper Trinity CDC Consolidated Model

--- CDC_Consolidated_Model.g01 (geometry) --- (continued)

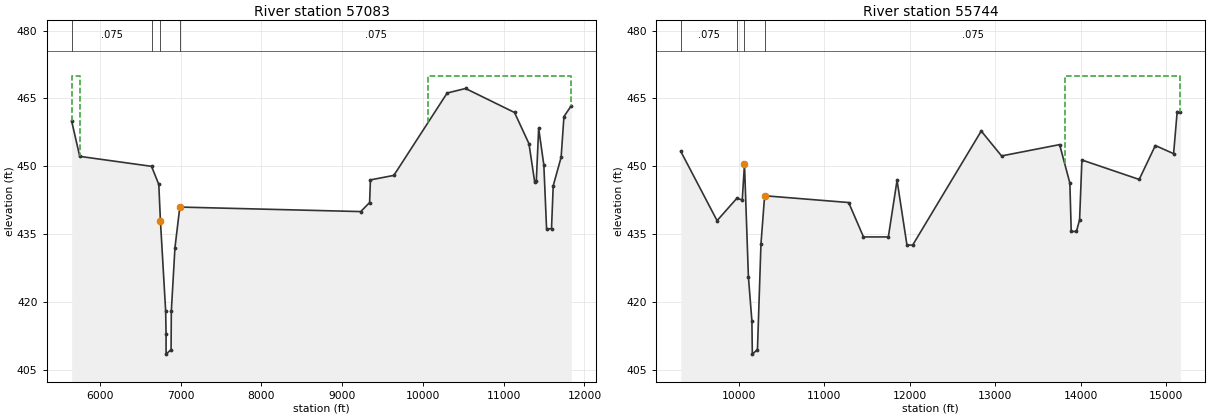
Type RM Length L Ch R = 1 ,57083   ,650,1339,650
BEGIN DESCRIPTION:
This cross section corresponds to cross section 57099 of the non-georeferenced CDC model which was the source of this model.
END DESCRIPTION:
XS GIS Cut Line= 6
2424402.77116189 6972201.5633654 2424348.9889356 6971991.3389108
 2422785.3798581 6971331.7588652 2422013.6714278 6969797.2963829
 2421241.8878663 6968262.8526014 2420871.5818484 6967508.9764845
#Sta/Elev= 30
    5651     460    5751   452.2    6640     450    6730     446    6750     438
    6815     418    6820     413    6820   408.5    6882   409.5    6885     418
    6930     432    6990     441    9230     440    9340     442    9350     447
    9640     448   10300   466.2   10528   467.2   11134   461.9   11313     455
   11384   446.5   11404   446.8   11433   458.4   11497   450.3   11531   436.2
   11592   436.2   11613   445.7   11711     452   11746     461   11837   463.4
#Mann= 4 ,-1,0
    5651    .075       0    6640     .12       0    6750     .05       0
    6990    .075       0
#XS Ineff= 4 ,-1
   10060   11837     470    5651    5751     470    6990   10060     441
    5751    6750     438
Permanent Ineff=
       F       F       F       F
Bank Sta=6750,6990
XS Rating Curve= 0 ,0
Exp/Cntr=0.3,0.1

Type RM Length L Ch R = 1 ,55744   ,0,0,0
BEGIN DESCRIPTION:
This cross section corresponds to cross section 55761 of the non-georeferenced CDC model which was the source of this model.
END DESCRIPTION:
XS GIS Cut Line= 6
  2424345.492879  6970366.043605 2424303.4358771 6970257.6930999
 2423045.2090628 6970337.7700395 2422241.3379672 6968935.5973189
  2421531.980462  6967698.403271 2420774.6634071 6966480.1438965
#Sta/Elev= 30
    9318   453.3    9743     438    9973   442.9   10038   442.6   10064   450.5
   10110   425.6   10151   415.8   10156   408.5   10216   409.5   10257   432.8
   10300   443.5   11284     442   11458   434.4   11749   434.4   11851   446.9
   11967   432.6   12034   432.6   12837   457.8   13075   452.3   13755   454.8
   13875   446.3   13891   435.6   13952   435.6   13989   438.2   14016   451.4
   14687   447.1   14876   454.6   15090   452.8   15132   462.1   15170   461.9
#Mann= 4 ,-1,0
    9318    .075       0    9973     .12       0   10064     .05       0
   10300    .075       0
#XS Ineff= 3 ,-1
   13816   15170     470   10300   13816     441    9318   10064     441
Permanent Ineff=
       F       F       F
Bank Sta=10064,10300
XS Rating Curve= 0 ,0
Exp/Cntr=0.3,0.1

River Reach=West Fork Split ,wfs
Reach XY= 30
      2423548.65      6969142.43      2424328.33      6969304.48
      2424884.32       6969934.5      2426135.87      6970989.99
      2427952.18      6972131.21      2429709.24      6973064.19
       2430496.5       6973174.4      2433207.03      6973064.51
      2433491.54      6972883.52      2434356.44        6972755.
      2434605.27      6972622.64      2434468.97      6972419.33
      2434784.65      6972362.14       2435043.7      6971972.11
      2435290.33       6972077.3      2435565.25      6972061.98
      2435607.22      6971930.23      2435513.06      6971894.13
      2435503.28      6971720.76      2435911.65      6971768.86
      2436029.27      6971643.43      2436010.53      6971521.14
      2436642.57      6971341.07       2436847.2      6971385.03
      2436899.94      6971179.472437062.405932366971170.73997248
2437168.014923466970795.828054062437115.210427916970241.38085076
  2437410.9156036968989.91430618        2438660.      6965610.97

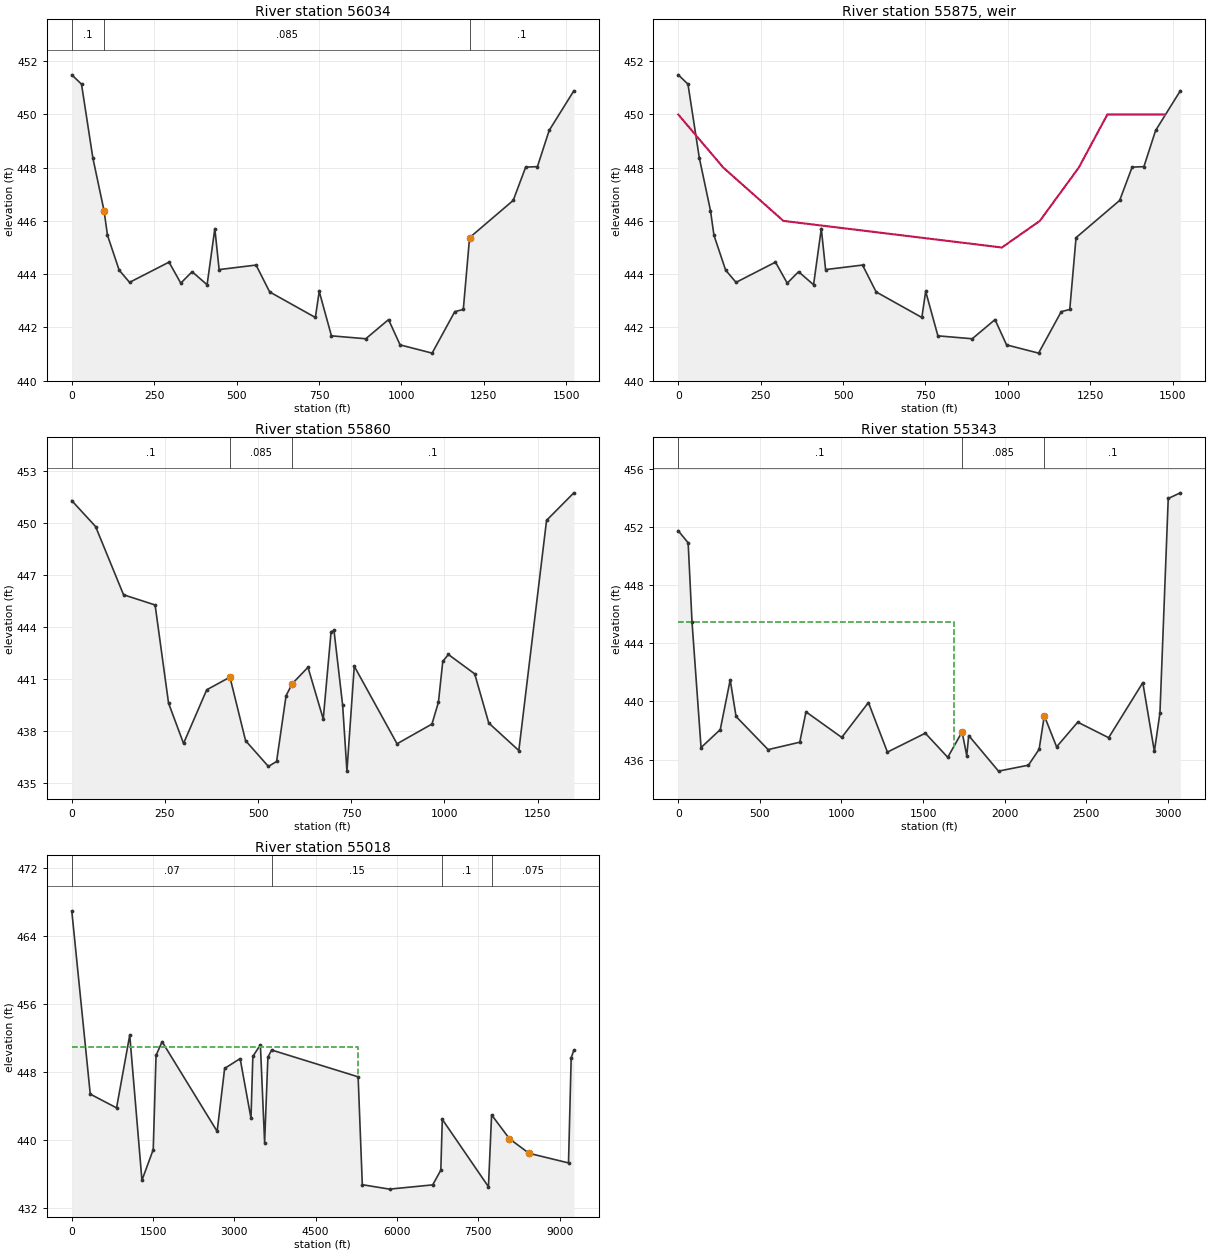
Type RM Length L Ch R = 1 ,56034   ,173,173,173
BEGIN DESCRIPTION:
This cross section corresponds to cross section 54405 of the non-georeferenced CDC model which was the source of this model.
END DESCRIPTION:
XS GIS Cut Line= 3
  2424080.305536 6970120.6975978     2424195.808     6970013.706
     2425197.768     6969085.576
#Sta/Elev= 30
       0  451.49   29.53  451.14   63.92  448.37    97.8  446.39  108.36  445.46
  143.75  444.15  175.36  443.69  295.04  444.45   330.7  443.66  365.07  444.09
  410.58   443.6  434.04  445.71  447.06  444.17  559.15  444.34  600.43  443.33
  739.05  442.37  750.72  443.35  787.79  441.68  891.94  441.57  961.05  442.29
   996.1  441.34 1093.24  441.03 1162.02  442.59 1187.84  442.67 1206.87  445.37
 1339.25  446.77 1377.03  448.02 1412.76  448.04 1448.34   449.4 1523.22  450.89
#Mann= 3 ,0,0
       0      .1       0    97.8    .085       0 1206.87      .1       0
Bank Sta=97.8,1206.87
XS Rating Curve= 0 ,0
Exp/Cntr=0.3,0.1

Type RM Length L Ch R = 5 ,55875   ,,,
BEGIN DESCRIPTION:
Hardrock Road - Weir
SPLIT FLOW FOR 50YR AND 100 YR
END DESCRIPTION:
Node Name=Hardrock Road -
IW Pilot Flow=0
#Inline Weir SE= 8
       0     450     137     448     319     446     982     445    1097     446
    1215     448    1302     450 1475.74     450
IW Dist,WD,Coef,Skew,MaxSub,Min_El,Is_Ogee,SpillHt,DesHd
40,30,2.6,0,0.95,, 0 ,,,10,10,
Inline Weir Flap Gates= 0
IW Outlet Rating Curve= 0 ,False,,

Type RM Length L Ch R = 1 ,55860   ,605,518,314
BEGIN DESCRIPTION:
This cross section corresponds to cross section 54255 of the non-georeferenced CDC model which was the source of this model.
END DESCRIPTION:
XS GIS Cut Line= 2
  2424339.916966 6970134.7280418 2425306.7890336 6969196.5739583
#Sta/Elev= 30
       0   451.3   63.95   449.8  138.92  445.86  223.62  445.27  259.69   439.6
  299.88  437.27  362.15  440.37  424.42   441.1  466.36  437.43  527.66  435.94
  549.61  436.23  575.04  440.03  591.54  440.72   633.8  441.67  674.79  438.68
  695.76  443.72   703.6   443.8  726.84  439.48  738.33  435.67  758.03  441.73
  872.81  437.25  966.45  438.39  983.84  439.65  995.52  442.01 1010.56  442.41
 1081.17  441.29 1118.92  438.45  1199.6  436.86 1273.99  450.16 1347.21  451.75
#Mann= 3 ,0,0
       0      .1       0  424.42    .085       0  591.54      .1       0
Bank Sta=424.42,591.54
XS Rating Curve= 0 ,0
Exp/Cntr=0.3,0.1

Type RM Length L Ch R = 1 ,55343   ,648,324,97
BEGIN DESCRIPTION:
This cross section corresponds to cross section 53930 of the non-georeferenced CDC model which was the source of this model.
END DESCRIPTION:
XS GIS Cut Line= 4
     2423907.631     6971603.114      2424119.38      6971335.78
      2425605.44      6969459.63     2425817.189     6969192.296
#Sta/Elev= 30
       0  451.74   60.72  450.91   84.31  445.48  139.79  436.82   257.5  438.06
  318.31  441.48  354.23  438.96  550.71  436.68   744.4  437.19  782.56  439.28
 1001.52  437.52 1164.97  439.92 1281.33  436.51 1513.55  437.81 1650.86  436.15
 1738.63   437.9  1767.4  436.26 1779.17  437.65 1961.81   435.2 2145.22  435.61
 2210.72  436.71 2242.41  439.01 2317.69  436.87 2447.17  438.57 2636.52   437.5
 2845.75  441.29 2916.52  436.56 2950.71   439.2 3001.47  453.96 3075.46  454.35
#Mann= 3 ,0,0
       0      .1       0 1738.63    .085       0 2242.41      .1       0
#XS Ineff= 2 , 0
       0    1687  445.45               0
Permanent Ineff=
       T       F
Bank Sta=1738.63,2242.41
XS Rating Curve= 0 ,0
Exp/Cntr=0.3,0.1

Type RM Length L Ch R = 1 ,55018   ,424,424,424
BEGIN DESCRIPTION:
This cross section corresponds to cross section 53730 of the non-georeferenced CDC model which was the source of this model.
END DESCRIPTION:
XS GIS Cut Line= 4
  2423889.955486 6978397.0338837  2424011.140298 6977231.3579531
       2424639.5      6971187.17      2425902.66      6969617.52
#Sta/Elev= 30
       0  466.98  340.87  445.44  826.31  443.82 1069.55  452.37 1294.81  435.31
 1503.16  438.92 1554.98  449.99 1666.57   451.6 2682.26  441.06 2820.77  448.46
 3106.31  449.61 3306.64   442.6 3341.01  449.87 3480.05  451.23 3558.14  439.73
 3618.57  449.78 3687.83  450.62 5283.42  447.47 5360.69  434.79 5862.92  434.27
 6658.89  434.77 6809.23   436.5 6836.28  442.47 7687.99  434.55 7746.08     443
 8075.38  440.19 8437.37  438.48 9165.09  437.35  9214.4   449.7 9263.51  450.61
#Mann= 4 ,-1,0
       0     .07       0 3687.83     .15       0 6836.28      .1       0
 7746.08    .075       0
#XS Ineff= 3 ,-1
       0    5283     451    5283 8075.38  440.19 8437.37 9263.51  438.48
Permanent Ineff=
       T       F       F
Bank Sta=8075.38,8437.37
XS Rating Curve= 0 ,0
Exp/Cntr=0.3,0.1