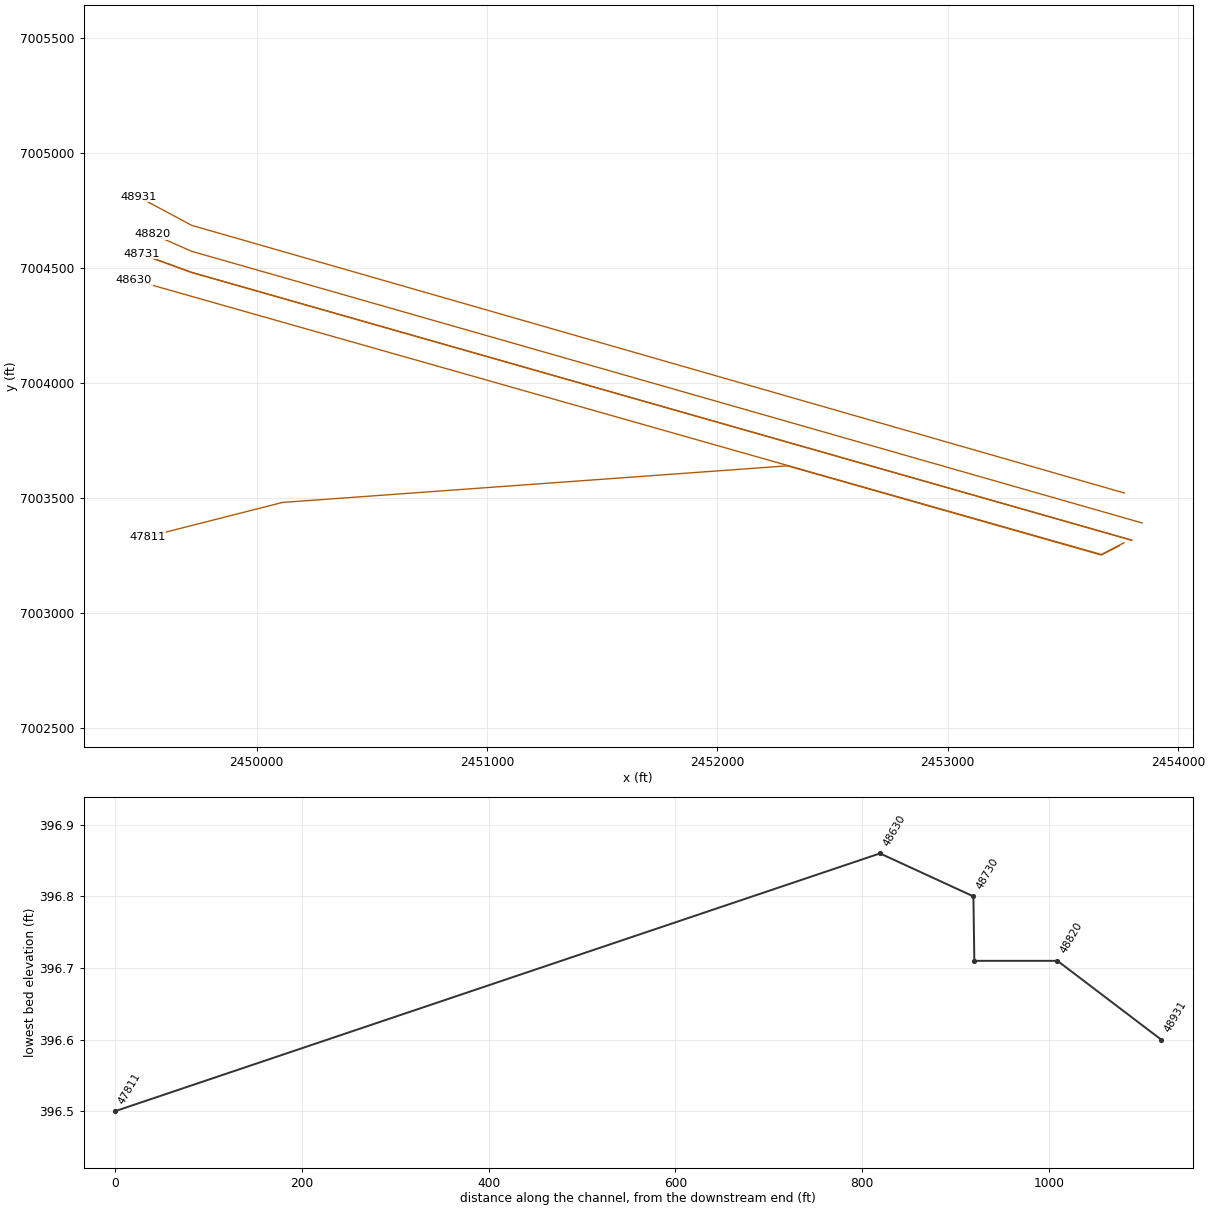
HEC-RAS study CDC_Consolidated_Model.prj: Upper Trinity CDC Consolidated Model

--- CDC_Consolidated_Model.g01 (geometry) --- (continued)

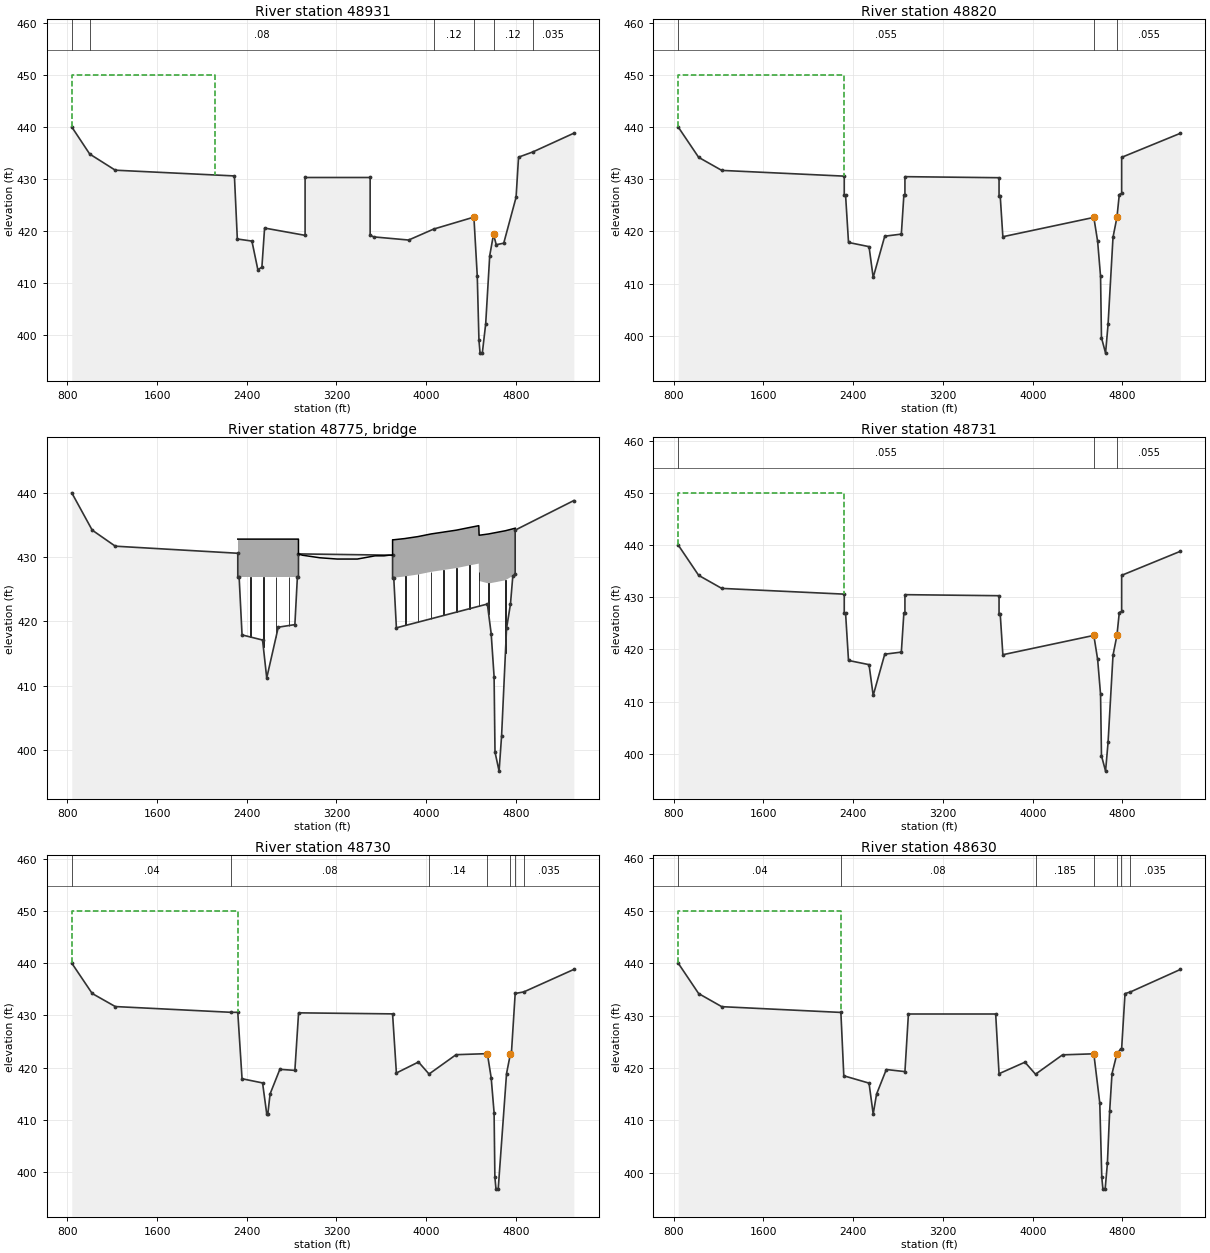
Type RM Length L Ch R = 1 ,48931   ,111,111,111
BEGIN DESCRIPTION:
This cross section corresponds to cross section 48911 of the non-georeferenced CDC model which was the source of this model.
Cross-section EF065.  111 feet upstream of SH 348/Northwest Highway. Conveyance blocked from sta 2920 - 3500 due to roadway. Effective flow limit set at sta 2120 in LOB, at Las Colinas Levee in ROB. Stemmons North Industrial District east of Luna Road in LOB.
Channel data from COD Elm Fork channel survey.
END DESCRIPTION:
XS GIS Cut Line= 3
2453766.362840837003523.163969132449718.07598993 7004687.1859193
2449485.64075926 7004811.7053553
#Sta/Elev= 30
     840     440    1000   434.8    1228   431.7    2290   430.6    2316   418.5
    2446   418.1    2499   412.6    2535   413.1    2559   420.6    2920   419.2
    2920   430.3    3500   430.3    3500   419.2    3533   418.9    3843   418.3
    4066   420.4    4425   422.7    4455   411.4    4470   399.1    4480   396.6
    4500   396.6    4530   402.2    4566   415.3    4600   419.4    4624   417.4
    4691   417.7    4801   426.5    4823   434.2    4950   435.2    5316   438.8
#Mann= 6 ,-1,0
     840      .1       0    1000     .08       0    4066     .12       0
    4425     .05       0    4600     .12       0    4950    .035       0
#XS Ineff= 3 ,-1
     840    2120     450    2120    4425   422.7    4600    5316   419.4
Permanent Ineff=
       F       F       F
Bank Sta=4425,4600
XS Rating Curve= 0 ,0
Exp/Cntr=0.3,0.1

Type RM Length L Ch R = 1 ,48820   ,89,89,89
BEGIN DESCRIPTION:
This cross section corresponds to cross section 48801 of the non-georeferenced CDC model which was the source of this model.
END DESCRIPTION:
XS GIS Cut Line= 3
2453843.513605187003392.909636472449717.273498097004574.50438613
2449548.940173337004648.58068155
#Sta/Elev= 30
     840     440    1022   434.2    1228   431.7    2320   430.6    2320   426.9
    2332   426.9    2358   417.9    2541   417.1    2578   411.2    2681   419.1
    2829   419.5  2851.3   426.9    2861   426.9    2861   430.5    3700   430.3
    3700   426.8  3710.5   426.8    3734     419    4545   422.7    4579   418.1
    4605   411.4  4613.1  399.68  4649.6  396.71  4671.9  402.21    4716   418.9
    4751   422.7    4772  427.08    4793   427.3    4793   434.2    5316   438.8
#Mann= 3 ,0,0
     840    .055       0    4545     .05       0    4751    .055       0
#XS Ineff= 3 ,-1
     840    2320     450    2320    4545   422.7    4751    5616   422.7
Permanent Ineff=
       F       F       F
Bank Sta=4545,4751
XS Rating Curve= 0 ,0
Exp/Cntr=0.5,0.3

Type RM Length L Ch R = 3 ,48775   ,,,
BEGIN DESCRIPTION:
SH 348/Northwest Highway
END DESCRIPTION:
Node Name=Northwest Highwa
Bridge Culvert--1,0,-1,-1, 0
Deck Dist Width WeirC Skew NumUp NumDn MinLoCord MaxHiCord MaxSubmerge Is_Ogee
2,86,2.6,0, 41, 41, , , 0.95, 0, ,,,
    2320    2431    2437    2545    2551    2659    2665    2773    2779    2861
    2861    2895    3050    3206    3386    3544    3623    3670    3700    3700
  3710.5    3811    3817    3925    3931    4039    4045    4153    4159    4267
    4273    4381    4387  4468.5  4471.5  4554.5  4557.5  4704.5  4707.5    4772
    4793
   432.8   432.8   432.8   432.8   432.8   432.8   432.8   432.8   432.8   432.8
   430.5   430.3   429.9   429.7   429.7   430.2   430.2   430.3   430.3   432.7
   432.7  432.89  432.91  433.19  433.21  433.59  433.61  433.89  433.91  434.19
  434.21  434.59  434.61  434.89   433.4   433.6  433.61   434.1  434.11   434.4
   434.5
   426.9   426.9   426.9   426.9   426.9   426.9   426.9   426.9   426.9   426.9
   430.5   430.3   429.9   429.7   429.7   430.2   430.2   430.3   430.3   426.8
   426.8  426.99  427.01  427.29  427.31  427.69  427.71  427.99  428.01  428.29
  428.31  428.69  428.71  428.99  426.29  425.91   425.9  426.39  426.42  427.08
   427.3
    2320    2431    2437    2545    2551    2659    2665    2773    2779    2861
    2861    2895    3050    3206    3386    3544    3623    3670    3700    3700
  3710.5    3811    3817    3925    3931    4039    4045    4153    4159    4267
    4273    4381    4387  4468.5  4471.5  4554.5  4557.5  4704.5  4707.5    4772
    4793
   432.8   432.8   432.8   432.8   432.8   432.8   432.8   432.8   432.8   432.8
   430.5   430.3   429.9   429.7   429.7   430.2   430.2   430.3   430.3   432.7
   432.7  432.89  432.91  433.19  433.21  433.59  433.61  433.89  433.91  434.19
  434.21  434.59  434.61  434.89   433.4   433.6  433.61   434.1  434.11   434.4
   434.5
   426.9   426.9   426.9   426.9   426.9   426.9   426.9   426.9   426.9   426.9
   430.5   430.3   429.9   429.7   429.7   430.2   430.2   430.3   430.3   426.8
   426.8  426.99  427.01  427.29  427.31  427.69  427.71  427.99  428.01  428.29
  428.31  428.69  428.71  428.99  426.29  425.91   425.9  426.39  426.42  427.08
   427.3
Pier Skew, UpSta & Num, DnSta & Num=  ,2434, 2 ,2434, 2 , 0 , 0 , 0 ,,
       6       6
     415     430
       6       6
     415     430
Pier Skew, UpSta & Num, DnSta & Num=  ,2548, 2 ,2548, 2 , 0 , 0 , 0 ,,
       6       6
     415     430
       6       6
     415     430
Pier Skew, UpSta & Num, DnSta & Num=  ,2662, 2 ,2662, 2 , 0 , 0 , 0 ,,
       6       6
     415     430
       6       6
     415     430
Pier Skew, UpSta & Num, DnSta & Num=  ,2776, 2 ,2776, 2 , 0 , 0 , 0 ,,
       6       6
     415     430
       6       6
     415     430
Pier Skew, UpSta & Num, DnSta & Num=  ,3814, 2 ,3814, 2 , 0 , 0 , 0 ,,
       6       6
     410     430
       6       6
     410     430
Pier Skew, UpSta & Num, DnSta & Num=  ,3928, 2 ,3928, 2 , 0 , 0 , 0 ,,
       6       6
     410     430
       6       6
     410     430
Pier Skew, UpSta & Num, DnSta & Num=  ,4042, 2 ,4042, 2 , 0 , 0 , 0 ,,
       6       6
     410     430
       6       6
     410     430
Pier Skew, UpSta & Num, DnSta & Num=  ,4156, 2 ,4156, 2 , 0 , 0 , 0 ,,
       6       6
     410     430
       6       6
     410     430
Pier Skew, UpSta & Num, DnSta & Num=  ,4270, 2 ,4270, 2 , 0 , 0 , 0 ,,
       6       6
     410     430
       6       6
     410     430
Pier Skew, UpSta & Num, DnSta & Num=  ,4384, 2 ,4384, 2 , 0 , 0 , 0 ,,
       6       6
     410     430
       6       6
     410     430
Pier Skew, UpSta & Num, DnSta & Num=  ,4470, 2 ,4470, 2 , 0 , 0 , 0 ,,
       3       3
     410     430
       3       3
     410     430
Pier Skew, UpSta & Num, DnSta & Num=  ,4556, 2 ,4556, 2 , 0 , 0 , 0 ,,
       3       3
     410     430
       3       3
     410     430
Pier Skew, UpSta & Num, DnSta & Num=  ,4706, 2 ,4706, 2 , 0 , 0 , 0 ,,
       3       3
     410     430
       3       3
     410     430
BR Coef= 1 , 0 , 0 ,1.05, 0 ,,,0.8,-1,0.5,1,
WSPro=,,,, 1 ,,,, 0 ,,,, 0 ,,,,-1 ,-1 ,-1 , 0 , 0 , 0 , 0 , 0
BC Design=,, 0 ,, 0 ,,,,,,
BC HTab HWMax=440
BC Use User HTab Curves=0
BC User HTab FreeFlow(D)= 0

Type RM Length L Ch R = 1 ,48731   ,1,1,1
BEGIN DESCRIPTION:
This cross section corresponds to cross section 48712 of the non-georeferenced CDC model which was the source of this model.
END DESCRIPTION:
XS GIS Cut Line= 4
2453798.242698347003318.449483542449716.046138357004483.49931879
2449503.06395274 7004561.47160382449499.307726687004562.84660105
#Sta/Elev= 30
     840     440    1022   434.2    1228   431.7    2320   430.6    2320   426.9
    2332   426.9    2358   417.9    2541   417.1    2578   411.2    2681   419.1
    2829   419.5  2851.3   426.9    2861   426.9    2861   430.5    3700   430.3
    3700   426.8  3710.5   426.8    3734     419    4545   422.7    4579   418.1
    4605   411.4  4613.1  399.68  4649.6  396.71  4671.9  402.21    4716   418.9
    4751   422.7    4772  427.08    4793   427.3    4793   434.2    5316   438.8
#Mann= 3 ,0,0
     840    .055       0    4545     .05       0    4751    .055       0
#XS Ineff= 3 ,-1
     840    2320     450    2320    4545   422.7    4751    5616   422.7
Permanent Ineff=
       F       F       F
Bank Sta=4545,4751
XS Rating Curve= 0 ,0
Exp/Cntr=0.5,0.3

Type RM Length L Ch R = 1 ,48730   ,100,100,100
BEGIN DESCRIPTION:
This cross section corresponds to cross section 48711 of the non-georeferenced CDC model which was the source of this model.
One-foot downstream of SH 348/Northwest Highway.  Stemmons North Industrial District in LOB.  Conveyance blocked from sta 840 - 2320, sta 2862 - 3700.
Channel data from COD Elm Fork channel survey.
END DESCRIPTION:
XS GIS Cut Line= 4
2453797.939221267003317.554144132449716.026781417004482.47832346
2449502.699452167004560.403036392449498.942569917004561.77540897
#Sta/Elev= 30
     840     440    1022   434.2    1228   431.7    2261   430.6    2320   430.6
    2358   417.9    2541   417.1    2578   411.2    2588   411.2    2608     415
    2695   419.7    2829   419.5    2862   430.5    3700   430.3    3734     419
    3931   421.1    4025   418.8    4266   422.5    4545   422.7    4579   418.1
    4605   411.4    4612   399.1    4622   396.8    4642   396.9    4716   418.9
    4751   422.7    4760     423    4793   434.2    4870   434.5    5316   438.8
#Mann= 7 ,-1,0
     840     .04       0    2261     .08       0    4025     .14       0
    4545     .04       0    4751     .12       0    4793     .06       0
    4870    .035       0
#XS Ineff= 3 ,-1
     840    2320     450    2320    4545   422.7    4751    5616   422.7
Permanent Ineff=
       F       F       F
Bank Sta=4545,4751
XS Rating Curve= 0 ,0
Exp/Cntr=0.3,0.1

Type RM Length L Ch R = 1 ,48630   ,600,819,1000
BEGIN DESCRIPTION:
This cross section corresponds to cross section 48610 of the non-georeferenced CDC model which was the source of this model.
Cross-section EF063.  102 feet downstream of SH 348/Northwest Highway. Conveyance blocked from sta 840 - 2290, sta 2892 - 3670 due to roadway.  Stemmons North Industrial District in LOB.
Channel data from COD Elm Fork channel survey - cross-section EF#063 surveyed February 1994.
END DESCRIPTION:
XS GIS Cut Line= 4
 2453764.65516717003306.71722355 2453757.06069417003302.77366188
2453666.417174587003255.705842632449467.509890027004449.46526614
#Sta/Elev= 30
     840     440    1022   434.2    1228   431.7    2290   430.6    2316   418.5
    2541   417.1    2578   411.2    2608     415    2695   419.7    2861   419.3
    2892   430.3    3670   430.3    3700   418.9    3931   421.1    4025   418.8
    4266   422.5    4545   422.7    4598   413.3    4616   399.1    4626  396.86
    4646  396.86    4666   401.8    4686   411.7    4707   418.9    4751   422.7
    4784   423.6    4793   423.7    4823   434.2    4870   434.5    5316   438.8
#Mann= 7 ,-1,0
     840     .04       0    2290     .08       0    4025    .185       0
    4545     .04       0    4751     .12       0    4784     .06       0
    4870    .035       0
#XS Ineff= 3 ,-1
     840    2290     450    2290    4545   422.7    4751    5316   422.7
Permanent Ineff=
       F       F       F
Bank Sta=4545,4751
XS Rating Curve= 0 ,0
Exp/Cntr=0.3,0.1

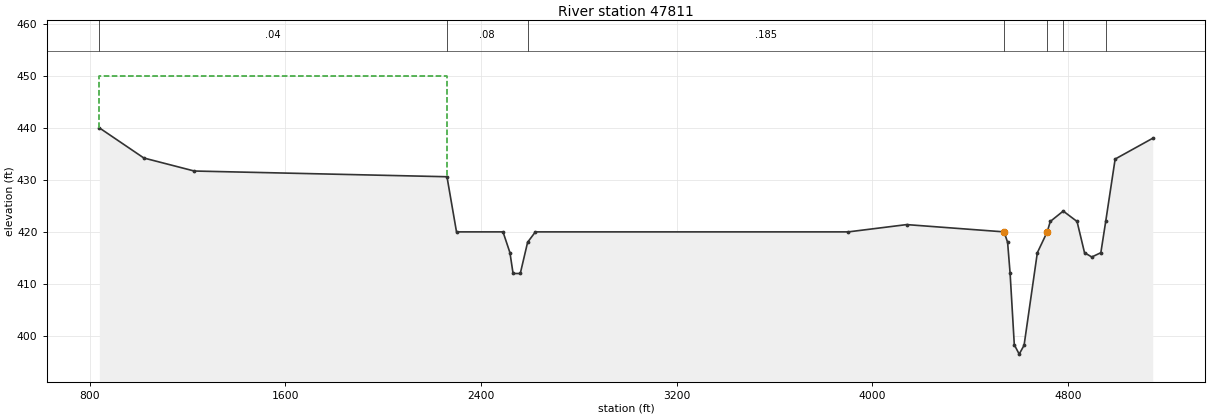
Type RM Length L Ch R = 1 ,47811   ,1200,3446,1000
BEGIN DESCRIPTION:
This cross section corresponds to cross section 47791 of the non-georeferenced CDC model which was the source of this model.
Cross-section generated from topographic file.  Effective flow limit set at sta 2261 in LOB, at Las Colinas Levee in ROB.  Stemmons North Industrial in LOB.
Channel data from COD Elm Fork channel survey.
END DESCRIPTION:
XS GIS Cut Line= 6
2453744.767739687003293.939033882453666.132070187003253.49324863
2452308.200402837003640.129286382452294.250955677003640.68210679
2450112.615883267003482.20703004 2449527.06128017003333.13810247
#Sta/Elev= 30
     840     440    1022   434.2    1228   431.7    2261   430.6    2300     420
    2490     420  2518.4     416  2531.2     412  2560.6     412  2590.6     418
  2622.4     420  3901.6     420    4140   421.4  4538.2     420  4552.6     418
  4562.9     412    4580   398.3    4600   396.5    4620   398.2  4674.2     416
  4714.6     420    4727     422    4780     424  4836.5     422    4867     416
  4896.7  415.17  4933.8     416  4953.6     422  4992.2     434  5145.9     438
#Mann= 7 ,-1,0
     840     .04       0    2261     .08       0  2590.6    .185       0
  4538.2     .05       0  4714.6     .12       0    4780     .06       0
  4953.6    .035       0
#XS Ineff= 3 ,-1
     840    2261     450    2261  4538.2     420  4714.6  5145.9     420
Permanent Ineff=
       F       F       F
Bank Sta=4538.2,4714.6
XS Rating Curve= 0 ,0
Exp/Cntr=0.3,0.1