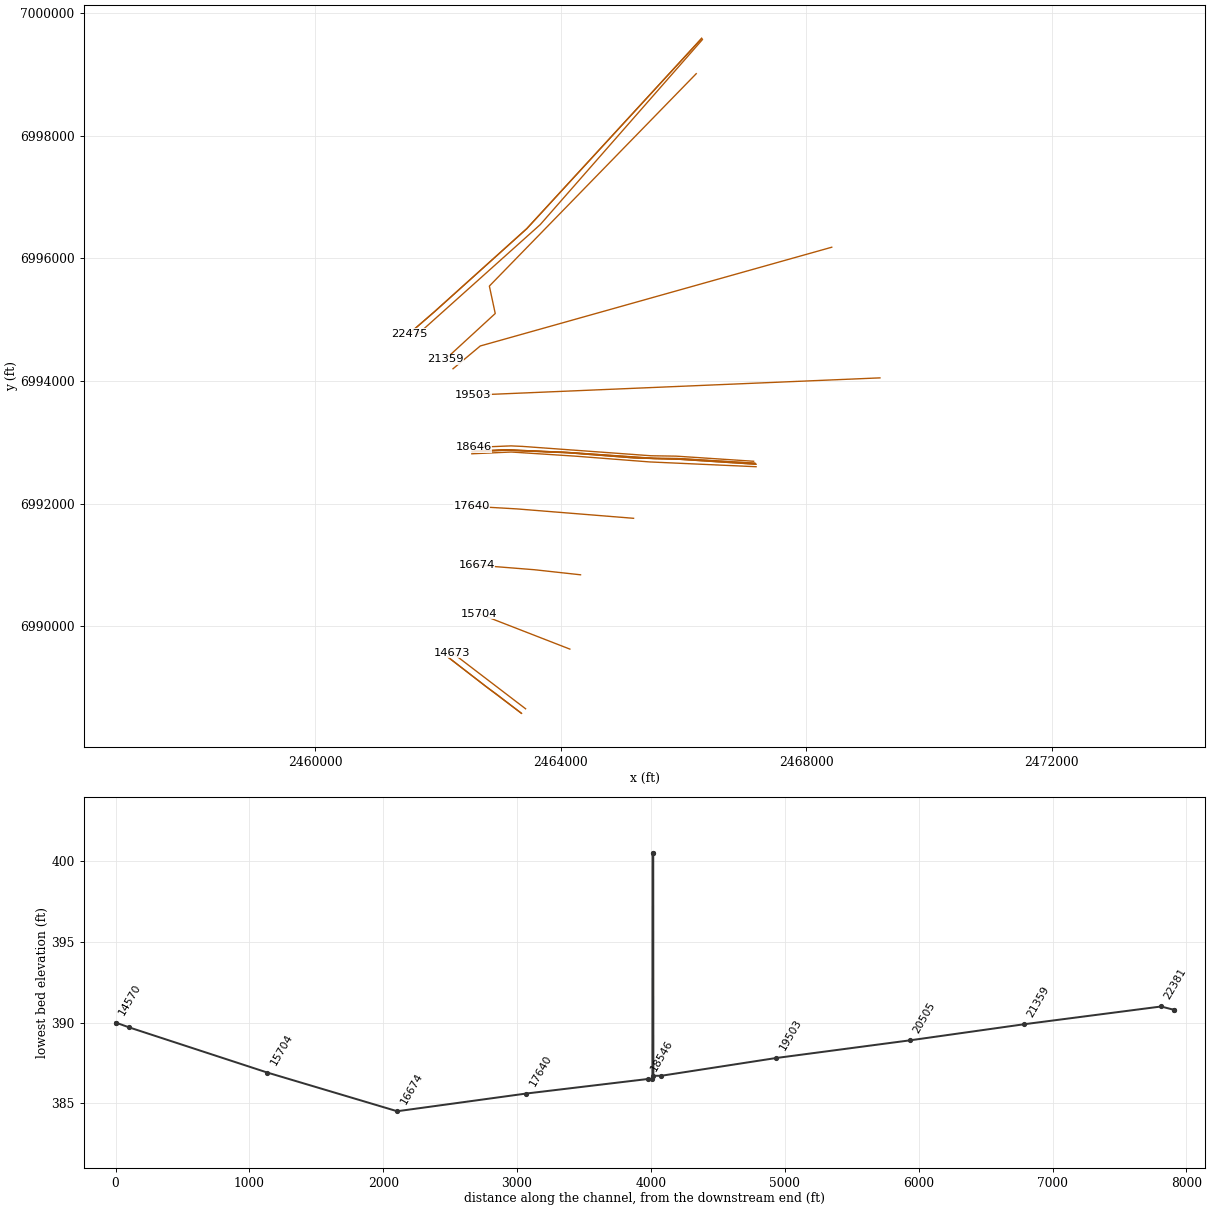
HEC-RAS study CDC_Consolidated_Model.prj: Upper Trinity CDC Consolidated Model

--- CDC_Consolidated_Model.g01 (geometry) --- (continued)

Type RM Length L Ch R = 3 ,22519   ,,,
BEGIN DESCRIPTION:
SH 482/Storey Lane
Data from bridge plans 1971.
END DESCRIPTION:
Node Name=SH 482
Bridge Culvert--1,0,-1,-1, 0
Deck Dist Width WeirC Skew NumUp NumDn MinLoCord MaxHiCord MaxSubmerge Is_Ogee
2,86,2.6,0, 51, 51, , , 0.95, 0, ,,,
    2420  2497.5  2502.5 2564.75 2567.25 2630.75 2633.25  2761.5  2766.5 2828.75
 2831.25  2959.5  2964.5  3025.5  3030.5 3158.75 3161.25 3224.75 3227.25  3355.5
  3360.5  3487.5  3492.5 3554.75 3557.25  3689.5  3694.5  3779.5  3784.5 3920.75
 3923.25 4010.75 4013.25 4080.75 4083.25 4150.75 4153.25 4240.75 4243.25 4310.75
 4313.25 4380.75 4383.25 4470.75 4473.25 4540.75 4543.25  4609.5  4614.5    4772
 4806.81
     439     439     439     439     439     439     439     439     439     439
     439     439     439     439     439     439     439     439     439     439
     439     439     439     439     439     439     439     439     439     439
     439     439     439     439     439     439     439     439     439     439
     439     439     439     439     439     439     439     439     439     439
     439
   430.6 430.697 430.708 430.896 430.904 431.096 431.102 431.362 431.372 431.498
 431.504 431.763 431.773 431.896 431.904 432.098 432.102 432.198 432.202 432.283
 432.286 432.366 432.369   432.4 432.402  432.46 432.462   432.5   432.5   432.5
 432.499 432.401   432.4   432.4 432.396 432.204   432.2   432.1 432.088 432.004
 431.998 431.902 431.897 431.703 431.698 431.602 431.596 431.482 431.473   431.2
   431.2
    2420  2497.5  2502.5 2564.75 2567.25 2630.75 2633.25  2761.5  2766.5 2828.75
 2831.25  2959.5  2964.5  3025.5  3030.5 3158.75 3161.25 3224.75 3227.25  3355.5
  3360.5  3487.5  3492.5 3554.75 3557.25  3689.5  3694.5  3779.5  3784.5 3920.75
 3923.25 4010.75 4013.25 4080.75 4083.25 4150.75 4153.25 4240.75 4243.25 4310.75
 4313.25 4380.75 4383.25 4470.75 4473.25 4540.75 4543.25  4609.5  4614.5    4772
 4779.67
     439     439     439     439     439     439     439     439     439     439
     439     439     439     439     439     439     439     439     439     439
     439     439     439     439     439     439     439     439     439     439
     439     439     439     439     439     439     439     439     439     439
     439     439     439     439     439     439     439     439     439     439
     439
   430.6 430.697 430.708 430.896 430.904 431.096 431.102 431.362 431.372 431.498
 431.504 431.763 431.773 431.896 431.904 432.098 432.102 432.198 432.202 432.283
 432.286 432.366 432.369   432.4 432.402  432.46 432.462   432.5   432.5   432.5
 432.499 432.401   432.4   432.4 432.396 432.204   432.2   432.1 432.088 432.004
 431.998 431.902 431.897 431.703 431.698 431.602 431.596 431.482 431.473   431.2
   431.2
Pier Skew, UpSta & Num, DnSta & Num=  ,2460, 2 ,2460, 2 , 0 , 0 , 0 ,,
     2.5     2.5
     390     446
     2.5     2.5
     390     446
Pier Skew, UpSta & Num, DnSta & Num=  ,2500, 2 ,2500, 2 , 0 , 0 , 0 ,,
     2.5     2.5
     390     446
     2.5     2.5
     390     446
Pier Skew, UpSta & Num, DnSta & Num=  ,2566, 2 ,2566, 2 , 0 , 0 , 0 ,,
     2.5     2.5
     390     446
     2.5     2.5
     390     446
Pier Skew, UpSta & Num, DnSta & Num=  ,2632, 2 ,2632, 2 , 0 , 0 , 0 ,,
     2.5     2.5
     390     446
     2.5     2.5
     390     446
Pier Skew, UpSta & Num, DnSta & Num=  ,2698, 2 ,2698, 2 , 0 , 0 , 0 ,,
     2.5     2.5
     390     446
     2.5     2.5
     390     446
Pier Skew, UpSta & Num, DnSta & Num=  ,2764, 2 ,2764, 2 , 0 , 0 , 0 ,,
     2.5     2.5
     390     446
     2.5     2.5
     390     446
Pier Skew, UpSta & Num, DnSta & Num=  ,2830, 2 ,2830, 2 , 0 , 0 , 0 ,,
     2.5     2.5
     390     446
     2.5     2.5
     390     446
Pier Skew, UpSta & Num, DnSta & Num=  ,2896, 2 ,2896, 2 , 0 , 0 , 0 ,,
     2.5     2.5
     390     446
     2.5     2.5
     390     446
Pier Skew, UpSta & Num, DnSta & Num=  ,2962, 2 ,2962, 2 , 0 , 0 , 0 ,,
     2.5     2.5
     390     446
     2.5     2.5
     390     446
Pier Skew, UpSta & Num, DnSta & Num=  ,3028, 2 ,3028, 2 , 0 , 0 , 0 ,,
     2.5     2.5
     390     446
     2.5     2.5
     390     446
Pier Skew, UpSta & Num, DnSta & Num=  ,3094, 2 ,3094, 2 , 0 , 0 , 0 ,,
     2.5     2.5
     390     446
     2.5     2.5
     390     446
Pier Skew, UpSta & Num, DnSta & Num=  ,3160, 2 ,3160, 2 , 0 , 0 , 0 ,,
     2.5     2.5
     390     446
     2.5     2.5
     390     446
Pier Skew, UpSta & Num, DnSta & Num=  ,3226, 2 ,3226, 2 , 0 , 0 , 0 ,,
     2.5     2.5
     390     446
     2.5     2.5
     390     446
Pier Skew, UpSta & Num, DnSta & Num=  ,3292, 2 ,3292, 2 , 0 , 0 , 0 ,,
     2.5     2.5
     390     446
     2.5     2.5
     390     446
Pier Skew, UpSta & Num, DnSta & Num=  ,3358, 2 ,3358, 2 , 0 , 0 , 0 ,,
     2.5     2.5
     390     446
     2.5     2.5
     390     446
Pier Skew, UpSta & Num, DnSta & Num=  ,3424, 2 ,3424, 2 , 0 , 0 , 0 ,,
     2.5     2.5
     390     446
     2.5     2.5
     390     446
Pier Skew, UpSta & Num, DnSta & Num=  ,3490, 2 ,3490, 2 , 0 , 0 , 0 ,,
     2.5     2.5
     390     446
     2.5     2.5
     390     446
Pier Skew, UpSta & Num, DnSta & Num=  ,3556, 2 ,3556, 2 , 0 , 0 , 0 ,,
     2.5     2.5
     390     446
     2.5     2.5
     390     446
Pier Skew, UpSta & Num, DnSta & Num=  ,3556, 2 ,3556, 2 , 0 , 0 , 0 ,,
     2.5     2.5
     390     446
     2.5     2.5
     390     446
Pier Skew, UpSta & Num, DnSta & Num=  ,3622, 2 ,3622, 2 , 0 , 0 , 0 ,,
     2.5     2.5
     390     446
     2.5     2.5
     390     446
Pier Skew, UpSta & Num, DnSta & Num=  ,3692, 2 ,3692, 2 , 0 , 0 , 0 ,,
     2.5     2.5
     390     446
     2.5     2.5
     390     446
Pier Skew, UpSta & Num, DnSta & Num=  ,3782, 2 ,3782, 2 , 0 , 0 , 0 ,,
     2.5     2.5
     390     446
     2.5     2.5
     390     446
Pier Skew, UpSta & Num, DnSta & Num=  ,3852, 2 ,3852, 2 , 0 , 0 , 0 ,,
     2.5     2.5
     390     446
     2.5     2.5
     390     446
Pier Skew, UpSta & Num, DnSta & Num=  ,3922, 2 ,3922, 2 , 0 , 0 , 0 ,,
     2.5     2.5
     390     446
     2.5     2.5
     390     446
Pier Skew, UpSta & Num, DnSta & Num=  ,4012, 2 ,4012, 2 , 0 , 0 , 0 ,,
     2.5     2.5
     390     446
     2.5     2.5
     390     446
Pier Skew, UpSta & Num, DnSta & Num=  ,4082, 2 ,4082, 2 , 0 , 0 , 0 ,,
     2.5     2.5
     390     446
     2.5     2.5
     390     446
Pier Skew, UpSta & Num, DnSta & Num=  ,4152, 2 ,4152, 2 , 0 , 0 , 0 ,,
     2.5     2.5
     390     446
     2.5     2.5
     390     446
Pier Skew, UpSta & Num, DnSta & Num=  ,4242, 2 ,4242, 2 , 0 , 0 , 0 ,,
     2.5     2.5
     390     446
     2.5     2.5
     390     446
Pier Skew, UpSta & Num, DnSta & Num=  ,4311, 2 ,4311, 2 , 0 , 0 , 0 ,,
     2.5     2.5
     390     446
     2.5     2.5
     390     446
Pier Skew, UpSta & Num, DnSta & Num=  ,4382, 2 ,4382, 2 , 0 , 0 , 0 ,,
     2.5     2.5
     390     446
     2.5     2.5
     390     446
Pier Skew, UpSta & Num, DnSta & Num=  ,4472, 2 ,4472, 2 , 0 , 0 , 0 ,,
     2.5     2.5
     390     446
     2.5     2.5
     390     446
Pier Skew, UpSta & Num, DnSta & Num=  ,4542, 2 ,4542, 2 , 0 , 0 , 0 ,,
     2.5     2.5
     390     446
     2.5     2.5
     390     446
Pier Skew, UpSta & Num, DnSta & Num=  ,4612, 2 ,4612, 2 , 0 , 0 , 0 ,,
       5       5
     390     446
     2.5     2.5
     390     446
Pier Skew, UpSta & Num, DnSta & Num=  ,4702, 2 ,4702, 2 , 0 , 0 , 0 ,,
     2.5     2.5
     390     446
     2.5     2.5
     390     446
BR Coef= 1 , 0 , 0 ,1.05, 0 ,,,0.8,-1,0.5,1,
WSPro=,,,, 1 ,,,, 0 ,,,, 0 ,,,,-1 ,-1 ,-1 , 0 , 0 , 0 , 0 , 0
BC Design=,, 0 ,, 0 ,,,,,,
BC HTab HWMax=436.1
BC Use User HTab Curves=0
BC User HTab FreeFlow(D)= 0

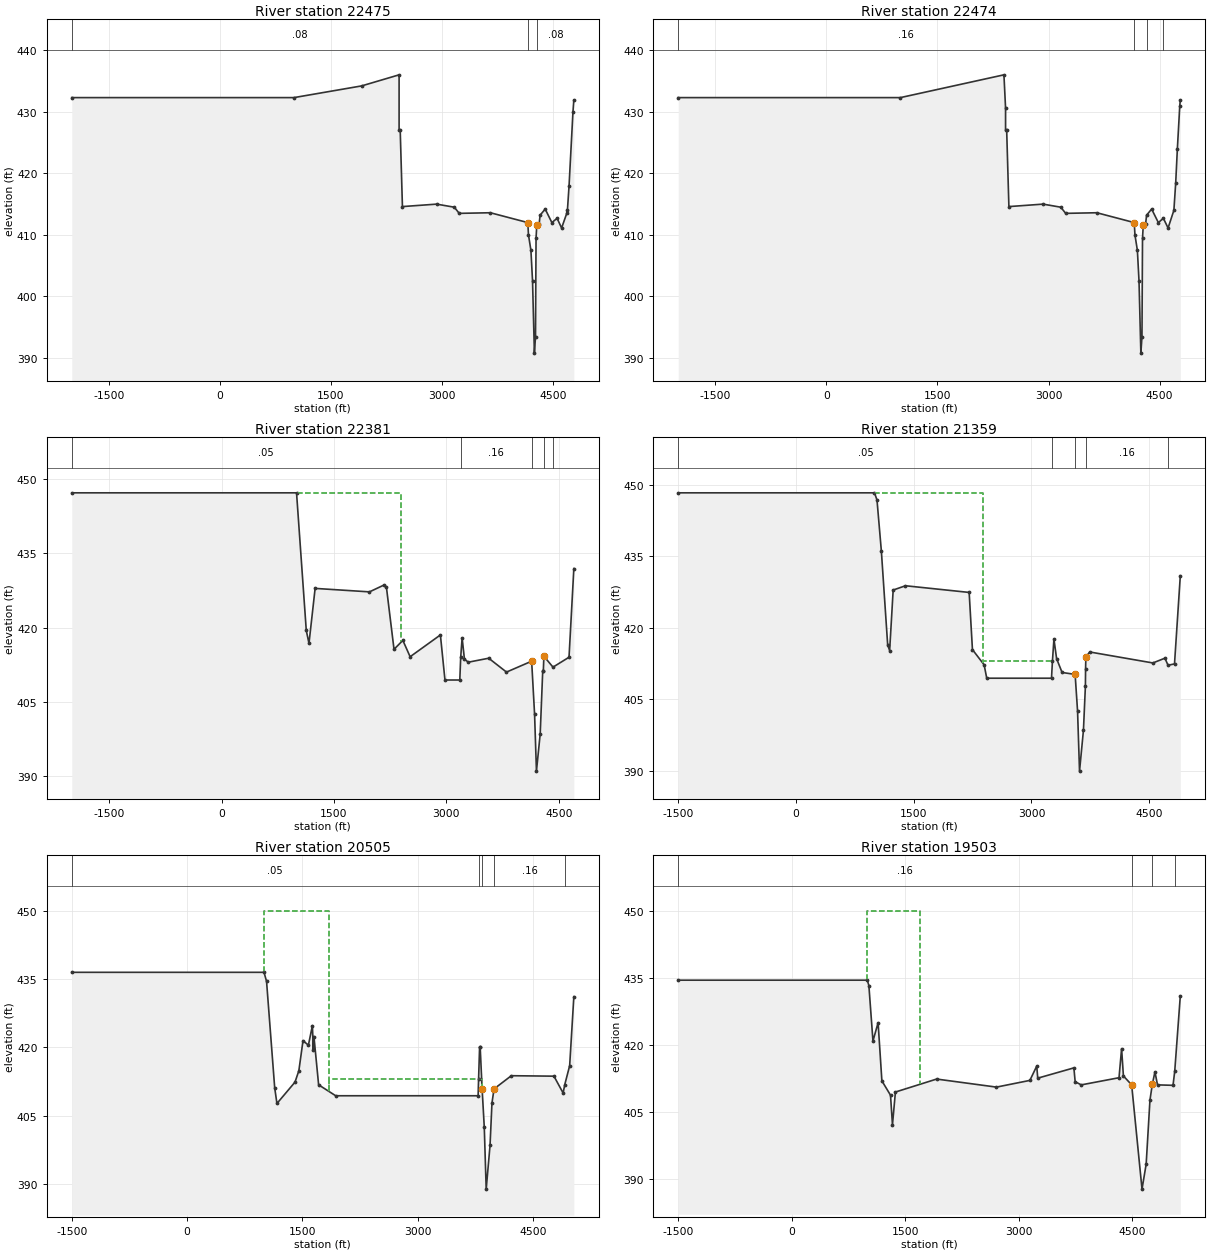
Type RM Length L Ch R = 1 ,22475   ,1,1,1
BEGIN DESCRIPTION:
This cross section corresponds to cross section 22457 of the non-georeferenced CDC model which was the source of this model.
END DESCRIPTION:
XS GIS Cut Line= 6
2466294.615507126999584.726372022464264.798864936997375.68938747
2463444.908772416996483.408035552461941.305152336995130.35792014
2461529.763652596994773.588292462461529.400136266994773.27333246
#Sta/Elev= 30
   -2000   432.3    1000   432.3    1914   434.2    2420     436    2420     427
    2435     427    2465   414.6  2926.5     415  3165.5   414.5    3232   413.5
  3652.5   413.6    4158     412    4167     410    4200   407.5    4222   402.5
    4247   390.8    4262   393.5 4269.29 409.451 4279.95  411.68  4310.5   411.7
    4324   413.2  4392.5   414.2    4483     412  4553.5   412.7  4614.5 411.117
 4683.95  413.51 4692.95     414 4715.14     418 4767.81     430 4779.67   431.9
#Mann= 3 ,0,0
   -2000     .08       0    4158     .05       0 4279.95     .08       0
#XS Ineff= 2 , 0
       0    4158     412 4279.95       0  411.68
Permanent Ineff=
       F       F
Bank Sta=4158,4279.95
XS Rating Curve= 0 ,0
Exp/Cntr=0.5,0.3

Type RM Length L Ch R = 1 ,22474   ,93,93,93
BEGIN DESCRIPTION:
This cross section corresponds to cross section 22456 of the non-georeferenced CDC model which was the source of this model.
One-foot downstream of SH 482/Storey Lane.
END DESCRIPTION:
XS GIS Cut Line= 6
2466296.252193496999583.149704742465957.822253056999215.09376414
2463445.497353916996482.841107552461942.059415946995129.69814456
2461530.059583756994773.05253239 2461529.82467616994772.84912072
#Sta/Elev= 30
   -2000   432.3    1000   432.3    2398     436    2420   430.6    2420     427
    2435     427    2465   414.6  2926.5     415  3165.5   414.5    3232   413.5
  3652.5   413.6    4158     412    4167     410    4200   407.5    4222   402.5
    4247   390.8    4262   393.5 4269.29 409.451 4279.95  411.68  4310.5   411.7
    4324   413.2  4392.5   414.2    4483     412    4551   412.7  4614.5 411.117
 4692.95     414  4717.3  418.43 4739.99     424 4772.28  430.95 4779.67   431.9
#Mann= 4 ,-1,0
   -2000     .16       0    4158     .05       0    4324     .16       0
    4551     .03       0
#XS Ineff= 2 , 0
       0    4158     412 4279.95       0  411.68
Permanent Ineff=
       F       F
Bank Sta=4158,4279.95
XS Rating Curve= 0 ,0
Exp/Cntr=0.3,0.1

Type RM Length L Ch R = 1 ,22381   ,170,1022,629
BEGIN DESCRIPTION:
This cross section corresponds to cross section 22356 of the non-georeferenced CDC model which was the source of this model.
Right Overbank updated with 2007 levee topo.
Cross-section EF033.  101 feet downstream of S.H. 482/Storey Lane.  Effective flow limit set at sta 2400 in LOB, at Irving Flood Control District No. 1 Levee (Northwest Levee) in ROB.  Conveyance of pond in LOB set at elev. 414.0.
Channel data from COD Elm Fork channel survey - cross-section EF#033 surveyed February 1994.
END DESCRIPTION:
XS GIS Cut Line= 5
2466307.205482396999563.958806072465977.621669746999187.96078687
 2464329.70260656997307.970690882463665.247898676996549.94300747
2461659.184325526994753.14246722
#Sta/Elev= 30
   -2000   447.2    1000   447.2    1130   419.4    1166   416.8    1248   427.9
    1973   427.2    2170   428.6    2200   428.1    2301   415.6    2419   417.4
    2516   414.1    2920   418.5    2981   409.4    3179   409.4    3191     414
    3210   417.9    3241   413.6    3293     413    3565   413.8    3802     411
    4138   413.2    4177   402.5    4202     391    4252   398.5    4286   411.3
    4294   411.2    4301   414.2    4423     412 4636.75     414 4701.12   431.9
#Mann= 5 ,-1,0
   -2000     .05       0    3191     .16       0    4138     .05       0
    4301     .16       0    4423     .03       0
#XS Ineff= 4 ,-1
    1000    2400   447.2    3191    4138   413.2    4301    4714   414.2
    2940    3191     414
Permanent Ineff=
       T       F       F       T
Bank Sta=4138,4301
XS Rating Curve= 0 ,0
Exp/Cntr=0.3,0.1

Type RM Length L Ch R = 1 ,21359   ,1251,854,220
BEGIN DESCRIPTION:
This cross section corresponds to cross section 21333 of the non-georeferenced CDC model which was the source of this model.
Right Overbank updated with 2007 levee topo.
Cross-section EF032.  Effective flow limit set at sta 2380 in LOB, at Irving Flood Control District No. 1 Levee (Northwest Levee) in ROB. Conveyance of pond in LOB set at elev. 413.0.
Channel data from COD Elm Fork channel survey.
END DESCRIPTION:
XS GIS Cut Line= 5
2466206.728350886999008.439819222464462.372288676997217.56798455
 2462835.13505766995546.938123722462930.937031336995099.86519897
2462116.145025766994351.13802189
#Sta/Elev= 30
   -1500   448.3    1000   448.3    1032   446.8    1088     436    1168   416.4
    1193   415.2    1238   427.9    1395   428.8    2206   427.4    2248   415.4
    2397   412.2    2430   409.4    3255   409.4    3267     413    3286   417.6
    3320   413.5    3390   410.6    3556   410.2    3587   402.5    3612   389.9
    3662   398.5    3687   407.8    3689   411.3    3693   413.9    3743   414.9
    4546   412.6    4700   413.6 4739.43  412.12 4822.02   412.4 4895.93   430.9
#Mann= 5 ,-1,0
   -1500     .05       0    3267     .16       0    3556     .05       0
    3693     .16       0 4739.43     .03       0
#XS Ineff= 3 ,-1
    1000    2380   448.3    2380    3267     413    3693    4911   413.9
Permanent Ineff=
       T       T       F
Bank Sta=3556,3693
XS Rating Curve= 0 ,0
Exp/Cntr=0.3,0.1

Type RM Length L Ch R = 1 ,20505   ,1099,1002,699
BEGIN DESCRIPTION:
This cross section corresponds to cross section 20480 of the non-georeferenced CDC model which was the source of this model.
Right Overbank updated with 2007 levee topo.
Cross-section EF031.  Effective flow limit set at sta 1850 in LOB, at Irving Flood Control District No. 1 Levee (Northwest Levee) in ROB.  Conveyance of pond in LOB set at elev. 413.0.
Channel data from COD Elm Fork channel survey.
END DESCRIPTION:
XS GIS Cut Line= 4
2468415.272110666996180.070888352466008.458107266995503.87095264
2462686.856154686994570.659236392462243.046018666994199.47231472
#Sta/Elev= 30
   -1500   436.5    1000   436.5    1033   434.5    1139   411.1    1168   407.7
    1403   412.4    1453   414.9    1507   421.5    1577   420.5    1629   424.8
    1641   419.5    1649   422.4    1710   411.8    1932   409.4    3784   409.4
    3790     413    3803     420    3811     420    3836   410.9    3864   402.5
    3889   388.9    3939   398.5    3964   407.8    3991   410.9    4216   413.8
    4770   413.7 4889.32     410 4911.12  411.87 4974.38     416 5028.78  431.15
#Mann= 5 ,-1,0
   -1500     .05       0    3790      .1       0    3836     .05       0
    3991     .16       0 4911.12     .03       0
#XS Ineff= 3 ,-1
    1000    1850     450    1850    3836     413    3991 5028.78   410.9
Permanent Ineff=
       F       T       F
Bank Sta=3836,3991
XS Rating Curve= 0 ,0
Exp/Cntr=0.3,0.1

Type RM Length L Ch R = 1 ,19503   ,941,857,857
BEGIN DESCRIPTION:
This cross section corresponds to cross section 19477 of the non-georeferenced CDC model which was the source of this model.
Right Overbank updated with 2007 levee topo.
Cross-section EF030.  At Elm Fork/old Elm Fork channel confluence - upstream end of Dallas Floodway improved Elm Fork channel.  Effective flow limit set at sta 1700 in LOB, at Irving Flood Control District No.1 Levee (Northwest Levee) in ROB.  Old Elm Fork channel removed from conveyance in LOB.
Channel data from COD Elm Fork channel survey.
END DESCRIPTION:
XS GIS Cut Line= 3
2469201.277757516994050.72805524 2466703.51905316993944.89113097
2462567.770106766993769.64804313
#Sta/Elev= 30
   -1500   434.5    1000   434.5    1021   433.3    1075   420.9    1143     425
    1193     412    1307   408.8    1333   402.2    1372   409.5    1917   412.4
    2708   410.6    3150   412.1    3241   415.3    3254   412.6    3732   414.9
    3749   411.8    3830   411.1    4329   412.7    4363   419.2    4387   413.1
    4496   411.1    4633   387.8    4688   393.4    4738   407.7    4769   411.2
    4804     414    4838   411.1    5043     411 5065.63  414.13 5139.46     431
#Mann= 4 ,-1,0
   -1500     .16       0    4496    .035       0    4769     .09       0
 5065.63     .03       0
#XS Ineff= 3 ,-1
    1000    1700     450    1700    4496   411.1    4769 5139.46   411.2
Permanent Ineff=
       F       F       F
Bank Sta=4496,4769
XS Rating Curve= 0 ,0
Exp/Cntr=0.3,0.1

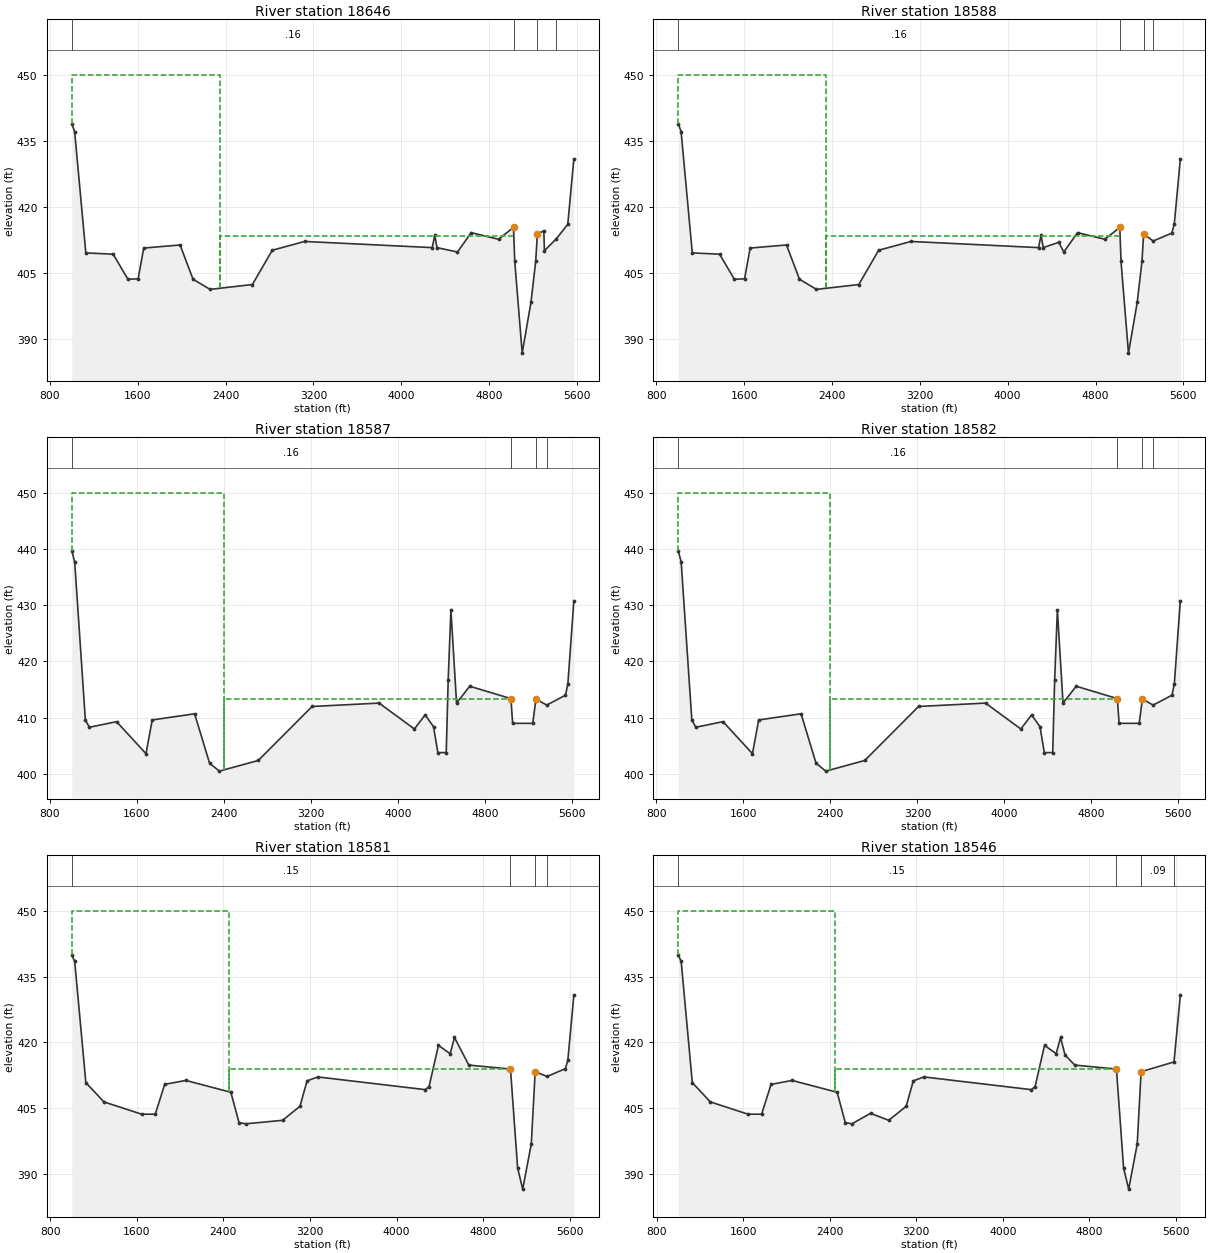
Type RM Length L Ch R = 1 ,18646   ,58,58,58
BEGIN DESCRIPTION:
This cross section corresponds to cross section 18621 of the non-georeferenced CDC model which was the source of this model.
Right Overbank updated with 2007 levee topo.
45 feet upstream of Frazier Dam.  Effective low limit
set at sta 2350 in LOB, at Irving Flood Control District No. 1 Levee (Northwest Levee) in ROB.
Channel data from COD Elm Fork channel survey.
END DESCRIPTION:
XS GIS Cut Line= 6
2467142.067716666992691.711878812465881.004622016992774.94432388
2465468.325985436992781.417079972463377.266191186992933.72517429
2463186.99983943 6992942.16019682462581.209384356992917.82888064
#Sta/Elev= 30
    1000   438.9    1026   437.1    1128   409.5    1377   409.2    1511   403.5
    1604   403.6    1655   410.6    1986   411.3    2104   403.5    2259   401.2
    2644   402.3    2825   410.1    3119   412.1    4281   410.7    4304   413.5
    4324   410.7    4511   409.7    4636   414.1    4885   412.6    5021   415.3
    5032   407.6    5100   386.7    5180   398.3    5223   407.6    5238   413.8
    5297   414.5 5302.15     410 5408.99  412.66 5514.85     416  5570.1  430.85
#Mann= 4 ,-1,0
    1000     .16       0    5021    .035       0    5238     .09       0
 5408.99     .03       0
#XS Ineff= 3 ,-1
    1000    2350     450    2350    5021   413.4    5238 5572.03   413.8
Permanent Ineff=
       F       F       F
Bank Sta=5021,5238
XS Rating Curve= 0 ,0
Exp/Cntr=0.3,0.1

Type RM Length L Ch R = 1 ,18588   ,1,1,1
BEGIN DESCRIPTION:
This cross section corresponds to cross section 18577 of the non-georeferenced CDC model which was the source of this model.
One-foot upstream of Frasier Dam.  Channel data from COD Elm Fork channel survey.
END DESCRIPTION:
XS GIS Cut Line= 6
2467153.318022256992660.74802996 2465901.3493976 6992737.1074573
2465500.271131526992741.911253472464097.138439096992836.77523696
2463108.754261026992879.171477632462588.256614336992857.04652189
#Sta/Elev= 30
    1000   438.9    1026   437.1    1128   409.5    1377   409.2    1511   403.5
    1604   403.6    1655   410.6    1986   411.3    2104   403.5    2259   401.2
    2644   402.3    2825   410.1    3119   412.1    4281   410.7    4304   413.5
    4324   410.7    4465   411.9    4511   409.7    4636   414.1    4885   412.6
    5021   415.3    5032   407.6    5100   386.7    5180   398.3    5223   407.6
    5238   413.8 5325.22   412.2 5494.63     414 5516.96     416 5572.03   430.8
#Mann= 4 ,-1,0
    1000     .16       0    5021    .035       0    5238     .09       0
 5325.22     .03       0
#XS Ineff= 3 ,-1
    1000    2350     450    2350    5021   413.4    5238 5572.03   413.8
Permanent Ineff=
       F       F       F
Bank Sta=5021,5238
XS Rating Curve= 0 ,0
Exp/Cntr=0.3,0.1

Type RM Length L Ch R = 1 ,18587   ,5,5,5
BEGIN DESCRIPTION:
This cross section corresponds to cross section 18576 of the non-georeferenced CDC model which was the source of this model.
Frasier Dam
END DESCRIPTION:
XS GIS Cut Line= 6
2467168.62967142 6992658.07218232465924.089509586992733.17308196
2465511.603129836992736.290201722464129.732205936992833.94879904
 2463115.28016666992878.409996212462557.091322336992852.88708138
#Sta/Elev= 30
    1000   439.7    1027   437.7    1125   409.6    1162   408.3    1412   409.3
    1683   403.6    1740   409.6    2130   410.7    2268   401.9    2358   400.5
    2716   402.4    3211     412    3827   412.6    4152     408    4251   410.5
    4328   408.4    4368   403.8    4445   403.8    4463   416.7    4488   429.2
    4540   412.6    4661   415.6    5040   413.4    5056     409    5241     409
    5270   413.3 5369.71  412.25 5541.63     414 5563.96     416 5619.03   430.8
#Mann= 4 ,-1,0
    1000     .16       0    5040     .02       0    5270     .07       0
 5369.71     .03       0
#XS Ineff= 3 ,-1
    1000    2400     450    2400    5040   413.4    5270 5619.03   413.3
Permanent Ineff=
       F       F       F
Bank Sta=5040,5270
XS Rating Curve= 0 ,0
Exp/Cntr=0.3,0.1

Type RM Length L Ch R = 1 ,18582   ,1,1,1
BEGIN DESCRIPTION:
This cross section corresponds to cross section 18571 of the non-georeferenced CDC model which was the source of this model.
Frasier Dam - Cross-section EF028.  Weir crest elev. 409.0.  Effective flow limit set at sta 2400 in LOB, at Irving Flood Control District No. 1 Levee (Northwest Levee) in ROB.
---------------------------------------------------------------------
CDC DAL021201-1 Frasier Dam Modifications
Cross-section 18571 - 18576
---------------------------------------------------------------
END DESCRIPTION:
Node Name=Frasier Dam
XS GIS Cut Line= 6
    2467169.2997    6992644.8492     2465917.426     6992725.511
     2465206.977     6992746.233     2464113.071     6992831.255
     2463114.446     6992873.398   2462558.26797   6992848.16738
#Sta/Elev= 30
    1000   439.7    1027   437.7    1125   409.6    1162   408.3    1412   409.3
    1683   403.6    1740   409.6    2130   410.7    2268   401.9    2358   400.5
    2716   402.4    3211     412    3827   412.6    4152     408    4251   410.5
    4328   408.4    4368   403.8    4445   403.8    4463   416.7    4488   429.2
    4540   412.6    4661   415.6    5040   413.4    5056     409    5241     409
    5270   413.3 5369.71  412.25 5541.63     414 5563.96     416 5619.03   430.8
#Mann= 4 ,-1,0
    1000     .16       0    5040     .02       0    5270     .07       0
 5369.71     .03       0
#XS Ineff= 3 ,-1
    1000    2400     450    2400    5040   413.4    5270 5619.03   413.3
Permanent Ineff=
       F       F       F
Bank Sta=5040,5270
XS Rating Curve= 0 ,0
Exp/Cntr=0.3,0.1

Type RM Length L Ch R = 1 ,18581   ,35,35,35
BEGIN DESCRIPTION:
This cross section corresponds to cross section 18570 of the non-georeferenced CDC model which was the source of this model.
One-foot downstream of Frasier Dam.
END DESCRIPTION:
XS GIS Cut Line= 6
2467183.315665666992643.066634882465917.463210496992724.50774497
2465207.013844016992745.230144472464113.108223416992830.25162797
2463114.483580266992872.394916392462555.309501776992847.00914039
#Sta/Elev= 30
    1000   439.9    1027   438.5    1130   410.8    1297   406.4    1645   403.6
    1771   403.6    1858   410.4    2053   411.3    2469   408.6    2544   401.7
    2605   401.4    2946   402.2    3107   405.4    3173   411.2    3271   412.1
    4264   409.2    4299   409.9    4386   419.3    4494   417.4    4534   421.1
    4666   414.8    5051   413.9    5117   391.3    5164   386.5    5243   396.8
    5279   413.3 5389.22   412.2 5558.63     414 5580.96     416 5636.03   430.8
#Mann= 4 ,-1,0
    1000     .15       0    5051    .035       0    5279     .09       0
 5389.22     .03       0
#XS Ineff= 3 ,-1
    1000    2450     450    2450    5051   413.9    5279 5641.32   413.3
Permanent Ineff=
       F       F       F
Bank Sta=5051,5279
XS Rating Curve= 0 ,0
Exp/Cntr=0.3,0.1

Type RM Length L Ch R = 1 ,18546   ,960,906,906
BEGIN DESCRIPTION:
This cross section corresponds to cross section 18521 of the non-georeferenced CDC model which was the source of this model.
Right Overbank updated with 2007 levee topo.
Cross-section EF027.  50 feet downstream of Frazier Dam.  Effective flow limit set at sta 2450 in LOB, at Irving Flood Control District No. 1 Levee (Northwest Levee) in ROB.
Channel data from COD Elm Fork channel survey.
END DESCRIPTION:
XS GIS Cut Line= 6
2467182.491848416992602.669405972465445.249259926992680.86642805
2464236.476415016992774.954494462463214.511923496992840.84182988
2463187.191112016992842.053113552462549.376114676992813.51970606
#Sta/Elev= 30
    1000   439.9    1027   438.5    1130   410.8    1297   406.4    1645   403.6
    1771   403.6    1858   410.4    2053   411.3    2469   408.6    2544   401.7
    2605   401.4    2778   403.8    2946   402.2    3107   405.4    3173   411.2
    3271   412.1    4264   409.2    4299   409.9    4386   419.3    4494   417.4
    4534   421.1    4576   417.1    4666   414.8    5051   413.9    5117   391.3
    5164   386.5    5243   396.8    5279   413.3 5582.95  415.52 5641.32  430.78
#Mann= 4 ,-1,0
    1000     .15       0    5051    .035       0    5279     .09       0
 5582.95     .03       0
#XS Ineff= 3 ,-1
    1000    2450     450    2450    5051   413.9    5279 5641.32   413.3
Permanent Ineff=
       F       F       F
Bank Sta=5051,5279
XS Rating Curve= 0 ,0
Exp/Cntr=0.3,0.1

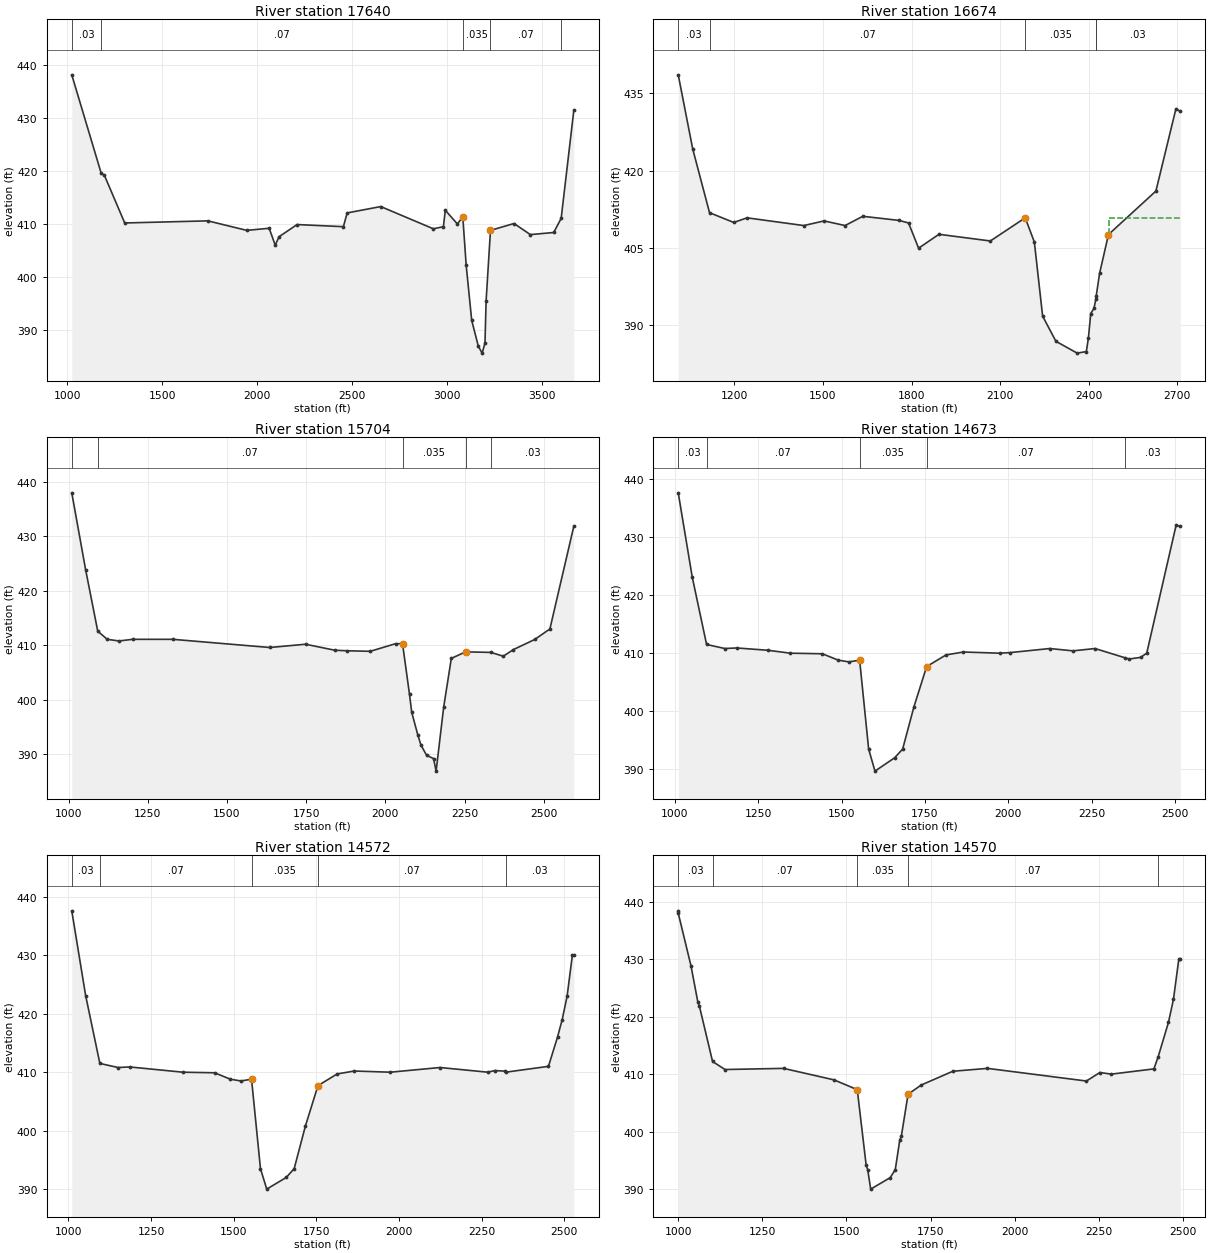
Type RM Length L Ch R = 1 ,17640   ,1000,966,950
BEGIN DESCRIPTION:
This cross section corresponds to cross section 17615 of the non-georeferenced CDC model which was the source of this model.
Right Overbank updated with 2007 levee topo.
Cross-section EF026.  Effective flow limit set at East Levee in LOB, at Irving Flood Control District No. 1 Levee (Northwest Levee) in ROB.  Bachman Branch in LOB removed from conveyance.
Channel data from COD Elm Fork channel survey.
END DESCRIPTION:
XS GIS Cut Line= 3
2465185.311131516991762.060850962463278.727346246991915.61730239
 2462547.4738875 6991957.5086228
#Sta/Elev= 30
    1023   438.2    1178   419.6    1195   419.2    1302   410.2    1740   410.6
    1945   408.8    2063   409.2    2095     406    2115   407.6    2210   409.9
    2454   409.5    2474   412.1    2651   413.3    2928   409.1    2981   409.5
    2991   412.6    3055     410    3083   411.4    3101   402.2    3130   391.8
    3165   386.9    3185   385.6    3200   387.5    3206   395.5    3229   408.8
    3353   410.1    3439     408    3562   408.4  3601.4  411.06 3668.21  431.52
#Mann= 5 ,-1,0
    1023     .03       0    1178     .07       0    3083    .035       0
    3229     .07       0  3601.4     .03       0
#XS Ineff= 2 , 0
       0    3083   411.4    3229       0   408.8
Permanent Ineff=
       F       F
Bank Sta=3083,3229
XS Rating Curve= 0 ,0
Exp/Cntr=0.3,0.1

Type RM Length L Ch R = 1 ,16674   ,1049,970,849
BEGIN DESCRIPTION:
This cross section corresponds to cross section 16649 of the non-georeferenced CDC model which was the source of this model.
Proposed grading for levee overbank.
Right Overbank updated with 2007 levee topo.
Cross-section EF025.  Effective flow limit set at East Levee in LOB, at Irving Flood Control District No. 1 Levee (Northwest Levee) in ROB. Channel data from COD Elm Fork channel survey - cross-section EF#025 surveyed
February 1994.
END DESCRIPTION:
XS GIS Cut Line= 3
2464321.024146176990841.184739962463571.845526436990923.54153064
2462628.231600026990998.89964764
#Sta/Elev= 30
    1010   438.6    1059   424.2    1116   411.8    1198   409.9    1243   410.8
    1435   409.3    1504   410.2    1575   409.3    1635   411.1    1758   410.3
    1790   409.8    1824   404.9    1893   407.6    2067   406.3    2185   410.8
    2216   406.1    2244   391.7    2289   386.8    2361   384.5    2392   384.8
    2399   387.4    2407   392.2    2418   393.2  2424.2  394.96 2425.34  395.54
 2436.94     400    2467  407.55 2627.64     416 2695.44     432 2710.31  431.49
#Mann= 5 ,-1,0
    1010     .03       0    1116     .07       0    2185    .035       0
  2424.2     .07       0 2425.34     .03       0
#XS Ineff= 2 , 0
       0    2185   410.8    2469       0   410.8
Permanent Ineff=
       F       F
Bank Sta=2185,2467
XS Rating Curve= 0 ,0
Exp/Cntr=0.3,0.1

Type RM Length L Ch R = 1 ,15704   ,1061,1031,851
BEGIN DESCRIPTION:
This cross section corresponds to cross section 15678 of the non-georeferenced CDC model which was the source of this model.
Proposed grading for levee overbank.
Right Overbank updated with 2007 levee topo.
Cross-section EF024.  Effective flow limit set at East Levee in LOB, at Irving Flood Control District No. 1 Levee (Northwest Levee) in ROB.  Pond in ROB removed from conveyance.
Channel data from COD Elm Fork channel survey.
END DESCRIPTION:
XS GIS Cut Line= 2
2464147.013667436989630.166492722462670.037946856990204.54624946
#Sta/Elev= 30
    1010     438    1054   423.8    1092   412.6    1122   411.1    1159   410.8
    1202   411.1    1329   411.1    1635   409.6    1748   410.2    1840   409.1
    1878     409    1952   408.9    2032   410.3    2054   410.3    2076     401
    2083   397.7    2102   393.6    2112   391.7    2130   389.8    2152   389.2
    2160   386.9    2184   398.7    2208   407.6    2253   408.8    2333   408.7
 2372.06     408 2404.04  409.22 2471.15  411.07 2519.11     413 2594.73  431.89
#Mann= 5 ,-1,0
    1010     .03       0    1092     .07       0    2054    .035       0
    2253     .07       0    2333     .03       0
#XS Ineff= 2 , 0
       0    2054   410.3    2253       0   408.8
Permanent Ineff=
       F       F
Bank Sta=2054,2253
XS Rating Curve= 0 ,0
Exp/Cntr=0.3,0.1

Type RM Length L Ch R = 1 ,14673   ,101,101,101
BEGIN DESCRIPTION:
This cross section corresponds to cross section 14648 of the non-georeferenced CDC model which was the source of this model.
Proposed grading for levee overbank.
Right Overbank updated with 2007 levee topo.
Cross-section EF023.  104 feet upstream of S.H. 183.  Effective flow limit set at East Levee in LOB, at Irving Flood Control District No. 1 Levee (Northwest Levee) in ROB.
Channel data from COD Elm Fork channel survey.
END DESCRIPTION:
XS GIS Cut Line= 2
 2463425.48033366988657.478477462462228.986007426989571.50453655
#Sta/Elev= 30
    1010   437.6    1052   423.1    1095   411.5    1150   410.8    1185   410.9
    1279   410.5    1346     410    1442   409.9    1490   408.8    1522   408.5
    1554   408.8    1581   393.5    1600   389.7    1659     392    1683   393.5
    1717   400.8    1755   407.7    1813   409.7    1865   410.2    1974     410
    2005   410.1    2124   410.8    2194   410.4 2259.93   410.8  2349.7  409.21
 2362.59     409 2396.68  409.28 2414.94     410 2502.98     432 2515.67  431.83
#Mann= 5 ,-1,0
    1010     .03       0    1095     .07       0    1554    .035       0
    1755     .07       0  2349.7     .03       0
#XS Ineff= 2 , 0
       0    1554   408.8    1755       0   407.7
Permanent Ineff=
       F       F
Bank Sta=1554,1755
XS Rating Curve= 0 ,0
Exp/Cntr=0.3,0.1

Type RM Length L Ch R = 1 ,14572   ,2,2,2
BEGIN DESCRIPTION:
This cross section corresponds to cross section 14545 of the non-georeferenced CDC model which was the source of this model.
Proposed grading for levee overbank.
Right Overbank updated with 2007 levee topo.
One-foot upstream of S.H. 183.
Channel data from COD Elm Fork channel survey.
END DESCRIPTION:
XS GIS Cut Line= 4
2463360.138600776988582.560976392462954.787377336988893.08528972
2462792.263096096989011.351457392462153.760764186989505.91542888
#Sta/Elev= 30
    1010   437.6    1052   423.1    1095   411.5    1150   410.8    1185   410.9
    1346     410    1442   409.9    1490   408.8    1522   408.5    1554   408.8
    1581   393.5    1600     390    1659     392    1683   393.5    1717   400.8
    1755   407.7    1813   409.7    1865   410.2    1974     410    2124   410.8
    2269     410 2290.21  410.28 2321.22  410.18 2324.22  410.01 2452.44     411
 2479.83     416 2494.05     419 2508.87     423 2524.81     430 2529.26     430
#Mann= 5 ,-1,0
    1010     .03       0    1095     .07       0    1554    .035       0
    1755     .07       0 2324.22     .03       0
#XS Ineff= 2 , 0
       0    1554   408.8    1755       0   407.7
Permanent Ineff=
       F       F
Bank Sta=1554,1755
XS Rating Curve= 0 ,0
Exp/Cntr=0.5,0.3

Type RM Length L Ch R = 1 ,14570   ,135,135,135
BEGIN DESCRIPTION:
This cross section corresponds to cross section 14544 of the non-georeferenced CDC model which was the source of this model.
Proposed grading for levee overbank.
Right Overbank updated with 2007 levee topo.
END DESCRIPTION:
XS GIS Cut Line= 3
2463350.542163256988588.547184882462811.876245836988996.14610721
2462165.39886427 6989494.9682723
#Sta/Elev= 30
    1000   438.4    1000     438    1038   428.8  1058.5 422.464    1063   421.8
    1102   412.2    1139   410.8    1313     411    1463     409    1532   407.3
  1558.5  394.15    1563   393.4    1572     390    1630     392    1645   393.4
  1658.5  398.57    1663   399.2    1683   406.5    1722   408.1    1816   410.5
    1919     411    2213   408.8    2253  410.28 2287.25     410 2413.57  410.91
 2426.17     413 2456.84     419 2471.66     423  2487.6     430 2492.05     430
#Mann= 5 ,-1,0
    1000     .03       0    1102     .07       0    1532    .035       0
    1683     .07       0 2426.17     .03       0
#XS Ineff= 2 , 0
       0    1532   407.3    1683       0   406.5
Permanent Ineff=
       F       F
Bank Sta=1532,1683
XS Rating Curve= 0 ,0
Exp/Cntr=0.5,0.3