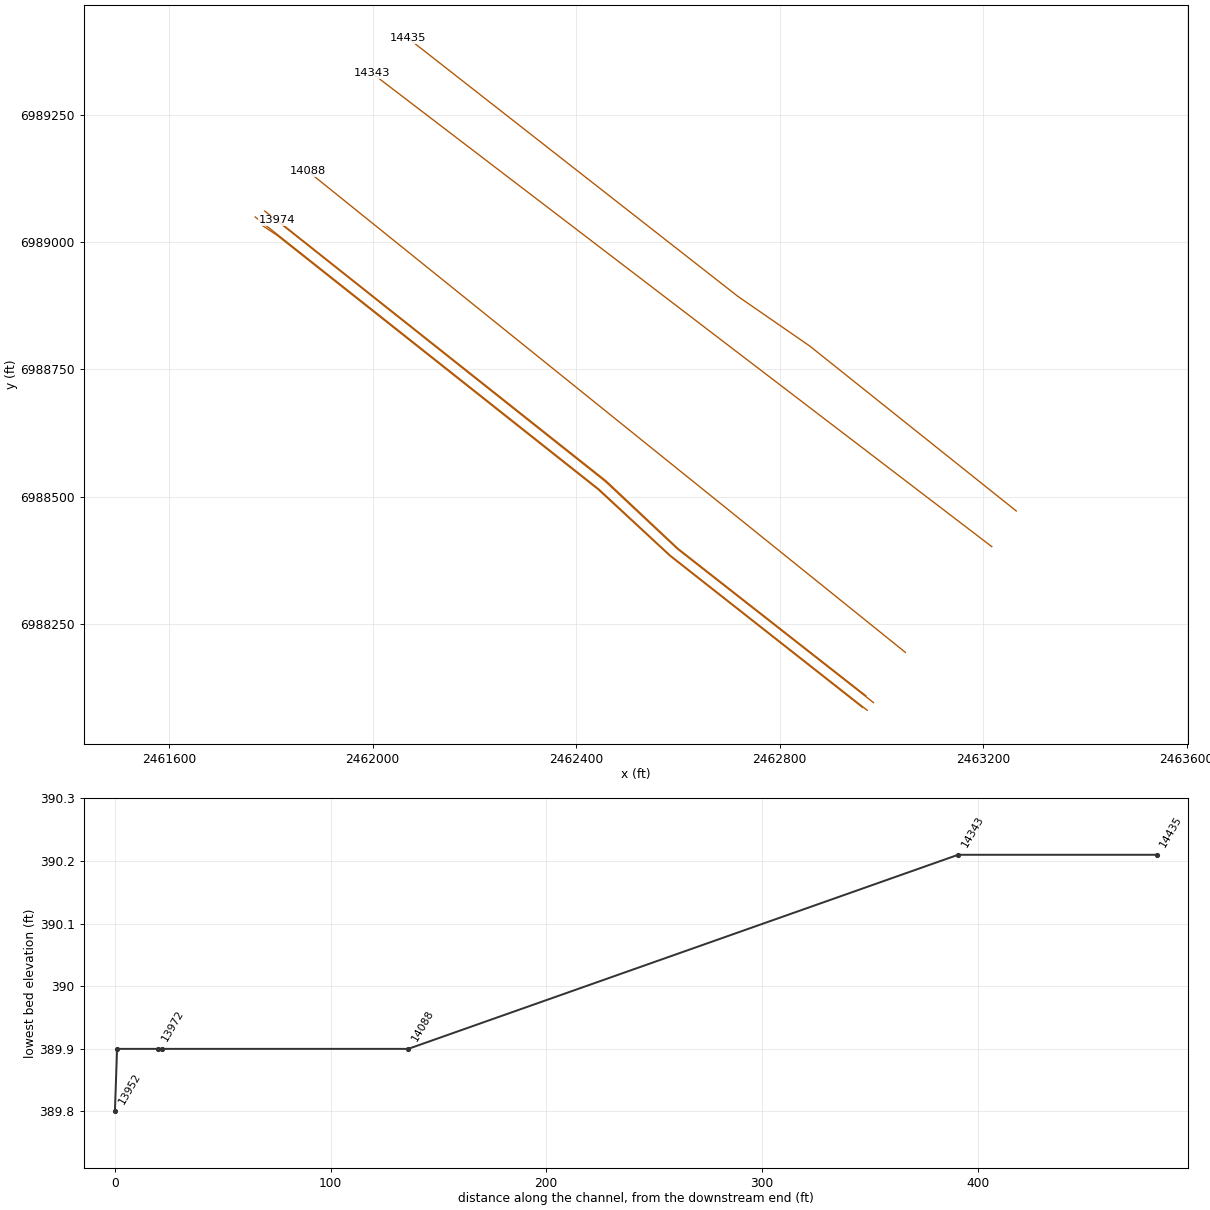
HEC-RAS study CDC_Consolidated_Model.prj: Upper Trinity CDC Consolidated Model

--- CDC_Consolidated_Model.g01 (geometry) --- (continued)

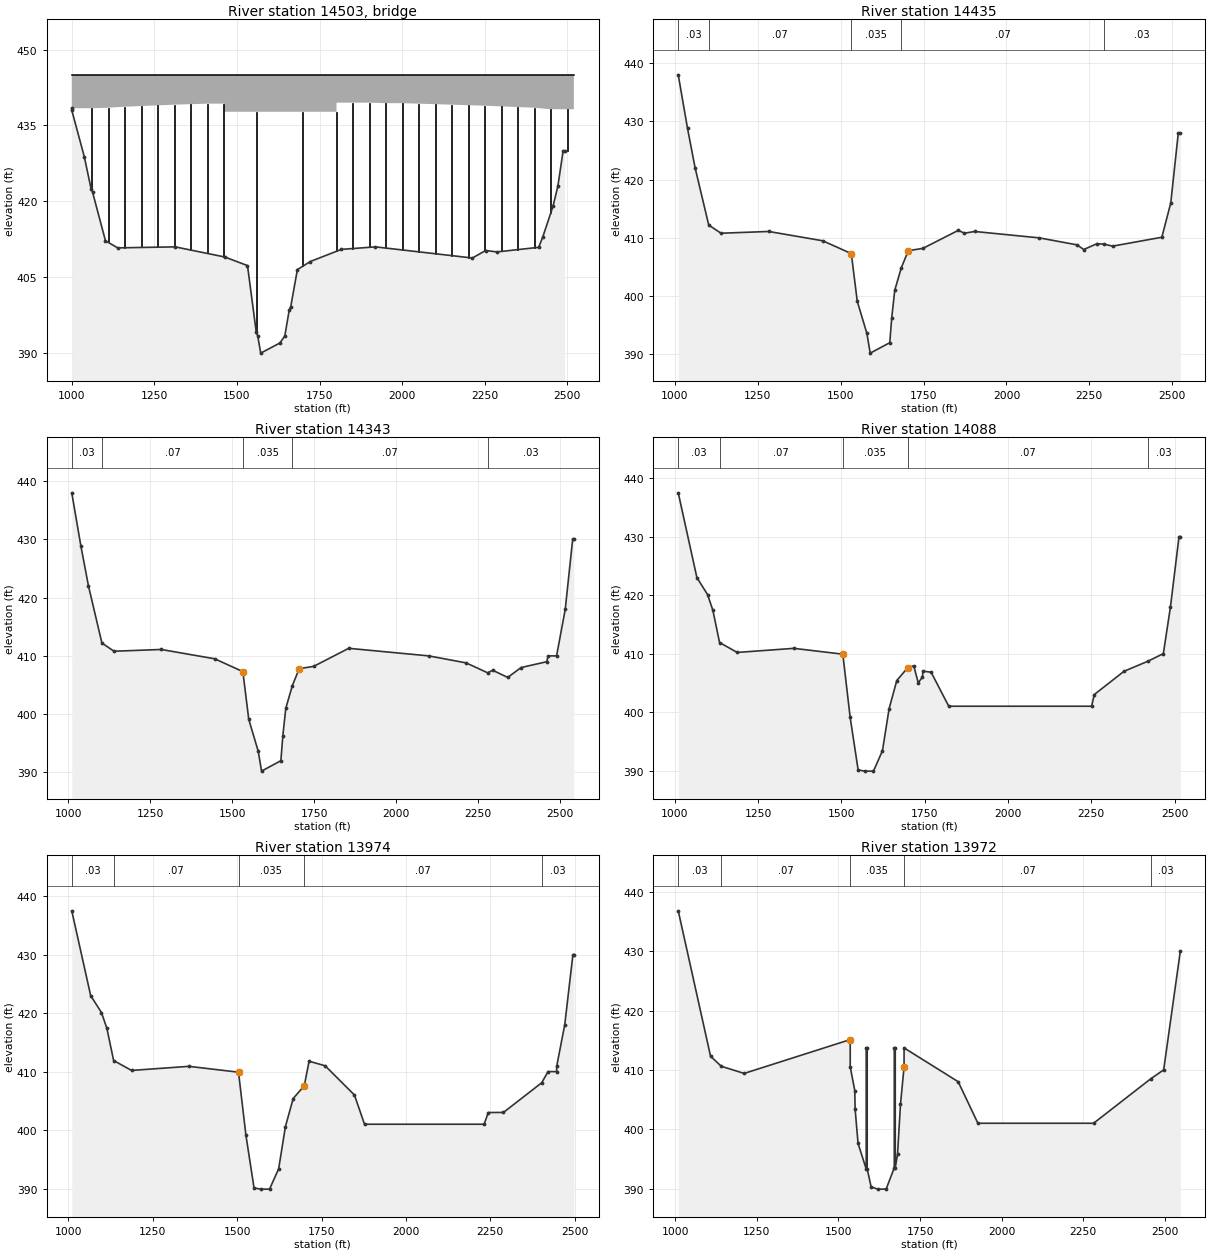
Type RM Length L Ch R = 3 ,14503   ,,,
BEGIN DESCRIPTION:
SH 183/John W. Carpenter Freeway
Data from bridge plans 1977.
END DESCRIPTION:
Node Name=SH 183
Bridge Culvert--1,0,-1,-1, 0
Deck Dist Width WeirC Skew NumUp NumDn MinLoCord MaxHiCord MaxSubmerge Is_Ogee
1,132,2.6,0, 52, 52, , , 0.95, 0, ,,,
    1000  1058.5  1061.5  1108.5  1111.5  1158.5  1161.5    1207    1213  1308.5
  1311.5  1358.5  1361.5  1408.5  1411.5  1458.5  1461.5  1461.5  1558.5  1561.5
  1698.5  1701.5  1798.5  1801.5  1801.5  1848.5  1851.5  1898.5  1901.5  1948.5
  1951.5  1998.5  2001.5  2048.5  2051.5  2098.5  2101.5  2148.5  2151.5  2198.5
  2201.5  2248.5  2251.5    2297    2303  2398.5  2401.5  2448.5  2451.5  2498.5
  2501.5    2520
     445     445     445     445     445     445     445     445     445     445
     445     445     445     445     445     445     445     445     445     445
     445     445     445     445     445     445     445     445     445     445
     445     445     445     445     445     445     445     445     445     445
     445     445     445     445     445     445     445     445     445     445
     445     445
   438.4   438.4 438.403 438.497 438.506 438.694 438.703 438.825 438.841 439.097
 439.103 439.197 439.203 439.297   439.3   439.3   439.3   437.7   437.7   437.7
   437.7   437.7   437.7   437.7   439.5   439.5   439.5   439.5 439.497 439.403
   439.4   439.4 439.397 439.303 439.297 439.203 439.197 439.103 439.097 439.003
 438.997 438.903 438.897 438.775 438.759 438.503 438.491 438.209   438.2   438.2
   438.2   438.2
    1000  1058.5  1061.5  1108.5  1111.5  1158.5  1161.5    1207    1213  1308.5
  1311.5  1358.5  1361.5  1408.5  1411.5  1458.5  1461.5  1461.5  1558.5  1561.5
  1698.5  1701.5  1798.5  1801.5  1801.5  1848.5  1851.5  1898.5  1901.5  1948.5
  1951.5  1998.5  2001.5  2048.5  2051.5  2098.5  2101.5  2148.5  2151.5  2198.5
  2201.5  2248.5  2251.5    2297    2303  2398.5  2401.5  2448.5  2451.5  2498.5
  2501.5    2520
     445     445     445     445     445     445     445     445     445     445
     445     445     445     445     445     445     445     445     445     445
     445     445     445     445     445     445     445     445     445     445
     445     445     445     445     445     445     445     445     445     445
     445     445     445     445     445     445     445     445     445     445
     445     445
   438.4   438.4 438.403 438.497 438.506 438.694 438.703 438.825 438.841 439.097
 439.103 439.197 439.203 439.297   439.3   439.3   439.3   437.7   437.7   437.7
   437.7   437.7   437.7   437.7   439.5   439.5   439.5   439.5 439.497 439.403
   439.4   439.4 439.397 439.303 439.297 439.203 439.197 439.103 439.097 439.003
 438.997 438.903 438.897 438.775 438.759 438.503 438.491 438.209   438.2   438.2
   438.2   438.2
Pier Skew, UpSta & Num, DnSta & Num=  ,1060, 2 ,1060, 2 , 0 , 0 , 0 ,,
       3       3
     390     442
       3       3
     390     442
Pier Skew, UpSta & Num, DnSta & Num=  ,1110, 2 ,1110, 2 , 0 , 0 , 0 ,,
       3       3
     390     442
       3       3
     390     442
Pier Skew, UpSta & Num, DnSta & Num=  ,1160, 2 ,1160, 2 , 0 , 0 , 0 ,,
       3       3
     390     442
       3       3
     390     442
Pier Skew, UpSta & Num, DnSta & Num=  ,1210, 2 ,1210, 2 , 0 , 0 , 0 ,,
       3       3
     390     442
       3       3
     390     442
Pier Skew, UpSta & Num, DnSta & Num=  ,1260, 2 ,1260, 2 , 0 , 0 , 0 ,,
       3       3
     390     442
       3       3
     390     442
Pier Skew, UpSta & Num, DnSta & Num=  ,1310, 2 ,1310, 2 , 0 , 0 , 0 ,,
       3       3
     390     442
       3       3
     390     442
Pier Skew, UpSta & Num, DnSta & Num=  ,1360, 2 ,1360, 2 , 0 , 0 , 0 ,,
       3       3
     390     442
       3       3
     390     442
Pier Skew, UpSta & Num, DnSta & Num=  ,1410, 2 ,1410, 2 , 0 , 0 , 0 ,,
       3       3
     390     442
       3       3
     390     442
Pier Skew, UpSta & Num, DnSta & Num=  ,1460, 2 ,1460, 2 , 0 , 0 , 0 ,,
       3       3
     390     442
       3       3
     390     442
Pier Skew, UpSta & Num, DnSta & Num=  ,1560, 2 ,1560, 2 , 0 , 0 , 0 ,,
       3       3
     390     442
       3       3
     390     442
Pier Skew, UpSta & Num, DnSta & Num=  ,1700, 2 ,1700, 2 , 0 , 0 , 0 ,,
       3       3
     390     442
       3       3
     390     442
Pier Skew, UpSta & Num, DnSta & Num=  ,1800, 2 ,1800, 2 , 0 , 0 , 0 ,,
       3       3
     390     442
       3       3
     390     442
Pier Skew, UpSta & Num, DnSta & Num=  ,1850, 2 ,1850, 2 , 0 , 0 , 0 ,,
       3       3
     390     442
       3       3
     390     442
Pier Skew, UpSta & Num, DnSta & Num=  ,1900, 2 ,1900, 2 , 0 , 0 , 0 ,,
       3       3
     390     442
       3       3
     390     442
Pier Skew, UpSta & Num, DnSta & Num=  ,1950, 2 ,1950, 2 , 0 , 0 , 0 ,,
       3       3
     390     442
       3       3
     390     442
Pier Skew, UpSta & Num, DnSta & Num=  ,2000, 2 ,2000, 2 , 0 , 0 , 0 ,,
       3       3
     390     442
       3       3
     390     442
Pier Skew, UpSta & Num, DnSta & Num=  ,2050, 2 ,2050, 2 , 0 , 0 , 0 ,,
       3       3
     390     442
       3       3
     390     442
Pier Skew, UpSta & Num, DnSta & Num=  ,2100, 2 ,2100, 2 , 0 , 0 , 0 ,,
       3       3
     390     442
       3       3
     390     442
Pier Skew, UpSta & Num, DnSta & Num=  ,2150, 2 ,2150, 2 , 0 , 0 , 0 ,,
       3       3
     390     442
       3       3
     390     442
Pier Skew, UpSta & Num, DnSta & Num=  ,2200, 2 ,2200, 2 , 0 , 0 , 0 ,,
       3       3
     390     442
       3       3
     390     442
Pier Skew, UpSta & Num, DnSta & Num=  ,2250, 2 ,2250, 2 , 0 , 0 , 0 ,,
       3       3
     390     442
       3       3
     390     442
Pier Skew, UpSta & Num, DnSta & Num=  ,2300, 2 ,2300, 2 , 0 , 0 , 0 ,,
       3       3
     390     442
       3       3
     390     442
Pier Skew, UpSta & Num, DnSta & Num=  ,2350, 2 ,2350, 2 , 0 , 0 , 0 ,,
       3       3
     390     442
       3       3
     390     442
Pier Skew, UpSta & Num, DnSta & Num=  ,2400, 2 ,2400, 2 , 0 , 0 , 0 ,,
       3       3
     390     442
       3       3
     390     442
Pier Skew, UpSta & Num, DnSta & Num=  ,2450, 2 ,2450, 2 , 0 , 0 , 0 ,,
       3       3
     390     442
       3       3
     390     442
Pier Skew, UpSta & Num, DnSta & Num=  ,2500, 2 ,2500, 2 , 0 , 0 , 0 ,,
       3       3
     390     442
       3       3
     390     442
BR Coef= 1 , 0 , 0 ,1.05, 0 ,,,0.8,-1,0.5,1,
WSPro=,,,, 1 ,,,, 0 ,,,, 0 ,,,,-1 ,-1 ,-1 , 0 , 0 , 0 , 0 , 0
BC Design=,, 0 ,, 0 ,,,,,,
BC HTab HWMax=438.4
BC Use User HTab Curves=0
BC User HTab FreeFlow(D)= 0

Type RM Length L Ch R = 1 ,14435   ,92,92,92
BEGIN DESCRIPTION:
This cross section corresponds to cross section 14411 of the non-georeferenced CDC model which was the source of this model.
Proposed grading for levee overbank.
Right Overbank updated with 2007 levee topo.
One-foot downstream of S.H. 183.
END DESCRIPTION:
XS GIS Cut Line= 4
2463265.036428756988471.588757382462859.100560846988795.77282029
2462717.625450076988893.593162722462069.660538676989400.73420879
#Sta/Elev= 30
    1010     438    1038   428.8    1061     422    1102   412.2    1139   410.8
    1283   411.1    1446   409.5    1532   407.3    1550   399.1    1579   393.6
    1589  390.21    1648     392    1654   396.3    1663     401    1683   404.9
    1704   407.8    1748   408.2    1855   411.3    1873   410.8    1904   411.1
    2099     410    2213   408.8    2233     408 2272.88     409 2294.92  408.92
 2319.94  408.58 2468.66  410.11 2495.52     416 2518.23     428 2524.33     428
#Mann= 5 ,-1,0
    1010     .03       0    1102     .07       0    1532    .035       0
    1683     .07       0 2294.92     .03       0
#XS Ineff= 2 , 0
       0    1532   407.3    1704       0   407.8
Permanent Ineff=
       F       F
Bank Sta=1532,1704
XS Rating Curve= 0 ,0
Exp/Cntr=0.3,0.1

Type RM Length L Ch R = 1 ,14343   ,255,255,255
BEGIN DESCRIPTION:
This cross section corresponds to cross section 14317 of the non-georeferenced CDC model which was the source of this model.
Proposed grading for levee overbank.
Right Overbank updated with 2007 levee topo.
Cross-section EF021.  95 feet downstream of S.H. 183.  Effective flow limit set at East Levee in LOB, at Irving Flood Control District No. 1 Levee (Northwest Levee) in ROB.
Channel data from COD Elm Fork channel survey - cross-section EF#021 surveyed April 1994.
END DESCRIPTION:
XS GIS Cut Line= 2
2463216.977469746988401.485551132461999.679051346989331.40429497
#Sta/Elev= 30
    1010     438    1038   428.8    1061     422    1102   412.2    1139   410.8
    1283   411.1    1446   409.5    1532   407.3    1550   399.1    1579   393.6
    1589  390.21    1648     392    1654   396.3    1663     401    1683   404.9
    1704   407.8    1748   408.2    1855   411.3    2099     410    2213   408.8
    2279  407.09 2294.24  407.53 2340.04   406.3 2380.98     408 2459.29     409
  2463.3     410 2489.18     410 2515.63     418 2538.26     430 2541.85     430
#Mann= 5 ,-1,0
    1010     .03       0    1102     .07       0    1532    .035       0
    1683     .07       0    2279     .03       0
#XS Ineff= 2 , 0
       0    1532   407.3    1704       0   407.8
Permanent Ineff=
       F       F
Bank Sta=1532,1704
XS Rating Curve= 0 ,0
Exp/Cntr=0.3,0.1

Type RM Length L Ch R = 1 ,14088   ,114,114,114
BEGIN DESCRIPTION:
This cross section corresponds to cross section 14062 of the non-georeferenced CDC model which was the source of this model.
Proposed grading for borrow pit and levee overbank.
Cross-section EF020.  Effective flow limit set at East Levee in LOB, at Irving Flood Control District No. 1 Levee (Northwest Levee) in LOB.
Channel data from COD Elm Fork channel survey.
END DESCRIPTION:
XS GIS Cut Line= 2
2463047.122166436988193.733998132461873.421757946989138.87712097
#Sta/Elev= 30
    1010   437.5    1066     423    1098   420.1    1114   417.4    1134   411.9
    1187   410.2    1357   410.9    1504   409.9    1526   399.1    1550   390.1
    1570   389.9    1596   389.9    1623   393.4    1643   400.6    1666   405.4
    1699   407.6    1717   407.9 1730.33     405 1743.02     406 1744.38     407
 1768.99  406.82  1821.9     401 2250.75     401 2258.75     403 2348.05  406.98
 2419.59  408.69    2466     410 2487.41     418 2513.01     430 2516.94     430
#Mann= 5 ,-1,0
    1010     .03       0    1134     .07       0    1504    .035       0
    1699     .07       0 2419.59     .03       0
#XS Ineff= 2 , 0
       0    1504   409.9    1699       0   407.6
Permanent Ineff=
       F       F
Bank Sta=1504,1699
XS Rating Curve= 0 ,0
Exp/Cntr=0.3,0.1

Type RM Length L Ch R = 1 ,13974   ,2,2,2
BEGIN DESCRIPTION:
This cross section corresponds to cross section 13962 of the non-georeferenced CDC model which was the source of this model.
Proposed grading for borrow pit and levee overbank.
Right Overbank updated with 2007 levee topo and borrow pit topography.
Channel data from COD Elm Fork channel survey.
END DESCRIPTION:
XS GIS Cut Line= 4
2462969.44351602 6988108.49860432462600.548912586988397.58332796
2462459.242436686988530.428206642461812.814267586989042.76871738
#Sta/Elev= 30
    1010   437.5    1066     423    1098   420.1    1114   417.4    1134   411.9
    1187   410.2    1357   410.9    1504   409.9    1526   399.1    1550   390.1
    1570   389.9    1596   389.9    1623   393.4    1643   400.6    1666   405.4
    1699   407.6 1713.01  411.78 1760.53     411 1847.45     406 1877.26     401
  2231.7     401 2243.95     403 2289.02  403.02 2402.17  408.09  2421.1     410
 2446.52     410 2446.68  410.92 2470.46     418 2494.68     430 2497.46     430
#Mann= 5 ,-1,0
    1010     .03       0    1134     .07       0    1504    .035       0
    1699     .07       0 2402.17     .03       0
#XS Ineff= 2 , 0
       0    1504   409.9    1699       0   407.6
Permanent Ineff=
       F       F
Bank Sta=1504,1699
XS Rating Curve= 0 ,0
Exp/Cntr=0.3,0.1

Type RM Length L Ch R = 1 ,13972   ,19,19,19
BEGIN DESCRIPTION:
This cross section corresponds to cross section 13961 of the non-georeferenced CDC model which was the source of this model.
Proposed grading for borrow pit and levee overbank.
Right Overbank updated with 2007 levee topo and borrow pit topo.
END DESCRIPTION:
XS GIS Cut Line= 4
2462984.652475096988094.885770632462599.451801936988396.62565272
2462457.15484244 6988529.85209232461788.142729016989060.98652871
#Sta/Elev= 30
    1009   436.8    1108   412.3    1141   410.6    1211   409.4    1536   415.1
    1536   410.5    1550   406.5    1551   403.4    1560   397.6    1585   393.3
    1585   413.7    1588   413.7    1588   393.3    1600   390.3    1620   389.9
    1646   389.9    1671   393.5    1671   413.7    1674   413.7    1674   393.5
    1681   395.8    1690   404.2    1701   410.5    1701   413.7 1866.84     408
 1927.26     401  2281.7     401 2456.52  408.48 2496.52     410 2547.46     430
#Mann= 5 ,-1,0
    1009     .03       0    1141     .07       0    1536    .035       0
    1701     .07       0 2456.52     .03       0
#XS Ineff= 2 , 0
       0    1536   415.1    1701       0   410.5
Permanent Ineff=
       F       F
Bank Sta=1536,1701
XS Rating Curve= 0 ,0
Exp/Cntr=0.3,0.1

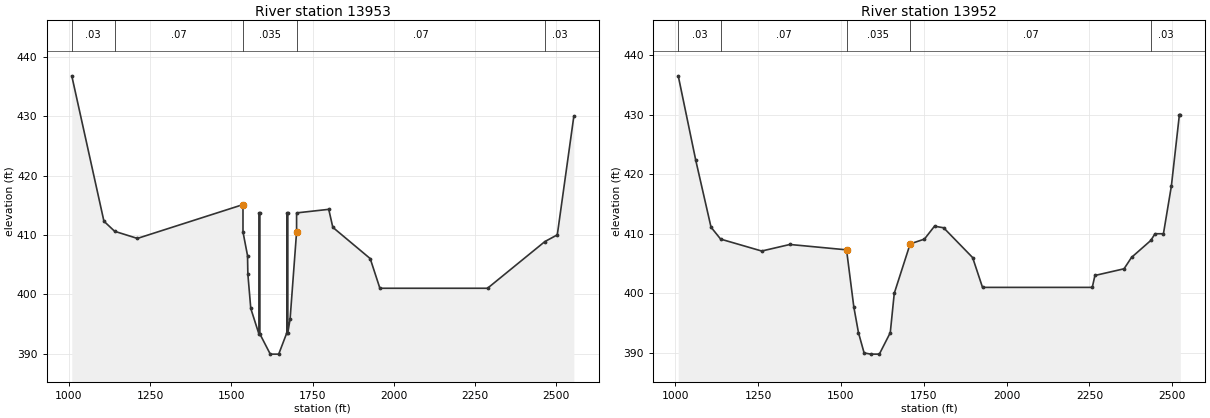
Type RM Length L Ch R = 1 ,13953   ,1,1,1
BEGIN DESCRIPTION:
This cross section corresponds to cross section 13941 of the non-georeferenced CDC model which was the source of this model.
Proposed grading for borrow pit and levee overbank.
Right Overbank updated with 2007 levee topo and borrow pit topo. Site of old Proctor Street bridge.  Steel trestle bridge and deck removed in 1994.  Steel bridge piers remain in channel. Effective flow limit set at East Levee in LOB, at Irving Flood Control District No.1 Levee (Northwest Levee) in ROB. Channel data from COD Elm For
END DESCRIPTION:
XS GIS Cut Line= 4
2462972.107224586988079.919265142462585.26515052 6988384.1063208
 2462444.83268866988514.452516792461769.316979266989049.42093505
#Sta/Elev= 30
    1009   436.8    1108   412.3    1141   410.6    1211   409.4    1536   415.1
    1536   410.5    1550   406.5    1551   403.4    1560   397.6    1585   393.3
    1585   413.7    1588   413.7    1588   393.3    1620   389.9    1646   389.9
    1671   393.5    1671   413.7    1674   413.7    1674   393.5    1681   395.8
    1701   410.5    1701   413.7    1800   414.3 1812.52  411.27  1927.6     406
 1957.41     401  2288.7     401 2465.25  408.87 2503.47     410 2554.41     430
#Mann= 5 ,-1,0
    1009     .03       0    1141     .07       0    1536    .035       0
    1701     .07       0 2465.25     .03       0
#XS Ineff= 2 , 0
       0    1536   415.1    1701       0   410.5
Permanent Ineff=
       F       F
Bank Sta=1536,1701
XS Rating Curve= 0 ,0
Exp/Cntr=0.3,0.1

Type RM Length L Ch R = 1 ,13952   ,84,84,84
BEGIN DESCRIPTION:
This cross section corresponds to cross section 13940 of the non-georeferenced CDC model which was the source of this model.
Proposed grading for borrow pit and levee overbank.
Right Overbank updated with 2007 levee topo and borrow pit topo.
END DESCRIPTION:
XS GIS Cut Line= 5
2462962.927124836988085.442219972462584.427881846988383.21065331
2462443.641089926988513.475812722461812.113809686989013.52960263
2461781.766757526989033.76118946
#Sta/Elev= 30
    1009   436.5    1062   422.3    1108   411.1    1137   409.1    1261   407.1
    1346   408.2    1517   407.3    1539   397.7    1553   393.4    1570     390
    1590   389.8    1616   389.8    1649   393.4    1661     400    1709   408.3
    1752   409.1 1782.51  411.27 1810.06     411 1897.59     406  1927.4     401
 2258.69     401 2266.69     403 2354.58  404.12 2377.12  406.03 2435.24  408.87
 2448.09     410 2473.46     410 2497.41     418 2521.67     430  2524.4     430
#Mann= 5 ,-1,0
    1009     .03       0    1137     .07       0    1517    .035       0
    1709     .07       0 2435.24     .03       0
#XS Ineff= 2 , 0
       0    1517   407.3    1709       0   408.3
Permanent Ineff=
       F       F
Bank Sta=1517,1709
XS Rating Curve= 0 ,0
Exp/Cntr=0.3,0.1