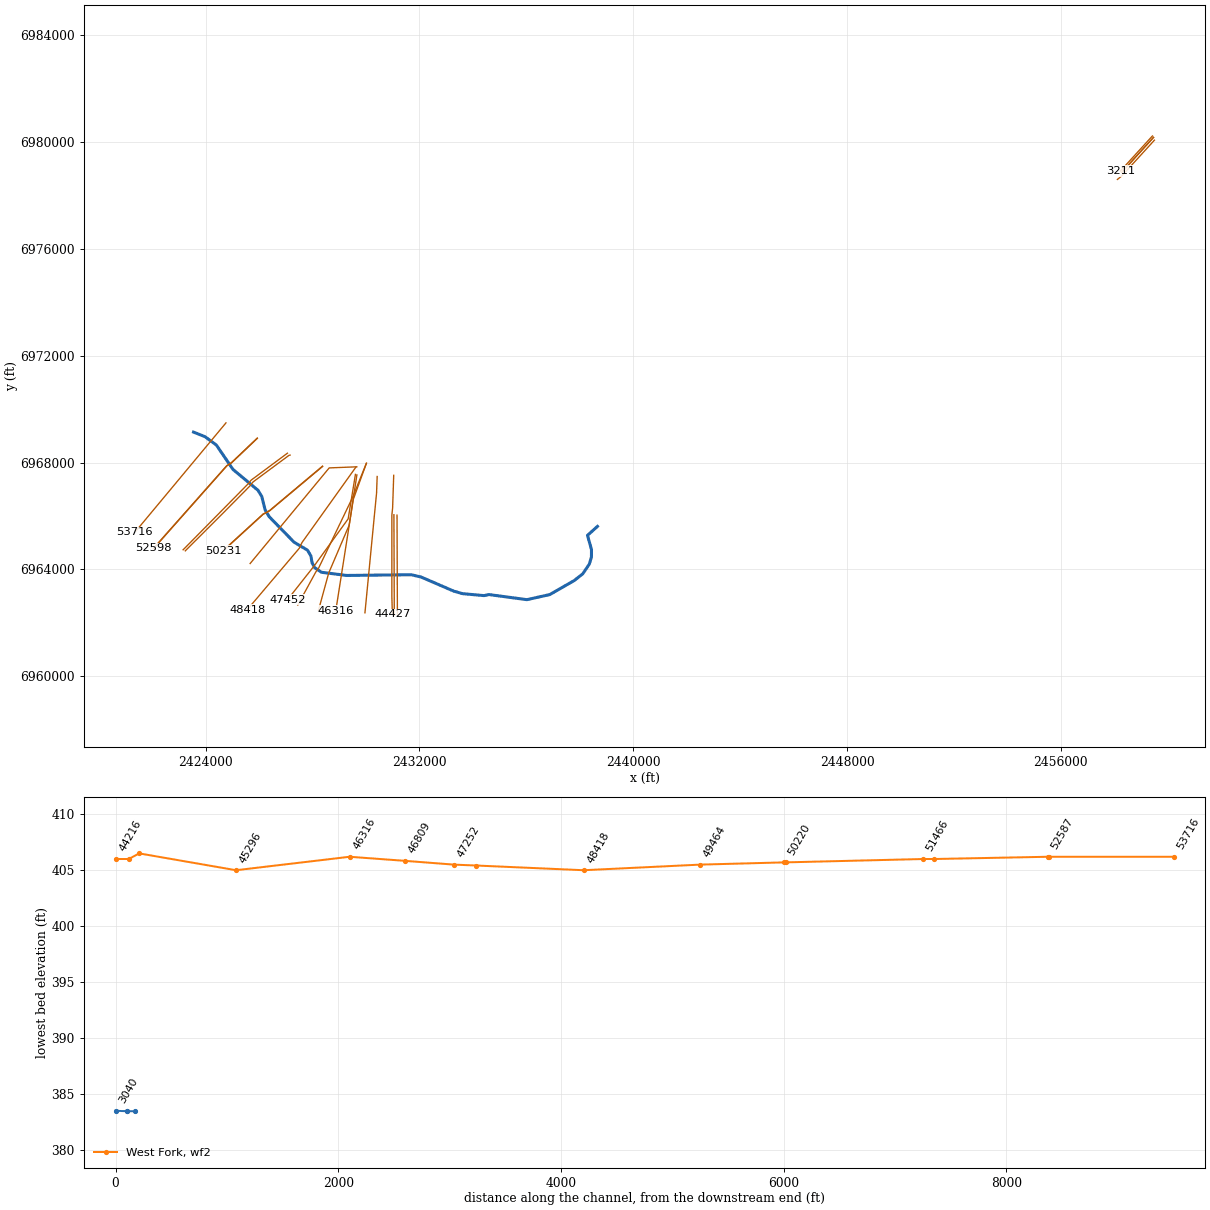
HEC-RAS study CDC_Consolidated_Model.prj: Upper Trinity CDC Consolidated Model

--- CDC_Consolidated_Model.g01 (geometry) --- (continued)

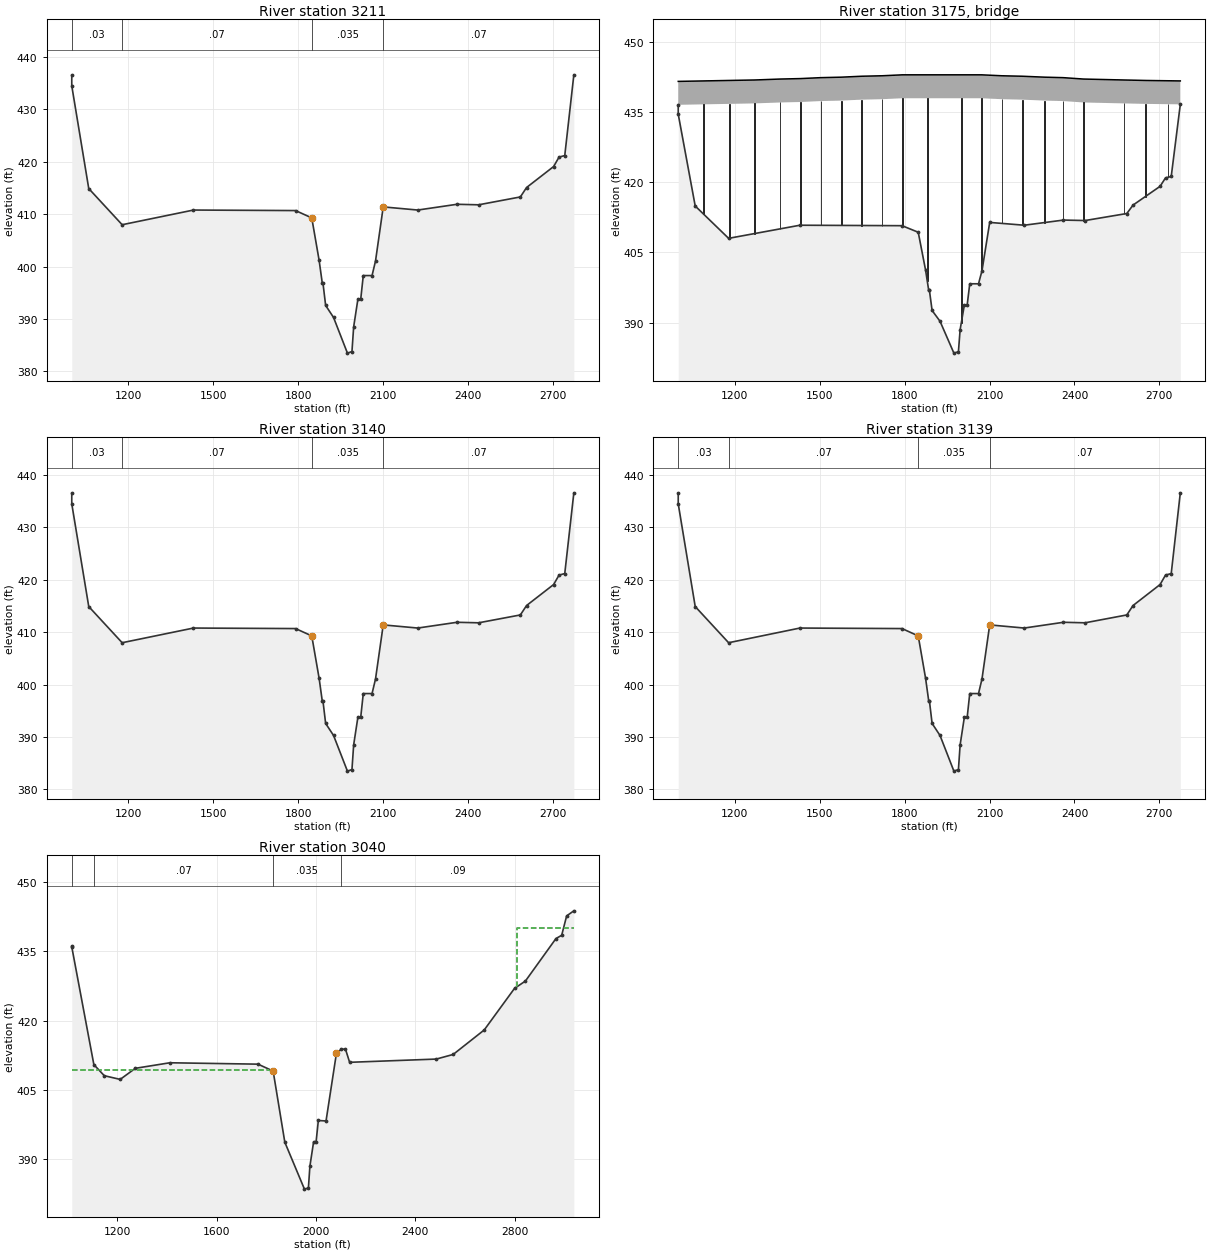
Type RM Length L Ch R = 1 ,3211    ,71,71,71
BEGIN DESCRIPTION:
This cross section corresponds to cross section 3190 of the non-georeferenced CDC model which was the source of this model.
One-foot upstream of Shady Grove Road.  East Levee at LOB.  Channel data from COD Elm Fork channel survey.
END DESCRIPTION:
XS GIS Cut Line= 3
2459425.753424916980231.53830838 2458789.85541856979535.99278347
2458230.308309266978920.82012931
#Sta/Elev= 30
    1000   436.5    1000   434.5    1060   414.9    1178     408    1430   410.8
 1790.75   410.7    1848   409.3    1874   401.2    1885   396.9  1887.5   396.9
    1897   392.6    1925   390.3    1974   383.5    1990   383.8    1996   388.5
    2011   393.8    2021   393.8    2030   398.3    2061   398.3 2073.25 401.084
  2100.5   411.4  2222.5   410.8 2361.25   411.9  2437.5   411.8    2585   413.3
    2607   415.1  2702.5   419.1  2721.7   420.9  2741.9   421.2    2774   436.6
#Mann= 4 ,-1,0
    1000     .03       0    1178     .07       0    1848    .035       0
  2100.5     .07       0
#XS Ineff= 2 , 0
       0    1848   409.3  2100.5       0   411.4
Permanent Ineff=
       F       F
Bank Sta=1848,2100.5
XS Rating Curve= 0 ,0
Exp/Cntr=0.5,0.3

Type RM Length L Ch R = 3 ,3175    ,,,
BEGIN DESCRIPTION:
Shady Grove Road
END DESCRIPTION:
Node Name=Shady Grove Road
Bridge Culvert--1,0,-1,-1, 0
Deck Dist Width WeirC Skew NumUp NumDn MinLoCord MaxHiCord MaxSubmerge Is_Ogee
2,68,2.6,0, 46, 46, , , 0.95, 0, ,,,
    1000  1088.5 1088.75 1091.25  1091.5 1178.75 1181.25 1268.75 1271.25 1358.75
 1361.25 1430.75 1433.25 1502.75 1505.25 1574.75 1577.25 1646.75 1649.25 1718.75
 1721.25 1790.75 1793.25 1878.75 1881.25 1998.75 2001.25 2070.75 2073.25 2142.75
 2145.25 2214.75 2217.25 2293.75 2296.25 2358.75 2361.25 2430.75 2433.25 2573.75
 2576.25 2648.75 2651.25 2728.75 2731.25    2774
   441.5 441.598 441.599 441.601 441.602 441.699 441.701 441.799 441.803 441.997
 442.002 442.098 442.103 442.297 442.302 442.398 442.404 442.596 442.602 442.698
 442.703 442.897   442.9   442.9   442.9   442.9   442.9   442.9 442.897 442.703
 442.698 442.602 442.597 442.403 442.398 442.302 442.295 442.005 441.998 441.802
 441.798 441.702 441.698 441.636 441.634   441.6
   436.5 436.598 436.599 436.601 436.602 436.699 436.701 436.799 436.803 436.997
 437.002 437.098 437.103 437.297 437.302 437.398 437.404 437.596 437.602 437.698
 437.703 437.897   437.9   437.9   437.9   437.9   437.9   437.9 437.897 437.703
 437.698 437.602 437.597 437.403 437.398 437.302 437.295 437.005 436.998 436.802
 436.798 436.702 436.698 436.636 436.634   436.6
    1000  1088.5 1088.75 1091.25  1091.5 1178.75 1181.25 1268.75 1271.25 1358.75
 1361.25 1430.75 1433.25 1502.75 1505.25 1574.75 1577.25 1646.75 1649.25 1718.75
 1721.25 1790.75 1793.25 1878.75 1881.25 1998.75 2001.25 2070.75 2073.25 2142.75
 2145.25 2214.75 2217.25 2293.75 2296.25 2358.75 2361.25 2430.75 2433.25 2573.75
 2576.25 2648.75 2651.25 2728.75 2731.25    2774
   441.5 441.598 441.599 441.601 441.602 441.699 441.701 441.799 441.803 441.997
 442.002 442.098 442.103 442.297 442.302 442.398 442.404 442.596 442.602 442.698
 442.703 442.897   442.9   442.9   442.9   442.9   442.9   442.9 442.897 442.703
 442.698 442.602 442.597 442.403 442.398 442.302 442.295 442.005 441.998 441.802
 441.798 441.702 441.698 441.636 441.634   441.6
   436.5 436.598 436.599 436.601 436.602 436.699 436.701 436.799 436.803 436.997
 437.002 437.098 437.103 437.297 437.302 437.398 437.404 437.596 437.602 437.698
 437.703 437.897   437.9   437.9   437.9   437.9   437.9   437.9 437.897 437.703
 437.698 437.602 437.597 437.403 437.398 437.302 437.295 437.005 436.998 436.802
 436.798 436.702 436.698 436.636 436.634   436.6
Pier Skew, UpSta & Num, DnSta & Num=  ,1090, 2 ,1090, 2 , 0 , 0 , 0 ,,
     2.5     2.5
       0     440
     2.5     2.5
       0     440
Pier Skew, UpSta & Num, DnSta & Num=  ,1180, 2 ,1180, 2 , 0 , 0 , 0 ,,
     2.5     2.5
       0     440
     2.5     2.5
       0     440
Pier Skew, UpSta & Num, DnSta & Num=  ,1270, 2 ,1270, 2 , 0 , 0 , 0 ,,
     2.5     2.5
       0     440
     2.5     2.5
       0     440
Pier Skew, UpSta & Num, DnSta & Num=  ,1360, 2 ,1360, 2 , 0 , 0 , 0 ,,
     2.5     2.5
       0     440
     2.5     2.5
       0     440
Pier Skew, UpSta & Num, DnSta & Num=  ,1432, 2 ,1432, 2 , 0 , 0 , 0 ,,
     2.5     2.5
       0     440
     2.5     2.5
       0     440
Pier Skew, UpSta & Num, DnSta & Num=  ,1504, 2 ,1504, 2 , 0 , 0 , 0 ,,
     2.5     2.5
       0     440
     2.5     2.5
       0     440
Pier Skew, UpSta & Num, DnSta & Num=  ,1576, 2 ,1576, 2 , 0 , 0 , 0 ,,
     2.5     2.5
       0     440
     2.5     2.5
       0     440
Pier Skew, UpSta & Num, DnSta & Num=  ,1648, 2 ,1648, 2 , 0 , 0 , 0 ,,
     2.5     2.5
       0     440
     2.5     2.5
       0     440
Pier Skew, UpSta & Num, DnSta & Num=  ,1720, 2 ,1720, 2 , 0 , 0 , 0 ,,
     2.5     2.5
       0     440
     2.5     2.5
       0     440
Pier Skew, UpSta & Num, DnSta & Num=  ,1792, 2 ,1792, 2 , 0 , 0 , 0 ,,
     2.5     2.5
       0     440
     2.5     2.5
       0     440
Pier Skew, UpSta & Num, DnSta & Num=  ,1880, 2 ,1880, 2 , 0 , 0 , 0 ,,
     2.5     2.5
       0     440
     2.5     2.5
       0     440
Pier Skew, UpSta & Num, DnSta & Num=  ,2000, 2 ,2000, 2 , 0 , 0 , 0 ,,
     2.5     2.5
       0     440
     2.5     2.5
       0     440
Pier Skew, UpSta & Num, DnSta & Num=  ,2072, 2 ,2072, 2 , 0 , 0 , 0 ,,
     2.5     2.5
       0     440
     2.5     2.5
       0     440
Pier Skew, UpSta & Num, DnSta & Num=  ,2144, 2 ,2144, 2 , 0 , 0 , 0 ,,
     2.5     2.5
       0     440
     2.5     2.5
       0     440
Pier Skew, UpSta & Num, DnSta & Num=  ,2216, 2 ,2216, 2 , 0 , 0 , 0 ,,
     2.5     2.5
       0     440
     2.5     2.5
       0     440
Pier Skew, UpSta & Num, DnSta & Num=  ,2295, 2 ,2295, 2 , 0 , 0 , 0 ,,
     2.5     2.5
       0     440
     2.5     2.5
       0     440
Pier Skew, UpSta & Num, DnSta & Num=  ,2360, 2 ,2360, 2 , 0 , 0 , 0 ,,
     2.5     2.5
       0     440
     2.5     2.5
       0     440
Pier Skew, UpSta & Num, DnSta & Num=  ,2432, 2 ,2432, 2 , 0 , 0 , 0 ,,
     2.5     2.5
       0     440
     2.5     2.5
       0     440
Pier Skew, UpSta & Num, DnSta & Num=  ,2575, 2 ,2575, 2 , 0 , 0 , 0 ,,
     2.5     2.5
       0     440
     2.5     2.5
       0     440
Pier Skew, UpSta & Num, DnSta & Num=  ,2650, 2 ,2650, 2 , 0 , 0 , 0 ,,
     2.5     2.5
       0     440
     2.5     2.5
       0     440
Pier Skew, UpSta & Num, DnSta & Num=  ,2730, 2 ,2730, 2 , 0 , 0 , 0 ,,
     2.5     2.5
       0     440
     2.5     2.5
       0     440
BR Coef= 1 , 0 , 0 ,1.05, 0 ,,,0.8,-1,0.5,1,
WSPro=,,,, 1 ,,,, 0 ,,,, 0 ,,,,-1 ,-1 ,-1 , 0 , 0 , 0 , 0 , 0
BC Design=,, 0 ,, 0 ,,,,,,
BC HTab HWMax=436.6
BC Use User HTab Curves=0
BC User HTab FreeFlow(D)= 0

Type RM Length L Ch R = 1 ,3140    ,1,1,1
BEGIN DESCRIPTION:
This cross section corresponds to cross section 3119 of the non-georeferenced CDC model which was the source of this model.
END DESCRIPTION:
XS GIS Cut Line= 3
2459466.637857596980178.474438132458826.652588996979475.10839079
2458275.535909096978863.81269738
#Sta/Elev= 30
    1000   436.5    1000   434.5    1060   414.9    1178     408    1430   410.8
 1790.75   410.7    1848   409.3    1874   401.2    1885   396.9  1887.5   396.9
    1897   392.6    1925   390.3    1974   383.5    1990   383.8    1996   388.5
    2011   393.8    2021   393.8    2030   398.3    2061   398.3 2073.25 401.084
  2100.5   411.4  2222.5   410.8 2361.25   411.9  2437.5   411.8    2585   413.3
    2607   415.1  2702.5   419.1  2721.7   420.9  2741.9   421.2    2774   436.6
#Mann= 4 ,-1,0
    1000     .03       0    1178     .07       0    1848    .035       0
  2100.5     .07       0
Bank Sta=1848,2100.5
XS Rating Curve= 0 ,0
Exp/Cntr=0.5,0.3

Type RM Length L Ch R = 1 ,3139    ,99,99,99
BEGIN DESCRIPTION:
This cross section corresponds to cross section 3118 of the non-georeferenced CDC model which was the source of this model.
One-foot downstream of Shady Grove Road.  Duplication of following bridge cross-section (3119) without bridge piers.  Channel data from COD Elm Fork channel survey.
END DESCRIPTION:
XS GIS Cut Line= 3
2459467.939364176980177.220831722458827.149635266979474.23831379
2458276.238335526978863.11223947
#Sta/Elev= 30
    1000   436.5    1000   434.5    1060   414.9    1178     408    1430   410.8
 1790.75   410.7    1848   409.3    1874   401.2    1885   396.9  1887.5   396.9
    1897   392.6    1925   390.3    1974   383.5    1990   383.8    1996   388.5
    2011   393.8    2021   393.8    2030   398.3    2061   398.3 2073.25 401.084
  2100.5   411.4  2222.5   410.8 2361.25   411.9  2437.5   411.8    2585   413.3
    2607   415.1  2702.5   419.1  2721.7   420.9  2741.9   421.2    2774   436.6
#Mann= 4 ,-1,0
    1000     .03       0    1178     .07       0    1848    .035       0
  2100.5     .07       0
#XS Ineff= 2 , 0
       0    1848   409.3  2100.5       0   411.4
Permanent Ineff=
       F       F
Bank Sta=1848,2100.5
XS Rating Curve= 0 ,0
Exp/Cntr=0.3,0.1

Type RM Length L Ch R = 1 ,3040    ,0,0,0
BEGIN DESCRIPTION:
This cross section corresponds to cross section 3013 of the non-georeferenced CDC model which was the source of this model.
Cross-section EF001.  3013 feet upstream of West Fork/Elm Fork confluence.
106 feet downstream of Shady Grove Road.  McPeeter's property in ROB downstream to West Fork/Elm Fork confluence.  Effective flow limit set at East Levee in LOB, at sta 2810 in ROB.  Channel data from COD Elm Fork channel survey - cross-section EF#001 surveyed February 1994.
END DESCRIPTION:
XS GIS Cut Line= 3
2459501.03050533 6980073.93002782458285.60905167 6978741.9130068
2458116.621856846978602.92345539
#Sta/Elev= 30
    1017   436.1    1017     436    1106   410.5    1148   408.1    1212   407.3
    1273   409.7    1412   410.9    1767   410.6    1828   409.1    1875   393.7
    1954  383.54    1970   383.8    1976   388.5    1991   393.8    2001   393.8
    2010   398.4    2041   398.3    2083     413    2102   413.8    2119   413.9
    2136     411    2485   411.7    2553   412.7    2678     418    2800     427
    2844   428.6    2967   437.8    2990   438.5    3010   442.7    3039   443.8
#Mann= 4 ,-1,0
    1017     .03       0    1106     .07       0    1828    .035       0
    2102     .09       0
#XS Ineff= 3 ,-1
    1000    1828   409.3    2083    2810     411    2810    3039     440
Permanent Ineff=
       F       F       F
Bank Sta=1828,2083
XS Rating Curve= 0 ,0
Exp/Cntr=0.3,0.1

River Reach=West Fork       ,wf2
Reach XY= 30
      2423548.65      6969142.43      2423976.25      6968970.81
      2424403.02      6968655.85      2425023.17      6967744.39
      2425959.14      6966962.71      2426098.85       6966734.7
      2426227.36      6966224.62      2426380.15      6965972.72
       2427305.8      6965022.61      2427810.75      6964721.15
      2427940.56      6964501.17      2427981.58      6964249.07
      2428077.14      6964069.59      2428334.72      6963893.06
      2429276.94      6963774.78      2431694.52      6963801.24
       2432063.1      6963714.52      2433284.44      6963187.31
      2433611.14      6963093.15      2434417.15      6963019.71
      2434599.32      6963059.56      2436019.26      6962867.72
      2436877.34      6963058.67      2437797.07      6963587.52
      2438107.52       6963832.5      2438354.79      6964195.56
      2438435.95      6964465.48      2438436.94      6964747.33
      2438287.28      6965275.21        2438660.      6965610.97

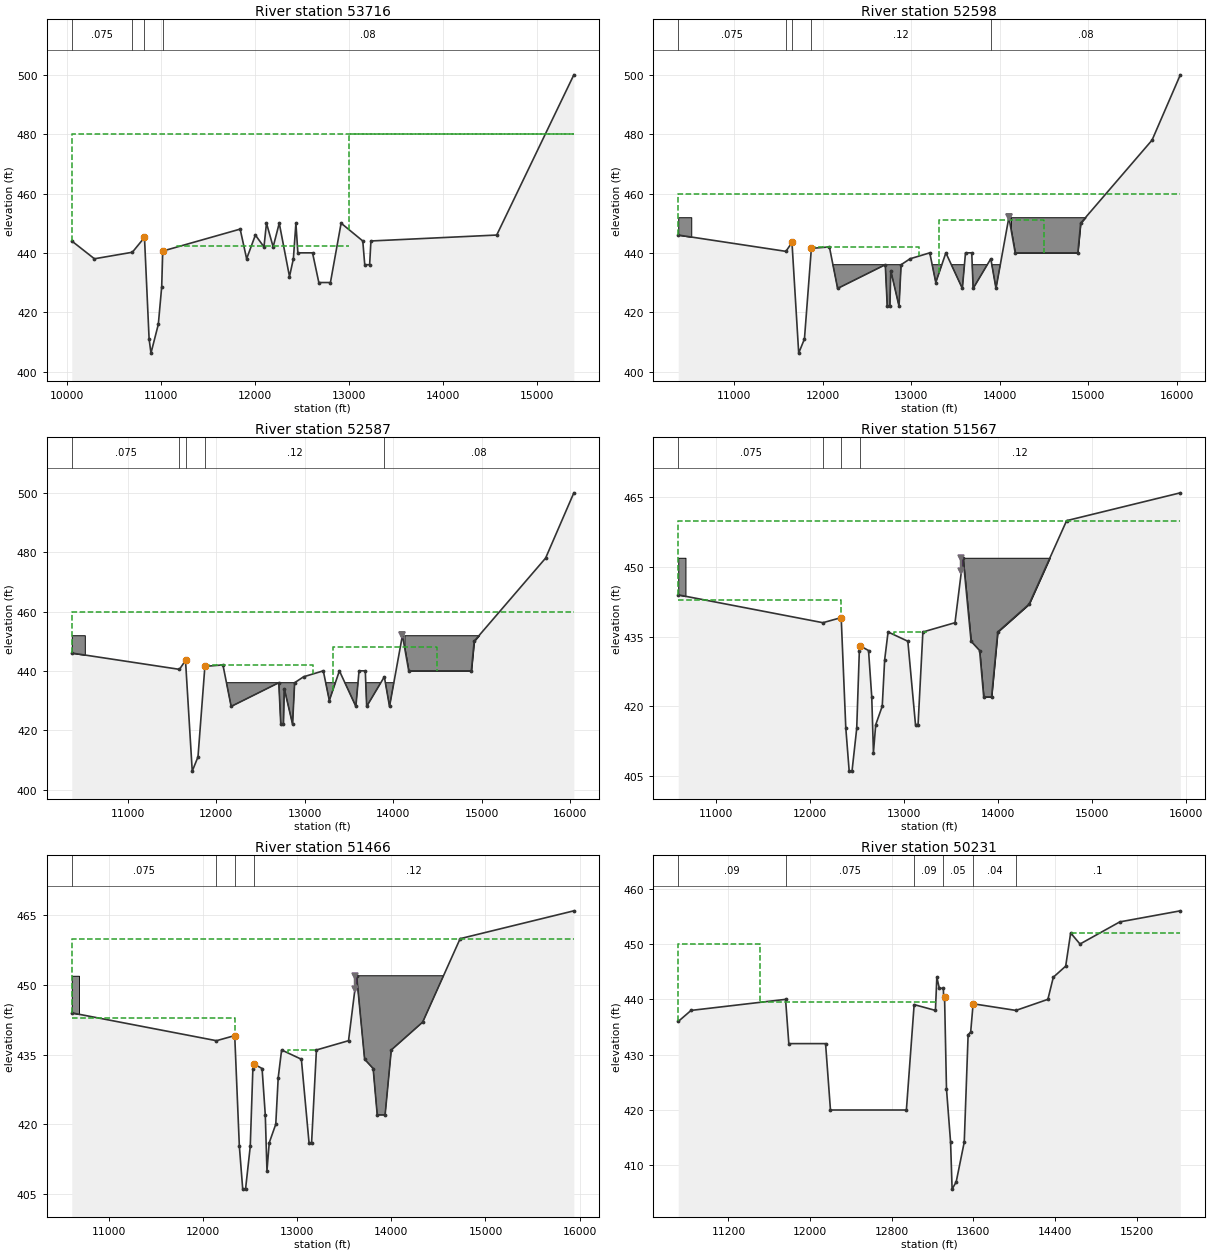
Type RM Length L Ch R = 1 ,53716   ,1040,1117,1149
BEGIN DESCRIPTION:
This cross section corresponds to cross section 53730 of the non-georeferenced CDC model which was the source of this model.
END DESCRIPTION:
XS GIS Cut Line= 6
    2424760.7759 6969487.5342079 2423913.9819316 6968469.5542877
 2423436.7230436 6967895.8526792 2423019.1077371 6967393.8697593
 2422183.8377541 6966389.9199956 2421348.5149497 6965385.9918853
#Sta/Elev= 30
10052.29     44410292.95     438   10696   440.2   10825   445.2   10874     411
   10894   406.2   10972   415.9   11008   428.6   11019   440.611841.73     448
11910.44     43812003.37     44612094.74     44212121.38     45012192.33     442
12257.07     45012365.97     43212407.27     43812434.12     45012454.87     440
12610.79     440 12677.7     43012801.06     43012914.55     45013144.78     444
13165.62     43613217.64     43613231.31     44414568.05     44615387.66     500
#Mann= 4 ,-1,0
10052.29    .075       0   10696     .12       0   10825     .05       0
   11019     .08       0
#XS Ineff= 4 ,-1
   1005210052.29     480   1300015387.66     48011166.52   13000  442.44
10052.29   10825  442.44
Permanent Ineff=
       F       F       F       F
Bank Sta=10825,11019
XS Rating Curve= 0 ,0
Exp/Cntr=0.3,0.1

Type RM Length L Ch R = 1 ,52598   ,12,12,12
BEGIN DESCRIPTION:
This cross section corresponds to cross section 52602 of the non-georeferenced CDC model which was the source of this model.
END DESCRIPTION:
XS GIS Cut Line= 6
  2425929.629482 6968917.5881283 2425890.5093671  6968880.364192
 2424968.2634376 6968002.8201525 2424877.6356435 6967943.2408798
 2424787.0078494 6967883.6616071 2422049.0670401 6964792.3936625
#Sta/Elev= 30
10367.73     44611584.67   440.5   11653   443.5   11729   406.2   11794     411
   11872   441.512075.93     44212168.78     428 12707.3     43612729.57     422
12759.63     42212769.36     43412862.76     42212886.07     43612987.36     438
   13210     44013278.05     43013391.88     44013578.09     42813613.85     440
13684.46     44013700.16     42813899.75     43813958.43     428 14104.3     452
14175.25     440 14882.8     44014915.02     45015722.02     47816041.12     500
#Mann= 5 ,-1,0
10367.73    .075       011584.67     .11       0   11653     .05       0
   11872     .12       013899.75     .08       0
Levee=0,,,-1,14104,452,,
#XS Ineff= 4 ,-1
   13315   14500     451   11872   13091     442   10839   11653     442
   1036710367.73     460
Permanent Ineff=
       F       F       F       F
#Block Obstruct= 3 ,-1
10367.73   10515     452   12000 14126.7     436 14126.7   15500     452
Bank Sta=11653,11872
XS Rating Curve= 0 ,0
Exp/Cntr=0.3,0.1

Type RM Length L Ch R = 1 ,52587   ,978,1020,1130
BEGIN DESCRIPTION:
This cross section corresponds to cross section 52592 of the non-georeferenced CDC model which was the source of this model.
END DESCRIPTION:
XS GIS Cut Line= 4
      2425936.47      6968909.22      2424965.97      6967986.03
       2424791.7      6967874.42      2422056.98      6964785.51
#Sta/Elev= 30
10367.73     44611584.67   440.5   11653   443.5   11729   406.2   11794     411
   11872   441.512075.93     44212168.78     428 12707.3     43612729.57     422
12759.63     42212769.36     43412862.76     42212886.07     43612987.36     438
   13210     44013278.05     43013391.88     44013578.09     42813613.85     440
13684.46     44013700.16     42813899.75     43813958.43     428 14104.3     452
14175.25     440 14882.8     44014915.02     45015722.02     47816041.12     500
#Mann= 5 ,-1,0
10367.73    .075       011584.67     .11       0   11653     .05       0
   11872     .12       013899.75     .08       0
Levee=0,,,-1,14104,452,,
#XS Ineff= 4 ,-1
   13315   14500     448   10839   11653     443   11872   13091     442
   1036710367.73     460
Permanent Ineff=
       F       F       F       F
#Block Obstruct= 3 ,-1
10367.73   10515     452   12000 14126.7     436 14126.7   15500     452
Bank Sta=11653,11872
XS Rating Curve= 0 ,0
Exp/Cntr=0.3,0.1

Type RM Length L Ch R = 1 ,51567   ,102,102,102
BEGIN DESCRIPTION:
This cross section corresponds to cross section 51581 of the non-georeferenced CDC model which was the source of this model.
END DESCRIPTION:
XS GIS Cut Line= 5
  2427060.784316  6968352.753633 2425700.8356255  6967341.938079
 2425635.4563173 6967263.5863462 2425570.0770091 6967185.2346134
 2423158.5438984 6964735.8762459
#Sta/Elev= 30
 10603.2     44412140.86     438   12335   439.1   12384   415.3   12420     406
   12450     406   12500   415.2   12528     432   12537     43312625.72     432
12659.76     42212677.68     41012701.89     41612771.27     42012797.01     430
12833.26     43613043.35     43413124.76     41613151.95     416 13203.2     436
13544.49     43813630.45     45213715.48     43413806.11     43213849.61     422
13933.19     42213998.85     43614332.45     442 14730.7     46015939.03     466
#Mann= 4 ,-1,0
 10603.2    .075       012140.86     .09       0   12335    .055       0
   12537     .12       0
Levee=0,,,-1,13612.76,452,,
#XS Ineff= 4 ,-1
 10603.2   12335     443   12900   13250     436   12580   12900     432
   10603 10603.2     460
Permanent Ineff=
       F       T       T       F
#Block Obstruct= 4 ,-1
13630.4514601.83     452
 10603.2   10680     452
Bank Sta=12335,12537
XS Rating Curve= 0 ,0
Exp/Cntr=0.3,0.1

Type RM Length L Ch R = 1 ,51466   ,1087,1234,1110
BEGIN DESCRIPTION:
This cross section corresponds to cross section 51481 of the non-georeferenced CDC model which was the source of this model.
END DESCRIPTION:
XS GIS Cut Line= 6
2427160.587162266968281.60773871       2427117.6      6968270.99
      2425773.88      6967275.77      2425650.06      6967118.32
 2424627.0911659 6966084.3782401      2423237.58      6964695.48
#Sta/Elev= 30
 10603.2     44412140.86     438   12335   439.1   12384   415.3   12420     406
   12450     406   12500   415.2   12528     432   12537     43312625.72     432
12659.76     42212677.68     41012701.89     41612771.27     42012797.01     430
12833.26     43613043.35     43413124.76     41613151.95     416 13203.2     436
13544.49     43813630.45     45213715.48     43413806.11     43213849.61     422
13933.19     42213998.85     43614332.45     442 14730.7     46015939.03     466
#Mann= 4 ,-1,0
 10603.2    .075       012140.86     .09       0   12335    .055       0
   12537     .12       0
Levee=0,,,-1,13612.76,452,,
#XS Ineff= 4 ,-1
 10603.2   12335     443   12900   13205     436   12600   12900     432
   10603 10603.2     460
Permanent Ineff=
       F       T       T       F
#Block Obstruct= 4 ,-1
13612.76   15000     452
 10603.2   10680     452
Bank Sta=12335,12537
XS Rating Curve= 0 ,0
Exp/Cntr=0.3,0.1

Type RM Length L Ch R = 1 ,50231   ,11,11,11
BEGIN DESCRIPTION:
This cross section corresponds to cross section 50235 of the non-georeferenced CDC model which was the source of this model.
END DESCRIPTION:
XS GIS Cut Line= 6
 2428372.9316959    6967867.2287 2426391.5371728 6966204.7813902
 2426269.6696579 6966138.4456566 2426147.8021431 6966072.1099229
  2424663.081165 6964714.0524508   2424646.90042 6964699.2521065
#Sta/Elev= 30
 10708.3     43610833.94     438   11760     440   11792     432   12152     432
   12200     420   12944     420   13020  439.0513228.79     43813242.36     444
13266.76     44213306.29     44213309.57     440   13318   440.5   13337   423.8
   13377   414.2   13392   405.7   13432     407   13511   414.2   13549   433.6
   13574   434.1   13598   439.214017.33     43814330.51     44014383.82     444
14504.97     44614553.74     45214645.33     45015035.22     45415628.24     456
#Mann= 6 ,-1,0
 10708.3     .09       0   11760    .075       0   13020     .09       0
13306.29     .05       0   13598     .04       014017.33      .1       0
#XS Ineff= 3 ,-1
 14553.715628.24     452 10708.3   11508     450   11508   13242   439.5
Permanent Ineff=
       F       T       F
Bank Sta=13318,13598
XS Rating Curve= 0 ,0
Exp/Cntr=0.3,0.1

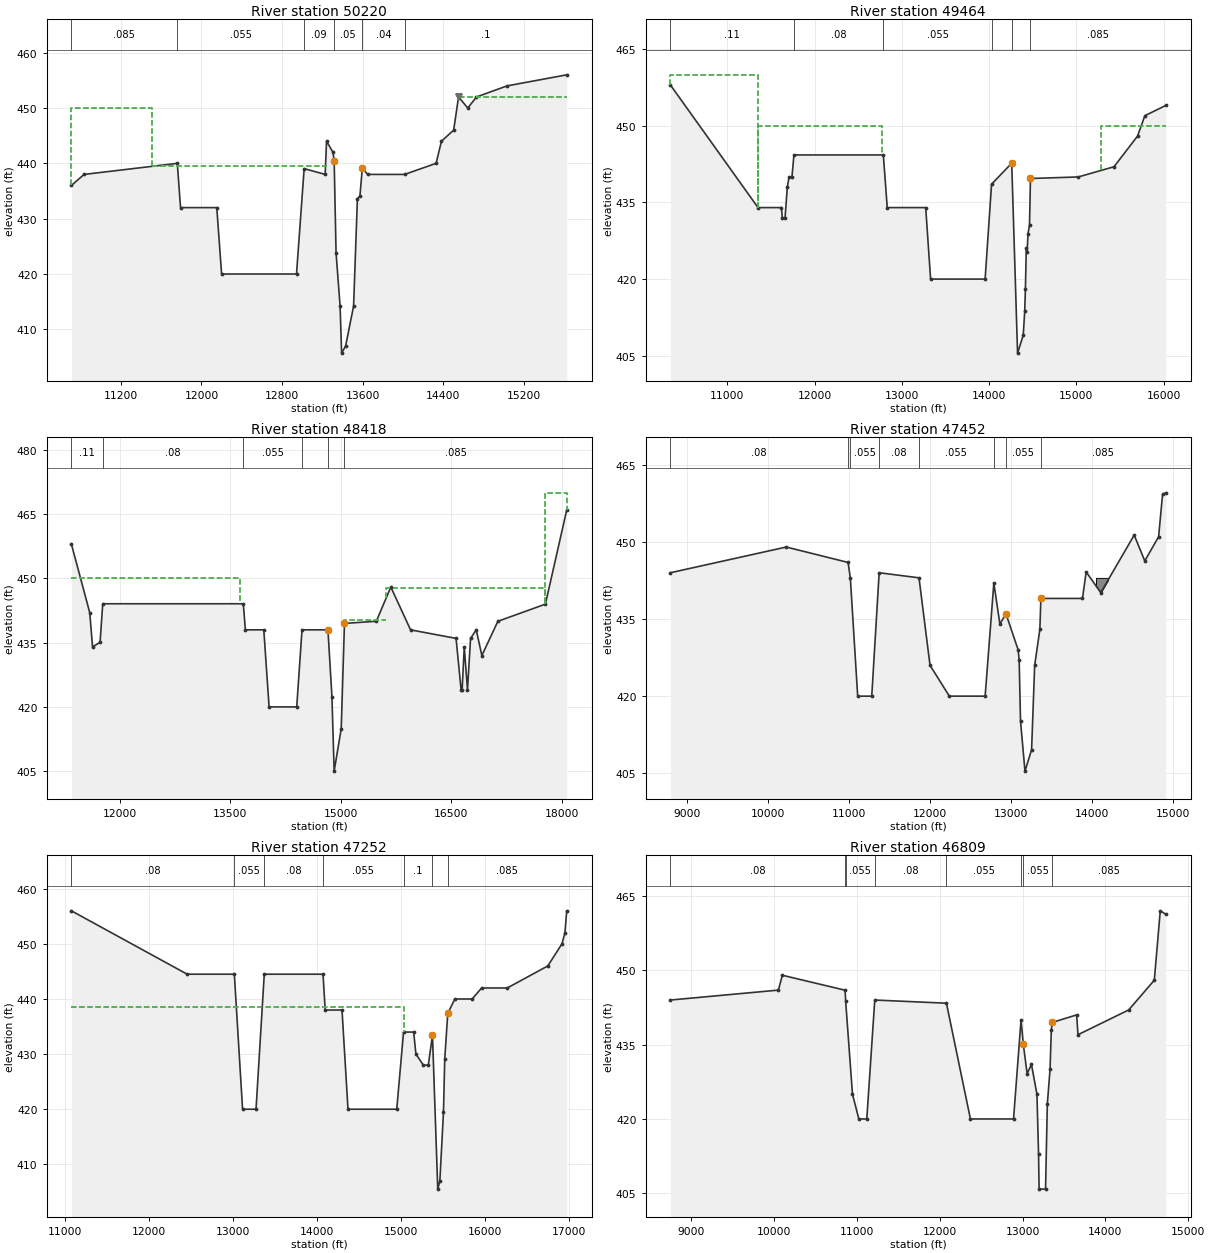
Type RM Length L Ch R = 1 ,50220   ,870,756,667
BEGIN DESCRIPTION:
This cross section corresponds to cross section 50225 of the non-georeferenced CDC model which was the source of this model.
END DESCRIPTION:
XS GIS Cut Line= 6
      2428377.83      6967857.02  2427957.614398 6967505.3760632
      2426396.69      6966194.86      2426149.91      6966061.54
      2424654.12      6964692.982424634.402630236964676.04083453
#Sta/Elev= 30
 10708.3     43610833.94     438   11760     440   11792     432   12152     432
   12200     420   12944     420   13020  439.0513228.79     43813242.36     444
13306.29     442   13318   440.5   13337   423.8   13377   414.2   13392   405.7
   13432     407   13511   414.2   13549   433.6   13574   434.1   13598   439.2
13649.61     43814017.33     43814330.51     44014383.82     44414504.97     446
14553.74     45214645.33     45014731.85     45215035.22     45415628.24     456
#Mann= 6 ,-1,0
 10708.3    .085       0   11760    .055       0   13020     .09       0
   13318     .05       0   13598     .04       014017.33      .1       0
Levee=0,,,-1,14553.7,452,,
#XS Ineff= 3 ,-1
 10708.3   11508     450   11508   13242   439.6 14553.715628.24     452
Permanent Ineff=
       T       F       F
Bank Sta=13318,13598
XS Rating Curve= 0 ,0
Exp/Cntr=0.3,0.1

Type RM Length L Ch R = 1 ,49464   ,1046,1046,1046
BEGIN DESCRIPTION:
This cross section corresponds to cross section 49477 of the non-georeferenced CDC model which was the source of this model.
END DESCRIPTION:
XS GIS Cut Line= 3
      2429656.28      6967842.24  2428622.914703 6967801.7684232
2425665.333996236964221.27412843
#Sta/Elev= 30
 10346.7     458 11350.7     43411618.69     43411629.47     43211660.62     432
11686.39     43811706.55     44011739.65     440 11762.5  444.31 12787.2  444.31
   12832     434   13273     434   13329     420   13954     420   14028  438.58
   14259   442.7   14326   405.5   14391     409   14408   413.7   14416   418.1
   14426     426   14436   425.4   14446   428.9   14463   430.6   14474   439.7
15021.34     44015431.75     44215701.23     44815785.65     45216024.91     454
#Mann= 6 ,-1,0
 10346.7     .11       0 11762.5     .08       0 12787.2    .055       0
   14028     .09       0   14259     .05       0   14474    .085       0
#XS Ineff= 4 ,-1
 10346.7 11350.7     460   1528716024.91     450 11350.7   12774     450
   12774   14080   438.1
Permanent Ineff=
       F       F       T       F
Bank Sta=14259,14474
XS Rating Curve= 0 ,0
Exp/Cntr=0.3,0.1

Type RM Length L Ch R = 1 ,48418   ,811,966,996
BEGIN DESCRIPTION:
This cross section corresponds to cross section 48431 of the non-georeferenced CDC model which was the source of this model.
END DESCRIPTION:
XS GIS Cut Line= 6
  2429626.156508 6967836.7802991 2427602.3594439 6965002.9963729
 2427555.6944689 6964901.0646995 2427509.0294938  6964799.133026
 2425747.0381223 6962717.10546012425559.794940386962495.85269316
#Sta/Elev= 30
11345.06     45811593.79     44211631.66     43411734.23  435.11   11770  444.09
   13678  444.09   13706     438   13956     438   14028     420   14403     420
   14475     43814826.82     438   14881   422.4   14911     405   15007   414.9
   15051   439.515483.35     44015680.21     44815948.16     43816565.71     436
 16634.2     424 16648.2     42416676.96     43416720.76     42416762.65     436
 16839.9     43816915.85     43217133.41     44017778.15     444   18068     466
#Mann= 6 ,-1,0
11345.06     .11       0   11770     .08       0   13678    .055       0
   14475      .1       014826.82    .055       0   15051    .085       0
#XS Ineff= 5 ,-1
17778.15   18068     47011345.06   13632     45015615.9717778.15  447.75
   1505115615.97   440.2   13632   14475   437.5
Permanent Ineff=
       F       T       F       F       F
Bank Sta=14826.82,15051
XS Rating Curve= 0 ,0
Exp/Cntr=0.5,0.3

Type RM Length L Ch R = 1 ,47452   ,109,200,192
BEGIN DESCRIPTION:
As-Built Survey by Halff Associates September 2016
Beltline West LOMR Project Area
END DESCRIPTION:
XS GIS Cut Line= 4
  2429604.9793666967559.126844972429332.276217776965892.98895183
2428058.470925126964128.892764642427057.834521196962859.12152854
#Sta/Elev= 30
 8799.89     44410229.45     44910992.41     44611020.34  442.9111110.78     420
11284.32     42011375.78     44411867.53  443.0112003.44     42612241.94     420
 12683.7     42012791.24     44212865.66  434.0412940.99     43613091.23     429
 13103.7     42713120.24  415.1713175.45  405.4213256.96  409.5713295.14     426
13359.23     43313371.71     43913885.04     43913930.34  444.1614110.76  440.13
14523.25  451.3214653.92   446.314824.75     45114873.53  459.2414912.89  459.54
#Mann= 8 ,-1,0
 8799.89     .08       010992.41    .055       011020.34    .055       0
11375.78     .08       011867.53    .055       012791.24      .1       0
12940.99    .055       013371.71    .085       0
#Block Obstruct= 1 ,-1
14051.72   14200     443
Bank Sta=12940.99,13371.71
XS Rating Curve= 0 ,0
Exp/Cntr=0.3,0.1

Type RM Length L Ch R = 1 ,47252   ,306,443,564
BEGIN DESCRIPTION:
This cross section corresponds to cross section 47265 of the non-georeferenced CDC model which was the source of this model.
END DESCRIPTION:
XS GIS Cut Line= 6
2430010.973736986967965.49071761  2429495.153798  6966689.441682
 2428231.9115015 6964058.5956805 2428178.6982606 6963984.7601018
 2428125.4850197  6963910.924523  2427448.424783 6962667.8975583
#Sta/Elev= 30
   11081     456   12458   444.5   13019   444.5   13117     420   13277     420
   13375   444.5   14074   444.5   14100     438   14300     438   14371     420
   14951     420   15032     43415152.31     43415178.94     43015267.66     428
15326.42     428   15376   433.4   15439   405.5   15464     407   15507   419.5
   15522   429.1   15558   437.415642.44     44015847.86     44015960.53     442
16265.83     44216747.97     44616916.32     450 16951.7     45216973.26     456
#Mann= 7 ,-1,0
   11081     .08       0   13019    .055       0   13375     .08       0
   14074    .055       0   15032      .1       0   15376    .055       0
   15558    .085       0
#XS Ineff= 2 , 0
       0   15032   438.5   15558       0   437.4
Permanent Ineff=
       F       F
Bank Sta=15376,15558
XS Rating Curve= 0 ,0
Exp/Cntr=0.5,0.3

Type RM Length L Ch R = 1 ,46809   ,435,493,552
BEGIN DESCRIPTION:
As-Built Survey by Halff Associates September 2016
Beltline West LOMR Project Area
END DESCRIPTION:
XS GIS Cut Line= 4
  2429659.8590786967540.124145142429369.285494826965654.66702025
2428604.602845746963864.688805852428220.993689856962464.52207144
#Sta/Elev= 30
 8750.55     444   10053     446 10101.2     44910858.46  445.9810865.46  443.73
10947.55     42511024.16     420 11120.4     42011216.71     44412081.62  443.36
 12371.1     42012891.58     42012982.01     44013009.54  435.0413055.35  429.16
13107.81     43113174.12     42513193.46     41313200.17  405.84 13277.9  405.84
13299.35     42313332.24     43013347.77     43813358.78  439.4813653.46     441
13669.34     43714281.48     44214590.59     44814662.58     46214728.78  461.31
#Mann= 8 ,-1,0
 8750.55     .08       010858.46    .055       010865.46    .055       0
11216.71     .08       012081.62    .055       012982.01      .1       0
13009.54    .055       013358.78    .085       0
Bank Sta=13009.54,13358.78
XS Rating Curve= 0 ,0
Exp/Cntr=0.3,0.1

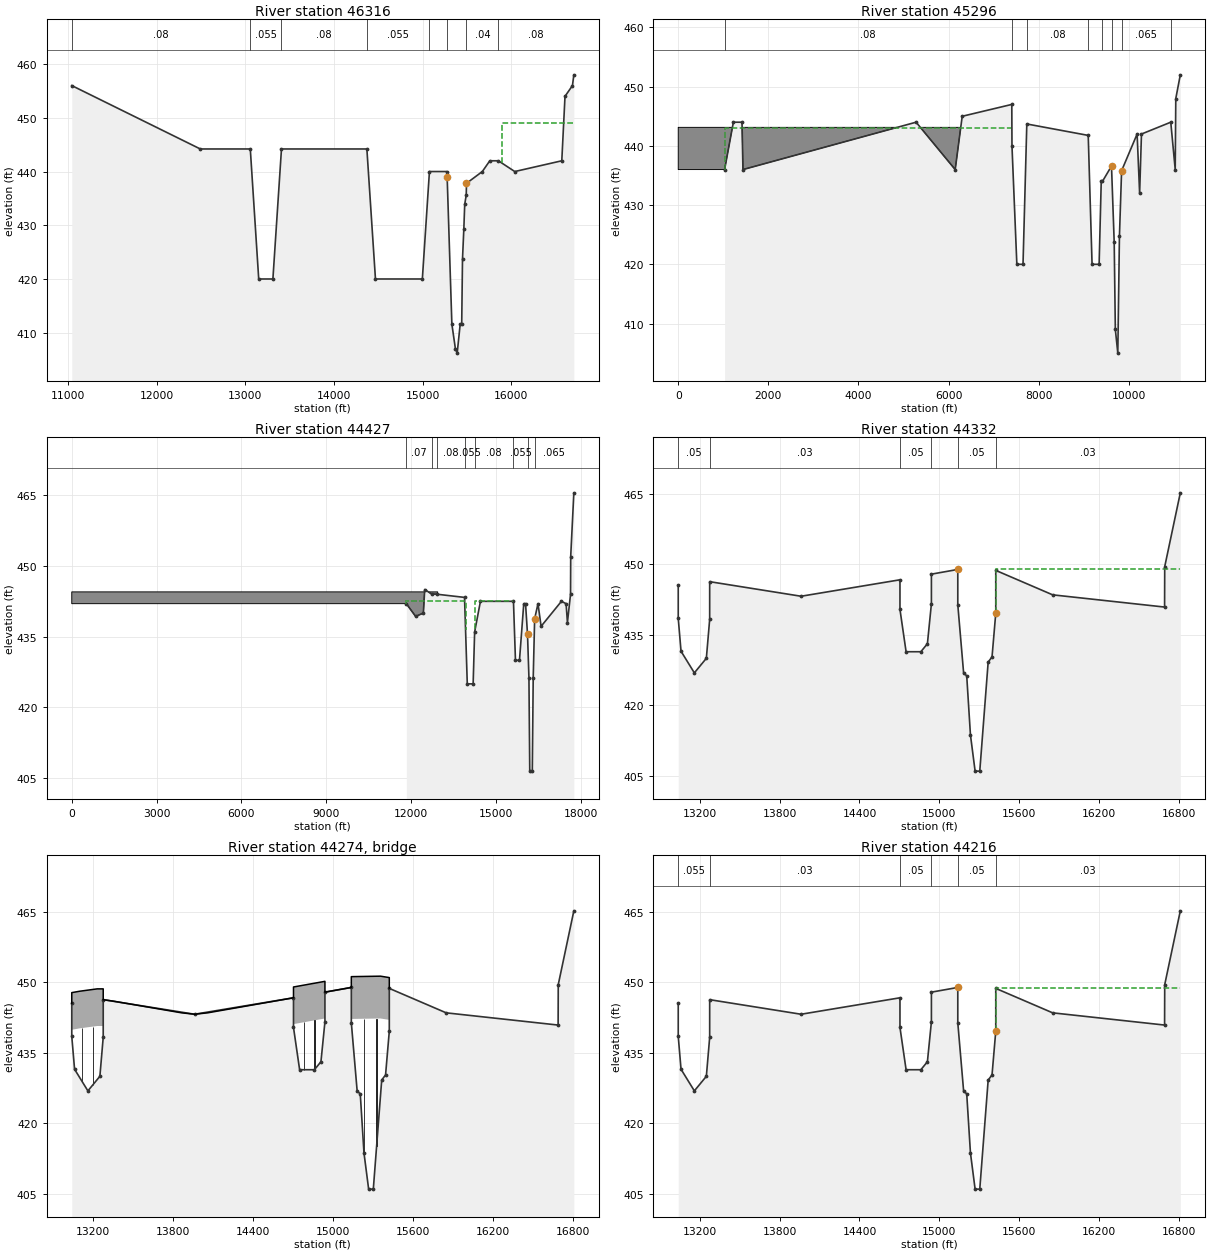
Type RM Length L Ch R = 1 ,46316   ,979,1020,1058
BEGIN DESCRIPTION:
This cross section corresponds to cross section 46329 of the non-georeferenced CDC model which was the source of this model.
PROPOSED EXCAVATION SWALE MODIFIED FROM CLOMR SUBMITTED TO CITY OF GRAND PRAIRIE ON JUNE 27, 2008, "SOUTHERN EXCAVATION SWALE WIDENED BY 16' TO MITIGATE A MINISCULE RISE CREATED IN THE CDC 100 YEAR WATER SURFACE ELEVATION
END DESCRIPTION:
XS GIS Cut Line= 6
2430017.85243406 6967980.8013151  2429523.113936  6966617.814221
 2429361.1327827 6965585.0528389 2429192.3453906 6964508.9759228
 2429023.5458594  6963432.899991 2428870.0809433  6962454.649979
#Sta/Elev= 30
   11042     456   12492   444.2   13056   444.2   13151     420   13311     420
 13407.8   444.2 14371.2   444.2   14468     420   14997     420   15077     440
15271.52     440   15277   438.9   15330   411.6   15370     407   15390   406.2
   15424   411.6   15441   411.6   15450   423.7   15465   429.3   15475   433.9
   15492   435.6   15495   437.815673.63     440   15758     44215854.83     442
16039.63     44016570.12     44216606.41     45416690.41     45616706.07     458
#Mann= 8 ,-1,0
   11042     .08       0   13056    .055       0 13407.8     .08       0
 14371.2    .055       0   15077     .09       0   15277    .055       0
   15495     .04       015854.83     .08       0
#XS Ineff= 2 , 0
       0   15077     437   15895       0     449
Permanent Ineff=
       F       T
Bank Sta=15277,15495
XS Rating Curve= 0 ,0
Exp/Cntr=0.5,0.3

Type RM Length L Ch R = 1 ,45296   ,800,869,900
BEGIN DESCRIPTION:
As-Built Survey by Halff Associates September 2016
Beltline West LOMR Project Area
Cross Section Truncated due to Ineffective Flow Areas.
END DESCRIPTION:
XS GIS Cut Line= 3
  2430418.0712976967479.592201212430395.776155236966863.75086606
     2429960.804      6962374.89
#Sta/Elev= 30
 1029.21     436 1224.07     444 1415.65     444 1436.45     436 5280.04     444
 6148.16     436    6304     445  7404.7     447 7408.54     440 7516.76     420
 7653.67     420  7737.9   443.7 9101.13  441.77 9186.46     420  9343.2     420
 9390.03     434    9417     434    9618   436.6    9678   423.7    9703     409
    9758     405    9794   424.7    9842   435.810186.47     44210242.32     432
10283.19     44210933.53     444 11032.4     43611045.12     44811145.43     452
#Mann= 8 ,-1,0
 1029.21     .08       0  7404.7    .055       0  7737.9     .08       0
 9101.13    .055       0    9417     .09       0    9618     .05       0
    9842    .065       010933.53     .04       0
#XS Ineff= 3 ,-1
       0  7388.6     443    984211145.43   435.8  7388.6    9618     435
Permanent Ineff=
       F       F       F
#Block Obstruct= 2 , 0
       0    6398  443.1310186.47       0     445
Bank Sta=9618,9842
XS Rating Curve= 0 ,0
Exp/Cntr=0.3,0.1

Type RM Length L Ch R = 1 ,44427   ,95,95,95
BEGIN DESCRIPTION:
As-Built Survey by Halff Associates September 2016
Cross Section Truncated due to Ineffective Flow Areas
END DESCRIPTION:
XS GIS Cut Line= 5
  2431037.1800266967524.365856352430996.476759476966303.74660712
   2430968.003296966032.29090739     2430967.962      6962988.18
2430986.149878916962321.31748248
#Sta/Elev= 30
   11830     442   12159   439.3   12433     440 12480.4     44512726.45  444.04
12918.27     444 13888.3  443.3313985.76     425   14193     42514245.93     436
14450.82   442.5   15619   442.515689.48     43015831.48     43015982.82     442
   16046     442   16116   435.5   16166   426.3   16195   406.5   16285   406.5
   16317   426.2   16368   438.8   16486     442   16596   437.2   17315   442.5
   17480     442   17527     438   17637     444   17643     452   17754   465.5
#Mann= 8 ,-1,0
   11830     .07       012726.45     .09       012918.27     .08       0
 13888.3    .055       014245.93     .08       0   15619    .055       0
   16116     .05       0   16368    .065       0
#XS Ineff= 4 ,-1
   11830   13925   442.5   14263   15619   442.5   16368   17754   438.8
   15619   16116     434
Permanent Ineff=
       F       F       F       F
#Block Obstruct= 2 , 0
       0   12938   444.5   16491       0   444.5
Bank Sta=16116,16368
XS Rating Curve= 0 ,0
Exp/Cntr=0.5,0.3

Type RM Length L Ch R = 1 ,44332   ,118,118,118
BEGIN DESCRIPTION:
This cross section corresponds to cross section 44330 of the non-georeferenced CDC model which was the source of this model.
END DESCRIPTION:
XS GIS Cut Line= 6
  2431044.622273  6966048.579772 2431047.2501453 6965365.8757838
 2431047.6294097 6965267.4058364 2431049.1451547  6964873.527031
  2431049.524419 6964775.0570836 2431059.1234812 6962280.6076762
#Sta/Elev= 30
   13040   445.5   13040   438.5   13061   431.5   13161   426.9   13251     430
   13276   438.3   13276   446.3   13962   443.2   14704   446.7   14704   440.4
   14750   431.4   14861   431.4   14910   433.1   14940   441.6   14940   447.9
   15138   448.9   15138   441.4   15182   426.8   15205   426.3   15233   413.7
   15268     406   15303     406   15366   429.2   15395   430.3   15423   439.6
   15423   448.7   15850   443.5   16690   440.9   16691   449.5   16808   465.2
#Mann= 6 ,-1,0
   13040     .05       0   13276     .03       0   14704     .05       0
   14940     .03       0   15138     .05       0   15423     .03       0
#XS Ineff= 2 , 0
       0   15138     436   15423       0     449
Permanent Ineff=
       F       T
Bank Sta=15138,15423
XS Rating Curve= 0 ,0
Exp/Cntr=0.5,0.3

Type RM Length L Ch R = 3 ,44274   ,,,
BEGIN DESCRIPTION:
Belt Line Road
END DESCRIPTION:
Node Name=Belt Line Road
Bridge Culvert--1,0,-1,-1, 0
Deck Dist Width WeirC Skew NumUp NumDn MinLoCord MaxHiCord MaxSubmerge Is_Ogee
0.5,117,2.6,0, 19, 19, , , 0.95, 0, ,,,
   13040   13040   13100   13231   13276   13276   13350   13864   13962   14060
   14704   14704   14940   14940   15138   15138   15357   15423   15423
   445.5   447.8   448.1   448.6   448.6   446.3     446   443.5   443.2   443.5
   446.7     449   450.2   447.9   448.9   451.2   451.3     451   448.7
   445.5   439.9   440.2   440.7   440.7   446.3     446   443.5   443.2   443.5
   446.7   441.1   442.3   447.9   448.9   442.2   442.3     442   448.7
   13040   13040   13100   13231   13276   13276   13350   13864   13962   14060
   14704   14704   14940   14940   15138   15138   15357   15423   15423
   445.5   447.8   448.1   448.6   448.6   446.3     446   443.5   443.2   443.5
   446.7     449   450.2   447.9   448.9   451.2   451.3     451   448.7
   445.5   439.9   440.2   440.7   440.7   446.3     446   443.5   443.2   443.5
   446.7   441.1   442.3   447.9   448.9   442.2   442.3     442   448.7
Pier Skew, UpSta & Num, DnSta & Num=  ,13119, 2 ,13119, 2 , 0 , 0 , 0 ,,
     2.5     2.5
     400     444
     2.5     2.5
     400     444
Pier Skew, UpSta & Num, DnSta & Num=  ,13198, 2 ,13198, 2 , 0 , 0 , 0 ,,
     2.5     2.5
     400     444
     2.5     2.5
     400     444
Pier Skew, UpSta & Num, DnSta & Num=  ,14783, 2 ,14783, 2 , 0 , 0 , 0 ,,
     2.5     2.5
     400     444
     2.5     2.5
     400     444
Pier Skew, UpSta & Num, DnSta & Num=  ,14862, 2 ,14862, 2 , 0 , 0 , 0 ,,
     2.5     2.5
     400     444
     2.5     2.5
     400     444
Pier Skew, UpSta & Num, DnSta & Num=  ,15233, 2 ,15233, 2 , 0 , 0 , 0 ,,
       3       3
     400     444
       3       3
     400     444
Pier Skew, UpSta & Num, DnSta & Num=  ,15328, 2 ,15328, 2 , 0 , 0 , 0 ,,
       3       3
     400     444
       3       3
     400     444
BR Coef= 1 , 0 , 0 ,1.05, 0 ,,,0.8,-1,0.5,1,
WSPro=,,,, 1 ,,,, 0 ,,,, 0 ,,,,-1 ,-1 ,-1 , 0 , 0 , 0 , 0 , 0
BC Design=,, 0 ,, 0 ,,,,,,
BC HTab HWMax=449
BC Use User HTab Curves=0
BC User HTab FreeFlow(D)= 0

Type RM Length L Ch R = 1 ,44216   ,75,75,75
BEGIN DESCRIPTION:
This cross section corresponds to cross section 44253 of the non-georeferenced CDC model which was the source of this model.
---------------------------
Belt Line Road downstream bounding cross-section.
CDC GP080808-1 Belt Line West Reclamation
Cross-section 44232 - 55761
Located in LOB.
-----------------------------------------
New modeling by Halff adopted for this reach of river.  Includes revised cross-sections from 34268 - 53730, new split flow reach, revised split analysis over Hardrock Road.
END DESCRIPTION:
XS GIS Cut Line= 6
  2431160.980098 6966033.3046537 2431166.5697886 6964580.4396907
 2431169.5858587 6963796.2785293 2431169.9631545 6963698.2580561
 2431172.9638047 6962917.9804172 2431175.4516606 6962265.3324442
#Sta/Elev= 30
   13040   445.5   13040   438.5   13061   431.5   13161   426.9   13251     430
   13276   438.3   13276   446.3   13962   443.2   14704   446.7   14704   440.4
   14750   431.4   14861   431.4   14910   433.1   14940   441.6   14940   447.9
   15138   448.9   15138   441.4   15182   426.8   15205   426.3   15233   413.7
   15268     406   15303     406   15366   429.2   15395   430.3   15423   439.6
   15423   448.7   15850   443.5   16690   440.9   16691   449.5   16808   465.2
#Mann= 6 ,-1,0
   13040    .055       0   13276     .03       0   14704     .05       0
   14940     .03       0   15138     .05       0   15423     .03       0
#XS Ineff= 2 , 0
       0   15138     436   15423       0   448.7
Permanent Ineff=
       F       T
Bank Sta=15138,15423
XS Rating Curve= 0 ,0
Exp/Cntr=0.5,0.3