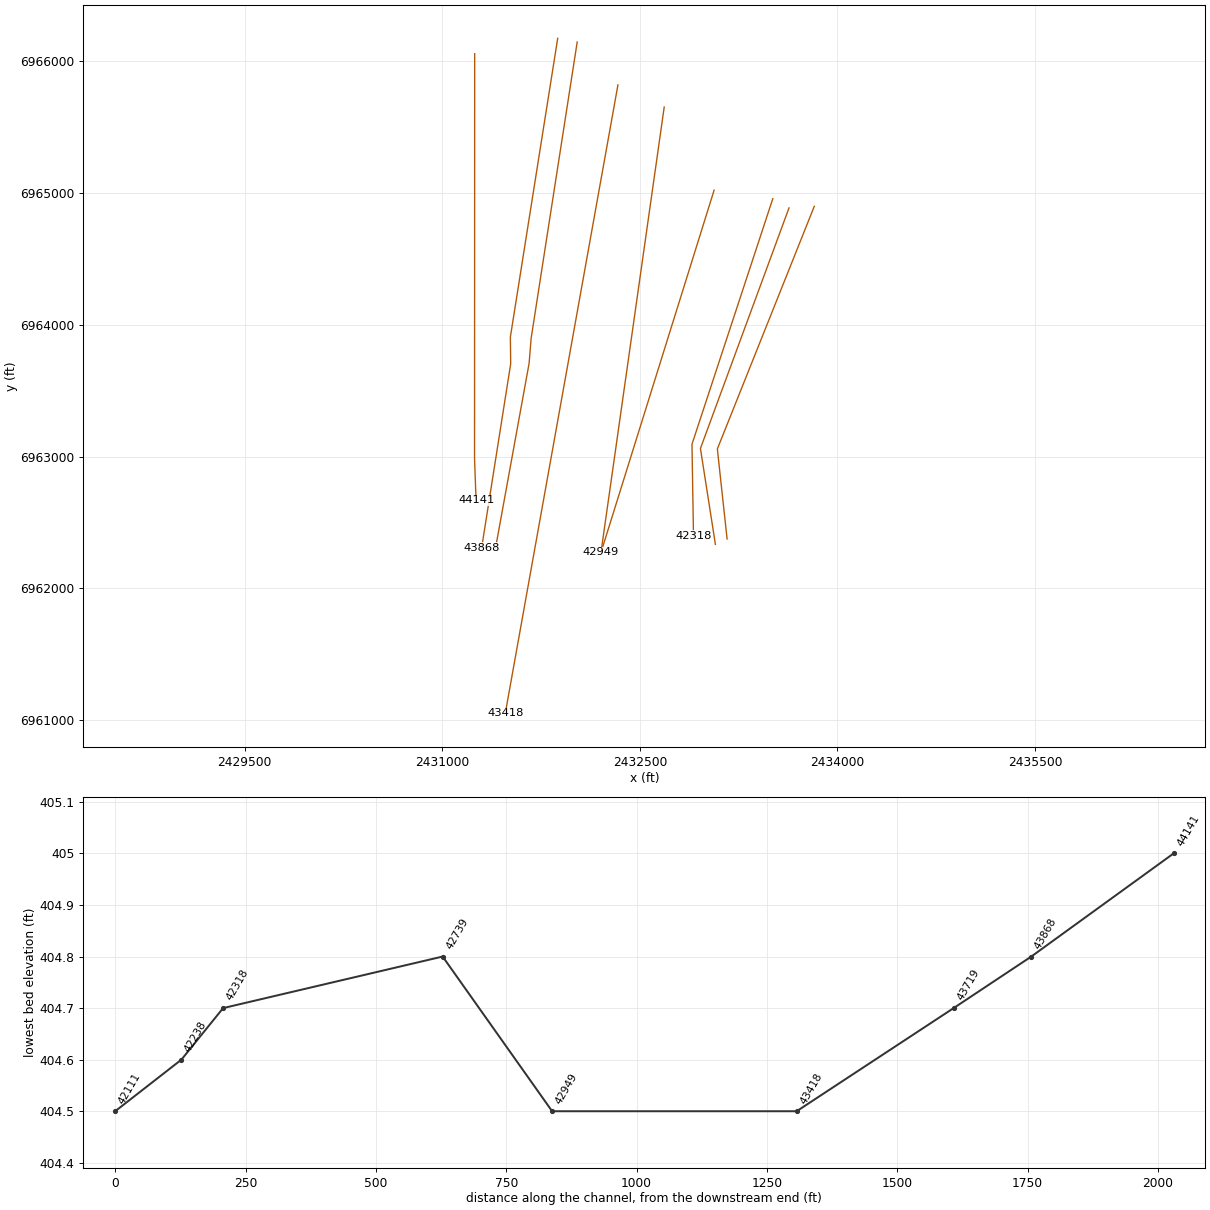
HEC-RAS study CDC_Consolidated_Model.prj: Upper Trinity CDC Consolidated Model

--- CDC_Consolidated_Model.g01 (geometry) --- (continued)

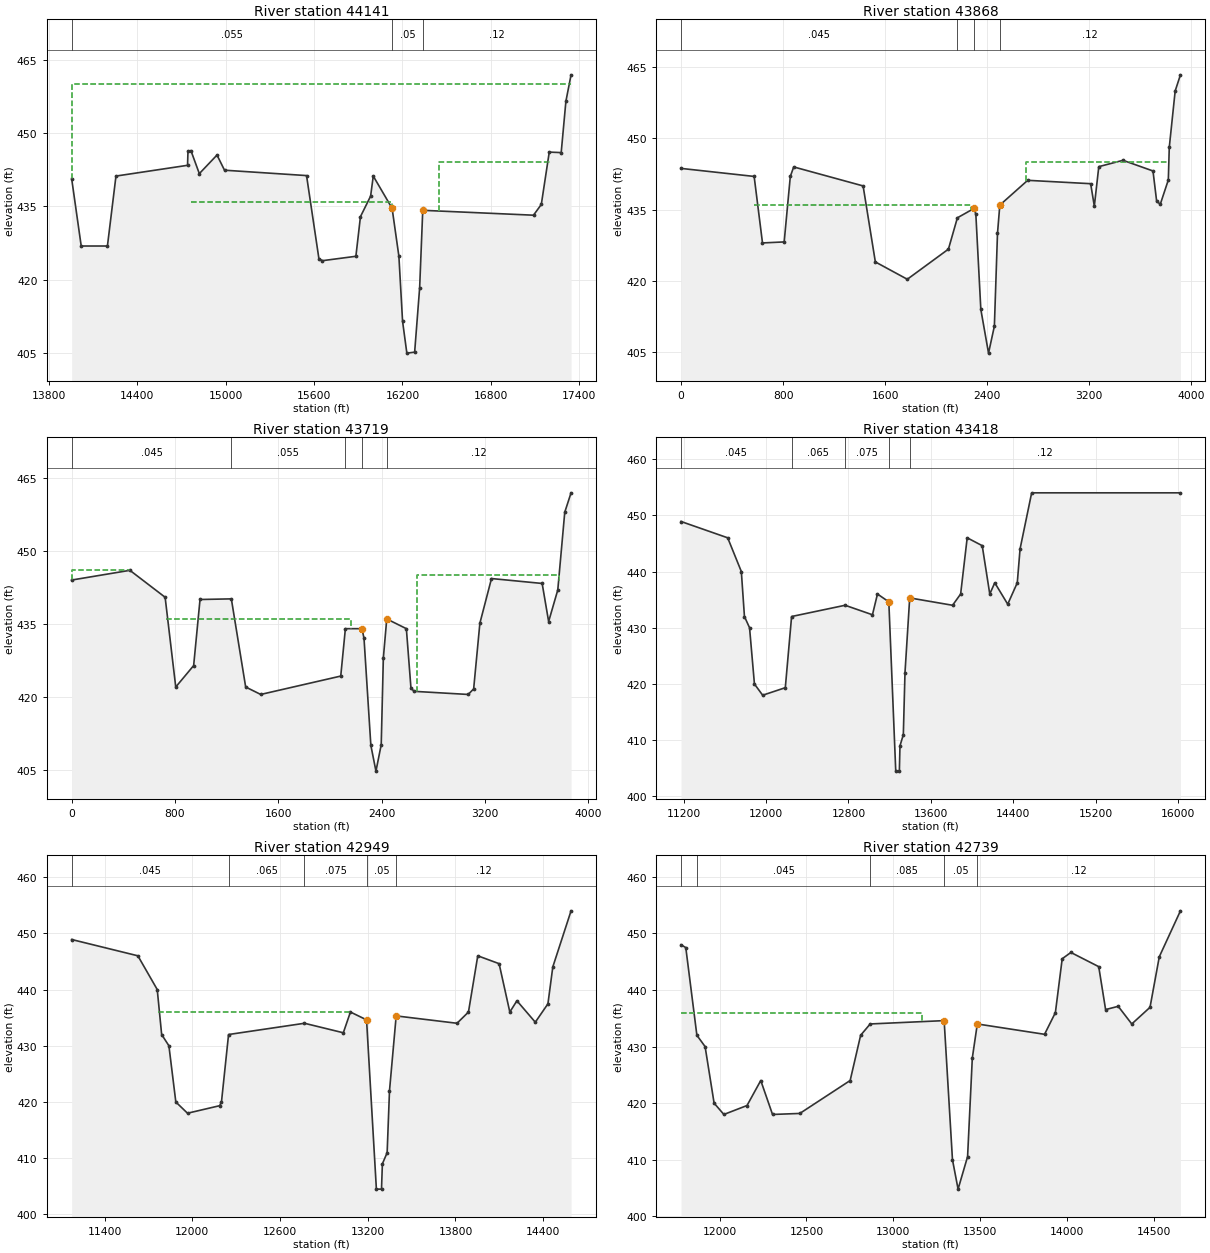
Type RM Length L Ch R = 1 ,44141   ,359,273,278
BEGIN DESCRIPTION:
This cross section corresponds to cross section 44153 of the non-georeferenced CDC model which was the source of this model.
Cross-section Truncated due to Ineffective Flow Areas
END DESCRIPTION:
XS GIS Cut Line= 6
  2431245.496262 6966057.5841621 2431245.2589357 6965391.9751411
 2431244.8645795 6964288.7201297 2431244.5771785 6963486.3532962
 2431244.3970608 6962984.8739841 2431255.9629825 6962666.7945678
#Sta/Elev= 30
   13954   440.7   14019   426.9   14197   426.9   14255   441.2   14741   443.4
   14744   446.3   14764   446.4   14821   441.7   14941   445.5   14992   442.4
   15549   441.3   15633   424.3   15657   423.9   15884   424.8   15915   432.9
   15984   437.1   16002   441.2   16130   434.6   16176   424.8   16201   411.5
   16230     405   16283   405.2   16317   418.4   16338   434.2   17090   433.2
   17143   435.4   17197   446.1   17278     446   17310   456.5   17345   461.9
#Mann= 3 ,0,0
   13954    .055       0   16130     .05       0   16338     .12       0
#XS Ineff= 3 ,-1
   16450   17209     444   14764   16130     436 13953.5   13954     460
Permanent Ineff=
       T       F       F
Bank Sta=16130,16338
XS Rating Curve= 0 ,0
Exp/Cntr=0.3,0.1

Type RM Length L Ch R = 1 ,43868   ,136,149,154
BEGIN DESCRIPTION:
This cross section corresponds to cross section 43880 of the non-georeferenced CDC model which was the source of this model.
OVERFLOW SWALE MODELED FROM STATIONS 580-856, FLOWLINE INTERPOLATED FROM THE EFFECTIVE PROFILE,  LEFT OVERBANK TAKEN FROM 1999 CGP TOPOGRAPHY, RIGHT OVERBANK TAKEN FROM COMBINATION OF 12/08 FIELD SURVEYS AND 1999 CGP TOPO
END DESCRIPTION:
XS GIS Cut Line= 6
  2431875.838436  6966174.324034 2431516.2954073 6963906.4269135
 2431517.6167176  6963805.331426 2431518.9380279 6963704.2359385
 2431311.8610553  6962392.4206782431298.20829234 6962305.9315693
#Sta/Elev= 30
       0  443.69  573.08     442  638.52     428  808.43  428.21  856.54     442
  883.18     444 1427.04     440 1522.94     424 1773.46  420.35 2095.65  426.69
 2165.99  433.29 2296.24  435.26 2310.67     434 2349.68     414    2410   404.8
 2455.82  410.48 2480.25     430 2498.45  435.96 2716.91  441.18  3210.4  440.47
 3239.14  435.75  3274.2  444.06 3463.87  445.39 3698.94  443.15 3727.83  436.73
 3756.48  436.18 3819.09  441.26 3826.52  448.11 3872.76  459.99 3914.08  463.39
#Mann= 4 ,-1,0
       0    .045       0 2165.99    .085       0 2296.24     .05       0
 2498.45     .12       0
#XS Ineff= 2 ,-1
    2707    3824     445     570    2273     436
Permanent Ineff=
       F       F
Bank Sta=2296.24,2498.45
XS Rating Curve= 0 ,0
Exp/Cntr=0.3,0.1

Type RM Length L Ch R = 1 ,43719   ,295,301,297
BEGIN DESCRIPTION:
This cross section corresponds to cross section 43731 of the non-georeferenced CDC model which was the source of this model.
OVERFLOW SWALE MODELED FROM STATIONS 740-994, FLOWLINE INTERPOLATED FROM THE EFFECTIVE PROFILE,  LEFT OVERBANK TAKEN FROM 1999 CGP TOPOGRAPHY, RIGHT OVERBANK TAKEN FROM COMBINATION OF 12/08 FIELD SURVEYS AND 1999 CGP TOPO
END DESCRIPTION:
XS GIS Cut Line= 5
      2432023.89      6966146.71 2431674.2286031 6963898.1235317
  2431666.452464 6963802.6154327  2431658.676325 6963707.1073337
  2431403.301283 6962302.6788034
#Sta/Elev= 30
       0     444  451.28     446  724.09  440.46  806.36     422  945.04  426.41
  994.42     440 1236.98  440.13 1347.98     422 1464.66  420.47 2084.31  424.25
 2120.18     434 2249.03     434 2264.52     432 2317.49     410    2357   404.7
 2397.76  410.13 2414.33     428 2440.68     436 2592.53     434 2628.08  421.79
 2652.29  421.11 3071.39  420.47 3113.68  421.61 3161.92  435.12 3251.93  444.31
 3644.28   443.3 3694.45  435.47 3765.38  441.97 3819.38  457.96 3868.15  461.94
#Mann= 5 ,-1,0
       0    .045       0 1236.98    .055       0 2120.18    .085       0
 2249.03     .05       0 2440.68     .12       0
#XS Ineff= 3 ,-1
       0  451.28     446    2675    3771     445     732    2167     436
Permanent Ineff=
       F       F       F
Bank Sta=2249.03,2440.68
XS Rating Curve= 0 ,0
Exp/Cntr=0.3,0.1

Type RM Length L Ch R = 1 ,43418   ,598,469,449
BEGIN DESCRIPTION:
This cross section corresponds to cross section 43369 of the non-georeferenced CDC model which was the source of this model.
FLOWLINE INTERPOLATED FROM THE EFFECTIVE PROFILE,  LEFT OVERBANK TAKEN FROM 1999 CGP TOPOGRAPHY, RIGHT OVERBANK TAKEN FROM COMBINATION OF 12/08 FIELD SURVEYS AND 1999 CGP TOPO
END DESCRIPTION:
XS GIS Cut Line= 4
      2432333.23      6965821.07      2431701.33      6962297.49
 2431521.0486329 6961291.85804072431477.723772866961050.18656578
#Sta/Elev= 30
   11175   448.911627.93     44611760.38     44011790.52     43211840.11     430
11887.49     42011967.34     41812187.15  419.3412248.12     43212767.37     434
13032.86  432.3113081.51     43613191.79  434.61   13259   404.5   13294   404.5
   13300     40913332.56  410.9813348.64     42213394.37  435.3113810.42     434
13888.69     43613952.35     44614098.21   444.6 14171.5     43614219.98     438
14345.71  434.1914438.47     43814465.51  444.0314578.05     45416021.98     454
#Mann= 5 ,-1,0
   11175    .045       012248.12    .065       012767.37    .075       0
13191.79     .05       013394.37     .12       0
#XS Ineff= 1 ,-1
13952.35   15757     446
Permanent Ineff=
       F
Bank Sta=13191.79,13394.37
XS Rating Curve= 0 ,0
Exp/Cntr=0.3,0.1

Type RM Length L Ch R = 1 ,42949   ,361,210,80
BEGIN DESCRIPTION:
This cross section corresponds to cross section 42961 of the non-georeferenced CDC model which was the source of this model.
FLOWLINE INTERPOLATED FROM THE EFFECTIVE PROFILE,  LEFT OVERBANK TAKEN FROM 1999 CGP TOPOGRAPHY, RIGHT OVERBANK TAKEN FROM COMBINATION OF 12/08 FIELD SURVEYS AND 1999 CGP TOPO
END DESCRIPTION:
XS GIS Cut Line= 6
  2432684.537395 6965652.8939046  2432579.281202 6964911.6617972
  2432509.852207 6964422.7520139 2432440.4209154 6963933.8425587
 2432329.3259932 6963151.5878896   2432204.33707   6962271.55192
#Sta/Elev= 30
   11175   448.911627.93     44611760.38     44011790.52     43211840.11     430
11887.49     42011967.34     41812187.15  419.3412199.64     42012248.12     432
12767.37     43413032.86  432.3113081.51     43613191.79  434.61   13259   404.5
   13294   404.5   13300     40913332.56  410.9813348.64     42213394.37  435.31
13810.42     43413888.69     43613952.35     44614098.21   444.6 14171.5     436
14219.98     43814345.71  434.1914432.07  437.4614465.51  444.0314590.27     454
#Mann= 5 ,-1,0
   11175    .045       012248.12    .065       012767.37    .075       0
13191.79     .05       013394.37     .12       0
#XS Ineff= 2 ,-1
13952.35   14502     442   11763   13081     436
Permanent Ineff=
       F       F
Bank Sta=13191.79,13394.37
XS Rating Curve= 0 ,0
Exp/Cntr=0.3,0.1

Type RM Length L Ch R = 1 ,42739   ,453,421,449
BEGIN DESCRIPTION:
This cross section corresponds to cross section 42751 of the non-georeferenced CDC model which was the source of this model.
FLOWLINE INTERPOLATED FROM THE EFFECTIVE CROSS SECTION AT STATIONS 13352-13417,  LEFT OVERBANK TAKEN FROM 1999 CGP TOPOGRAPHY, RIGHT OVERBANK TAKEN FROM COMBINATION OF 12/08 FIELD SURVEYS AND 1999 CGP TOPO
END DESCRIPTION:
XS GIS Cut Line= 6
  2433063.327041 6965021.7892554 2432846.3843423 6964327.1531237
 2432642.9375708 6963675.7607257 2432439.4825971 6963024.3699682
  2432323.218722 6962652.1469593 2432206.9518942 6962279.9246067
#Sta/Elev= 30
11778.45     44811805.86   447.511869.66     43211916.92     43011968.75     420
12024.87     41812157.98  419.5812237.08     42412304.79     41812461.61  418.18
12751.25     42412811.56     43212866.53     43413291.82  434.5913339.73     410
   13372   404.813426.67  410.5513453.89     42813482.62     43413869.39  432.17
13931.62     43613970.89  445.5314020.84  446.6414180.93  444.1314220.47  436.54
14293.02  437.1214371.02     43414475.93  436.9414529.31  445.8814650.94     454
#Mann= 5 ,-1,0
11778.45    .035       011869.66    .045       012866.53    .085       0
13291.82     .05       013482.62     .12       0
#XS Ineff= 2 ,-1
 14020.8   14567     44211778.45   13167     436
Permanent Ineff=
       F       F
Bank Sta=13291.82,13482.62
XS Rating Curve= 0 ,0
Exp/Cntr=0.3,0.1

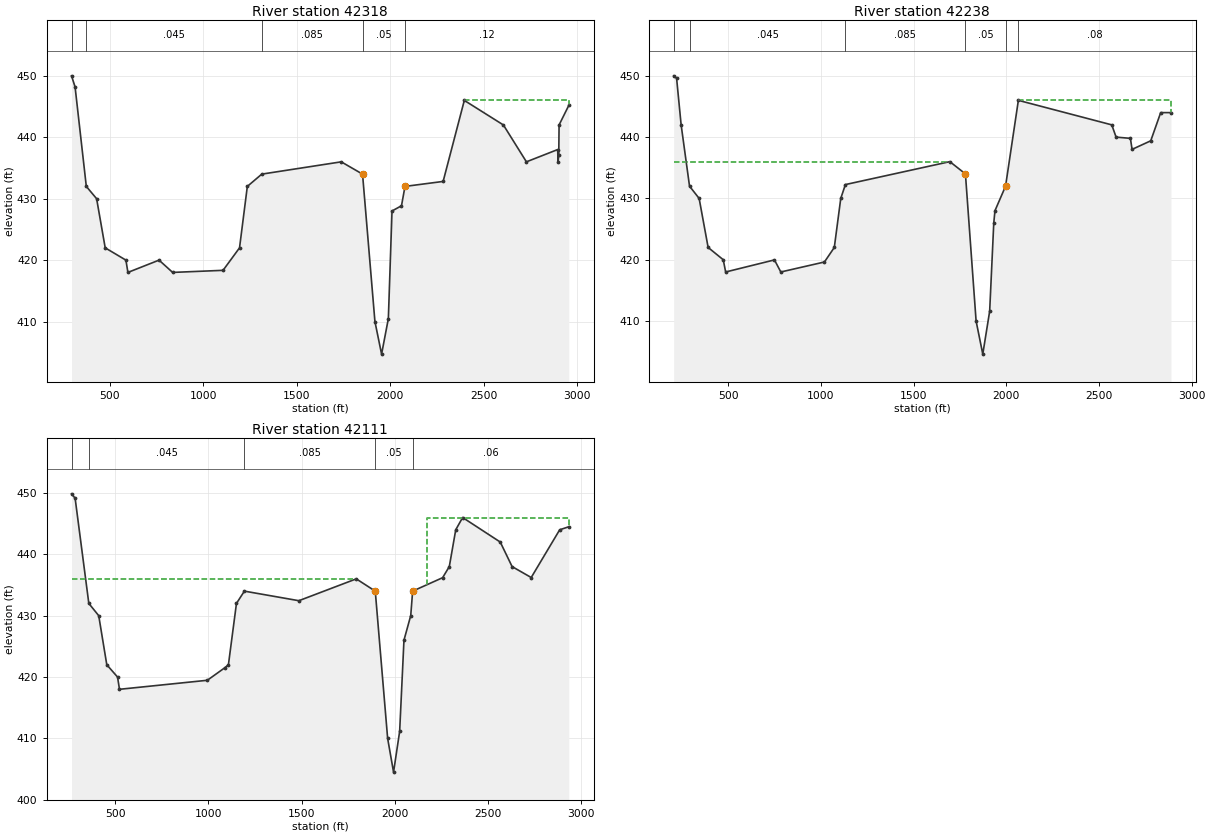
Type RM Length L Ch R = 1 ,42318   ,120,80,115
BEGIN DESCRIPTION:
This cross section corresponds to cross section 42373 of the non-georeferenced CDC model which was the source of this model.
FLOWLINE INTERPOLATED FROM EFFECTIVE PROFILE, LEFT OVERBANK TAKEN FROM 1999 CGP TOPOGRAPHY, RIGHT OVERBANK TAKEN FROM COMBINATION OF 12/08 FIELD SURVEYS AND 1999 CGP TOPO
---------------------------------------------------------------------
CDC GP091010-1 Palace Parkway
Cross-section 42373 - 44153
Project located in ROB.
--------------------------------------------------------
END DESCRIPTION:
XS GIS Cut Line= 3
2433508.944494936964957.25519405     2432895.277     6963093.157
2432906.886390686962396.61470836
#Sta/Elev= 30
  295.93     450  314.92  448.19  374.96     432  430.07     430  476.03     422
  586.76     420  597.41     418   763.9     420  836.69     418  1106.2  418.34
 1194.35     422 1236.06     432  1313.4     434 1738.34     436 1852.17     434
 1918.41     410    1954   404.7 1990.21  410.47  2009.8     428  2060.5  428.85
 2079.19     432 2283.13  432.81 2396.44     446 2605.46     442 2728.51     436
 2895.74     438 2897.89     436 2901.53  437.14 2903.18     442 2955.08  445.18
#Mann= 5 ,-1,0
  295.93    .035       0  374.96    .045       0  1313.4    .085       0
 1852.17     .05       0 2079.19     .12       0
#XS Ineff= 2 ,-1
  2396.4    2955     446     296 1738.34     436
Permanent Ineff=
       F       F
Bank Sta=1852.17,2079.19
XS Rating Curve= 0 ,0
Exp/Cntr=0.3,0.1

Type RM Length L Ch R = 1 ,42238   ,156,127,134
BEGIN DESCRIPTION:
This cross section corresponds to cross section 42303 of the non-georeferenced CDC model which was the source of this model.
FLOWLINE INTERPOLATED FROM EFFECTIVE PROFILE, LEFT OVERBANK TAKEN FROM 1999 CGP TOPOGRAPHY, RIGHT OVERBANK TAKEN FROM COMBINATION OF 12/08 FIELD SURVEYS AND 1999 CGP TOPO
END DESCRIPTION:
XS GIS Cut Line= 3
2433632.049699456964887.02022063     2432959.499     6963061.046
2433073.200408496962332.74270938
#Sta/Elev= 30
   205.2     450  220.94  449.61   245.4     442  290.69     432  342.53     430
  391.09     422  472.58     420  485.64     418  748.94  419.97  783.24     418
 1018.61  419.63 1071.88     422 1106.71     430 1131.67  432.26 1695.34     436
 1779.36     434 1836.94     410    1873   404.6 1910.19  411.61 1932.32     426
 1938.81     428 1995.93     432    2065     446    2569     442 2592.29     440
 2669.56   439.8 2678.46     438 2779.26   439.4 2832.96     444 2888.22     444
#Mann= 6 ,-1,0
   205.2    .035       0  290.69    .045       0 1131.67    .085       0
 1779.36     .05       0 1995.93     .06       0    2065     .08       0
#XS Ineff= 2 , 0
       0    1695     436    2065       0     446
Permanent Ineff=
       F       F
Bank Sta=1779.36,1995.93
XS Rating Curve= 0 ,0
Exp/Cntr=0.3,0.1

Type RM Length L Ch R = 1 ,42111   ,242,425,444
BEGIN DESCRIPTION:
This cross section corresponds to cross section 42166 of the non-georeferenced CDC model which was the source of this model.
FLOWLINE INTERPOLATED FROM CURRENT EFFECTIVE GEOMETRY, LEFT OVERBANK TAKEN FROM 1999 CGP TOPOGRAPHY, RIGHT OVERBANK TAKEN FROM COMBINATION OF 12/08 FIELD SURVEYS AND 1999 CGP TOPO
END DESCRIPTION:
XS GIS Cut Line= 3
2433823.960378896964899.18512677     2433087.944     6963057.478
2433161.922816556962373.91147914
#Sta/Elev= 30
  264.32  449.86  283.58  449.15  357.19     432   410.4     430  453.72     422
  511.46     420  521.98     418   993.7  419.47 1087.57  421.51 1107.02     422
 1150.21     432 1192.85     434 1485.37  432.44 1793.75     436 1895.77     434
 1962.23     410    1994   404.5 2026.81  411.15 2049.93     426 2086.32  430.02
 2096.57     434 2257.51  436.19 2293.47     438 2328.05     444  2365.1     446
 2567.17     442 2630.76     438  2733.4  436.22 2886.42     444 2935.21  444.49
#Mann= 5 ,-1,0
  264.32    .035       0  357.19    .045       0 1192.85    .085       0
 1895.77     .05       0 2096.57     .06       0
#XS Ineff= 2 , 0
       0    1793     436    2176       0     446
Permanent Ineff=
       F       F
Bank Sta=1895.77,2096.57
XS Rating Curve= 0 ,0
Exp/Cntr=0.3,0.1