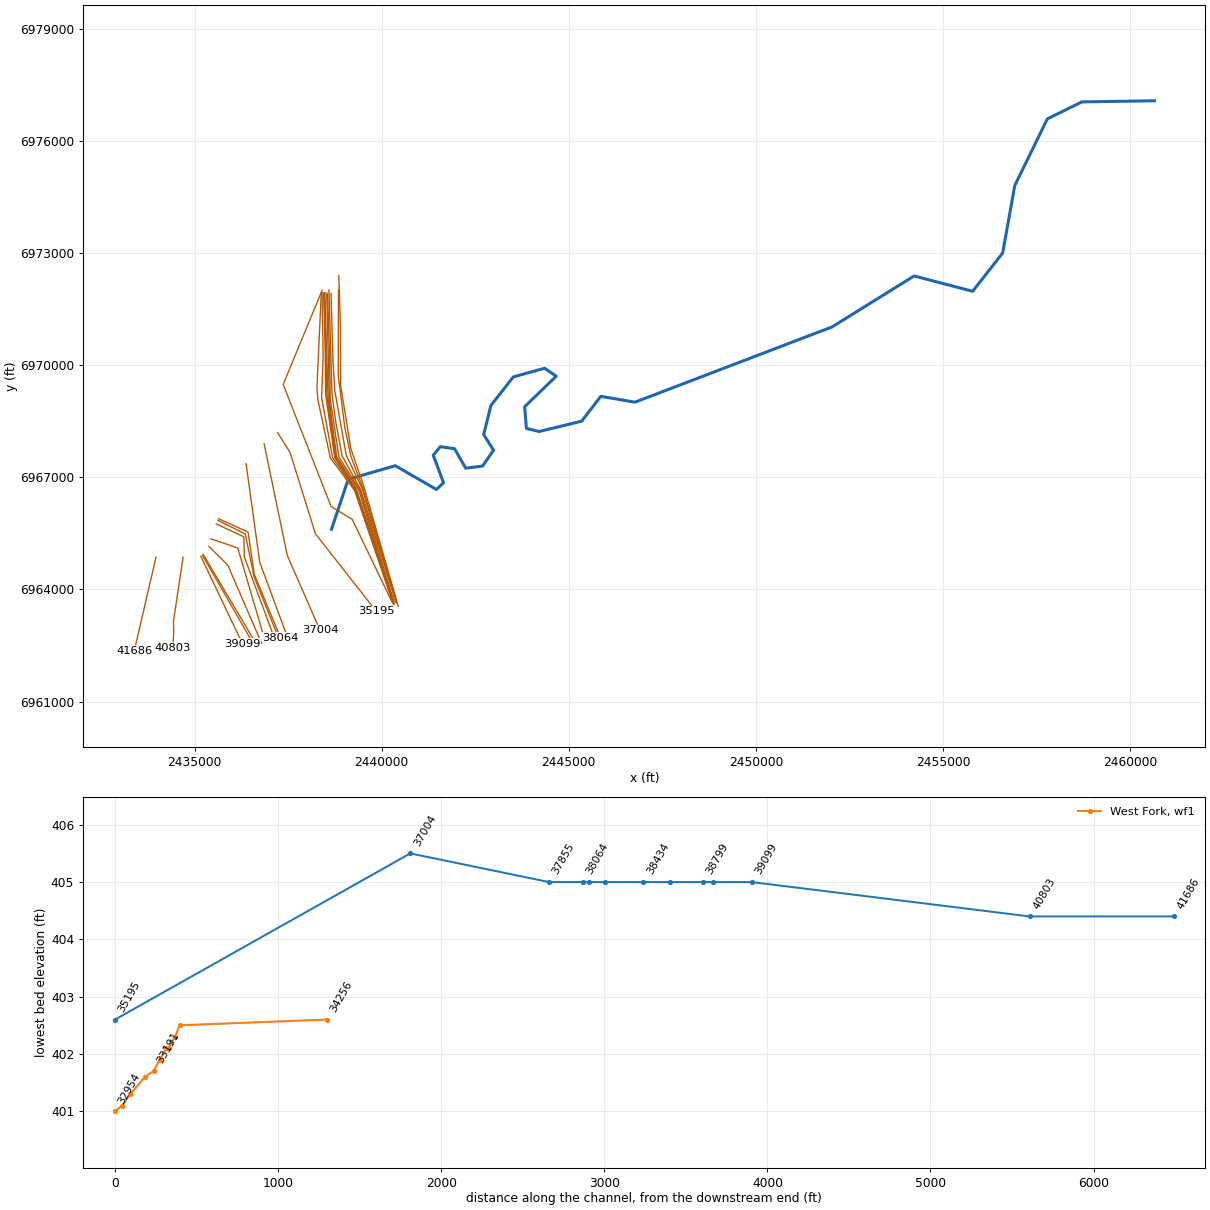
HEC-RAS study CDC_Consolidated_Model.prj: Upper Trinity CDC Consolidated Model

--- CDC_Consolidated_Model.g01 (geometry) --- (continued)

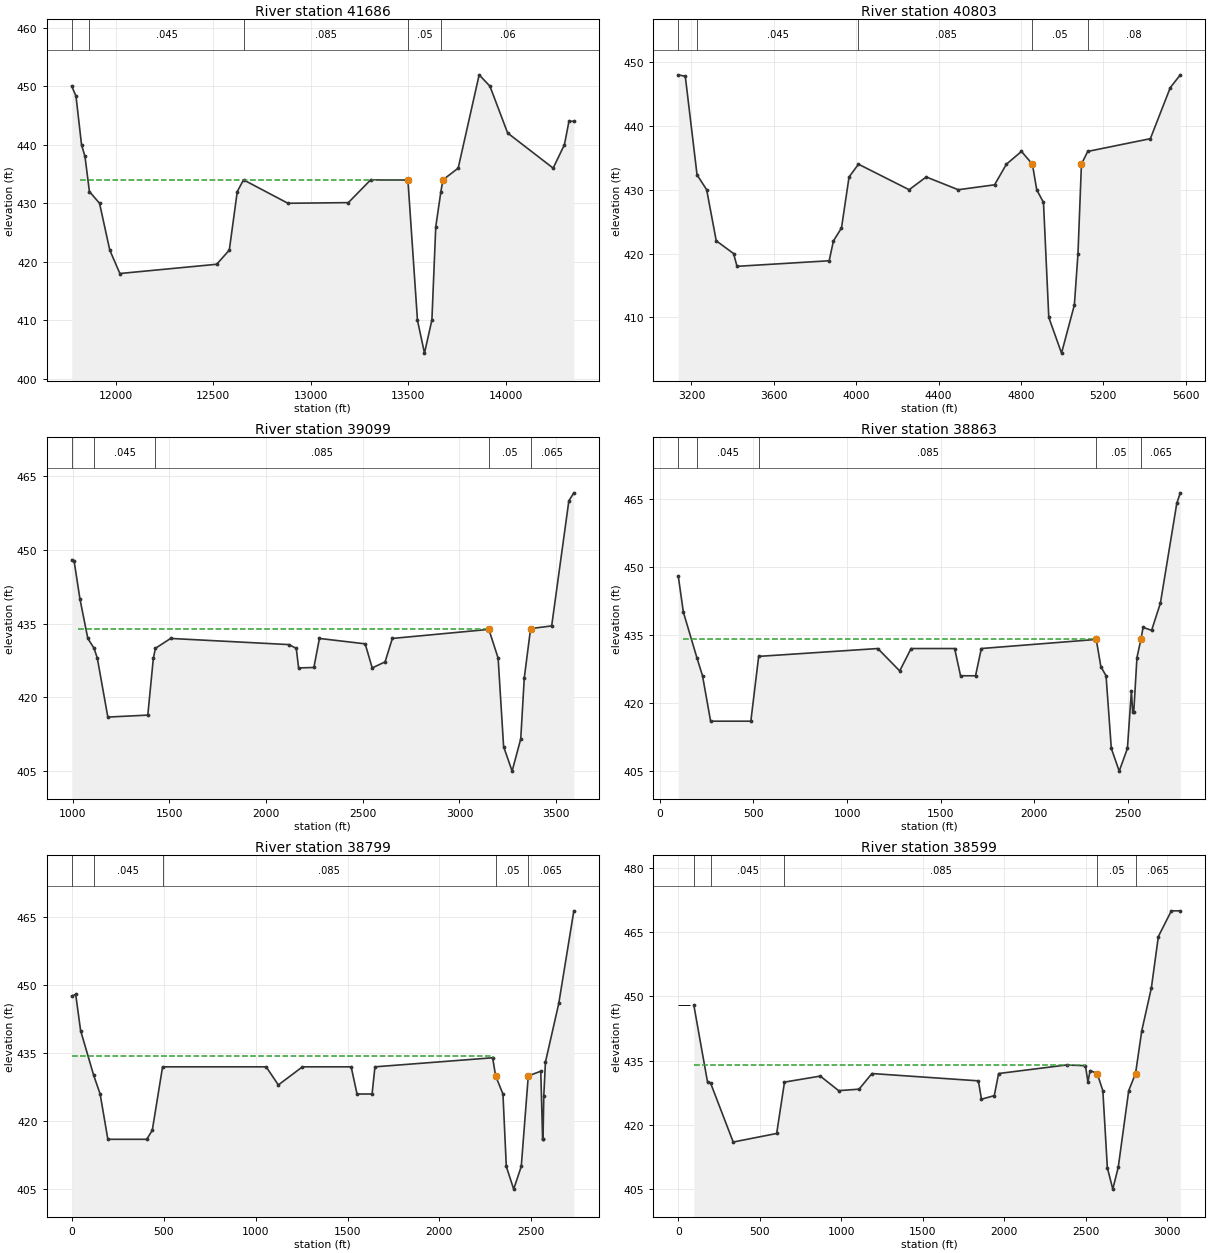
Type RM Length L Ch R = 1 ,41686   ,605,883,938
BEGIN DESCRIPTION:
This cross section corresponds to cross section 41697 of the non-georeferenced CDC model which was the source of this model.
FLOWLINE AND BOTTOM OF CHANNEL TAKEN FROM EFFECTIVE SECTION AT STATIONS 13563 AND 13583, TRANSITION TO 1999 CITY OF GRAND PRAIRIE TOPOGRAPHY AT STATION 13621,
LEFT OVERBANK STARTING AT STATION 13498 TO BEGIN OF XS TAKEN FROM 1999 CGP TOPOGRAPHY
-WAW
END DESCRIPTION:
XS GIS Cut Line= 6
  2433970.322007 6964865.2338734 2433862.5338848 6964399.7766662
 2433794.9539675 6964107.9563837 2433659.7901958 6963524.3161467
 2433524.6211748 6962940.6768941 2433389.4469045 6962357.0379695
#Sta/Elev= 30
11774.32     45011795.95   448.311824.39     44011842.06     438 11864.8     432
11916.68     43011969.25     422   12021     41812517.44  419.5812582.17     422
12622.92     43212655.07     43412882.71     43013192.61  430.1113307.01     434
   13498  433.9613547.05     410   13583   404.413621.02  410.0713640.86     426
13667.13     43213677.74     43413755.77     43613863.33  451.9413918.61     450
14009.42     44214242.81     43614300.56     44014323.81     444 14348.9     444
#Mann= 5 ,-1,0
11774.32    .035       0 11864.8    .045       012655.07    .085       0
   13498     .05       013667.13     .06       0
#XS Ineff= 1 ,-1
   11819   13498     434
Permanent Ineff=
       F
#Block Obstruct= 2 , 0
       0                   13860       0   451.7
Bank Sta=13498,13677.74
XS Rating Curve= 0 ,0
Exp/Cntr=0.3,0.1

Type RM Length L Ch R = 1 ,40803   ,1075,1704,1780
BEGIN DESCRIPTION:
This cross section corresponds to cross section 40850 of the non-georeferenced CDC model which was the source of this model.
END DESCRIPTION:
XS GIS Cut Line= 5
  2434693.981471 6964866.1636147 2434435.3497302 6963144.3570026
 2434439.7042704 6963020.3125196  2434444.058797 6962896.2685454
  2434418.596501 6962448.1952808
#Sta/Elev= 30
 3135.65     448 3169.88  447.77 3227.02  432.33 3273.69     430 3320.22     422
 3404.35     420 3421.19     418 3868.56  418.87 3889.49     422 3928.36     424
  3965.2     432 4010.95     434 4256.98     430 4339.81     432 4495.38     430
 4671.88  430.77 4729.27     434 4802.56     436 4855.51     434 4876.52     430
 4909.36     428 4935.12     410    4997   404.4 5059.37  411.95 5076.88     420
 5093.64     434 5124.21     436 5428.42     438 5525.08     446 5573.81     448
#Mann= 5 ,-1,0
 3135.65    .035       0 3227.02    .045       0 4010.95    .085       0
 4855.51     .05       0 5124.21     .08       0
#XS Ineff= 1 ,-1
    3191    4802     434
Permanent Ineff=
       F
Bank Sta=4855.51,5093.64
XS Rating Curve= 0 ,0
Exp/Cntr=0.3,0.1

Type RM Length L Ch R = 1 ,39099   ,107,236,236
BEGIN DESCRIPTION:
This cross section corresponds to cross section 39095 of the non-georeferenced CDC model which was the source of this model.
END DESCRIPTION:
XS GIS Cut Line= 2
     2435167.682     6964887.9172436283.00972025 6962543.4541269
#Sta/Elev= 30
   995.3     448 1007.42  447.75 1037.73     440 1078.28     432  1110.5     430
 1127.34     428 1181.83     416 1388.48   416.4 1417.18     428 1428.11     430
 1506.43     432 2117.14  430.75  2156.1     430 2168.26     426  2247.2  426.09
    2276     432  2512.5   430.9 2548.89     426 2615.35  427.23 2653.06     432
 3152.04  433.84    3200     428 3228.31     410  3272.3     405 3316.97  411.57
 3335.29     424 3367.94     434 3476.86  434.55 3565.73     460 3591.54  461.63
#Mann= 5 ,-1,0
   995.3    .035       0  1110.5    .045       0 1428.11    .085       0
 3152.04     .05       0 3367.94    .065       0
#XS Ineff= 1 ,-1
  1028.3  3151.3     434
Permanent Ineff=
       F
Bank Sta=3152.04,3367.94
XS Rating Curve= 0 ,0
Exp/Cntr=0.3,0.1

Type RM Length L Ch R = 1 ,38863   ,37,64,64
BEGIN DESCRIPTION:
This cross section corresponds to cross section 38702 of the non-georeferenced CDC model which was the source of this model.
END DESCRIPTION:
XS GIS Cut Line= 2
     2435213.571     6964910.862     2436538.604     6962599.224
#Sta/Elev= 30
    98.1     448  125.62     440  197.66     430  227.81     426  271.09     416
  485.96     416   527.8  430.27 1164.34     432 1281.31  427.07 1342.08     432
 1574.72     432 1606.31     426 1686.45     426 1717.36     432 2331.25     434
 2356.02     428 2383.63     426  2411.8     410    2454     405  2497.8     410
  2519.1  422.71 2525.82     418 2531.64     418 2548.75     430 2569.82     434
 2581.58  436.66 2627.01     436 2674.03     442 2761.63     464 2780.38  466.29
#Mann= 5 ,-1,0
    98.1    .035       0  197.66    .045       0   527.8    .085       0
 2331.25     .05       0 2569.82    .065       0
#XS Ineff= 1 ,-1
     121    2331     434
Permanent Ineff=
       F
Bank Sta=2331.25,2569.82
XS Rating Curve= 0 ,0
Exp/Cntr=0.3,0.1

Type RM Length L Ch R = 1 ,38799   ,431,200,184
BEGIN DESCRIPTION:
This cross section corresponds to cross section 38623 of the non-georeferenced CDC model which was the source of this model.
END DESCRIPTION:
XS GIS Cut Line= 2
     2435230.779     6964939.542     2436624.645     6962582.016
#Sta/Elev= 30
       0   447.6   21.37     448   48.11     440  119.39   430.1  154.28     426
  196.39     416  407.97     416     438     418     494     432 1057.62     432
 1123.73     428 1255.01     432 1519.88     432 1551.92     426  1633.7     426
 1649.36     432 2289.63     434 2305.72     430 2345.68     426 2363.96     410
    2404     405 2445.26     410 2483.51     430 2551.45  431.03 2561.43     416
 2563.57     416 2567.94  425.66 2576.75  433.03 2649.33     446 2731.35  466.44
#Mann= 5 ,-1,0
       0    .035       0  119.39    .045       0     494    .085       0
 2305.72     .05       0 2483.51    .065       0
#XS Ineff= 2 , 0
       0 2289.79  434.47 2483.51       0     430
Permanent Ineff=
       F       F
Bank Sta=2305.72,2483.51
XS Rating Curve= 0 ,0
Exp/Cntr=0.3,0.1

Type RM Length L Ch R = 1 ,38599   ,427,165,146
BEGIN DESCRIPTION:
This cross section corresponds to cross section 38451 of the non-georeferenced CDC model which was the source of this model.
END DESCRIPTION:
XS GIS Cut Line= 3
2435384.05502298 6965153.3748598     2435890.427     6964647.002
     2436790.991     6962564.807
#Sta/Elev= 30
   96.08  447.89   179.8     430  198.94  429.73  337.27     416     604     418
     652     430  871.64   431.4  984.38     428  1109.6  428.35 1188.43     432
 1841.51  430.29 1860.71     426 1939.25  426.84    1966     432 2382.95     434
 2498.81  433.82 2513.95     430 2527.35   432.7 2570.82     432 2605.44     428
 2633.11     410  2666.5     405 2700.13  410.15 2764.15     428  2806.1     432
 2844.31     442 2903.18     452 2946.04     464 3025.88     470  3080.8     470
#Mann= 5 ,-1,0
   96.08    .035       0  198.94    .045       0     652    .085       0
 2570.82     .05       0  2806.1    .065       0
#XS Ineff= 2 , 0
       0    2498     434               0
Permanent Ineff=
       F       F
#Block Obstruct= 2 , 0
       0      71     448               0
Bank Sta=2570.82,2806.1
XS Rating Curve= 0 ,0
Exp/Cntr=0.3,0.1

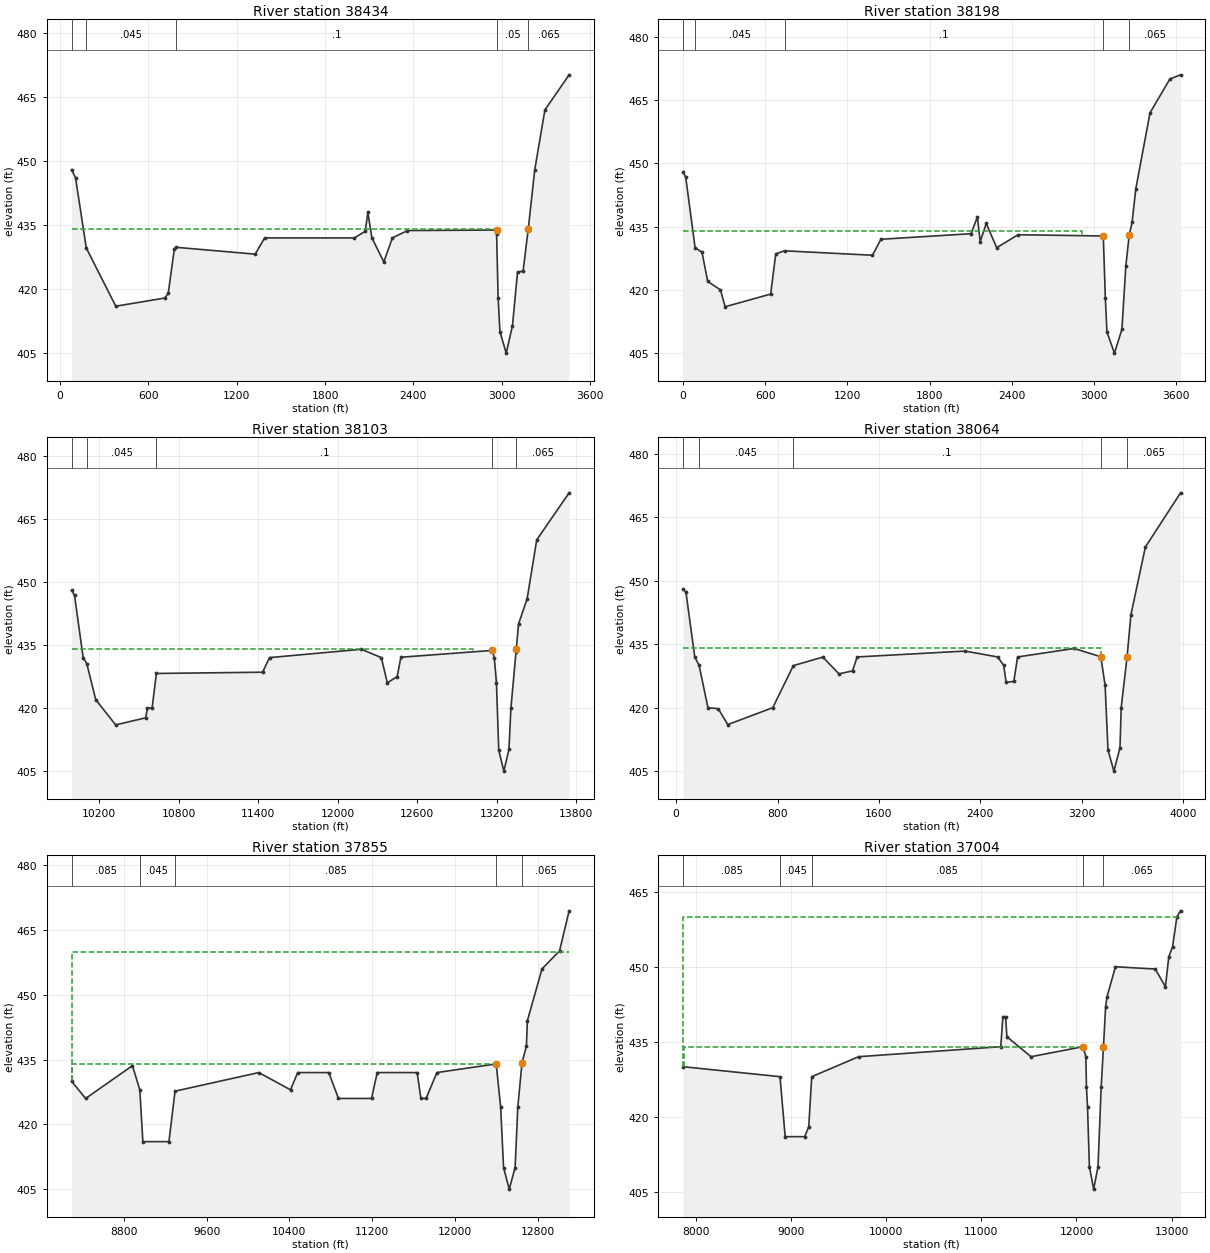
Type RM Length L Ch R = 1 ,38434   ,154,235,249
BEGIN DESCRIPTION:
This cross section corresponds to cross section 38285 of the non-georeferenced CDC model which was the source of this model.
END DESCRIPTION:
XS GIS Cut Line= 4
2435439.981997236965353.66118131     2435460.222     6965346.803
     2436154.287     6965111.624      2436894.24     6962593.488
#Sta/Elev= 30
   78.43     448  105.53  446.12  178.32  429.66  378.68     416  710.39   417.9
  734.86     419     776   429.3     790   429.8 1325.29   428.2 1389.87     432
 1999.11     432 2072.84  433.56 2090.53     438 2118.11     432 2198.94  426.38
 2257.01     432 2359.37  433.73 2964.18  433.85 2964.87  432.88 2975.08     418
 2987.54     410 3030.07     405 3072.64  411.43 3106.83     424 3144.61  424.22
 3179.42     434 3180.69  434.36 3223.93     448 3292.74     462 3457.23  470.23
#Mann= 5 ,-1,0
   78.43    .035       0  178.32    .045       0     790      .1       0
 2964.87     .05       0 3180.69    .065       0
#XS Ineff= 2 , 0
       0    2964     434               0
Permanent Ineff=
       F       F
Bank Sta=2964.18,3179.42
XS Rating Curve= 0 ,0
Exp/Cntr=0.3,0.1

Type RM Length L Ch R = 1 ,38198   ,60,95,99
BEGIN DESCRIPTION:
This cross section corresponds to cross section 38167 of the non-georeferenced CDC model which was the source of this model.
END DESCRIPTION:
XS GIS Cut Line= 4
     2435580.679     6965754.064     2436314.897       6965409.9
     2436332.105     6964864.9732437121.446464076962731.02988022
#Sta/Elev= 30
       0     448   20.18  446.71   88.63     430  139.05  428.92  180.51     422
  273.71     420  307.74     416     640     419  677.25  428.53  741.14  429.26
 1382.68  428.21 1445.33     432 2102.68  433.32 2148.79  437.28 2169.22  431.44
 2213.48  435.74 2289.76     430 2445.27  433.07 3067.52  432.78 3082.63     418
 3094.34     410 3148.92     405 3203.51  410.64  3232.1  425.66 3256.81  432.98
 3277.63     436 3305.12     444 3408.82     462 3553.89     470 3631.33  470.99
#Mann= 5 ,-1,0
       0    .035       0   88.63    .045       0  741.14      .1       0
 3067.52    .055       0 3256.81    .065       0
#XS Ineff= 2 , 0
       0    2912     434               0
Permanent Ineff=
       F       F
Bank Sta=3067.52,3256.81
XS Rating Curve= 0 ,0
Exp/Cntr=0.3,0.1

Type RM Length L Ch R = 1 ,38103   ,156,39,86
BEGIN DESCRIPTION:
This cross section corresponds to cross section 38059 of the non-georeferenced CDC model which was the source of this model.
END DESCRIPTION:
XS GIS Cut Line= 4
     2435620.832     6965851.578     2436355.049     6965484.469
     2436590.228      6964342.99 2437247.03113126962700.98265719
#Sta/Elev= 30
    9992     44810014.48  446.8310079.56     43210106.85  430.5810174.57     422
10324.69     41610551.45  417.68   10565     420   10600     42010632.12  428.23
11433.79  428.5311486.02     43212179.22  433.9812329.66     432 12375.1     426
12449.31  427.49 12477.5  432.0913166.35  433.7113182.04     432 13198.3     426
13215.78     41013254.19     405 13292.6  410.1513307.71     42013346.14  433.39
13347.89     43413365.25     44013430.14     44613502.31     46013746.83  471.19
#Mann= 5 ,-1,0
    9992    .035       010106.85    .045       010632.12      .1       0
13166.35    .055       013346.14    .065       0
#XS Ineff= 2 , 0
       0   13021     434               0
Permanent Ineff=
       F       F
Bank Sta=13166.35,13347.89
XS Rating Curve= 0 ,0
Exp/Cntr=0.3,0.1

Type RM Length L Ch R = 1 ,38064   ,417,209,203
BEGIN DESCRIPTION:
This cross section corresponds to cross section 37966 of the non-georeferenced CDC model which was the source of this model.
END DESCRIPTION:
XS GIS Cut Line= 4
     2435643.776      6965891.73     2436429.618     6965536.094
     2436595.964     6964406.087      2437296.58      6962712.77
#Sta/Elev= 30
   53.59     448   77.12  447.35  146.57     432  181.04     430  250.69     420
  331.92  419.76  407.02     416  761.92     420  924.49  429.95  1157.1  431.97
 1284.18     428 1391.17  428.71 1427.85     432  2278.7  433.39 2536.14     432
 2584.21     430  2602.9     426 2663.64  426.22 2693.47     432 3138.84     434
 3350.35  432.05 3383.89  425.28 3406.65     410 3453.05     405 3501.35  410.56
 3510.72     420 3557.09  431.99 3587.68     442 3701.65     458 3978.93  470.81
#Mann= 5 ,-1,0
   53.59    .035       0  181.04    .045       0  924.49      .1       0
 3350.35    .055       0 3557.09    .065       0
#XS Ineff= 2 , 0
       0    3350     434               0
Permanent Ineff=
       F       F
#Block Obstruct= 2 , 0
       0      54     448               0
Bank Sta=3350.35,3557.09
XS Rating Curve= 0 ,0
Exp/Cntr=0.3,0.1

Type RM Length L Ch R = 1 ,37855   ,961,851,880
BEGIN DESCRIPTION:
This cross section corresponds to cross section 37866 of the non-georeferenced CDC model which was the source of this model.
Cross-section Truncated due to Ineffective Flow Areas
END DESCRIPTION:
XS GIS Cut Line= 6
  2436376.906706  6967366.276467 2436565.8040688 6966001.9929499
 2436742.4759596 6964726.1011447 2437114.4086147 6963720.0769101
  2437283.476518 6963262.7943601 2437486.3639075 6962714.0569405
#Sta/Elev= 30
  8293.5     430  8429.5     426 8882.37   433.6 8953.52     428 8983.05     416
 9235.23     416 9293.89  427.6910103.46     43210410.75     42810479.71     432
10780.27     43210874.04     426 11193.7     42611248.91     43211635.02     432
11670.69     42611720.98     426 11825.9     43212398.99     43412442.07     424
12470.18     410   12525     40512581.95     410 12607.9     42412648.37  434.22
12691.31  438.1712700.31     44412841.76     45613011.55   460.213104.02  469.46
#Mann= 5 ,-1,0
  8293.5    .085       0 8953.52    .045       0 9293.89    .085       0
12398.99    .055       012648.37    .065       0
#XS Ineff= 2 ,-1
  8293.5   12398     434    8293  8293.5     460
Permanent Ineff=
       F       F
Bank Sta=12398.99,12648.37
XS Rating Curve= 0 ,0
Exp/Cntr=0.3,0.1

Type RM Length L Ch R = 1 ,37004   ,802,1810,1504
BEGIN DESCRIPTION:
This cross section corresponds to cross section 37015 of the non-georeferenced CDC model which was the source of this model.
Cross-section Truncated due to Ineffective Flow Areas
END DESCRIPTION:
XS GIS Cut Line= 6
  2436859.918435 6967892.8226235 2437138.8058756  6966548.842578
 2437299.1543082 6965776.1603963  2437479.554866 6964906.8940902
 2437898.5015347 6963949.8412143 2438355.5619722 6962905.7901528
#Sta/Elev= 30
    7861     430 8881.83     428  8936.2     416  9141.7     416 9184.24     418
 9215.47     428 9708.41     43211204.02     43411226.23     44011254.94     440
11268.47     43611522.11     43212068.39     434 12099.4     432 12105.1     426
12116.48     42212136.32     410   12181   405.512227.13     41012260.45     426
12284.33     43412306.89     44212321.73     44412410.36     45012829.84  449.54
12935.96     44612971.33     45213011.37     45413056.74     46013094.99  461.19
#Mann= 5 ,-1,0
    7861    .085       0 8881.83    .045       0 9215.47    .085       0
12068.39    .055       012284.33    .065       0
#XS Ineff= 2 ,-1
    7860    7861     460    7870   12068     434
Permanent Ineff=
       F       F
Bank Sta=12068.39,12284.33
XS Rating Curve= 0 ,0
Exp/Cntr=0.3,0.1

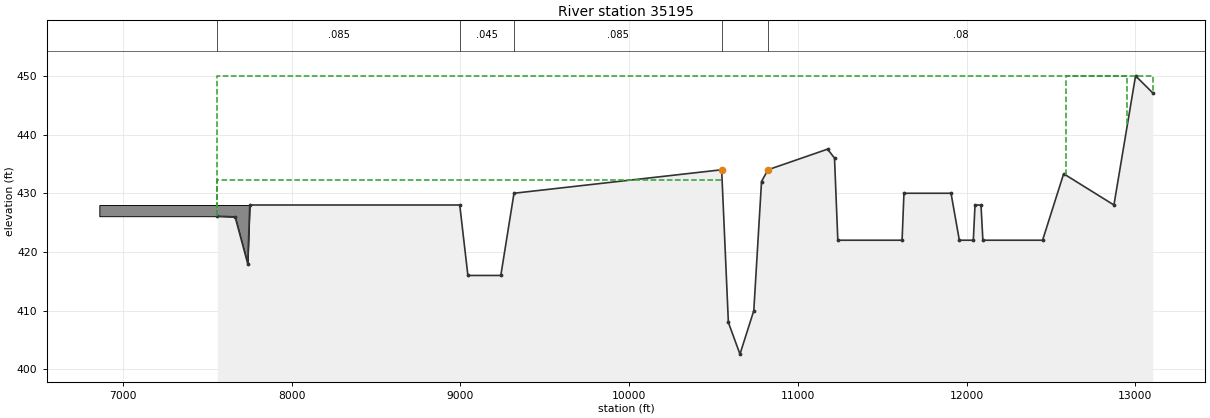
Type RM Length L Ch R = 1 ,35195   ,0,0,0
BEGIN DESCRIPTION:
This cross section corresponds to cross section 35205 of the non-georeferenced CDC model which was the source of this model.
FLOWLINE INTERPOLATED AT STATION 10661 FROM EFFECTIVE PROFILE
END DESCRIPTION:
XS GIS Cut Line= 6
      2437221.51      6968191.11 2437555.6311574 6967658.4994794
 2437877.7912743 6966622.1170377 2438229.2610438  6965491.521858
 2438934.0490043 6964592.7939967 2439856.6961147 6963416.2719413
#Sta/Elev= 30
    7560  426.09 7665.51  425.98 7740.26     418 7752.48     428  8996.6     428
 9044.83     416 9239.96     416 9318.02     43010548.51     43410588.34     408
   10657   402.610738.95     41010784.78     43210823.02     43411175.95  437.51
11217.23     43611236.85     42211617.63     42211628.68     43011907.63     430
11956.91     42212039.82     42212049.75     42812085.17     42812096.33     422
12450.17     42212575.02  433.3212872.88     428 13001.1     45013102.89  447.09
#Mann= 5 ,-1,0
    7560    .085       0  8996.6    .045       0 9318.02    .085       0
10548.51    .055       010823.02     .08       0
#XS Ineff= 4 ,-1
 12589.9   12953     450    7560    7560     450   11155 12589.9   432.2
    7560   10548   432.2
Permanent Ineff=
       T       F       F       F
#Block Obstruct= 1 ,-1
    6861    7753     428
Bank Sta=10548.51,10823.02
XS Rating Curve= 0 ,0
Exp/Cntr=0.3,0.1

River Reach=West Fork       ,wf1
Reach XY= 30
        2438660.      6965610.97      2439107.13       6966947.7
      2440364.74      6967311.11      2441463.54      6966675.05
       2441652.7      6966856.62      2441378.77      6967591.89
      2441565.52      6967819.41      2441947.52      6967765.42
      2442246.67      6967244.02      2442699.76      6967301.91
       2442990.1      6967724.76      2442726.08      6968143.18
      2442919.19      6968919.88       2443518.4      6969685.89
      2444352.98      6969917.06      2444667.07      6969705.87
      2443821.45      6968887.79      2443868.87      6968306.35
      2444209.34      6968225.94      2445345.53      6968501.95
      2445856.58      6969165.84      2446770.54      6969010.06
      2452038.46      6971023.33      2454231.09      6972385.64
      2455794.74      6971975.24      2456596.76      6973000.46
      2456919.85       6974803.1       2457790.9      6976586.85
      2458714.96      6977041.16       2460651.9      6977070.51

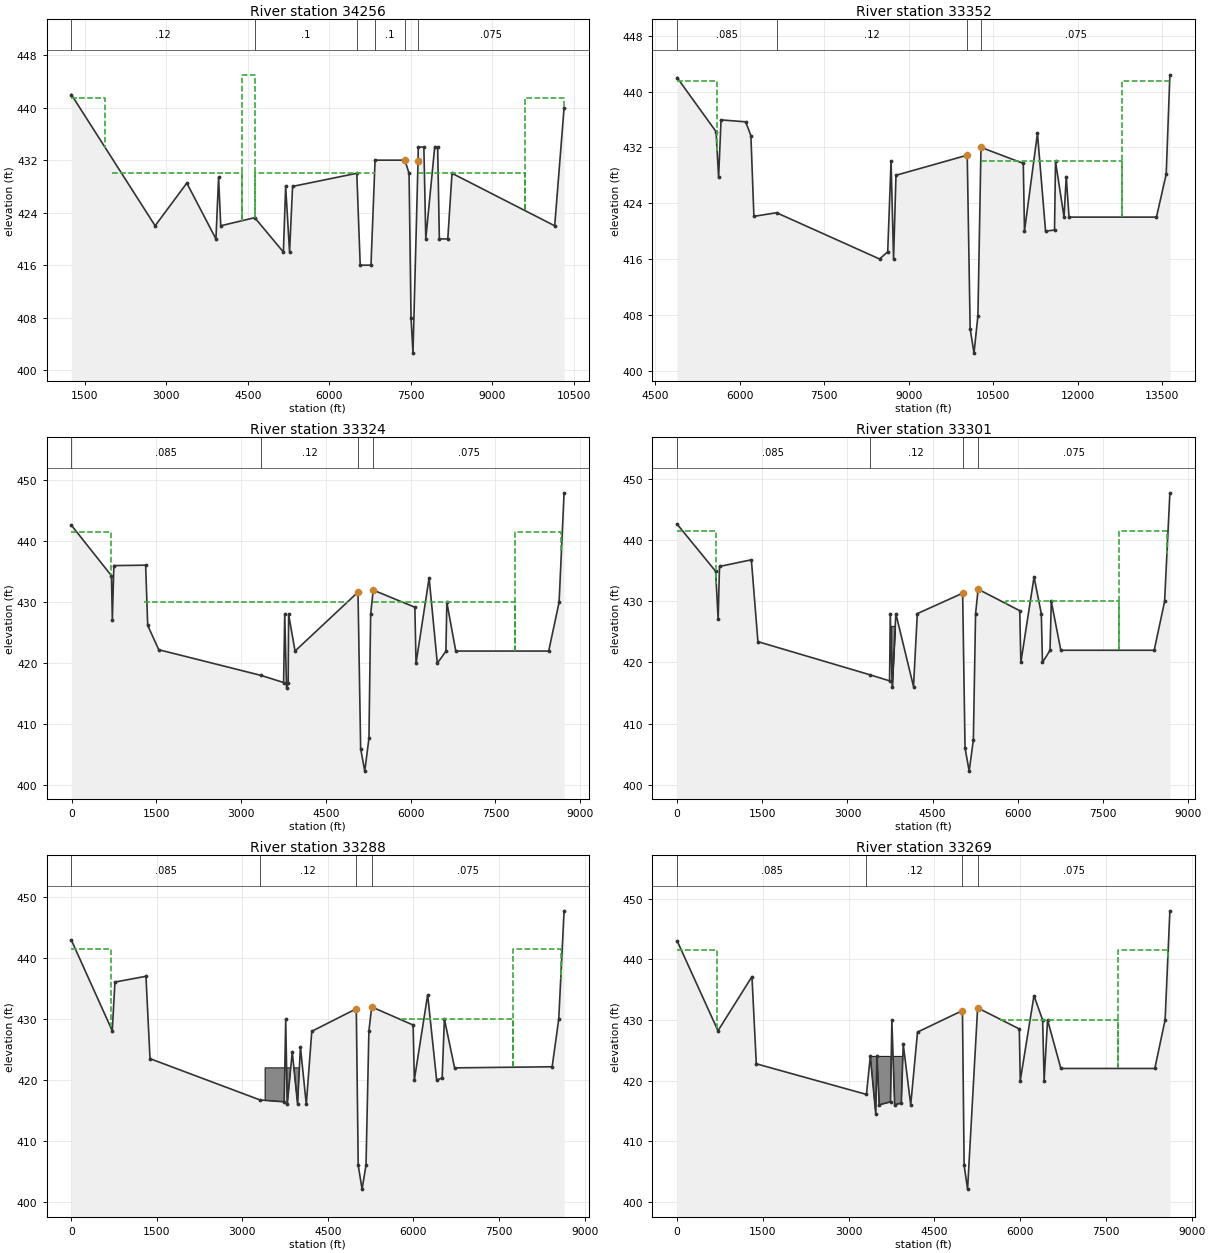
Type RM Length L Ch R = 1 ,34256   ,674,904,306
BEGIN DESCRIPTION:
This cross section corresponds to cross section 34268 of the non-georeferenced CDC model which was the source of this model.
STATIONS 7543-7573 ADDED FROM EFFECTIVE SECTION
FOR FLOWLINE
END DESCRIPTION:
XS GIS Cut Line= 6
      2438410.82      6972007.01       2437369.4      6969485.32
 2437700.4950409 6968636.1779702 2438650.5371041 6966217.6529516
 2439213.2738395 6965876.4180698 2440272.3609602 6963674.9818559
#Sta/Elev= 30
    1249     442 2793.01     422 3376.86  428.51  3913.3     420 3962.13  429.38
 4001.79     422 4627.69  423.24 5155.75     418 5197.43     428 5269.62     418
 5325.11     428 6507.97     430    6571     416 6769.38     416 6844.63     432
 7393.73     432 7470.61     430 7506.88     408    7543   402.6 7636.07  431.81
 7639.87     434 7743.76     434 7778.93     420 7943.02     434 7997.58     434
 8028.91     420 8184.18     420 8261.76     43010153.69     42210326.63     440
#Mann= 6 ,-1,0
    1249     .12       0 4627.69      .1       0 6507.97    .045       0
 6844.63      .1       0 7393.73    .055       0 7639.87    .075       0
#XS Ineff= 6 ,-1
 4389.04 4626.26     445    1249    1878   441.5    960010326.63   441.5
 4626.26    6844     430    7639    9600     430 2003.31    4389     430
Permanent Ineff=
       T       F       F       F       F       F
Bank Sta=7393.73,7636.07
XS Rating Curve= 0 ,0
Exp/Cntr=0.3,0.1

Type RM Length L Ch R = 1 ,33352   ,34,28,6
BEGIN DESCRIPTION:
This cross section corresponds to cross section 33382 of the non-georeferenced CDC model which was the source of this model.
END DESCRIPTION:
XS GIS Cut Line= 6
      2438386.71      6971935.91 2438270.8679159  6969406.600642
 2438292.5693161 6969094.1006108 2438626.7707474 6967522.9200262
      2439276.51      6966651.88      2440305.74      6963621.36
#Sta/Elev= 30
    4890     442 5581.54  434.25 5626.66  427.69 5669.97  435.94 6107.35  435.66
 6199.87  433.68 6253.14  422.11 6654.71  422.63 8482.86     416 8628.25  417.03
  8687.4  429.99 8732.44     416 8775.09     42810039.77  430.8810091.57     406
   10160   402.510229.52  407.8710283.96     432 11034.7   429.711056.13     420
11286.22     43411430.16     42011589.17  420.1411606.73     43011757.83     422
11797.07  427.8111846.53     42213398.52     422 13571.5  428.1613636.92   442.4
#Mann= 4 ,-1,0
    4890    .085       0 6654.71     .12       010039.77    .055       0
10283.96    .075       0
#XS Ineff= 4 ,-1
    4890    5601   441.5   12790   13636   441.5   10283   12790     430
    6137    9895     430
Permanent Ineff=
       T       F       F       F
Bank Sta=10039.77,10283.96
XS Rating Curve= 0 ,0
Exp/Cntr=0.3,0.1

Type RM Length L Ch R = 1 ,33324   ,57,23,13
BEGIN DESCRIPTION:
This cross section corresponds to cross section 33335 of the non-georeferenced CDC model which was the source of this model.
END DESCRIPTION:
XS GIS Cut Line= 6
2438405.47974354 6971935.2313794  2438437.076573 6970272.2472047
 2438395.8440439 6969130.7540808 2438688.8126181 6967524.8511246
  2439284.515823 6966668.7314458 2440320.4317302 6963618.9268499
#Sta/Elev= 30
      -5  442.66  705.53  434.36  721.21  427.12  748.19  436.02 1310.33  436.09
 1346.95  426.21 1542.07  422.22 3354.07     418 3751.43  416.84 3771.72     428
 3803.44     416  3832.1   416.7 3840.67     428    3954     422 5068.05  431.67
 5115.05     406    5188   402.3 5261.81   407.7 5291.99     428 5337.17     432
 6074.34  429.19 6095.09     420 6326.51     434 6471.56     420 6623.51  421.96
 6640.13     430 6798.23     422 8442.34     422 8626.45     430 8714.93  447.96
#Mann= 4 ,-1,0
      -5    .085       0 3354.07     .12       0 5068.05    .055       0
 5337.17    .075       0
#XS Ineff= 4 ,-1
      -5     690   441.5    7840    8667   441.5    5337    7840     430
    1288    4867     430
Permanent Ineff=
       T       F       F       F
Bank Sta=5068.05,5337.17
XS Rating Curve= 0 ,0
Exp/Cntr=0.3,0.1

Type RM Length L Ch R = 1 ,33301   ,34,13,9
BEGIN DESCRIPTION:
This cross section corresponds to cross section 33313 of the non-georeferenced CDC model which was the source of this model.
END DESCRIPTION:
XS GIS Cut Line= 6
  2438449.083438 6971937.8288472 2438492.4862391 6970352.5423197
 2438502.2519676 6969218.6446531  2438747.477527 6967524.8511246
 2439295.4377172 6966671.9866886 2440324.8431387 6963618.9268499
#Sta/Elev= 30
       0  442.66  678.57  434.94  722.84  427.09  747.05  435.73 1307.99  436.82
 1423.46  423.41 3390.11     418 3742.22  416.99  3754.7     428 3788.34     416
 3852.63     428 4163.98  416.06 4230.62     428 5029.25  431.35 5071.39     406
    5144   402.2  5217.9   407.3 5256.99     428 5302.07     432 6034.87  428.48
 6054.32     420 6286.96     434 6414.76     428 6435.46     420 6568.16  421.99
  6590.6     430 6758.66     422 8403.08     422 8586.15     430 8679.42  447.79
#Mann= 4 ,-1,0
       0    .085       0 3390.11     .12       0 5029.25    .055       0
 5302.07    .075       0
#XS Ineff= 4 ,-1
       0     690   441.5    7789    8627   441.5    5795    7789     430
    1325    4795     430
Permanent Ineff=
       T       F       F       F
#Block Obstruct= 1 ,-1
    3770    3839     426
Bank Sta=5029.25,5302.07
XS Rating Curve= 0 ,0
Exp/Cntr=0.3,0.1

Type RM Length L Ch R = 1 ,33288   ,29,18,17
BEGIN DESCRIPTION:
This cross section corresponds to cross section 33294 of the non-georeferenced CDC model which was the source of this model.
END DESCRIPTION:
XS GIS Cut Line= 6
  2438466.397708 6971932.2832547 2438536.9011765 6969172.1270296
 2438759.4706132 6967536.5367968  2439181.315242 6966872.0099106
 2439316.3395782  6966666.023446 2440325.2043584 6963620.2086715
#Sta/Elev= 30
       0  442.98   717.8  428.09   765.3  436.08 1308.83  437.03 1380.07  423.51
  3310.3  416.73 3732.68  416.43 3759.42     430 3786.24     416 3874.24   424.6
  3967.7  416.06 4017.49  425.41  4120.3     416 4216.51     428 4996.94   431.7
 5030.93     406  5098.5   402.1 5167.67  406.06 5217.83     428  5266.5     432
 5993.88  429.03 6014.47     420 6248.52     434 6405.88     420 6502.63  420.34
 6541.85     430 6720.75     422 8431.15  422.18  8546.9     430 8640.66  447.77
#Mann= 4 ,-1,0
       0    .085       0  3310.3     .12       0 4996.94    .055       0
  5266.5    .075       0
#XS Ineff= 4 ,-1
       0     690   441.5    7745    8582   441.5    5795    7745     430
    1322    4814     430
Permanent Ineff=
       T       F       F       F
#Block Obstruct= 1 ,-1
    3398    4017     422
Bank Sta=4996.94,5266.5
XS Rating Curve= 0 ,0
Exp/Cntr=0.3,0.1

Type RM Length L Ch R = 1 ,33269   ,35,39,21
BEGIN DESCRIPTION:
This cross section corresponds to cross section 33267 of the non-georeferenced CDC model which was the source of this model.
END DESCRIPTION:
XS GIS Cut Line= 6
  2438482.626678 6971933.4085805 2438526.8975876 6970412.5753361
 2438571.1681683 6969087.0543651 2438774.2934182 6967542.7835035
 2439328.9806291  6966672.991936 2440325.7256828 6963620.6916101
#Sta/Elev= 30
       0  443.06  715.21  428.22 1309.13  437.15 1384.98  422.77 3311.17  417.72
 3379.19     424  3473.6  414.57 3495.88     424 3534.83     416 3732.06  416.49
    3756     430 3804.84     416  3921.5   416.3 3954.56     426 4085.74     416
  4204.4     428 4990.42  431.55 5019.67     406    5080   402.1 5255.59     432
 5984.58  428.52  6001.4     420 6241.36     434 6392.41     430 6418.87     420
  6478.8     430 6711.57     422 8354.55     422 8534.31     430 8618.13     448
#Mann= 4 ,-1,0
       0    .085       0 3311.17     .12       0 4990.42    .055       0
 5255.59    .075       0
#XS Ineff= 4 ,-1
       0     690   441.5    7714    8580   441.5    5645    7714     430
    1301    4782     430
Permanent Ineff=
       T       F       F       F
#Block Obstruct= 1 ,-1
    3378    3953     424
Bank Sta=4990.42,5255.59
XS Rating Curve= 0 ,0
Exp/Cntr=0.3,0.1

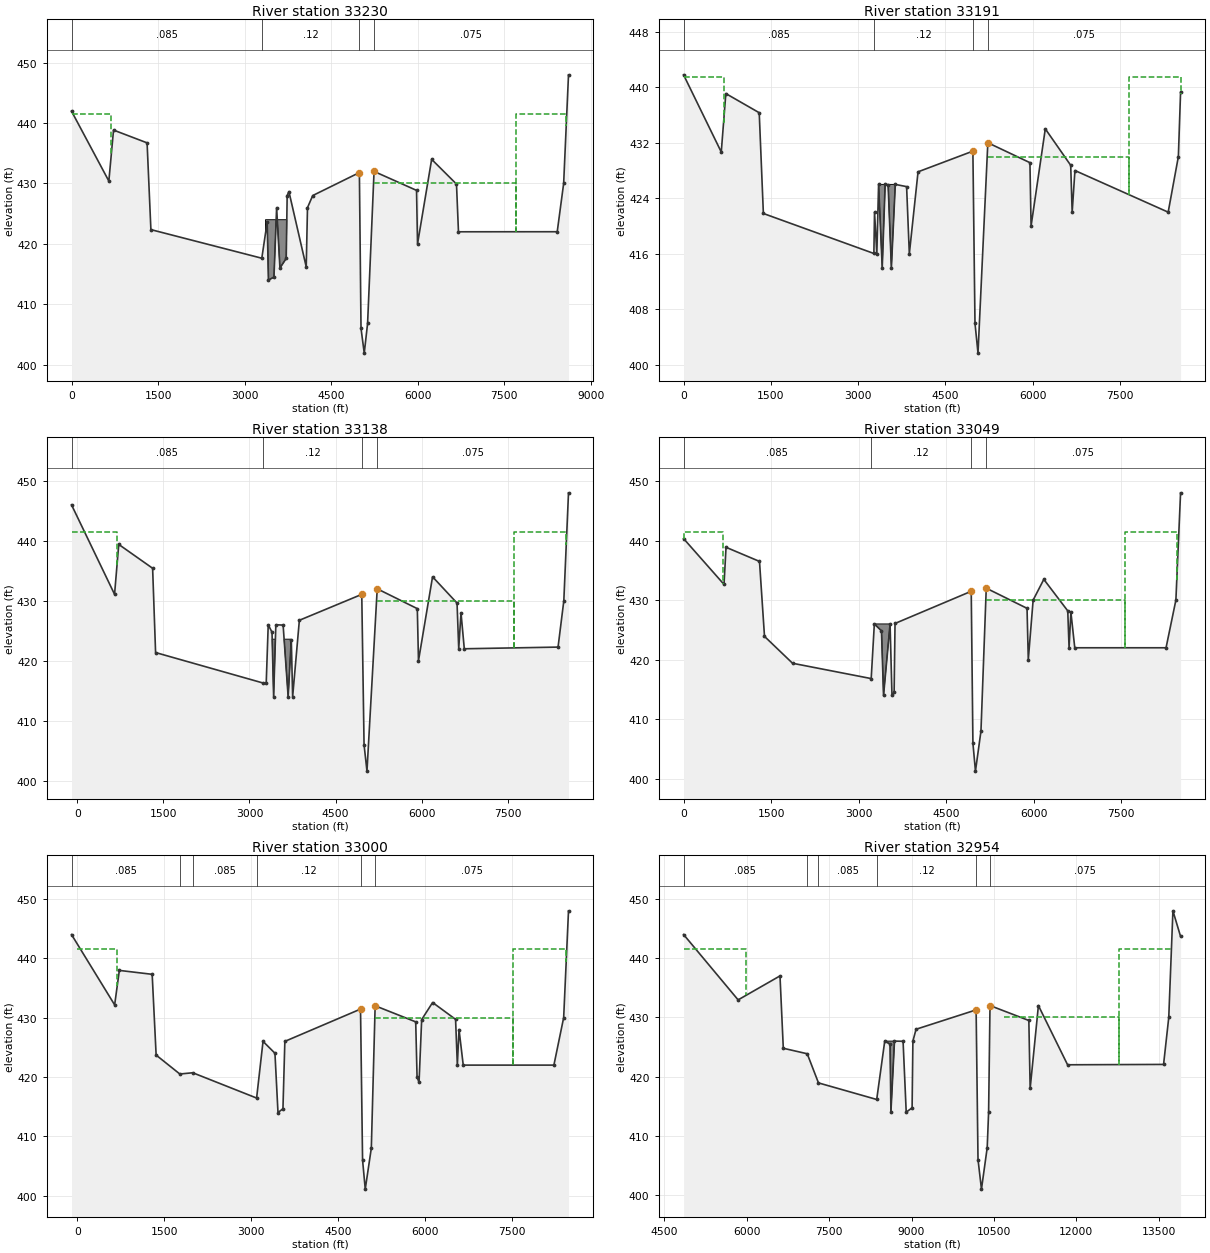
Type RM Length L Ch R = 1 ,33230   ,76,39,24
BEGIN DESCRIPTION:
This cross section corresponds to cross section 33220 of the non-georeferenced CDC model which was the source of this model.
END DESCRIPTION:
XS GIS Cut Line= 6
  2438532.237143 6971926.2183062 2438601.6815588 6969031.2532956
 2438801.3343747 6967542.5377691 2439387.2718511 6966661.4614472
 2440174.6144365 6964094.3209122 2440326.7896571 6963622.5708715
#Sta/Elev= 30
       0  441.98  647.03   430.4   728.1  438.85  1309.7  436.73 1375.63  422.36
 3297.73  417.62 3390.82  423.64 3412.93     414 3508.32  414.49 3554.53     426
 3611.89     416 3720.65  417.58 3737.11     428 3767.38  428.66 4067.54  416.19
 4089.48     426 4179.87     428 4988.64  431.81 5016.95     406    5073   401.9
 5130.83  406.81 5242.89     432 5979.18  428.86 5996.39     420 6241.17     434
 6671.55   429.9 6705.82     422 8417.35  422.01 8528.57     430 8612.74     448
#Mann= 4 ,-1,0
       0    .085       0 3297.73     .12       0 4988.64    .055       0
 5242.89    .075       0
#XS Ineff= 4 ,-1
       0     687   441.5    7705    8573   441.5    5243    7705     430
    1320    4853     430
Permanent Ineff=
       T       F       F       F
#Block Obstruct= 1 ,-1
    3362    3737     424
Bank Sta=4988.64,5242.89
XS Rating Curve= 0 ,0
Exp/Cntr=0.3,0.1

Type RM Length L Ch R = 1 ,33191   ,121,53,26
BEGIN DESCRIPTION:
This cross section corresponds to cross section 33188 of the non-georeferenced CDC model which was the source of this model.
END DESCRIPTION:
XS GIS Cut Line= 6
  2438555.120956 6971901.7967671 2438606.0217732 6970289.9338491
 2438627.7231733 6969083.3365247 2438857.7581463 6967542.5377691
 2439413.3134657 6966670.1422042  2440331.151525 6963676.4437952
#Sta/Elev= 30
       0  441.78  647.84  430.66  726.52  439.08 1300.35  436.32 1371.67  421.81
  3271.2  416.05 3282.27     422 3321.97  416.01 3352.08     426 3414.85     414
 3465.11     426 3516.09  425.95    3572     414 3639.22     426 3833.73  425.68
 3880.52     416 4030.41  427.81 4973.02  430.79 5009.14     406    5061   401.7
 5230.03     432 5953.65  429.13 5973.27     420 6217.76     434 6654.42  428.75
 6679.69     422 6727.25     428 8329.99     422 8504.98     430 8542.89  439.24
#Mann= 4 ,-1,0
       0    .085       0  3271.2     .12       0 4973.02    .055       0
 5230.03    .075       0
#XS Ineff= 4 ,-1
       0     687   441.5    7662    8542   441.5    5230    7662     430
    1320    4973     430
Permanent Ineff=
       T       F       F       F
#Block Obstruct= 1 ,-1
    3352    3639     426
Bank Sta=4973.02,5230.03
XS Rating Curve= 0 ,0
Exp/Cntr=0.3,0.1

Type RM Length L Ch R = 1 ,33138   ,221,89,30
BEGIN DESCRIPTION:
This cross section corresponds to cross section 33136 of the non-georeferenced CDC model which was the source of this model.
END DESCRIPTION:
XS GIS Cut Line= 6
2438590.401157336972015.51364757 2438673.4770188 6969220.4169592
 2438767.2271594 6968512.0837302 2438941.7061412 6967577.1876342
 2439436.4978025 6966676.1461292 2440386.2980683 6963652.2870194
#Sta/Elev= 30
    -100     446  649.96  431.08  722.97   439.4 1313.22  435.42 1364.85  421.37
 3241.53  416.28 3292.24  416.23 3327.43     426 3393.52  424.76 3421.65     414
 3460.22     426 3586.96  425.95 3674.75     414  3729.4  423.52 3752.83     414
  3869.9  426.75 4957.16  431.07 4997.22     406    5048   401.6 5226.59     432
 5924.98  428.69  5945.4     420 6190.62     434  6617.3  429.62 6646.77     422
 6686.18     428  6743.7     422 8377.38  422.28 8477.76     430 8559.47     448
#Mann= 4 ,-1,0
    -100    .085       0 3241.53     .12       0 4957.16    .055       0
 5226.59    .075       0
#XS Ineff= 4 ,-1
    -100     693   441.5    7618    8520   441.5    5227    7618     430
    1300    4815     430
Permanent Ineff=
       T       F       F       F
#Block Obstruct= 1 ,-1
    3327    3717   423.6
Bank Sta=4957.16,5226.59
XS Rating Curve= 0 ,0
Exp/Cntr=0.3,0.1

Type RM Length L Ch R = 1 ,33049   ,196,49,21
BEGIN DESCRIPTION:
This cross section corresponds to cross section 33062 of the non-georeferenced CDC model which was the source of this model.
END DESCRIPTION:
XS GIS Cut Line= 6
  2438646.363556 6971916.2839428 2438699.5186334 6970095.4168496
 2438748.9978652 6969314.1670998 2439051.0812505 6967600.6252513
 2439478.1643858 6966699.5837463 2440390.0313285  6963658.915287
#Sta/Elev= 30
       0  440.32  693.06  432.63  727.78  438.86 1301.06  436.49 1386.77  423.91
 1867.57   419.4 3215.26  416.83 3269.16     426 3391.74  424.83 3426.82     414
 3538.61  425.96 3571.63     414  3608.2  414.51 3623.64  426.08 4929.56  431.48
 4958.48     406    5002   401.3 5096.21     408 5187.05     432 5885.88  428.62
 5907.44     420 5990.47     430 6173.44  433.48 6583.87  428.19 6606.15     422
 6637.21     428 6703.77     422  8268.2     422 8436.84     430 8516.96     448
#Mann= 4 ,-1,0
       0    .085       0 3215.26     .12       0 4929.56    .055       0
 5187.05    .075       0
#XS Ineff= 4 ,-1
       0     683   441.5    7559    8450   441.5    5187    7559     430
    1300    4929     430
Permanent Ineff=
       T       F       F       F
#Block Obstruct= 1 ,-1
    3269 3533.41     426
Bank Sta=4929.56,5187.05
XS Rating Curve= 0 ,0
Exp/Cntr=0.3,0.1

Type RM Length L Ch R = 1 ,33000   ,58,45,23
BEGIN DESCRIPTION:
This cross section corresponds to cross section 33014 of the non-georeferenced CDC model which was the source of this model.
END DESCRIPTION:
XS GIS Cut Line= 6
2438846.289304856972015.82448962 2438840.1436802 6969725.6252664
 2439012.0186646 6968353.2293892  2439178.685326 6967561.5626654
  2439501.602003 6966702.1877437 2440395.8311857 6963661.4536677
#Sta/Elev= 30
    -100     444  643.82  432.15  724.93  437.96 1291.08   437.3 1359.37  423.69
 1768.05   420.5 1991.42  420.71 3092.42  416.45 3203.19     426 3408.66     424
 3461.08     414 3546.68  414.65 3579.51     426 4884.41  431.44 4919.89     406
    4966   401.1 5070.81     408 5136.79     432 5836.33  429.29 5859.65     420
 5893.81  419.08 5939.06  429.67 6127.95  432.55 6523.96  429.71  6554.5     422
 6583.38     428 6656.08     422 8219.81     422 8388.13     430 8471.68     448
#Mann= 6 ,-1,0
    -100    .085       0 1768.05    .065       0 1991.42    .085       0
 3092.42     .12       0 4884.41    .055       0 5136.79    .075       0
#XS Ineff= 4 ,-1
       0     688   441.5    7516    8432   441.5    5137    7516     430
    1300    4884     430
Permanent Ineff=
       T       F       F       F
Bank Sta=4884.41,5136.79
XS Rating Curve= 0 ,0
Exp/Cntr=0.3,0.1

Type RM Length L Ch R = 1 ,32954   ,46,41,52
BEGIN DESCRIPTION:
This cross section corresponds to cross section 32967 of the non-georeferenced CDC model which was the source of this model.
END DESCRIPTION:
XS GIS Cut Line= 6
2438854.218760676972396.93526111 2438900.0395578 6970957.3960968
 2438905.2478808 6969452.1878212 2439173.4770031 6967777.7085586
 2439514.6229743 6966785.5212385 2440441.6494056 6963559.0698902
#Sta/Elev= 30
    4850     444 5842.93  432.96 6605.26  437.01 6665.52  424.79 7101.22  423.86
 7305.64  418.94 8365.91  416.14 8512.22     426 8609.06  425.49 8624.53     414
 8689.68     426    8846  425.97 8903.09     414  9010.2  414.73 9024.68     426
 9082.24     42810175.69  431.2710210.15     406   10273     40110377.47     408
10403.06     41410428.55     43211135.59  429.48 11159.4     41811309.65     432
11840.67     42213588.32  422.0613682.71     43013758.38     44813897.58  443.68
#Mann= 6 ,-1,0
    4850    .085       0 7101.22    .065       0 7305.64    .085       0
 8365.91     .12       010175.69    .055       010428.55    .075       0
#XS Ineff= 4 ,-1
    4850    5983   441.5   12779   13731   441.5    6610    9837     430
   10683   12779     430
Permanent Ineff=
       T       F       F       F
#Block Obstruct= 1 ,-1
    8512    8689     426
Bank Sta=10175.69,10428.55
XS Rating Curve= 0 ,0
Exp/Cntr=0.3,0.1