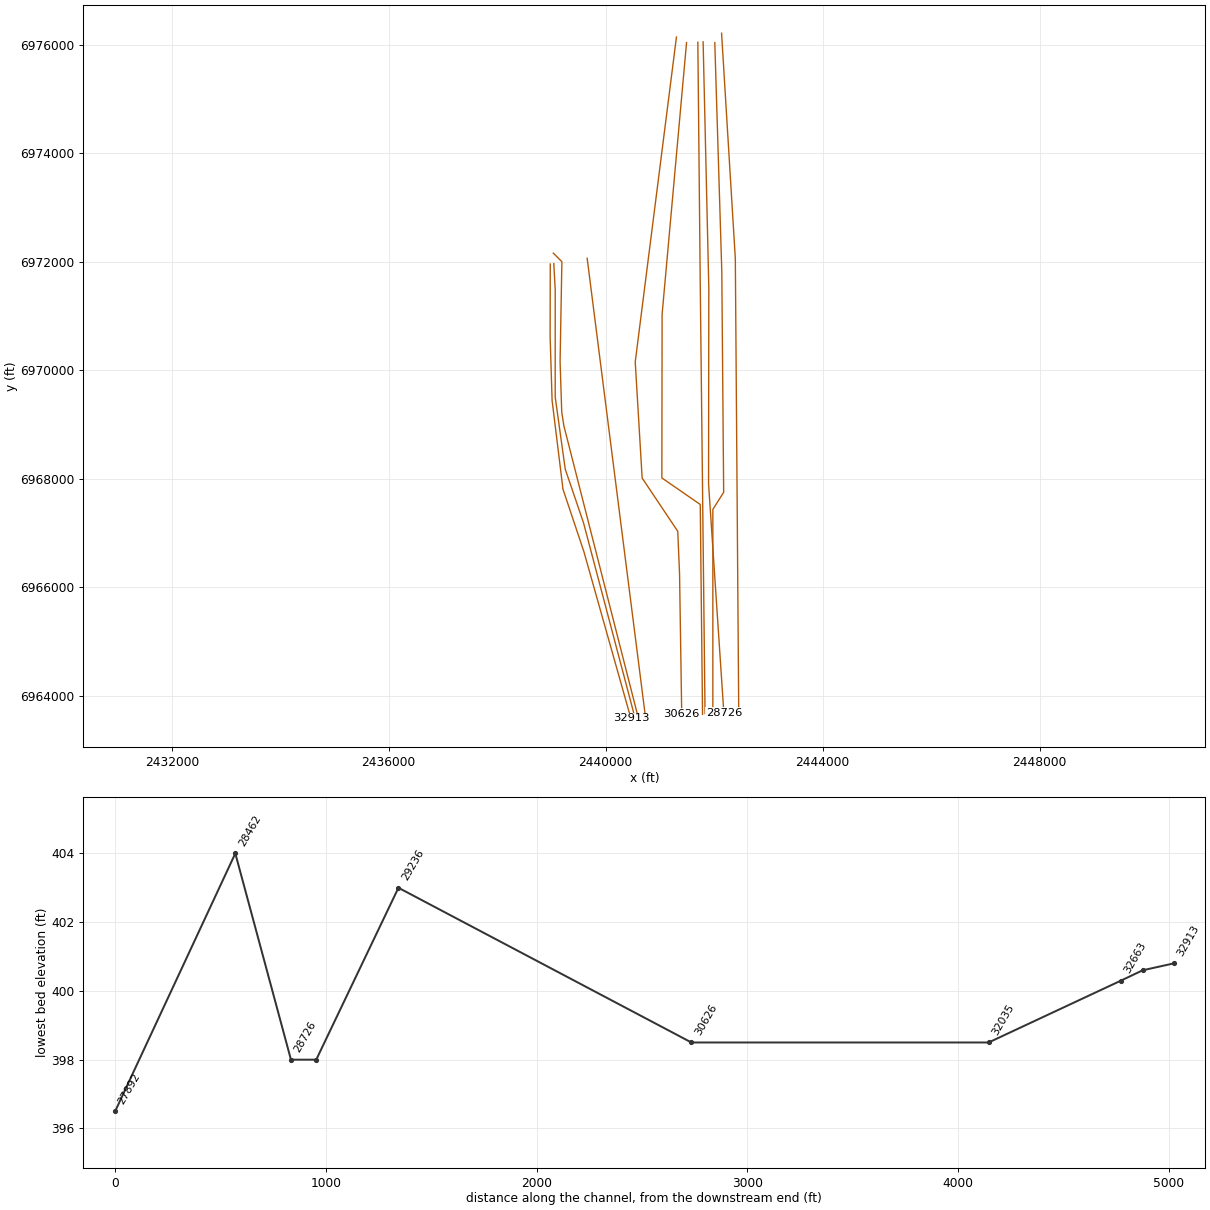
HEC-RAS study CDC_Consolidated_Model.prj: Upper Trinity CDC Consolidated Model

--- CDC_Consolidated_Model.g01 (geometry) --- (continued)

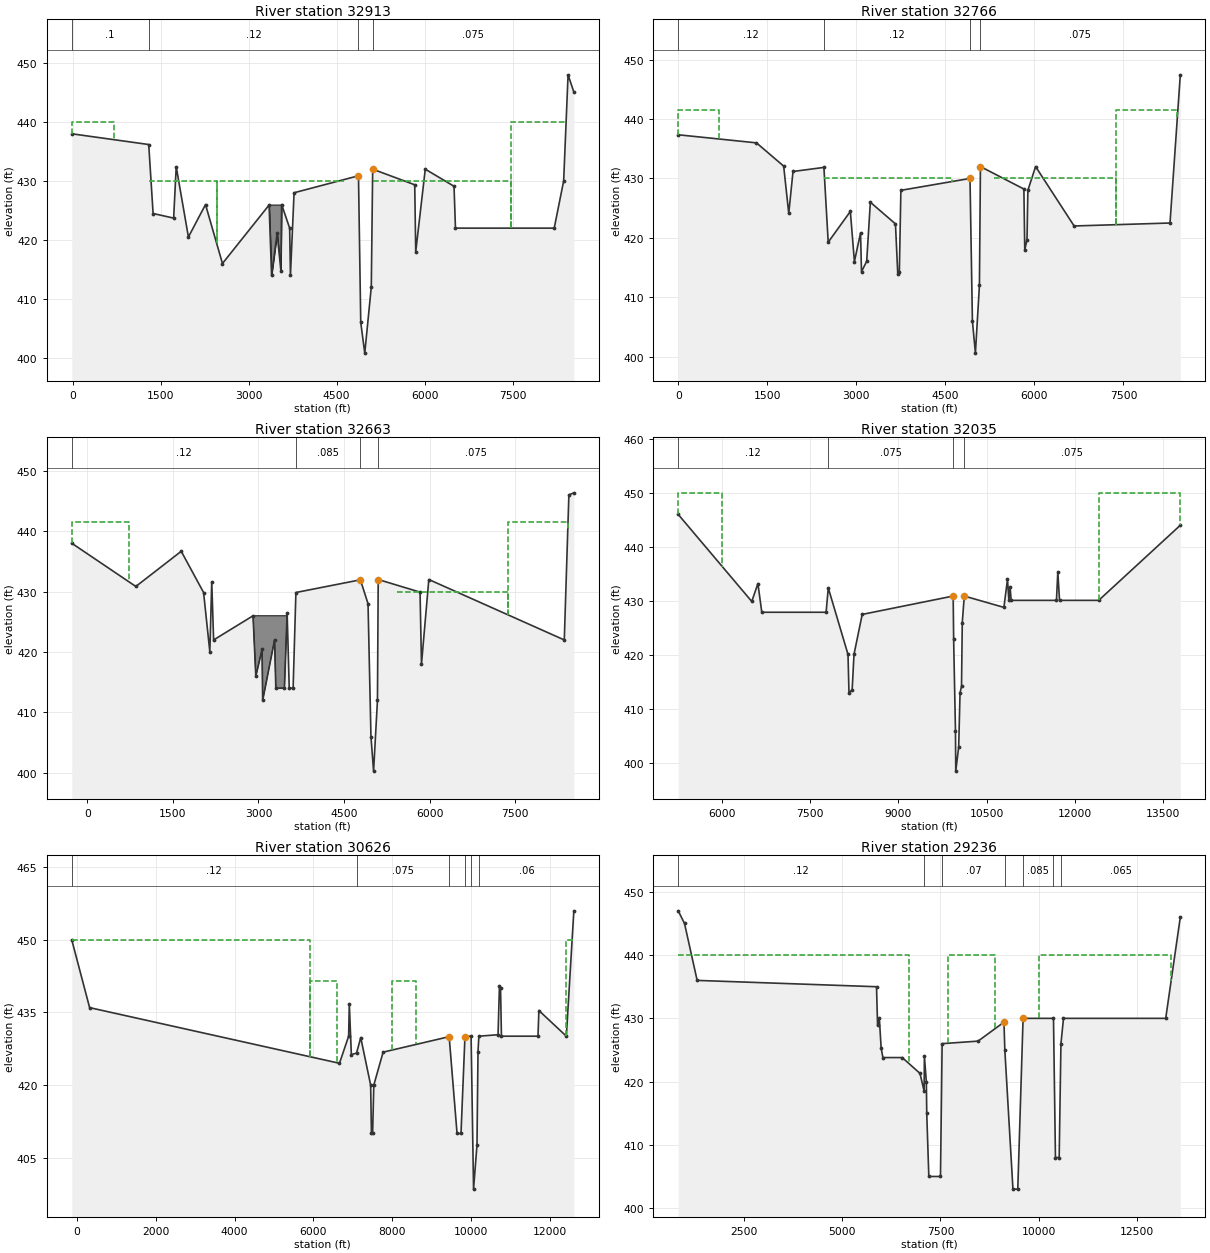
Type RM Length L Ch R = 1 ,32913   ,134,147,196
BEGIN DESCRIPTION:
This cross section corresponds to cross section 32919 of the non-georeferenced CDC model which was the source of this model.
END DESCRIPTION:
XS GIS Cut Line= 6
  2438978.164401 6971954.7920679 2438975.5604042 6970621.4584485
 2439012.0186646 6969439.1668498  2439212.539589 6967803.7501732
  2439597.956141  6966652.708512 2440465.1437111 6963577.1877601
#Sta/Elev= 30
     -19     438 1293.82  436.18 1368.63  424.48 1718.98   423.7 1762.99  432.41
 1971.06  420.49 2262.61     426 2551.66     416 3347.44  425.92 3389.73     414
 3484.52  421.11 3548.44   414.8 3561.24     426 3698.19     422  3711.7     414
 3773.53     428 4872.32  430.88 4911.08     406  4979.5   400.8 5090.91     412
 5114.63     432 5831.98  429.35 5849.12     418 6011.78     432 6502.42   429.1
 6526.95     422 8211.74     422 8372.67     430 8448.03     448 8546.57  445.08
#Mann= 4 ,-1,0
     -19      .1       0 1293.82     .12       0 4872.32    .055       0
 5114.63    .075       0
#XS Ineff= 5 ,-1
     -19     693     440    7482    8415     440    5114    7482     430
    2453    4633     430    1300    2453     430
Permanent Ineff=
       T       F       F       F       T
#Block Obstruct= 1 ,-1
    3347    3561     426
Bank Sta=4872.32,5114.63
XS Rating Curve= 0 ,0
Exp/Cntr=0.3,0.1

Type RM Length L Ch R = 1 ,32766   ,176,103,118
BEGIN DESCRIPTION:
This cross section corresponds to cross section 32814 of the non-georeferenced CDC model which was the source of this model.
END DESCRIPTION:
XS GIS Cut Line= 6
  2439043.268602 6971962.6043882 2439069.3102167 6971483.4380237
 2439069.3102167 6969501.6670529 2439254.2061723 6968173.5420845
 2439592.7478181 6967178.7504389 2440522.4352632 6963657.9169294
#Sta/Elev= 30
       0  437.35 1317.69  435.99 1776.04  432.08 1861.67  424.11 1933.43  431.17
 2453.98  431.86 2526.28  419.27 2899.42  424.45 2967.76     416 3070.86  420.84
 3087.14   414.3 3174.71  416.07 3236.11     426 3659.15  422.35 3697.63     414
  3724.3  414.18 3750.49     428 4914.83     430 4955.55     406 5005.95   400.6
 5073.61     412 5090.65     432 5822.57  428.22 5837.23     418 5874.99  419.67
 5889.75     428 6019.54     432 6668.99     422 8283.91   422.5 8457.54  447.44
#Mann= 4 ,-1,0
       0     .12       0 2453.98     .12       0 4914.83    .055       0
 5090.65    .075       0
#XS Ineff= 5 ,-1
       0     692   441.5    7377    8408   441.5    1300 2453.98  431.86
 2453.98    4614     430    5322    7377     430
Permanent Ineff=
       T       F       T       F       F
Bank Sta=4914.83,5090.65
XS Rating Curve= 0 ,0
Exp/Cntr=0.3,0.1

Type RM Length L Ch R = 1 ,32663   ,776,628,455
BEGIN DESCRIPTION:
This cross section corresponds to cross section 32718 of the non-georeferenced CDC model which was the source of this model.
END DESCRIPTION:
XS GIS Cut Line= 6
    2439034.3969 6972156.0987519 2439192.3162043 6971998.1794483
 2439159.3300498 6970154.1401574 2439189.7122068 6969225.3204927
 2439228.7744647 6968973.5844477 2440599.9662761 6963593.9702069
#Sta/Elev= 30
    -274     438  849.46  430.85 1645.33  436.67  2037.3  429.85  2146.9  420.04
 2180.41  431.63 2213.04     422  2904.5     426 2953.14     416 3062.87  420.43
 3073.18     412 3282.16     422 3304.16     414  3454.8  414.03 3502.41  426.43
 3539.08     414 3607.21  414.05 3656.02  429.85 4786.47  431.95 4920.76     428
 4972.12     406    5018   400.3  5086.1     412 5099.32     432 5832.82  429.91
  5857.9     418 5986.64     432 8361.98     422 8442.62     446 8529.56  446.34
#Mann= 4 ,-1,0
    -274     .12       0 3656.02    .085       0 4786.47    .055       0
 5099.32    .075       0
#XS Ineff= 4 ,-1
    7383    8423   441.5    -274     725   441.5    1874    4500     430
    5432    7383     430
Permanent Ineff=
       F       F       F       F
#Block Obstruct= 1 ,-1
    2904    3503     426
Bank Sta=4786.47,5099.32
XS Rating Curve= 0 ,0
Exp/Cntr=0.3,0.1

Type RM Length L Ch R = 1 ,32035   ,3250,1410,783
BEGIN DESCRIPTION:
This cross section corresponds to cross section 32042 of the non-georeferenced CDC model which was the source of this model.
END DESCRIPTION:
XS GIS Cut Line= 6
2439658.527059786972060.99871692  2439811.975398 6970853.4684832
 2439938.8406298 6969855.1692987 2440154.5275344 6968158.0621286
  2440344.856222 6966660.61630462440736.978060516963575.76508745
#Sta/Elev= 30
    5250     446    6502   429.9    6607   433.2    6673   427.9    7768   427.9
    7805   432.4    8141   420.1    8158   412.9    8212   413.6    8243   420.1
    8383   427.5    9932   430.9    9940   422.9    9971     406    9976   398.5
   10026     403   10049     413   10074   414.2   10087     426   10121   430.9
   10796   428.8   10857     434   10881   430.1   10902   432.5   10919   430.1
   11691   430.1   11714   435.4   11743   430.1   12410   430.1   13800     444
#Mann= 4 ,-1,0
    5250     .12       0    7805    .075       0    9932    .055       0
   10121    .075       0
#XS Ineff= 2 , 0
       0    6000     450   12410       0     450
Permanent Ineff=
       F       F
Bank Sta=9932,10121
XS Rating Curve= 0 ,0
Exp/Cntr=0.3,0.1

Type RM Length L Ch R = 1 ,30626   ,881,1390,1762
BEGIN DESCRIPTION:
This cross section corresponds to cross section 31471 of the non-georeferenced CDC model which was the source of this model.
END DESCRIPTION:
XS GIS Cut Line= 6
     2441304.614      6976140.39 2440544.5814227 6970150.1791222
 2440672.5176402 6968008.9325056 2441328.7016952 6967027.2966736
 2441361.8945423  6966244.823501 2441401.8615895 6963659.1547628
#Sta/Elev= 30
    -125     450     327     436    6660   424.5    6892   430.1    6909   436.8
    6961   426.3    7092   426.6    7199   429.8    7450     420    7470     410
    7500     410    7530     420    7766   426.8    9440     430    9640     410
    9740     410    9840     430    9996   430.1   10058   398.5   10145   407.6
   10171   426.9   10193   430.1   10679   430.4   10714   440.4   10742   440.1
   10765   430.1   11691   430.1   11714   435.4   12410   430.1   12600     456
#Mann= 6 ,-1,0
    -125     .12       0    7092    .075       0    9440    .055       0
    9840    .075       0    9996    .055       0   10193     .06       0
#XS Ineff= 4 ,-1
   12410   12600     450    -125    5913     450    5913    6600   441.5
    8000    8600   441.4
Permanent Ineff=
       F       F       F       F
Bank Sta=9440,9840
XS Rating Curve= 0 ,0
Exp/Cntr=0.3,0.1

Type RM Length L Ch R = 1 ,29236   ,390,390,390
BEGIN DESCRIPTION:
This cross section corresponds to cross section 29040 of the non-georeferenced CDC model which was the source of this model.
END DESCRIPTION:
XS GIS Cut Line= 6
     2441490.812     6976037.525 2441040.2742875 6971030.8631456
 2441035.6173077 6968011.3668839 2441427.7700667 6967740.2296309
 2441743.5768497 6967521.8783616 2441785.6132057 6963652.5172093
#Sta/Elev= 30
     817     447     977     445    1299     436    5870     435    5897   428.9
    5941   430.1    5988   425.3    6033   423.8    6525   423.8    6978   421.3
    7083   418.5    7090     424    7140     420    7150     415    7203     405
    7500     405    7542     426    8458   426.4    9118   429.4    9140     425
    9347     403    9470     403    9605     430   10380     430   10430     408
   10525     408   10570     426   10635     430   13240     430   13612     446
#Mann= 7 ,-1,0
     817     .12       0    7090    .055       0    7542     .07       0
    9140    .055       0    9605    .085       0   10380    .055       0
   10570    .065       0
#XS Ineff= 3 ,-1
     817    6700     440    7700    8900     440   10000   13378     440
Permanent Ineff=
       F       F       F
Bank Sta=9118,9605
XS Rating Curve= 0 ,0
Exp/Cntr=0.3,0.1

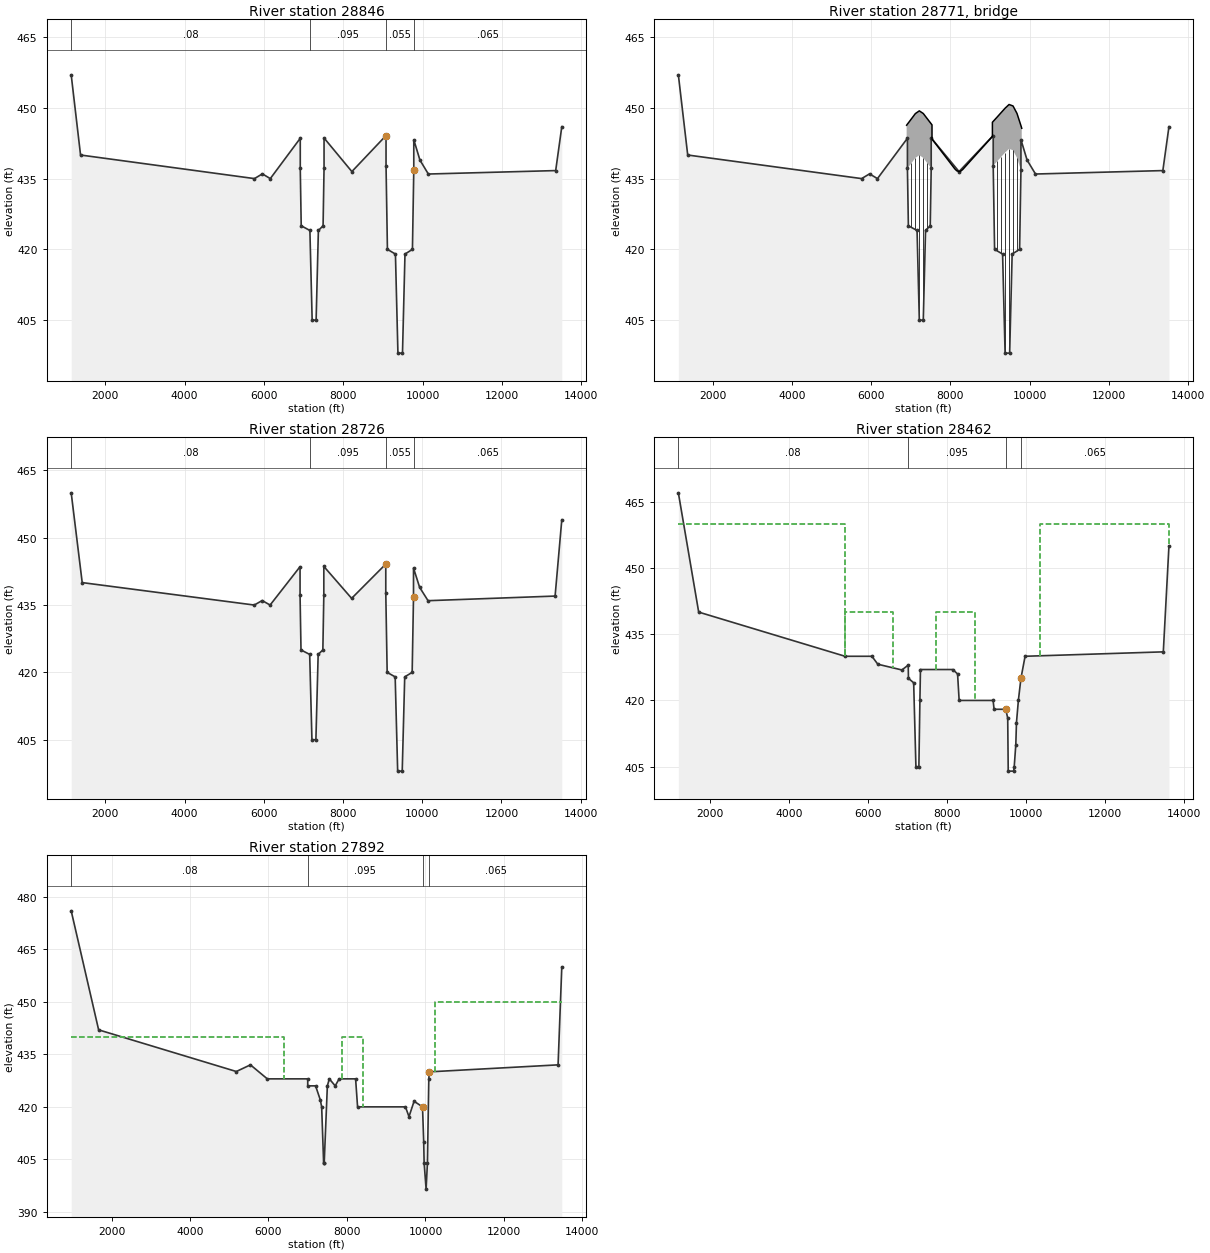
Type RM Length L Ch R = 1 ,28846   ,120,120,120
BEGIN DESCRIPTION:
This cross section corresponds to cross section 28841 of the non-georeferenced CDC model which was the source of this model.
Upstream bounding cross section for Meyers Road/MacArthur Blvd bridge (West Fork Trinity River and Bear Creek bridges modeled).
END DESCRIPTION:
XS GIS Cut Line= 6
     2441699.145      6976044.47  2441744.505981 6971501.2473713
 2441746.2080781 6971348.7640805 2441768.6063272 6969341.9049052
 2441794.3631655 6967034.0181168 2441831.9249294 6963667.7352168
#Sta/Elev= 30
    1137     457    1373     440    5760     435    5960     436    6160     435
    6916  443.55    6916  437.15    6940     425    7159     424    7216     405
    7316     405    7373     424  7491.6     425    7516  437.21    7516  443.61
    8218  436.49    9080  444.13    9080  437.72    9115     420    9317     419
    9380     398    9495     398    9558     419    9746     420    9780  436.83
    9780  443.24    9935  438.93   10147  435.97   13360   436.7   13514     446
#Mann= 4 ,-1,0
    1137     .08       0    7159    .095       0    9080    .055       0
    9780    .065       0
#XS Ineff= 2 , 0
       0    5680           10300       0
Permanent Ineff=
       F       F
Bank Sta=9080,9780
XS Rating Curve= 0 ,0
Exp/Cntr=0.3,0.1

Type RM Length L Ch R = 3 ,28771   ,,,
BEGIN DESCRIPTION:
Meyers Road/MacArthur Boulevard
-----------------------------
CDC DALCO040803-1 Meyers Road
-----------------------------
END DESCRIPTION:
Node Name=Meyers Road
Bridge Culvert--1,0,-1,-1, 0
Deck Dist Width WeirC Skew NumUp NumDn MinLoCord MaxHiCord MaxSubmerge Is_Ogee
1,90,2.6,0, 26, 26, , , 0.95, 0, 0,0,,
    6896    6916    7016    7116    7216    7316    7416    7516    7536    7536
    8110    8160    8218    8260    8310    9060    9060    9080    9180    9280
    9380    9480    9580    9680    9780    9800
  446.32  446.55  447.66  448.78  449.36   448.8   447.7  446.61  446.39  443.39
  437.08  436.66  436.49  436.58  436.92  443.94  446.94  447.13  448.05  448.99
  449.92  450.71   450.4  448.82  446.23  445.67
  437.15  437.15  438.26  439.38  439.96   439.4   438.3  437.21  437.21  443.39
  437.08  436.66  436.49  436.58  436.92  443.94  437.72  437.72  438.65  439.59
  440.52  441.31     441  439.42  436.83  436.83
    6896    6916    7016    7116    7216    7316    7416    7516    7536    7536
    8110    8160    8218    8260    8310    9060    9060    9080    9180    9280
    9380    9480    9580    9680    9780    9800
  446.32  446.55  447.66  448.78  449.36   448.8   447.7  446.61  446.39  443.39
  437.08  436.66  436.49  436.58  436.92  443.94  446.94  447.13  448.05  448.99
  449.92  450.71   450.4  448.82  446.23  445.67
  437.15  437.15  438.26  439.38  439.96   439.4   438.3  437.21  437.21  443.39
  437.08  436.66  436.49  436.58  436.92  443.94  437.72  437.72  438.65  439.59
  440.52  441.31     441  439.42  436.83  436.83
Pier Skew, UpSta & Num, DnSta & Num=  ,7016, 2 ,7016, 2 , 0 , 0 , 0 ,,
       3       3
     400     440
       3       3
     400     440
Pier Skew, UpSta & Num, DnSta & Num=  ,7116, 2 ,7116, 2 , 0 , 0 , 0 ,,
       3       3
     400     440
       3       3
     400     440
Pier Skew, UpSta & Num, DnSta & Num=  ,7216, 2 ,7216, 2 , 0 , 0 , 0 ,,
       4       4
     400     440
       4       4
     400     440
Pier Skew, UpSta & Num, DnSta & Num=  ,7316, 2 ,7316, 2 , 0 , 0 , 0 ,,
       4       4
     400     440
       4       4
     400     440
Pier Skew, UpSta & Num, DnSta & Num=  ,7416, 2 ,7416, 2 , 0 , 0 , 0 ,,
       3       3
     400     440
       3       3
     400     440
Pier Skew, UpSta & Num, DnSta & Num=  ,9180, 2 ,9180, 2 , 0 , 0 , 0 ,,
       3       3
     390     445
       3       3
     390     445
Pier Skew, UpSta & Num, DnSta & Num=  ,9280, 2 ,9280, 2 , 0 , 0 , 0 ,,
       3       3
     390     445
       3       3
     390     445
Pier Skew, UpSta & Num, DnSta & Num=  ,9380, 2 ,9380, 2 , 0 , 0 , 0 ,,
       4       4
     390     445
       4       4
     390     445
Pier Skew, UpSta & Num, DnSta & Num=  ,9480, 2 ,9480, 2 , 0 , 0 , 0 ,,
       4       4
     390     445
       4       4
     390     445
Pier Skew, UpSta & Num, DnSta & Num=  ,9580, 2 ,9580, 2 , 0 , 0 , 0 ,,
       3       3
     390     445
       3       3
     390     445
Pier Skew, UpSta & Num, DnSta & Num=  ,9680, 2 ,9680, 2 , 0 , 0 , 0 ,,
       3       3
     390     445
       3       3
     390     445
BR Coef=-1 , 0 , 0 ,, 0 ,,,0.8,-1,,1,
WSPro=,,,, 1 ,,,, 0 ,,,, 0 ,,,,-1 ,-1 ,-1 , 0 , 0 , 0 , 0 , 0
BR Coef=-1 , 0 , 0 ,, 0 ,,,0.8,-1,,1,
WSPro=,,,, 1 ,,,, 0 ,,,, 0 ,,,,-1 ,-1 ,-1 , 0 , 0 , 0 , 0 , 0
BR Coef=-1 , 0 , 0 ,, 0 ,,,0.8,-1,,1,
WSPro=,,,, 1 ,,,, 0 ,,,, 0 ,,,,-1 ,-1 ,-1 , 0 , 0 , 0 , 0 , 0
BR Coef=-1 , 0 , 0 ,, 0 ,,,0.8,-1,,1,
WSPro=,,,, 1 ,,,, 0 ,,,, 0 ,,,,-1 ,-1 ,-1 , 0 , 0 , 0 , 0 , 0
BC Design=,, 0 ,, 0 ,,,,,,
BC HTab HWMax=444.13
BC Use User HTab Curves=0
BC User HTab FreeFlow(D)= 0

Type RM Length L Ch R = 1 ,28726   ,265,264,80
BEGIN DESCRIPTION:
This cross section corresponds to cross section 28749 of the non-georeferenced CDC model which was the source of this model.
Downstream bounding cross section for Meyers Road/MacArthur Blvd bridge (West Fork Trinity River and Bear Creek bridges modeled).
END DESCRIPTION:
XS GIS Cut Line= 6
     2441796.368     6976051.414  2441901.458751 6971510.9005672
 2441899.2107248 6969683.3090781 2441897.0138788 6967899.9330517
  2441963.557709 6966902.5570937 2442178.6922069 6963677.6408459
#Sta/Elev= 30
    1139     460    1417     440    5760     435    5960     436    6160     435
    6916  443.55    6916  437.15    6940     425    7159     424    7216     405
    7316     405    7373     424  7491.6     425    7516  437.21    7516  443.61
    8218  436.49    9080  444.13    9080  437.72    9115     420    9317     419
    9380     398    9495     398    9558     419    9746     420    9780  436.83
    9780  443.24    9935  438.93   10147  435.97   13354     437   13523     454
#Mann= 4 ,-1,0
    1139     .08       0    7159    .095       0    9080    .055       0
    9780    .065       0
#XS Ineff= 2 , 0
       0    5680           10300       0
Permanent Ineff=
       F       F
Bank Sta=9080,9780
XS Rating Curve= 0 ,0
Exp/Cntr=0.3,0.1

Type RM Length L Ch R = 1 ,28462   ,442,570,241
BEGIN DESCRIPTION:
This cross section corresponds to cross section 28450 of the non-georeferenced CDC model which was the source of this model.
END DESCRIPTION:
XS GIS Cut Line= 6
     2442011.645     6976037.525  2442140.807833 6971816.5667829
 2442159.2472782 6969630.3101683 2442175.1340575 6967746.4979911
 2441975.8631306 6967431.0950786 2441975.8631306 6963672.2279581
#Sta/Elev= 30
    1198     467    1713     440    5420     430    6100     430    6250   428.2
    6860   426.9    7020     428    7026     425    7158     424    7215     405
    7290     405    7316     420    7330     427    8150     427    8270     426
    8310     420    9170     420    9195     418    9490     418    9540     416
    9553     404    9690     404    9705     405    9745     410    9762     415
    9810     420    9875     425    9980     430   13481     431   13624     455
#Mann= 4 ,-1,0
    1198     .08       0    7020    .095       0    9490    .055       0
    9875    .065       0
#XS Ineff= 4 ,-1
    5420    6640     440    7720    8700     440    1198    5420     460
   10360   13624     460
Permanent Ineff=
       F       F       F       F
Bank Sta=9490,9875
XS Rating Curve= 0 ,0
Exp/Cntr=0.3,0.1

Type RM Length L Ch R = 1 ,27892   ,302,2464,1208
BEGIN DESCRIPTION:
This cross section corresponds to cross section 27882 of the non-georeferenced CDC model which was the source of this model.
END DESCRIPTION:
XS GIS Cut Line= 6
     2442136.645     6976211.137  2442390.208591 6972055.5217222
 2442403.7139809 6970257.8112099 2442415.6841013 6968664.2914311
 2442420.1726094  6968066.721432 2442452.6118165 6963747.6683451
#Sta/Elev= 30
     973     476    1672     442    5180   430.1    5540     432    5970     428
    7000     428    7000     426    7200     426    7320     422    7355     420
    7405     404    7420     404    7500     426    7550     428    7700     426
    7800     428    8220     428    8270     420    9490     420    9580   417.2
    9710   421.6    9925     420    9955     410    9966     404   10016   396.5
   10050     404   10085     428   10099     430   13379     432 13473.6     460
#Mann= 4 ,-1,0
     973     .08       0    7000    .095       0    9925    .055       0
   10099    .065       0
#XS Ineff= 3 ,-1
   10250 13473.6     450    7870    8400     440     973    6400     440
Permanent Ineff=
       F       F       F
Bank Sta=9925,10099
XS Rating Curve= 0 ,0
Exp/Cntr=0.3,0.1