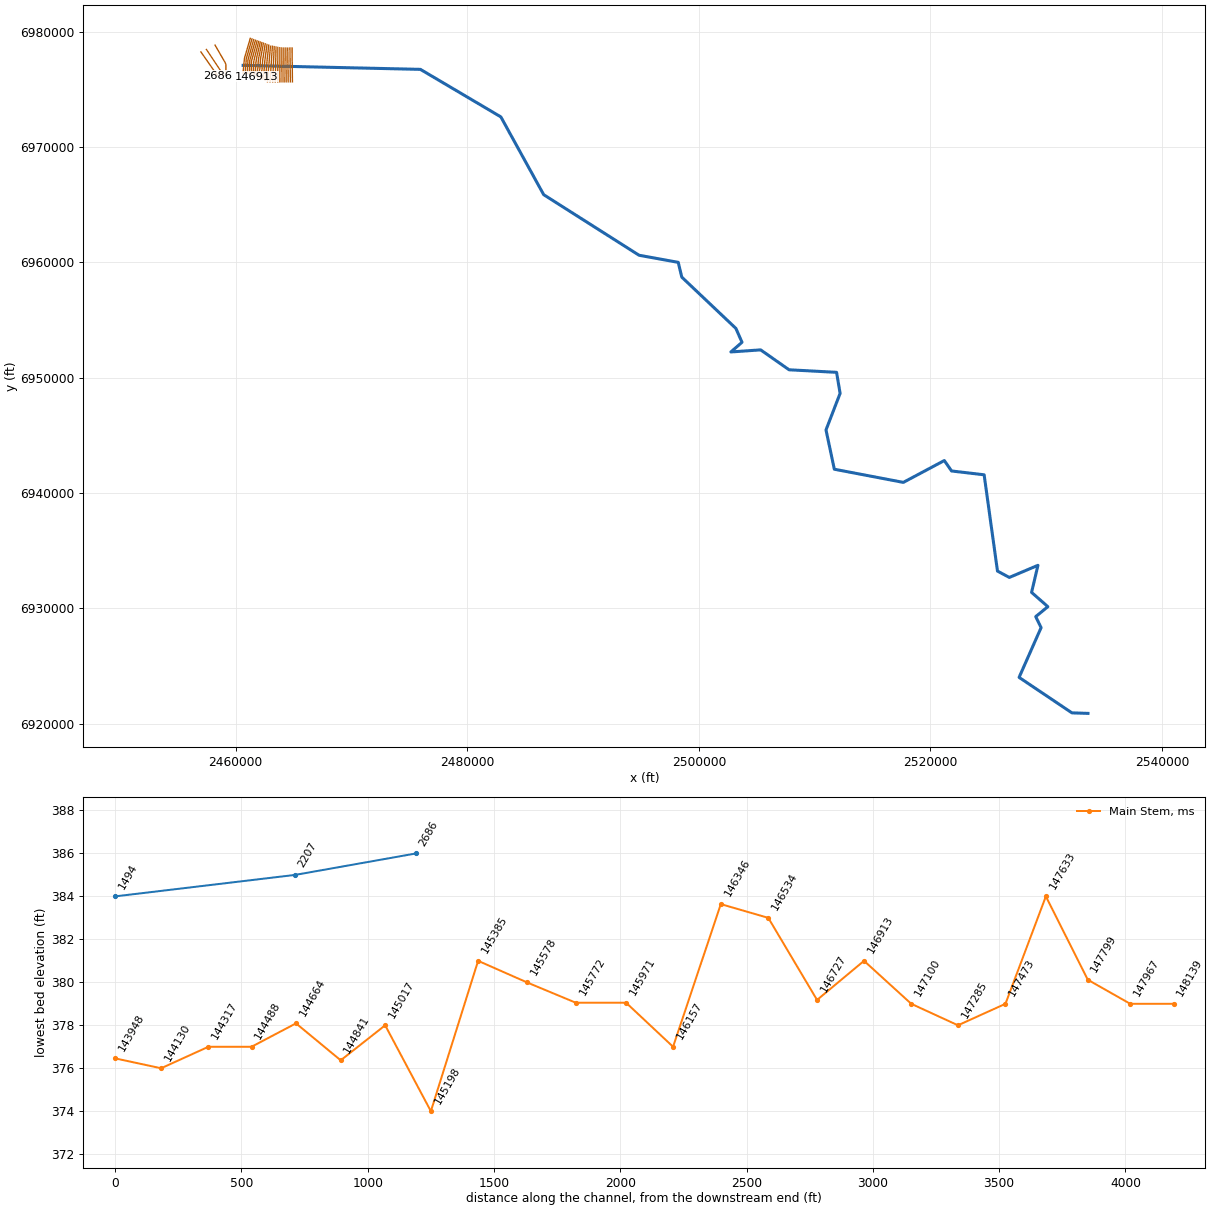
HEC-RAS study CDC_Consolidated_Model.prj: Upper Trinity CDC Consolidated Model

--- CDC_Consolidated_Model.g01 (geometry) --- (continued)

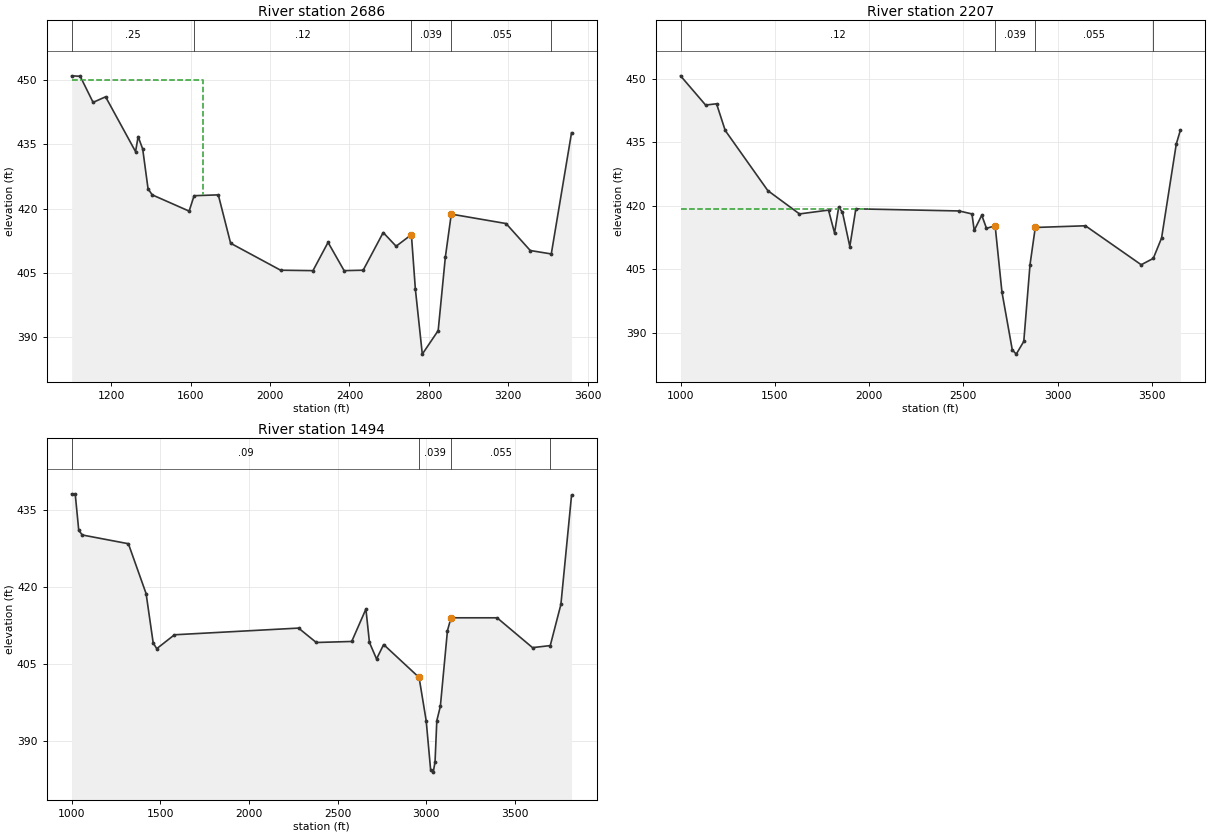
Type RM Length L Ch R = 1 ,2686    ,480,479,480
BEGIN DESCRIPTION:
This cross section corresponds to cross section 2687 of the non-georeferenced CDC model which was the source of this model.
Cross-section WF002.  McPeeter's property in LOB.  Effective flow limit set at West Levee in ROB.  Conveyance removed from pond in LOB below elev. 414.4.
Channel data from 1975 USACOE field survey.
END DESCRIPTION:
XS GIS Cut Line= 6
  2456998.734003 6978241.2548887 2457373.5990673 6977703.7891001
 2457587.8128777 6977396.6676671 2457748.4759423 6977166.3279047
 2458069.8092891 6976705.6500202 2458444.7091298 6976168.1970269
#Sta/Elev= 30
    1000     451    1043   450.9    1108   444.8    1171   446.1    1322   433.3
    1335   436.8    1358   433.9    1385   424.6    1406   423.2    1592   419.4
    1617     423    1739   423.2    1801   411.9    2053   405.6    2216   405.5
    2292   412.1    2373   405.5    2469   405.6    2570   414.4    2635   411.2
    2712   413.9    2732   401.2    2767     386    2847   391.5    2883   408.6
    2913   418.7    3189   416.5    3311   410.2    3417   409.4    3519   437.7
#Mann= 5 ,-1,0
    1000     .25       0    1617     .12       0    2712    .039       0
    2913    .055       0    3417     .03       0
#XS Ineff= 4 ,-1
    2913    3519     415    1663    2570   414.4    2570    2712   413.9
    1000    1663     450
Permanent Ineff=
       F       T       F       F
Bank Sta=2712,2913
XS Rating Curve= 0 ,0
Exp/Cntr=0.5,0.3

Type RM Length L Ch R = 1 ,2207    ,849,713,499
BEGIN DESCRIPTION:
This cross section corresponds to cross section 2208 of the non-georeferenced CDC model which was the source of this model.
Cross-section WF001.  Effective flow limit set at West Levee in ROB. McPeeter's property in LOB.  Conveyance removed from pond in LOB below elev. 419.3.
Channel data from 1975 USACOE field survey.
END DESCRIPTION:
XS GIS Cut Line= 6
  2457478.800956 6978447.4578883 2457847.0571099 6977893.3622117
 2458215.3257303 6977339.2708002  2458373.158748 6977101.8044117
 2458583.6064898 6976785.1839819 2458951.9000446 6976231.1011006
#Sta/Elev= 30
    1000   450.7    1133   443.8    1191   444.1    1237   437.8    1463   423.6
    1631   418.1    1785     419    1817   413.6    1839   419.7    1859   418.5
    1898   410.4    1930   419.3    2478   418.8    2546   418.1    2558   414.2
    2598   417.8    2623   414.7    2669   415.3    2705   399.7    2760     386
    2781     385    2821     388    2854   406.1    2882   414.9    3148   415.3
    3444   406.1    3508   407.6    3552   412.4    3630   434.6    3652   437.9
#Mann= 4 ,-1,0
    1000     .12       0    2669    .039       0    2882    .055       0
    3508     .03       0
#XS Ineff= 3 ,-1
    1000    2000   419.3    2000    2669   415.3    2882    3652   414.9
Permanent Ineff=
       T       F       F
Bank Sta=2669,2882
XS Rating Curve= 0 ,0
Exp/Cntr=0.5,0.3

Type RM Length L Ch R = 1 ,1494    ,0,0,0
BEGIN DESCRIPTION:
This cross section corresponds to cross section 1494 of the non-georeferenced CDC model which was the source of this model.
Cross-section from topographic file.  1494 feet upstream of the West Fork/Elm Fork confluence.  McPeeter's property in LOB.  Effective flow limit set at West Levee in ROB.
Channel data from 1975 USACOE field survey.
END DESCRIPTION:
XS GIS Cut Line= 6
  2458223.312919 6978824.4259664 2458635.0010721 6978109.9168967
 2459046.7069416 6977395.4130764 2459133.1421362 6977230.1118978
 2459164.8340019 6977120.8440717 2459164.8340019 6976250.4111013
#Sta/Elev= 30
    1000   438.1    1020   438.1    1040     431    1060   430.1    1320   428.4
    1420   418.7    1460   409.1    1480     408    1580   410.7    2280     412
    2380   409.2    2580   409.4    2660   415.7    2680   409.2    2720     406
    2760   408.8    2960   402.4    3000     394    3025   384.5    3040     384
    3050     386    3060     394    3080   396.8    3120   411.5    3140     414
    3400     414    3600   408.2    3700   408.6    3760   416.6    3820   437.8
#Mann= 4 ,-1,0
    1000     .09       0    2960    .039       0    3140    .055       0
    3700     .03       0
#XS Ineff= 2 , 0
                            3140             414
Permanent Ineff=
       F       F
Bank Sta=2960,3140
XS Rating Curve= 0 ,0
Exp/Cntr=0.5,0.3

River Reach=Main Stem       ,ms
Reach XY= 30
       2460651.9      6977070.51      2475956.02        6976723.
      2482902.21      6972603.81      2486601.03      6965861.25
      2494841.05      6960609.03      2498218.33      6959996.81
      2498526.81      6958713.48      2503198.36      6954269.99
      2503727.53      6953066.56      2502765.36      6952229.44
      2505335.43      6952409.66      2507789.67       6950684.6
      2511891.32      6950462.85      2512197.38      6948638.96
      2510979.79      6945468.76      2511698.66      6942064.93
      2517657.38      6940924.33      2521195.08      6942816.26
      2521824.01      6941912.62      2524634.19      6941582.52
      2525786.79      6933236.59      2526809.67      6932685.92
       2529281.6      6933737.03      2528731.26      6931389.82
      2530135.73      6930151.29      2529089.21      6929289.76
      2529552.65      6928333.05      2527652.49        6924023.
       2532218.2      6920945.83      2533600.64      6920903.28

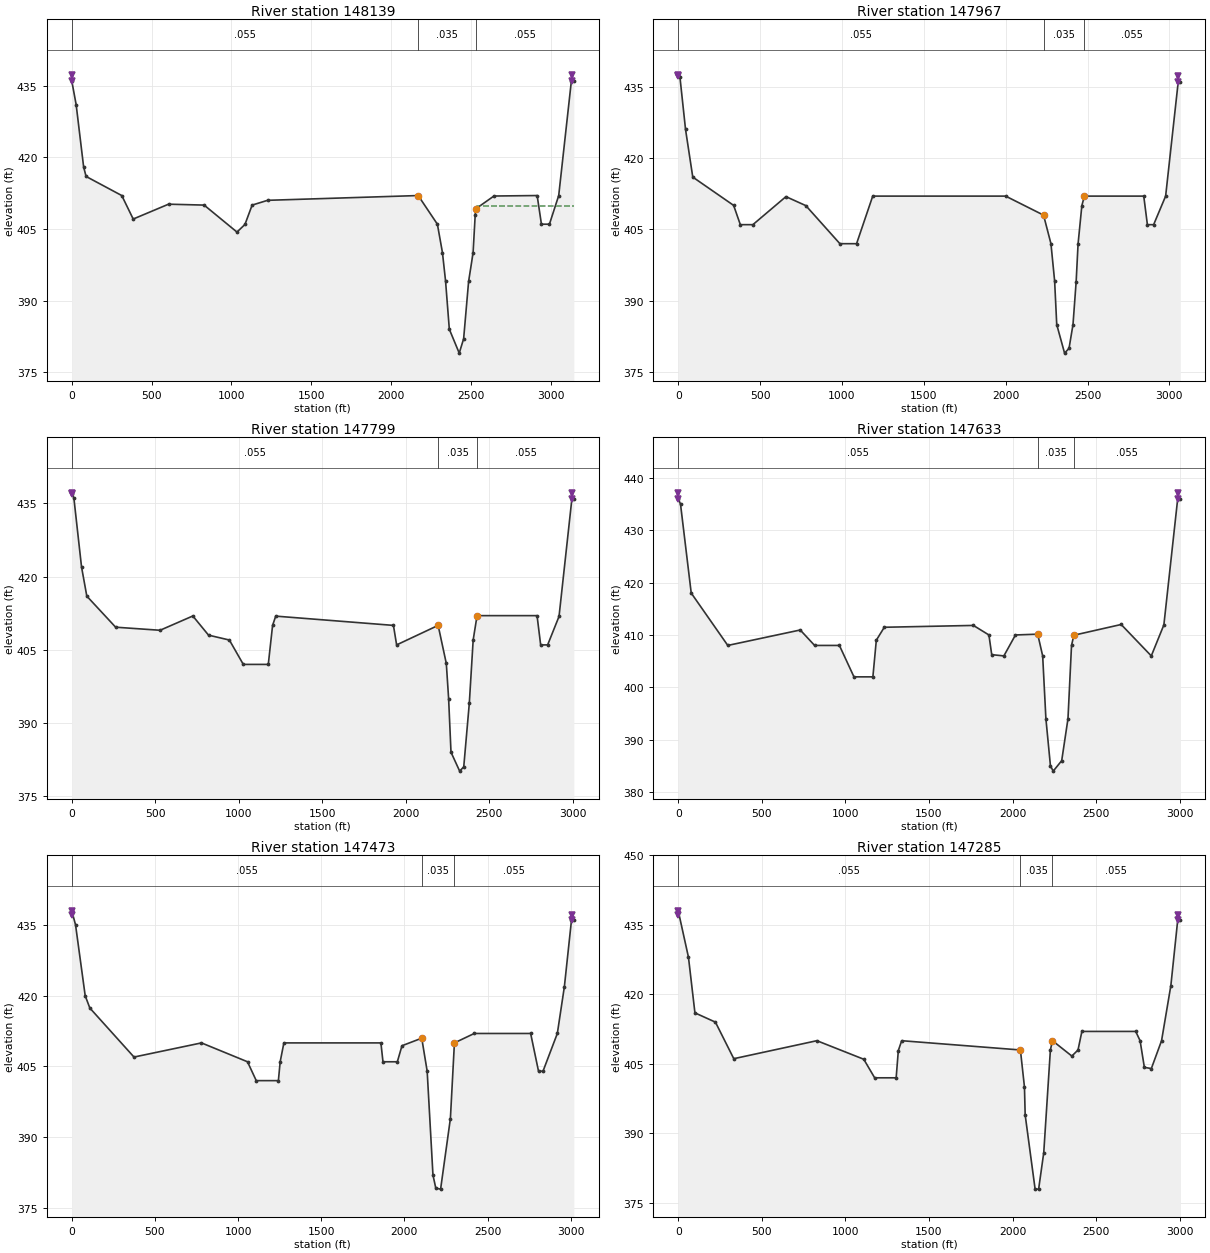
Type RM Length L Ch R = 1 ,148139  ,167,172,175
BEGIN DESCRIPTION:
Downstream of the confluence of Elm Fork and West Fork.
END DESCRIPTION:
XS GIS Cut Line= 3
2461264.280915836979412.294868132460759.000102256977671.00012238
2460636.75592417 6976344.2032353
#Sta/Elev= 30
       0     436   27.42  431.05   74.28     418   89.61     416  313.24     412
  384.89  407.08  606.27  410.19  829.29     410 1035.02  404.35 1085.06  405.95
 1129.96     410 1227.08     411 2170.34     412 2290.62     406 2322.29  400.07
 2341.66  394.16 2365.42     384 2427.49     379 2455.02     382 2486.18     394
 2514.23     400 2527.64     408 2533.03  409.26 2644.86   411.9 2915.71     412
 2942.45     406 2992.59     406 3050.72     412 3130.08     436 3145.54     436
#Mann= 3 ,0,0
       0    .055       0 2170.34    .035       0 2533.03    .055       0
Levee=-1,0,437.28,-1,3131,437.28,Levee 1,Levee 2
#XS Ineff= 2 , 0
       0 2290.62     406 2540.55       0  409.88
Permanent Ineff=
       F       F
Bank Sta=2170.34,2533.03
XS Rating Curve= 0 ,0
Exp/Cntr=0.3,0.1

Type RM Length L Ch R = 1 ,147967  ,163,168,171
BEGIN DESCRIPTION:
This cross section corresponds to cross section 147969 of the non-georeferenced CDC model which was the source of this model.
END DESCRIPTION:
XS GIS Cut Line= 3
2461413.161851676979361.517738712460918.000112336977632.00020038
2460822.115789686976367.85607514
#Sta/Elev= 30
       0  437.49   10.47     437   44.64     426   88.74     416  338.39  410.05
  379.26     406   455.9     406  657.92  411.89  779.46     410  987.48     402
 1089.32     402    1188     412 1999.98     412 2231.44     408 2276.59     402
 2299.04  394.18 2311.97     385  2359.8     379 2387.04     380 2411.26     385
 2430.53     394 2442.25  401.95 2465.38     410 2480.93     412 2843.47     412
 2865.69     406 2903.83     406 2977.13     412 3053.97     436 3066.78     436
#Mann= 3 ,0,0
       0    .055       0 2231.44    .035       0 2480.93    .055       0
Levee=-1,0,437.23,-1,3054,437.23,Levee 1,Levee 2
#XS Ineff= 2 , 0
       0 2231.44     408 2480.93       0     412
Permanent Ineff=
       F       F
Bank Sta=2231.44,2480.93
XS Rating Curve= 0 ,0
Exp/Cntr=0.3,0.1

Type RM Length L Ch R = 1 ,147799  ,161,166,169
BEGIN DESCRIPTION:
This cross section corresponds to cross section 147802 of the non-georeferenced CDC model which was the source of this model.
END DESCRIPTION:
XS GIS Cut Line= 4
2461561.133012416979303.910242382461081.019143256977606.52912271
2461065.812152686977522.079160382461008.404459096976367.38986872
#Sta/Elev= 30
       0     437   12.43  436.17   58.38     422   90.06     416  262.61  409.63
  528.52     409   724.8  411.93  818.76     408  943.54     407 1027.03     402
 1176.51     402 1202.32     410 1221.06   411.9 1925.82     410 1944.87     406
 2193.43     410 2242.35  402.19 2256.17     395 2270.41     384 2322.33  380.12
 2346.76     381 2379.99     394 2403.15     407 2426.46     412 2785.63     412
 2807.23     406 2849.02     406 2917.22  411.84 2994.39     436  3005.9     436
#Mann= 3 ,0,0
       0    .055       0 2193.43    .035       0 2426.46    .055       0
Levee=-1,0,437.18,-1,2995,437.18,Levee 1,Levee 2
#XS Ineff= 2 , 0
       0 2193.43     410 2426.46       0     412
Permanent Ineff=
       F       F
Bank Sta=2193.43,2426.46
XS Rating Curve= 0 ,0
Exp/Cntr=0.3,0.1

Type RM Length L Ch R = 1 ,147633  ,156,160,164
BEGIN DESCRIPTION:
This cross section corresponds to cross section 147635 of the non-georeferenced CDC model which was the source of this model.
END DESCRIPTION:
XS GIS Cut Line= 4
2461708.768871996979249.326690142461239.662854856977567.40518522
2461220.866960676977484.465062382461186.256465586976313.02547613
#Sta/Elev= 30
       0     436   13.56     435    77.7     418  296.37     408  729.72  410.95
  815.68     408  964.02     408 1051.07     402 1164.27     402 1184.81     409
  1232.6  411.47 1765.53  411.82 1858.28     410  1875.1  406.24 1947.74     406
 2017.08     410 2150.12  410.15 2179.83     406 2199.16     394 2226.34     385
 2242.93     384 2293.67     386 2331.18     394  2352.4     408 2366.46  409.95
 2649.35     412 2829.49     406 2904.78  411.92 2987.45     436 3003.11     436
#Mann= 3 ,0,0
       0    .055       0 2150.12    .035       0 2366.46    .055       0
Levee=-1,0,437.14,-1,2988,437.14,Levee 1,Levee 2
#XS Ineff= 2 , 0
       0 2179.83     406  2352.4       0     408
Permanent Ineff=
       F       F
Bank Sta=2150.12,2366.46
XS Rating Curve= 0 ,0
Exp/Cntr=0.3,0.1

Type RM Length L Ch R = 1 ,147473  ,171,188,179
BEGIN DESCRIPTION:
This cross section corresponds to cross section 147469 of the non-georeferenced CDC model which was the source of this model.
END DESCRIPTION:
XS GIS Cut Line= 3
2461856.277435246979198.192934132461370.999862496977432.99994221
2461361.084199946976245.09450963
#Sta/Elev= 30
       0     438   22.63  435.04   80.74     420   108.5   417.4  374.15     407
  779.89     410 1056.54     406 1109.14     402 1242.25     402 1252.96     406
 1275.29     410 1858.61     410 1871.09     406 1957.44     406 1985.35   409.4
 2104.17     411 2136.79     404 2171.55     382 2188.62  379.21 2217.54     379
 2276.44  393.97 2300.56     410 2419.92     412 2758.91     412 2806.27     404
 2833.19     404 2919.37     412 2961.73  421.92 3004.36     436 3018.63     436
#Mann= 3 ,0,0
       0    .055       0 2104.17    .035       0 2300.56    .055       0
Levee=-1,0,437.09,-1,3005,437.09,Levee 1,Levee 2
#XS Ineff= 2 , 0
       0 2104.17     411 2300.56       0     410
Permanent Ineff=
       F       F
Bank Sta=2104.17,2300.56
XS Rating Curve= 0 ,0
Exp/Cntr=0.3,0.1

Type RM Length L Ch R = 1 ,147285  ,169,185,176
BEGIN DESCRIPTION:
This cross section corresponds to cross section 147282 of the non-georeferenced CDC model which was the source of this model.
END DESCRIPTION:
XS GIS Cut Line= 5
2461993.409706926979144.458789632461656.600013086977807.80923197
 2461563.61791566977388.51512305 2461553.87384066976956.75614405
 2461501.64527056976194.61396755
#Sta/Elev= 30
       0     438   61.18     428   99.87     416  222.53     414  332.34  406.12
  829.47     410 1109.96     406 1175.09     402 1303.73     402  1316.7  407.87
 1336.79     410 2047.08     408 2071.35     400 2075.55     394 2135.08     378
 2156.09     378 2186.74  385.87 2226.44     408 2238.86     410 2354.79  406.69
 2391.72     408 2414.89     412 2736.85     412  2763.1     410  2788.7  404.25
 2830.43     404 2891.53     410 2947.17  421.89 2988.18     436 3003.71     436
#Mann= 3 ,0,0
       0    .055       0 2047.08    .035       0 2238.86    .055       0
Levee=-1,0,437.04,-1,2988,437.04,Levee 1,Levee 2
#XS Ineff= 2 , 0
       0 2047.08     408 2238.86       0     410
Permanent Ineff=
       F       F
Bank Sta=2047.08,2238.86
XS Rating Curve= 0 ,0
Exp/Cntr=0.3,0.1

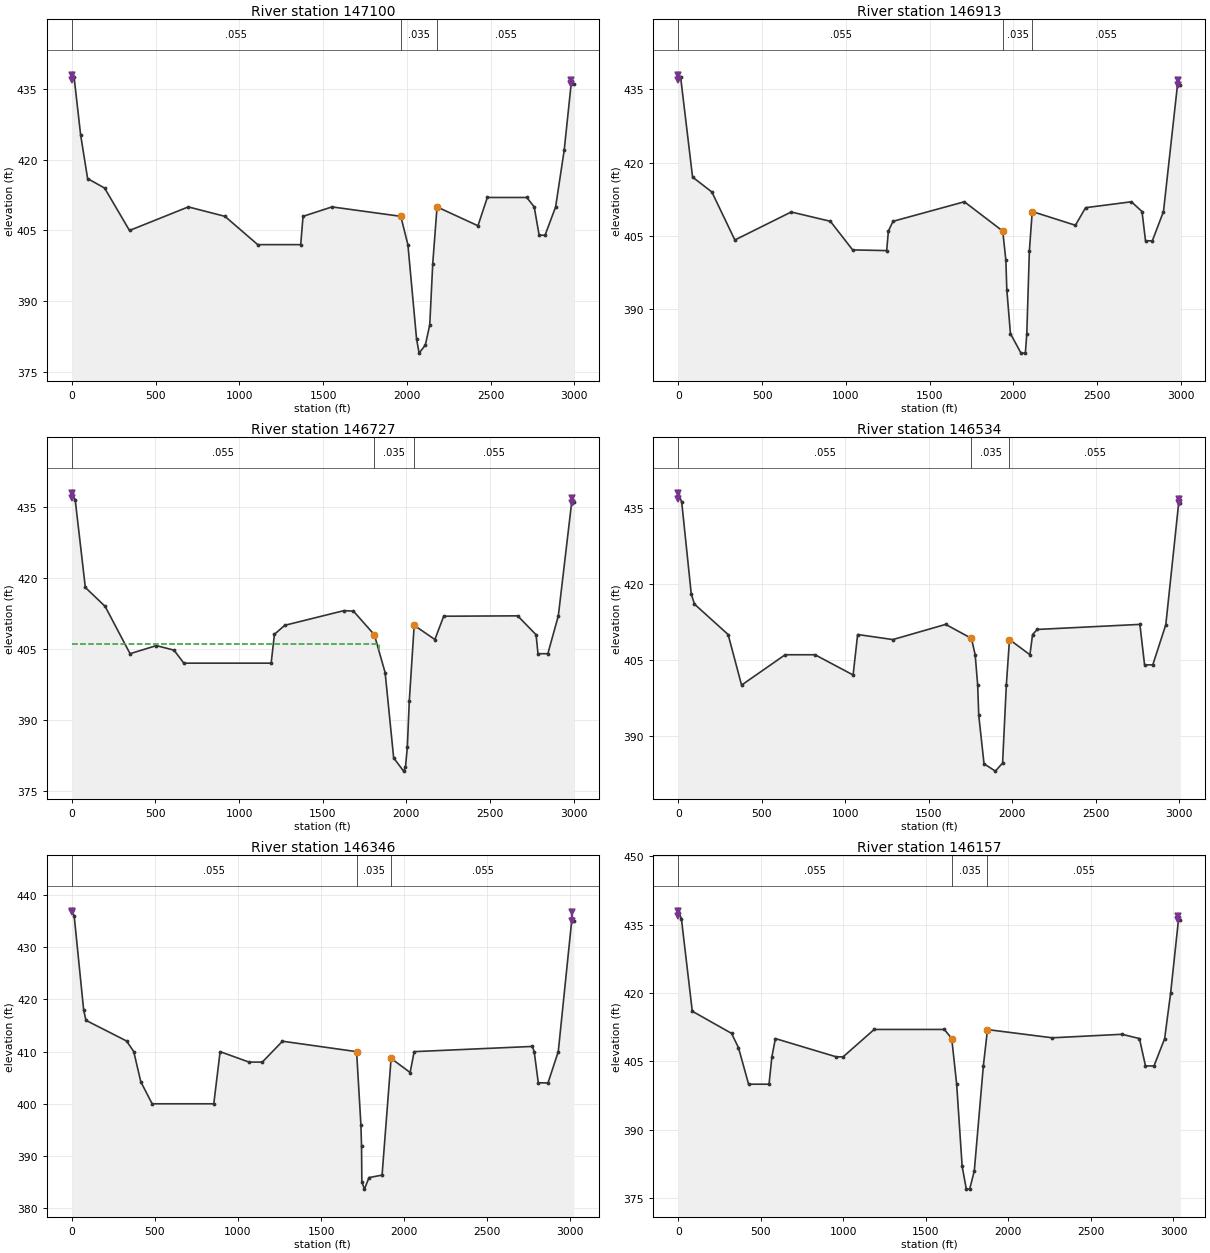
Type RM Length L Ch R = 1 ,147100  ,171,187,178
BEGIN DESCRIPTION:
This cross section corresponds to cross section 147096 of the non-georeferenced CDC model which was the source of this model.
END DESCRIPTION:
XS GIS Cut Line= 5
2462130.30871135 6979093.88080682461822.814903776977752.38414596
2461751.314062516977330.178953632461735.283910846976899.36911972
2461636.915669266976144.05960672
#Sta/Elev= 30
       0     438   13.69  437.57   52.85  425.29   94.59     416  195.85     414
  344.64     405  695.84     410  914.29     408 1110.21     402 1366.66     402
 1380.68     408 1553.61     410 1964.21     408 2006.59     402 2058.35     382
 2073.55     379 2110.75  380.72  2137.1     385 2154.92  397.98 2180.66     410
  2424.8     406  2480.8     412 2716.31     412  2760.7     410 2790.16     404
 2825.44     404 2888.53     410 2939.63     422 2981.05     436  2997.3     436
#Mann= 3 ,0,0
       0    .055       0 1964.21    .035       0 2180.66    .055       0
Levee=-1,0,436.99,-1,2981,436.99,Levee 1,Levee 2
#XS Ineff= 2 , 0
       0 1964.21     408 2180.66       0     410
Permanent Ineff=
       F       F
Bank Sta=1964.21,2180.66
XS Rating Curve= 0 ,0
Exp/Cntr=0.3,0.1

Type RM Length L Ch R = 1 ,146913  ,170,186,178
BEGIN DESCRIPTION:
This cross section corresponds to cross section 146910 of the non-georeferenced CDC model which was the source of this model.
END DESCRIPTION:
XS GIS Cut Line= 5
2462267.21329317 6979043.42815182461989.030122526977696.96004422
 2461939.00889716977271.844096562461916.693981086976841.98209538
2461772.103390996976093.37171596
#Sta/Elev= 30
       0     438    14.4  437.49   85.49  417.06  200.76     414  337.84  404.17
  674.07  409.91  907.84     408 1040.68  402.14 1243.82     402 1253.86     406
 1281.73     408 1707.26     412 1936.25     406 1955.05     400 1960.54     394
 1982.24     385 2045.19     381 2071.23     381 2079.86     385 2095.28     402
 2112.33     410 2369.84  407.19 2430.72  410.79 2704.08     412 2767.37     410
 2788.26     404 2828.93     404 2895.41     410 2979.15     436 2995.84     436
#Mann= 3 ,0,0
       0    .055       0 1936.25    .035       0 2112.33    .055       0
Levee=-1,0,436.95,-1,2980,436.95,Levee 1,Levee 2
#XS Ineff= 2 , 0
       0 1936.25     406 2112.33       0     410
Permanent Ineff=
       F       F
Bank Sta=1936.25,2112.33
XS Rating Curve= 0 ,0
Exp/Cntr=0.3,0.1

Type RM Length L Ch R = 1 ,146727  ,180,193,203
BEGIN DESCRIPTION:
This cross section corresponds to cross section 146724 of the non-georeferenced CDC model which was the source of this model.
END DESCRIPTION:
XS GIS Cut Line= 4
2462402.267484996978995.712696052462149.999944936977628.00020838
2462093.000058926976770.999953882461905.981732166976042.61197497
#Sta/Elev= 30
       0     438   20.82  436.44   81.15     418  199.48     414   348.5     404
  505.67  405.71  611.14  404.75  669.93     402 1192.03     402 1211.57   408.1
 1273.35     410 1627.24   413.1 1684.03     413 1809.06     408 1873.45     400
 1924.43     382 1983.58  379.18 1994.81  379.95 2006.22  384.27 2017.87     394
 2047.13     410 2170.82     407 2223.59  411.92 2666.02     412 2775.98     408
 2787.27     404 2846.22     404  2908.9     412 2988.41  435.91 3001.69     436
#Mann= 3 ,0,0
       0    .055       0 1809.06    .035       0 2047.13    .055       0
Levee=-1,0,436.9,-1,2989,436.9,Levee 1,Levee 2
#XS Ineff= 2 , 0
       0 1836.44     406 2047.13       0     410
Permanent Ineff=
       F       F
Bank Sta=1809.06,2047.13
XS Rating Curve= 0 ,0
Exp/Cntr=0.3,0.1

Type RM Length L Ch R = 1 ,146534  ,177,188,199
BEGIN DESCRIPTION:
This cross section corresponds to cross section 146534 of the non-georeferenced CDC model which was the source of this model.
END DESCRIPTION:
XS GIS Cut Line= 4
2462556.341323856978936.461502212462340.93985176 6977577.2440763
2462279.646995346976715.619159132462120.190949416975964.65314138
#Sta/Elev= 30
       0     438    21.1  436.11   78.03     418   97.41     416  298.84     410
   379.4     400  640.55     406  819.36     406  1047.6     402 1074.73     410
 1285.54     409 1602.04     412 1756.25  409.24 1778.84     406 1793.81     400
  1800.3     394 1831.87  384.45 1899.73     383 1943.01   384.6 1965.47     400
 1984.36     409  2106.8     406 2122.66     410 2150.57     411 2765.56     412
 2793.62     404 2842.81     404 2920.89  411.95 2997.96     436 3007.69     436
#Mann= 3 ,0,0
       0    .055       0 1756.25    .035       0 1984.36    .055       0
Levee=-1,0,436.85,-1,2998,436.85,Levee 1,Levee 2
#XS Ineff= 2 , 0
       0 1756.25  409.24 1984.36       0     409
Permanent Ineff=
       F       F
Bank Sta=1756.25,1984.36
XS Rating Curve= 0 ,0
Exp/Cntr=0.3,0.1

Type RM Length L Ch R = 1 ,146346  ,178,189,200
BEGIN DESCRIPTION:
This cross section corresponds to cross section 146345 of the non-georeferenced CDC model which was the source of this model.
END DESCRIPTION:
XS GIS Cut Line= 4
2462708.601518016978878.285437462462526.636002666977512.95319438
2462461.189939356976646.641934892462332.380485686975882.33440839
#Sta/Elev= 30
       0     437   14.59     436   71.52     418   85.41     416  330.04  412.04
  373.02     410  415.44  404.22  483.69     400  854.62     400  892.62     410
 1066.13     408 1146.71     408 1267.95     412 1713.96     410 1739.87     396
  1743.6     392 1745.63     385 1761.11  383.64 1788.41  385.85 1867.27  386.33
 1921.59  408.71  2036.2     406 2060.31     410 2771.42     411 2782.74     410
 2807.26  404.03 2865.66     404 2927.51     410 3008.02     435 3021.27  434.99
#Mann= 3 ,0,0
       0    .055       0 1713.96    .035       0 1921.59    .055       0
Levee=-1,0,436.81,-1,3008,436.81,Levee 1,Levee 2
#XS Ineff= 2 , 0
       0 1713.96     410 1921.59       0  408.71
Permanent Ineff=
       F       F
Bank Sta=1713.96,1921.59
XS Rating Curve= 0 ,0
Exp/Cntr=0.3,0.1

Type RM Length L Ch R = 1 ,146157  ,175,186,197
BEGIN DESCRIPTION:
This cross section corresponds to cross section 146156 of the non-georeferenced CDC model which was the source of this model.
END DESCRIPTION:
XS GIS Cut Line= 4
  2462862.1523926978829.147740472462712.330841246977448.66100013
2462642.733867596976577.666022972462545.477172346975804.80536397
#Sta/Elev= 30
       0     438   19.07   436.3   85.07     416  323.04  411.14  364.91     408
  426.27     400  550.02     400  567.22     406   588.5     410  956.92     406
  998.73     406 1187.02     412 1612.08     412 1656.77     410 1686.56     400
 1719.82     382 1745.04  377.01 1765.33     377  1793.4     381 1848.19     404
 1873.31  411.97 2265.24  410.17 2687.71  410.94 2793.79     410 2830.41     404
 2881.98     404 2946.46     410 2982.76     420 3030.07     436 3041.32     436
#Mann= 3 ,0,0
       0    .055       0 1656.77    .035       0 1873.31    .055       0
Levee=-1,0,436.76,-1,3030,436.76,Levee 1,Levee 2
#XS Ineff= 2 , 0
       0 1656.77     410 1873.31       0  411.97
Permanent Ineff=
       F       F
Bank Sta=1656.77,1873.31
XS Rating Curve= 0 ,0
Exp/Cntr=0.3,0.1

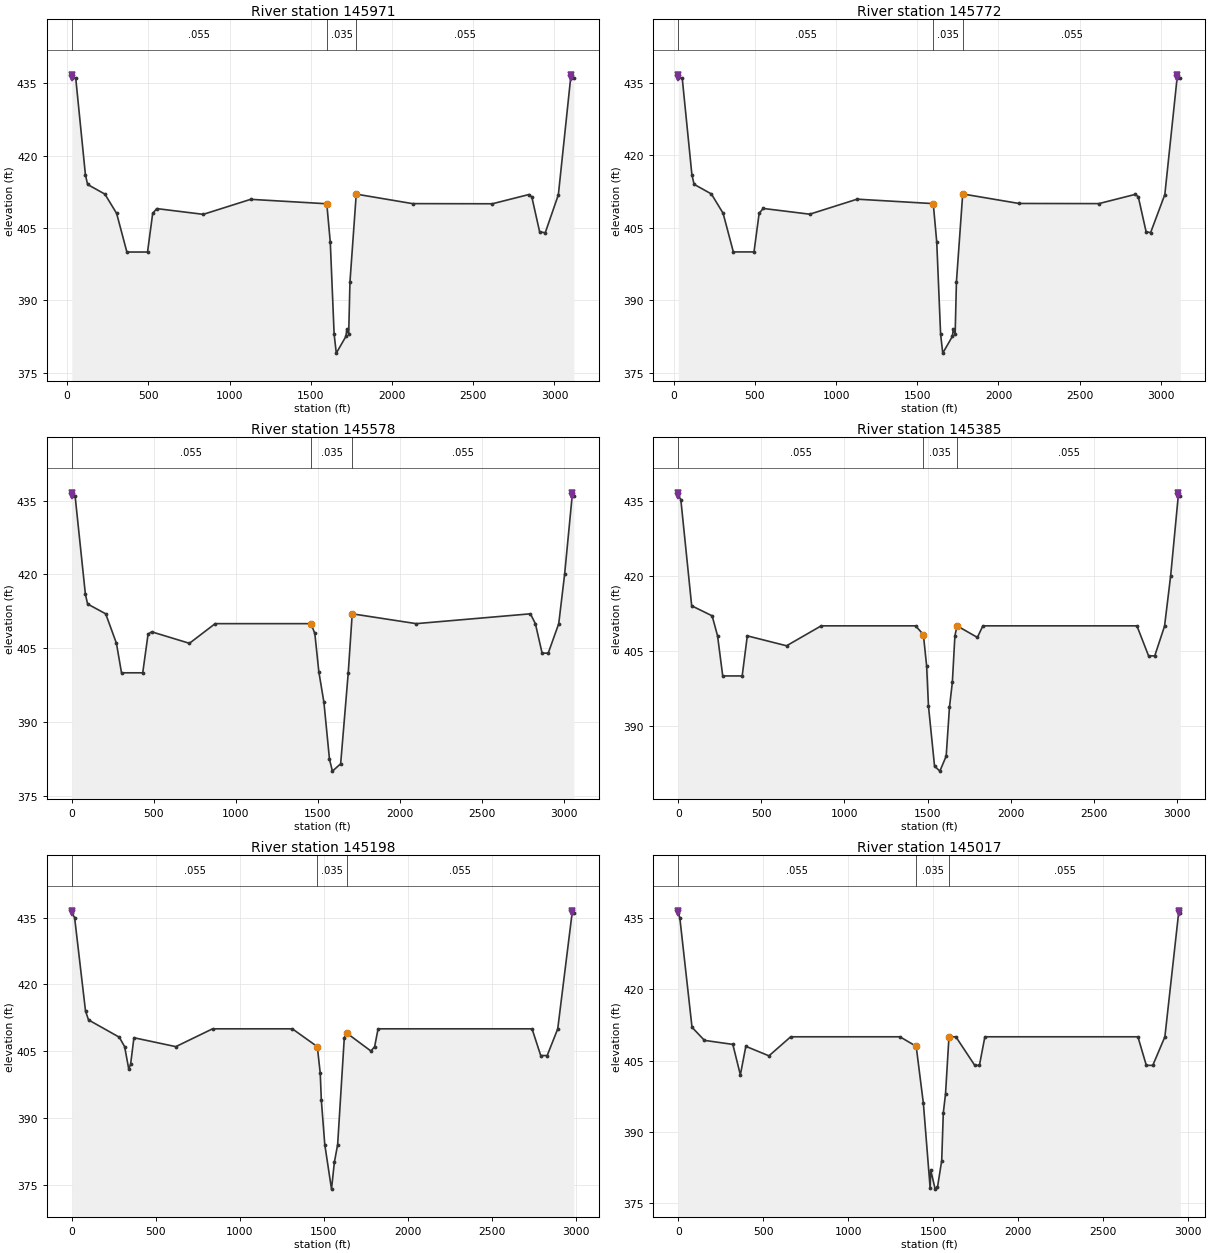
Type RM Length L Ch R = 1 ,145971  ,182,199,215
BEGIN DESCRIPTION:
This cross section corresponds to cross section 145967 of the non-georeferenced CDC model which was the source of this model.
END DESCRIPTION:
XS GIS Cut Line= 2
2463007.698032686978728.732586972462747.951833016975649.13704014
#Sta/Elev= 30
   28.72     436   53.24     436  112.75     416  126.19     414  232.69     412
   304.9     408  367.97     400  495.12     400  526.77     408  551.82     409
  838.24  407.81 1130.04  410.92 1598.51     410 1620.05     402 1643.68     383
 1656.92  379.05 1716.13  382.51 1721.73     384 1733.33     383 1741.13   393.8
 1779.82     412 2126.23  410.03 2617.65     410 2842.95  411.92 2860.69   411.4
 2908.68  404.18 2943.27     404 3023.96  411.87  3099.4     436 3119.25     436
#Mann= 3 ,0,0
   28.72    .055       0 1598.51    .035       0 1779.82    .055       0
Levee=-1,28.72,436.72,-1,3100,436.72,Levee 1,Levee 2
#XS Ineff= 2 , 0
       0 1598.51     410 1779.82       0     412
Permanent Ineff=
       F       F
Bank Sta=1598.51,1779.82
XS Rating Curve= 0 ,0
Exp/Cntr=0.3,0.1

Type RM Length L Ch R = 1 ,145772  ,179,194,211
BEGIN DESCRIPTION:
This cross section corresponds to cross section 145773 of the non-georeferenced CDC model which was the source of this model.
END DESCRIPTION:
XS GIS Cut Line= 2
2463173.029066836978730.485536222462976.152492086975646.23284647
#Sta/Elev= 30
   28.72     436   53.24     436  112.75     416  126.19     414  232.69     412
   304.9     408  367.97     400  495.12     400  526.77     408  551.82     409
  838.24  407.81 1130.04  410.92 1598.51     410 1620.05     402 1643.68     383
 1656.92  379.05 1716.13  382.51 1721.73     384 1733.33     383 1741.13   393.8
 1779.82     412 2126.23  410.03 2617.65     410 2842.95  411.92 2860.69   411.4
 2908.68  404.18 2936.45     404 3023.96  411.87  3099.4     436 3119.25     436
#Mann= 3 ,0,0
   28.72    .055       0 1598.51    .035       0 1779.82    .055       0
Levee=-1,28.72,436.66,-1,3100,436.66,Levee 1,Levee 2
#XS Ineff= 2 , 0
       0 1598.51     410 1779.82       0     412
Permanent Ineff=
       F       F
Bank Sta=1598.51,1779.82
XS Rating Curve= 0 ,0
Exp/Cntr=0.3,0.1

Type RM Length L Ch R = 1 ,145578  ,176,193,209
BEGIN DESCRIPTION:
This cross section corresponds to cross section 145580 of the non-georeferenced CDC model which was the source of this model.
END DESCRIPTION:
XS GIS Cut Line= 2
2463331.440495436978695.382916142463199.38662568 6975636.0215808
#Sta/Elev= 30
       0     436   20.21     436   83.02     416   96.46     414  206.94     412
  272.42     406  303.34     400  432.79     400  465.41  407.87  487.14  408.34
   717.6     406  874.59     410 1458.72     410 1482.43     408 1506.89  400.21
 1537.85     394 1571.88  382.39 1589.78     380 1639.93  381.49 1686.27     400
 1710.44     412 2100.95     410 2797.27     412 2827.58     410 2868.65     404
 2905.94     404 2970.11     410 3005.84     420 3051.92  435.97 3062.21     436
#Mann= 3 ,0,0
       0    .055       0 1458.72    .035       0 1710.44    .055       0
Levee=-1,0,436.61,-1,3052,436.61,Levee 1,Levee 2
#XS Ineff= 2 , 0
       0 1458.72     410 1710.44       0     412
Permanent Ineff=
       F       F
Bank Sta=1458.72,1710.44
XS Rating Curve= 0 ,0
Exp/Cntr=0.3,0.1

Type RM Length L Ch R = 1 ,145385  ,172,187,204
BEGIN DESCRIPTION:
This cross section corresponds to cross section 145386 of the non-georeferenced CDC model which was the source of this model.
END DESCRIPTION:
XS GIS Cut Line= 2
2463489.431321176978653.692054632463421.957046666975634.05570547
#Sta/Elev= 30
       0     436   15.57  435.21   80.89     414  203.92     412  236.57     408
  267.66     400  384.71     400  415.47     408  651.72  406.02  860.05     410
 1427.88     410 1474.68  408.25 1494.35     402 1505.32     394 1541.89     382
 1573.93     381 1611.95     384 1631.74  393.78 1649.02  398.71 1664.38     408
 1677.48     410 1799.62  407.69  1832.7     410 2759.38     410 2829.58     404
 2866.55     404 2925.59  409.95 2962.37     420 3008.29     436 3020.39     436
#Mann= 3 ,0,0
       0    .055       0 1474.68    .035       0 1677.48    .055       0
Levee=-1,0,436.55,-1,3009,436.55,Levee 1,Levee 2
#XS Ineff= 2 , 0
       0 1474.68  408.25 1677.48       0     410
Permanent Ineff=
       F       F
Bank Sta=1474.68,1677.48
XS Rating Curve= 0 ,0
Exp/Cntr=0.3,0.1

Type RM Length L Ch R = 1 ,145198  ,178,181,180
BEGIN DESCRIPTION:
This cross section corresponds to cross section 145193 of the non-georeferenced CDC model which was the source of this model.
END DESCRIPTION:
XS GIS Cut Line= 2
2463643.031735756978626.184235632463640.012384836975637.81586856
#Sta/Elev= 30
       0     436   16.87     435   81.82     414   99.67     412  282.76  408.12
   314.6     406  339.05     401  350.05     402  369.94     408  619.31     406
  837.84     410 1312.95     410 1461.41     406 1478.99     400 1485.36     394
 1505.96     384 1545.97     374 1562.84     380 1582.49     384 1622.07     408
 1638.33     409 1780.68  405.01 1802.67     406 1823.21     410 2739.56     410
 2791.23     404 2829.67     404 2892.53     410 2977.97  435.99 2988.37     436
#Mann= 3 ,0,0
       0    .055       0 1461.41    .035       0 1638.33    .055       0
Levee=-1,0,436.5,-1,2978,436.5,Levee 1,Levee 2
#XS Ineff= 2 , 0
       0 1461.41     406 1622.07       0     408
Permanent Ineff=
       F       F
Bank Sta=1461.41,1638.33
XS Rating Curve= 0 ,0
Exp/Cntr=0.3,0.1

Type RM Length L Ch R = 1 ,145017  ,174,176,176
BEGIN DESCRIPTION:
This cross section corresponds to cross section 145016 of the non-georeferenced CDC model which was the source of this model.
END DESCRIPTION:
XS GIS Cut Line= 2
 2463819.44214416978591.791587892463824.934587186975637.98679997
#Sta/Elev= 30
       0     436    9.26  435.02   81.09     412  154.07  409.25  321.23   408.4
  365.47     402   397.7     408  533.76     406  661.58     410 1304.31     410
 1399.89     408 1442.28     396 1482.19  378.14 1485.34     382 1511.43     378
 1525.07  378.37 1550.04  383.98 1559.42     394 1572.49     398 1592.77     410
 1633.38     410 1744.48     404  1771.9     404 1804.03     410 2704.44     410
 2753.81     404 2791.84     404 2863.06     410 2943.51   435.9 2953.81     436
#Mann= 3 ,0,0
       0    .055       0 1399.89    .035       0 1592.77    .055       0
Levee=-1,0,436.46,-1,2944,436.46,Levee 1,Levee 2
#XS Ineff= 2 , 0
       0 1399.89     408 1592.77       0     410
Permanent Ineff=
       F       F
Bank Sta=1399.89,1592.77
XS Rating Curve= 0 ,0
Exp/Cntr=0.3,0.1

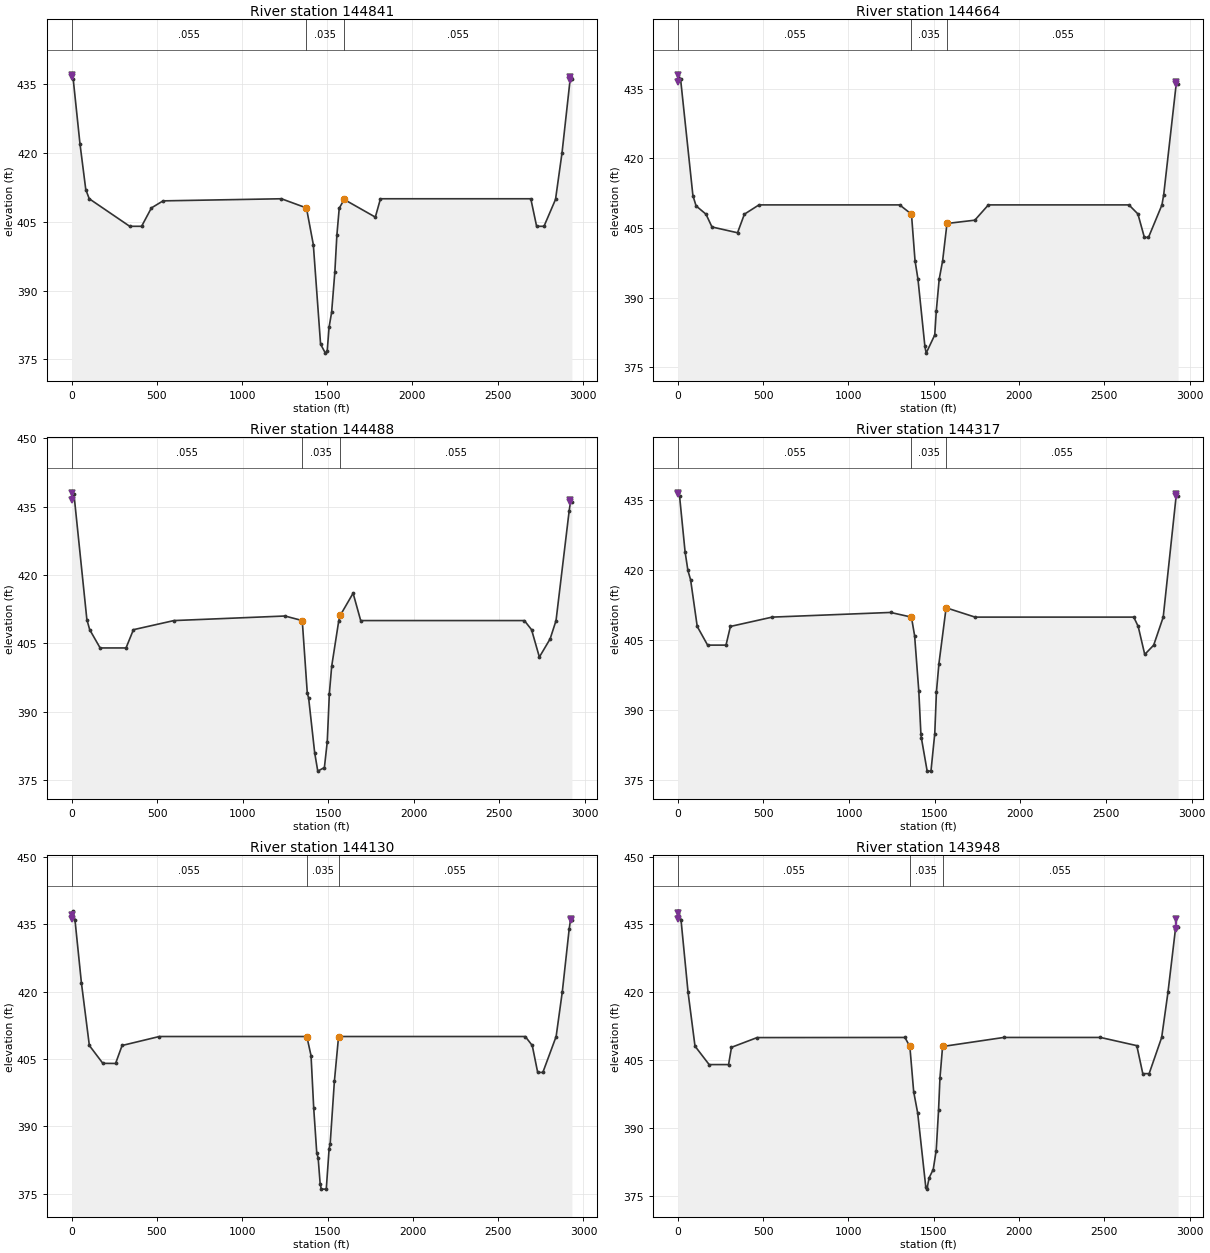
Type RM Length L Ch R = 1 ,144841  ,175,177,177
BEGIN DESCRIPTION:
This cross section corresponds to cross section 144840 of the non-georeferenced CDC model which was the source of this model.
END DESCRIPTION:
XS GIS Cut Line= 2
 2463991.48281056978576.529151222464005.193413026975639.96120547
#Sta/Elev= 30
       0     437    9.18     436   48.61     422   82.79     412  103.14     410
  340.65     404  410.45     404  467.98     408  536.32  409.54 1231.17     410
 1378.13     408 1418.56     400 1461.12  378.33 1489.26  376.37 1500.02  376.79
 1510.94     382 1525.89  385.24 1544.81     394 1556.67     402 1570.55  407.93
 1599.58  409.85 1782.55     406 1812.67     410 2695.19     410  2729.4     404
 2772.64     404 2840.31  409.86 2878.46     420 2925.64  435.85  2936.6     436
#Mann= 3 ,0,0
       0    .055       0 1378.13    .035       0 1599.58    .055       0
Levee=-1,0,436.42,-1,2926,436.42,Levee 1,Levee 2
#XS Ineff= 2 , 0
       0 1378.13     408 1599.58       0  409.85
Permanent Ineff=
       F       F
Bank Sta=1378.13,1599.58
XS Rating Curve= 0 ,0
Exp/Cntr=0.3,0.1

Type RM Length L Ch R = 1 ,144664  ,174,176,176
BEGIN DESCRIPTION:
This cross section corresponds to cross section 144664 of the non-georeferenced CDC model which was the source of this model.
END DESCRIPTION:
XS GIS Cut Line= 2
2464163.462781526978572.075091882464185.467330666975639.12754571
#Sta/Elev= 30
       0     438   15.92  437.15   88.38     412  107.02  409.78   165.1     408
  200.11  405.25     350     404  390.23     408  475.65     410 1300.59     410
 1369.85     408 1390.65     398 1407.97     394 1448.51  379.57    1456  378.09
 1506.31     382 1515.33  387.15 1532.34     394 1552.65     398 1578.15     406
 1741.22  406.71 1820.77     410 2644.78     410 2697.48  408.05 2735.41     403
 2759.47     403 2838.47     410 2848.72  412.19 2921.95     436 2933.03     436
#Mann= 3 ,0,0
       0    .055       0 1369.85    .035       0 1578.15    .055       0
Levee=-1,0,436.37,-1,2922,436.37,Levee 1,Levee 2
#XS Ineff= 2 , 0
       0 1369.85     408 1578.15       0     406
Permanent Ineff=
       F       F
Bank Sta=1369.85,1578.15
XS Rating Curve= 0 ,0
Exp/Cntr=0.3,0.1

Type RM Length L Ch R = 1 ,144488  ,169,171,171
BEGIN DESCRIPTION:
This cross section corresponds to cross section 144488 of the non-georeferenced CDC model which was the source of this model.
END DESCRIPTION:
XS GIS Cut Line= 2
2464335.404038676978567.13907814 2464365.70253456975642.77583238
#Sta/Elev= 30
       0     438   13.42  437.66   88.82  410.22  105.38     408  166.31     404
  317.72     404  360.96     408  597.74     410 1246.78     411 1347.99     410
 1377.41  394.11 1385.32     393 1420.73     381 1438.73     377 1477.44  377.79
 1494.18  383.45 1506.41     394 1520.11     400 1561.55     410 1571.19  411.21
 1645.26     416 1689.63     410 2646.47     410 2688.58     408 2734.22     402
 2797.26     406 2831.64     410 2908.28     434 2915.84     436 2924.52     436
#Mann= 3 ,0,0
       0    .055       0 1347.99    .035       0 1571.19    .055       0
Levee=-1,0,436.33,-1,2916,436.33,Levee 1,Levee 2
#XS Ineff= 2 , 0
       0 1347.99     410 1571.19       0  411.21
Permanent Ineff=
       F       F
Bank Sta=1347.99,1571.19
XS Rating Curve= 0 ,0
Exp/Cntr=0.3,0.1

Type RM Length L Ch R = 1 ,144317  ,186,187,186
BEGIN DESCRIPTION:
This cross section corresponds to cross section 144312 of the non-georeferenced CDC model which was the source of this model.
END DESCRIPTION:
XS GIS Cut Line= 2
2464501.848915766978561.873668722464540.880005666975641.12458897
#Sta/Elev= 30
       0  436.63    9.89     436   42.28     424   58.79     420   74.54     418
  113.24     408  173.84     404  281.22     404  306.97     408  550.86     410
 1242.23     411 1363.98     410 1382.63     406 1407.05  394.14 1419.15     385
 1421.82  384.17 1455.68  377.04 1478.03     377 1500.26  385.06 1510.03     394
 1524.43     400 1566.54     412 1735.59     410 2662.26     410 2688.09     408
 2726.31     402 2778.64     404 2834.22     410 2909.56   435.9 2921.01     436
#Mann= 3 ,0,0
       0    .055       0 1363.98    .035       0 1566.54    .055       0
Levee=-1,0,436.29,-1,2910,436.29,Levee 1,Levee 2
#XS Ineff= 2 , 0
       0 1363.98     410 1566.54       0     412
Permanent Ineff=
       F       F
Bank Sta=1363.98,1566.54
XS Rating Curve= 0 ,0
Exp/Cntr=0.3,0.1

Type RM Length L Ch R = 1 ,144130  ,182,182,182
BEGIN DESCRIPTION:
This cross section corresponds to cross section 144129 of the non-georeferenced CDC model which was the source of this model.
END DESCRIPTION:
XS GIS Cut Line= 2
2464689.745849676978572.57049772 2464726.64505416975640.56258221
#Sta/Elev= 30
       0  436.99    5.56     438   19.25     436   56.96     422   103.6     408
  182.73  404.02  257.35     404  295.49     408  513.65     410 1378.34     410
 1403.03  405.74 1418.81     394 1436.68     384 1444.63     383 1456.36  377.22
 1463.31     376 1492.31     376 1508.99     385 1515.03     386 1539.84     400
 1564.38     410 2658.75     410 2699.72     408 2731.58     402 2761.78     402
 2839.68     410 2875.99     420 2916.31     434 2924.16     436 2932.24     436
#Mann= 3 ,0,0
       0    .055       0 1378.34    .035       0 1564.38    .055       0
Levee=-1,0,436.25,-1,2924,436.25,Levee 1,Levee 2
#XS Ineff= 2 , 0
       0 1378.34     410 1564.38       0     410
Permanent Ineff=
       F       F
Bank Sta=1378.34,1564.38
XS Rating Curve= 0 ,0
Exp/Cntr=0.3,0.1

Type RM Length L Ch R = 1 ,143948  ,181,182,181
BEGIN DESCRIPTION:
This cross section corresponds to cross section 143947 of the non-georeferenced CDC model which was the source of this model.
END DESCRIPTION:
XS GIS Cut Line= 2
2464872.291088256978574.866424892464907.261818836975642.77484813
#Sta/Elev= 30
       0  437.41    2.71     438   18.64     436   59.86     420  100.61  408.08
  183.48     404  297.44     404  314.54  407.82  464.65  409.97 1331.13     410
 1360.02     408 1382.46     398 1406.02  393.27 1453.14     377 1459.86  376.46
 1473.04  378.97 1496.93   380.8  1514.5     385 1528.36     394 1536.42     401
 1551.89     408 1910.44     410 2477.33     410 2690.24  408.19 2725.47     402
 2762.61     402 2836.09     410 2873.08     420 2916.99     434  2932.3  434.46
#Mann= 3 ,0,0
       0    .055       0 1360.02    .035       0 1551.89    .055       0
Levee=-1,0,436.2,-1,2920,436.2,Levee 1,Levee 2
#XS Ineff= 2 , 0
       0 1360.02     408 1551.89       0     408
Permanent Ineff=
       F       F
Bank Sta=1360.02,1551.89
XS Rating Curve= 0 ,0
Exp/Cntr=0.3,0.1