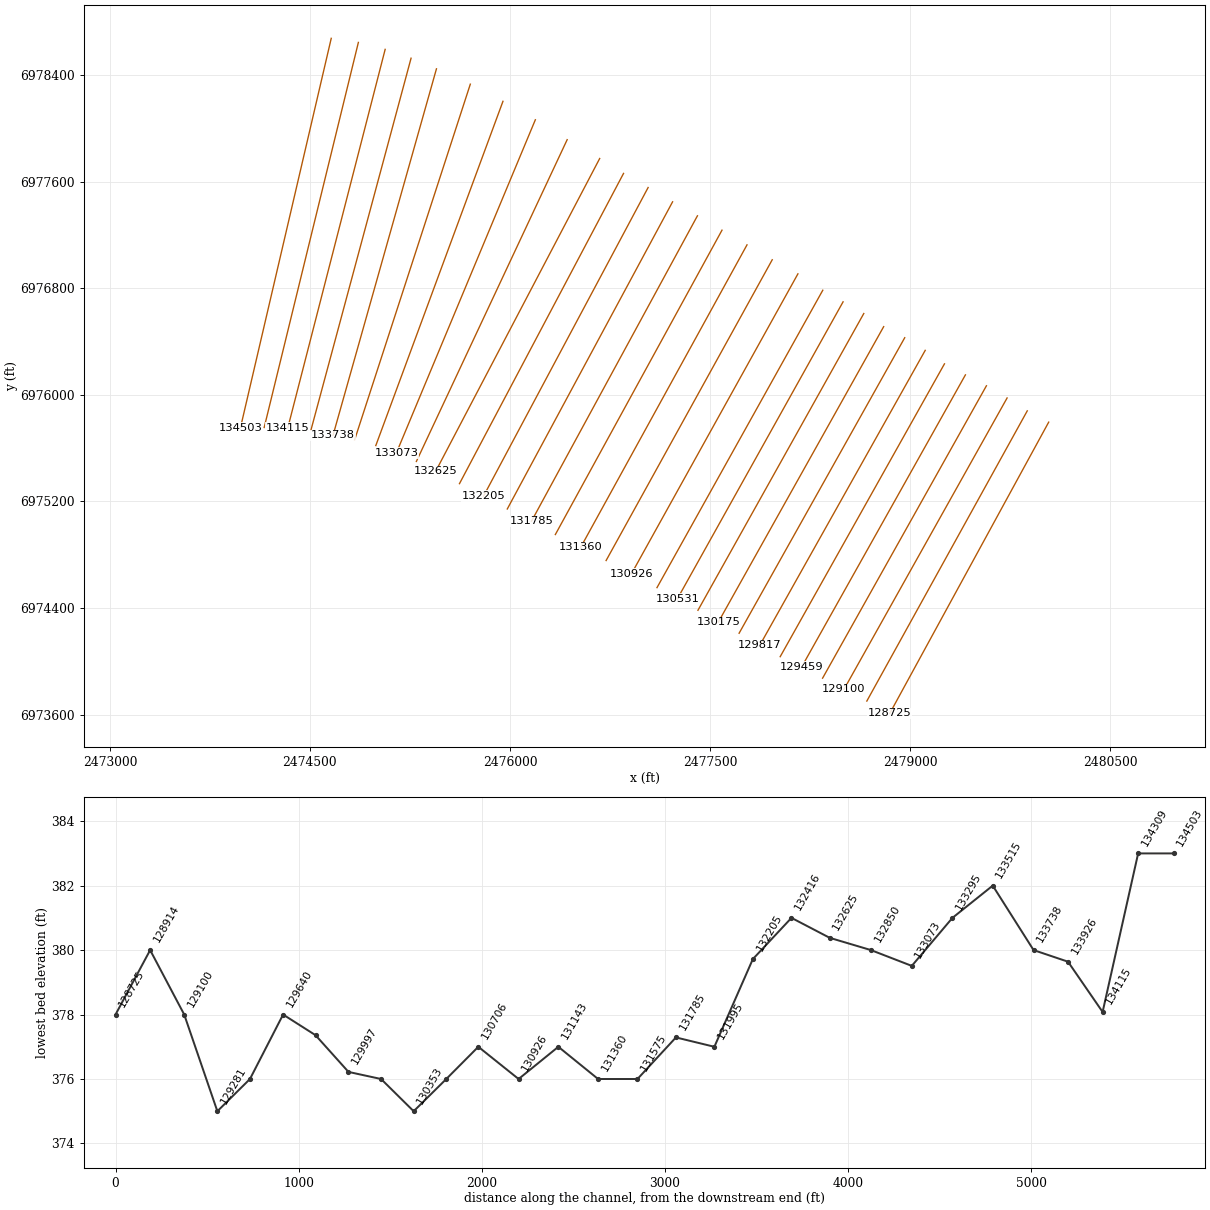
HEC-RAS study CDC_Consolidated_Model.prj: Upper Trinity CDC Consolidated Model

--- CDC_Consolidated_Model.g01 (geometry) --- (continued)

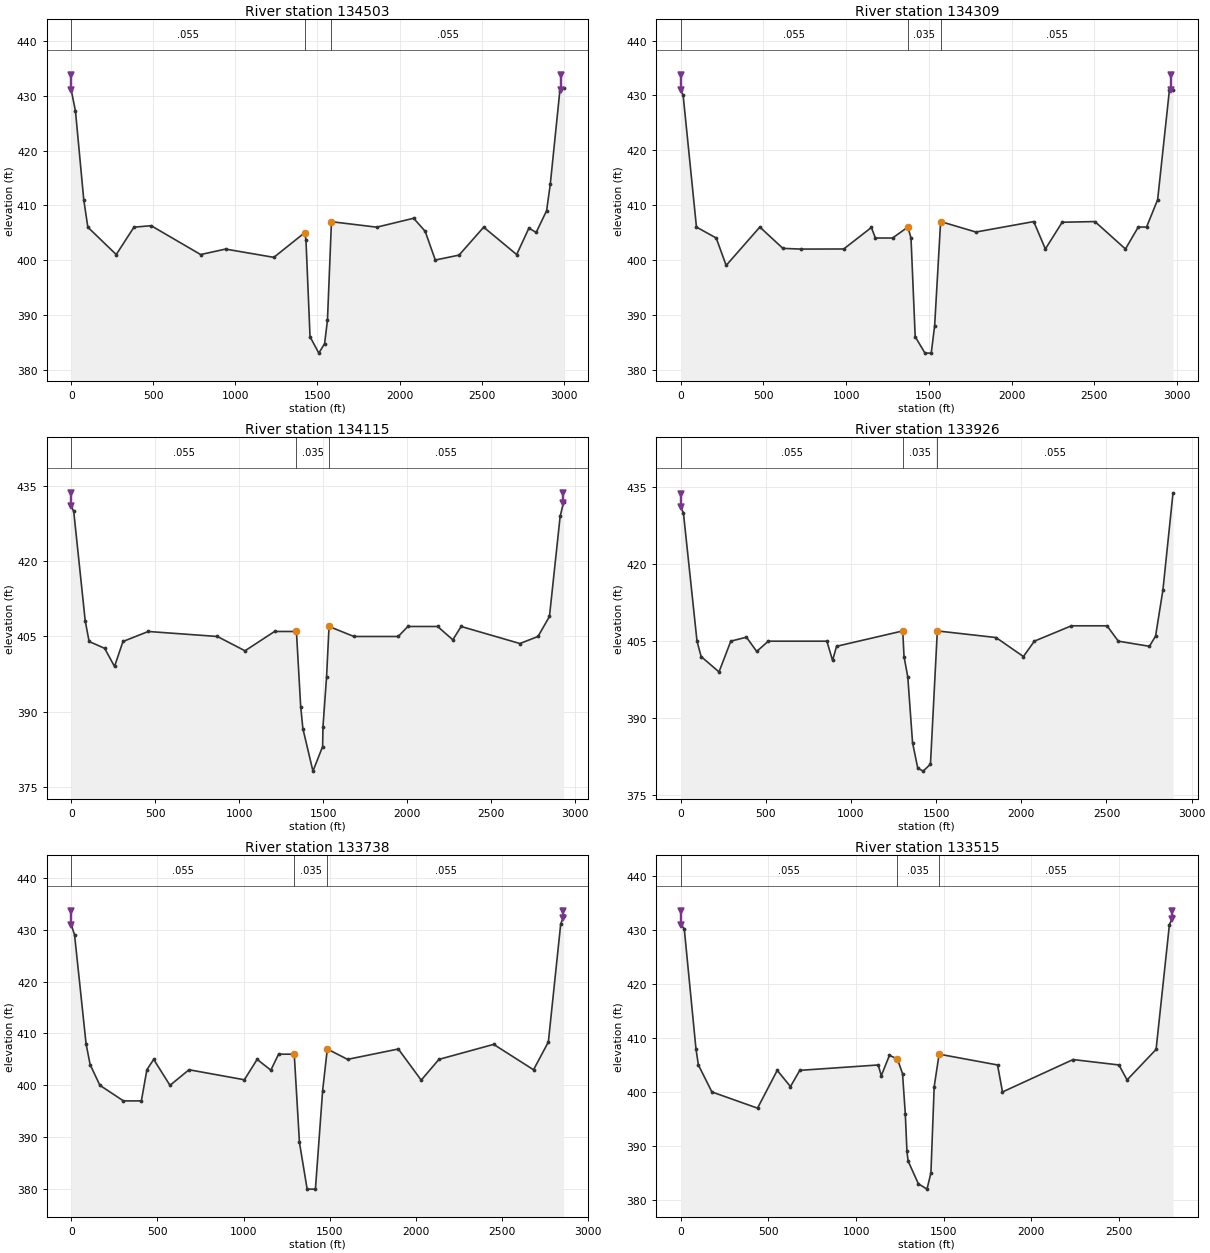
Type RM Length L Ch R = 1 ,134503  ,202,194,190
BEGIN DESCRIPTION:
This cross section corresponds to cross section 134505 of the non-georeferenced CDC model which was the source of this model.
END DESCRIPTION:
XS GIS Cut Line= 2
2474659.771185166978675.920684712473979.363753356975754.71458489
#Sta/Elev= 30
       0     431   25.53  427.19   76.05     411  100.91     406  273.83     401
  381.79     406  486.56  406.27  788.21     401  939.95     402 1234.05  400.49
 1422.29     405 1429.64  403.72 1454.54     386 1508.04     383 1543.28  384.74
 1560.68     389 1584.96     407 1860.95     406 2085.77  407.63 2155.89  405.25
 2217.63     400 2362.37   400.9 2512.44     406 2713.43     401 2787.92  405.83
 2832.18  405.04 2895.61     409 2918.08  413.81 2976.61  430.95  2999.4  431.33
#Mann= 3 ,0,0
       0    .055       0 1422.29    .035       0 1584.96    .055       0
Levee=-1,0,433.82,-1,2983,433.82,Levee 1,Levee 2
#XS Ineff= 2 , 0
       0 1422.29     405 1584.96       0     407
Permanent Ineff=
       F       F
Bank Sta=1422.29,1584.96
XS Rating Curve= 0 ,0
Exp/Cntr=0.3,0.1

Type RM Length L Ch R = 1 ,134309  ,202,194,190
BEGIN DESCRIPTION:
This cross section corresponds to cross section 134313 of the non-georeferenced CDC model which was the source of this model.
END DESCRIPTION:
XS GIS Cut Line= 2
2474863.244531516978645.260312962474156.997256346975755.07908547
#Sta/Elev= 30
       0     431   14.93     430   95.23     406  214.75     404   274.8     399
  478.32     406  617.61  402.11  726.36  401.98  985.31     402 1152.34  405.92
 1176.61     404 1280.45     404 1372.87     406 1391.81     404 1417.15     386
 1476.34     383 1514.17     383 1534.64     388 1570.83     407 1784.32  405.09
 2133.47     407 2203.73     402 2305.35  406.88 2503.24     407 2687.74     402
 2765.07     406 2815.38     406 2882.27     411 2953.27  430.96 2975.22  430.94
#Mann= 3 ,0,0
       0    .055       0 1372.87    .035       0 1570.83    .055       0
Levee=-1,0,433.77,-1,2963,433.77,Levee 1,Levee 2
#XS Ineff= 2 , 0
       0 1372.87     406 1570.83       0     407
Permanent Ineff=
       F       F
Bank Sta=1372.87,1570.83
XS Rating Curve= 0 ,0
Exp/Cntr=0.3,0.1

Type RM Length L Ch R = 1 ,134115  ,197,189,185
BEGIN DESCRIPTION:
This cross section corresponds to cross section 134121 of the non-georeferenced CDC model which was the source of this model.
END DESCRIPTION:
XS GIS Cut Line= 2
2475064.134549686978593.086860882474334.185222186975752.63027146
#Sta/Elev= 30
       0     431   14.59     430   82.97  408.15  106.14     404  198.96  402.63
  257.57     399  307.91     404  458.65     406  870.16     405 1034.78  402.14
 1210.97     406 1341.12     406 1366.53     391 1379.64  386.57 1439.54  378.08
 1497.21     383 1499.23  386.92 1520.61  396.89 1535.39     407 1683.56     405
 1947.45     405 2005.12     407 2182.51     407 2272.66  404.33 2322.34     407
 2672.44  403.59 2780.12     405 2848.38     409 2912.03  428.99 2932.75  431.88
#Mann= 3 ,0,0
       0    .055       0 1341.12    .035       0 1535.39    .055       0
Levee=-1,0,433.72,-1,2931,433.72,Levee 1,Levee 2
#XS Ineff= 2 , 0
       0 1341.12     406 1535.08       0   406.7
Permanent Ineff=
       F       F
Bank Sta=1341.12,1535.39
XS Rating Curve= 0 ,0
Exp/Cntr=0.3,0.1

Type RM Length L Ch R = 1 ,133926  ,197,188,185
BEGIN DESCRIPTION:
This cross section corresponds to cross section 133929 of the non-georeferenced CDC model which was the source of this model.
END DESCRIPTION:
XS GIS Cut Line= 2
 2475258.36972556978526.674592142474507.580872746975735.27991247
#Sta/Elev= 30
       0  431.17   16.13     430   95.81     405  119.93     402  224.99     399
   294.1     405  386.05  405.78   446.2     403  514.56     405  858.27     405
  891.77  401.24  915.09     404 1303.69     407 1311.24     402  1333.4     398
 1361.28  385.19 1391.79  380.24 1423.37  379.64 1466.47     381 1506.74     407
 1851.42  405.71 2012.18     402 2076.26     405  2293.9     408 2503.22     408
 2569.28     405  2752.2     404 2788.23     406 2831.32     415  2890.6  433.95
#Mann= 3 ,0,0
       0    .055       0 1303.69    .035       0 1506.74    .055       0
Levee=-1,0,433.67,-1,2891,433.67,Levee 1,Levee 2
#XS Ineff= 2 , 0
       0 1303.69     407 1506.74       0     407
Permanent Ineff=
       F       F
Bank Sta=1303.69,1506.74
XS Rating Curve= 0 ,0
Exp/Cntr=0.3,0.1

Type RM Length L Ch R = 1 ,133738  ,253,223,210
BEGIN DESCRIPTION:
This cross section corresponds to cross section 133738 of the non-georeferenced CDC model which was the source of this model.
END DESCRIPTION:
XS GIS Cut Line= 2
2475448.824725186978447.136365382474673.314465176975696.73832288
#Sta/Elev= 30
       0   430.9   19.01     429   85.87     408   109.3     404  166.14     400
  302.84     397   406.9     397  438.82     403  478.23     405  572.88     400
  683.41     403  1004.6  401.07 1078.76     405 1158.29  402.92 1203.25     406
 1294.13     406 1324.32     389 1369.03     380 1417.07     380 1458.97     399
 1486.09     407 1603.51     405 1898.25     407 2030.99     401 2134.02     405
 2451.68  407.89 2683.06     403 2769.06  408.35 2840.52     431 2857.64  432.65
#Mann= 3 ,0,0
       0    .055       0 1294.13    .035       0 1486.09    .055       0
Levee=-1,0,433.62,-1,2853,433.62,Levee 1,Levee 2
#XS Ineff= 2 , 0
       0 1294.13     406 1486.09       0     407
Permanent Ineff=
       F       F
Bank Sta=1294.13,1486.09
XS Rating Curve= 0 ,0
Exp/Cntr=0.3,0.1

Type RM Length L Ch R = 1 ,133515  ,252,220,208
BEGIN DESCRIPTION:
This cross section corresponds to cross section 133515 of the non-georeferenced CDC model which was the source of this model.
END DESCRIPTION:
XS GIS Cut Line= 2
2475702.735306596978331.928590552474835.012304516975661.44771105
#Sta/Elev= 30
       0     431   20.41  430.21   87.04     408  100.99     405  178.05     400
  438.21     397  550.54     404  626.11     401  679.13     404 1126.72     405
  1143.9     403  1190.6  406.79 1236.21   406.1 1265.28  403.38  1280.9     396
 1290.47     389 1297.03  387.21 1355.41     383 1404.74     382 1427.12     385
 1445.82     401 1473.88     407  1807.1     405 1835.34     400 2237.87     406
 2499.47     405 2545.81  402.23 2711.32  407.88 2787.35     431 2807.92   432.5
#Mann= 3 ,0,0
       0    .055       0 1236.21    .035       0 1473.88    .055       0
Levee=-1,0,433.55,-1,2801,433.55,Levee 1,Levee 2
#XS Ineff= 2 , 0
       0 1236.21   406.1 1473.88       0     407
Permanent Ineff=
       F       F
Bank Sta=1236.21,1473.88
XS Rating Curve= 0 ,0
Exp/Cntr=0.3,0.1

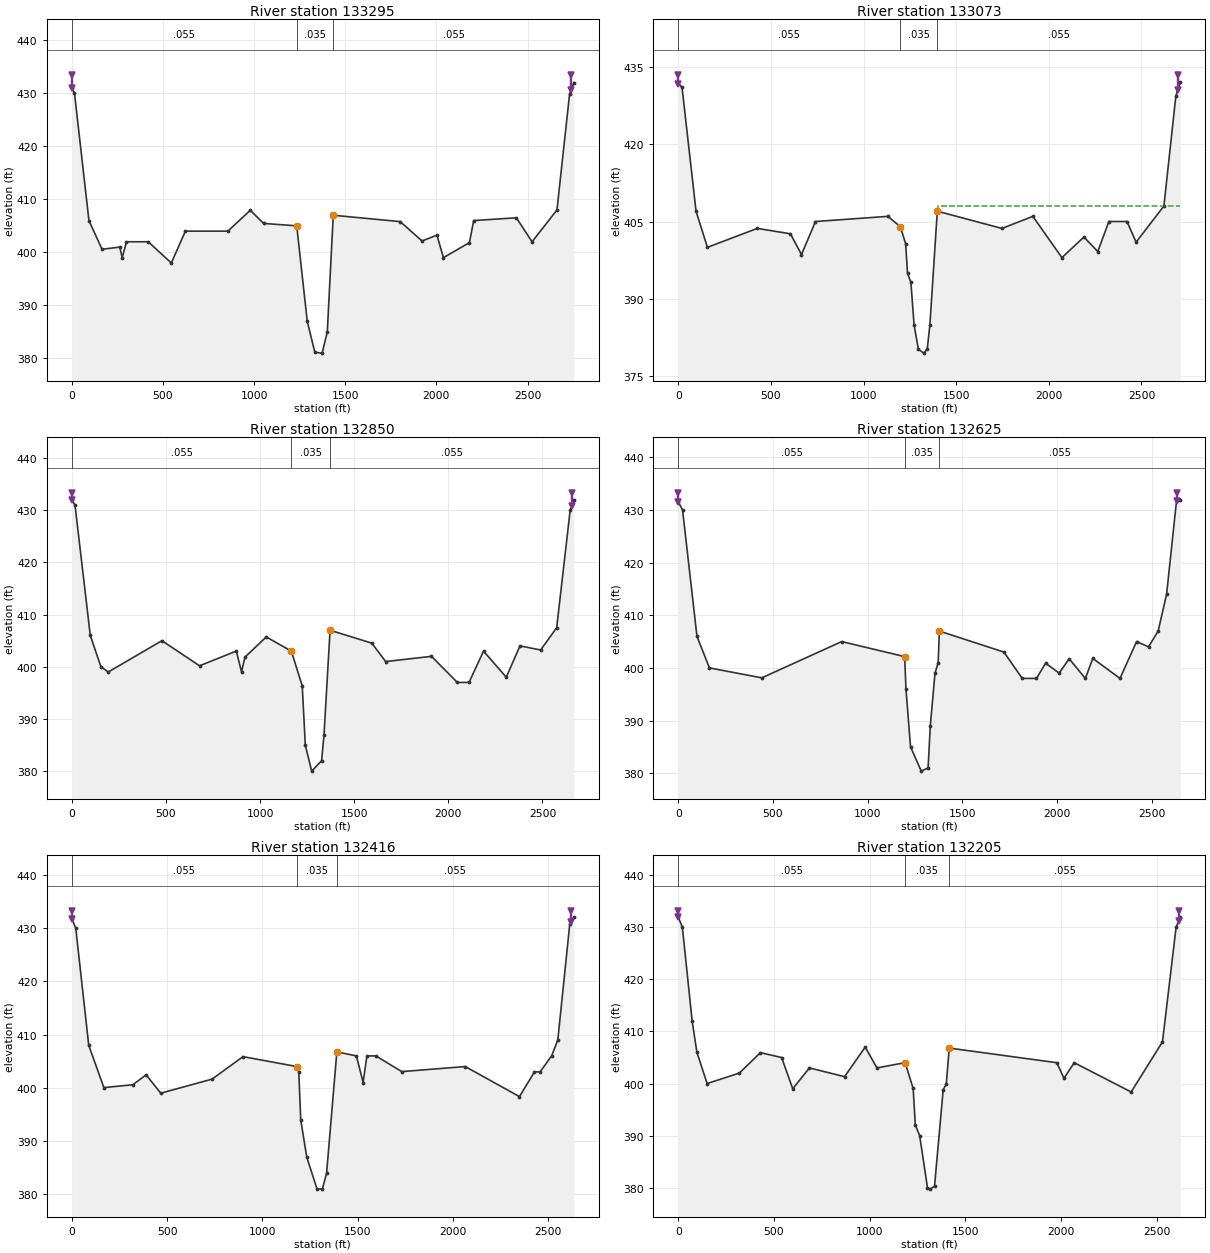
Type RM Length L Ch R = 1 ,133295  ,254,222,210
BEGIN DESCRIPTION:
This cross section corresponds to cross section 133293 of the non-georeferenced CDC model which was the source of this model.
END DESCRIPTION:
XS GIS Cut Line= 2
2475947.578977026978203.26611821 2474994.0418421 6975619.4172833
#Sta/Elev= 30
       0     431   14.95     430   94.17     406   166.1  400.58  263.35     401
  276.83     399  300.19     402  419.35     402  546.06     398  623.36     404
  855.98     404  979.33  407.93 1052.35  405.46 1234.05     405 1291.76     387
 1333.44  381.15 1373.41     381 1401.77     385 1434.36     407 1801.69   405.8
 1921.47  402.15 2003.12  403.25 2038.85     399 2181.55  401.85 2204.68     406
 2438.97  406.52 2525.01     402 2661.58     408 2730.65   429.8 2754.18     432
#Mann= 3 ,0,0
       0    .055       0 1234.05    .035       0 1434.36    .055       0
Levee=-1,0,433.48,-1,2740,433.48,Levee 1,Levee 2
#XS Ineff= 2 , 0
       0 1234.05     405 1434.36       0     407
Permanent Ineff=
       F       F
Bank Sta=1234.05,1434.36
XS Rating Curve= 0 ,0
Exp/Cntr=0.3,0.1

Type RM Length L Ch R = 1 ,133073  ,255,223,211
BEGIN DESCRIPTION:
This cross section corresponds to cross section 133071 of the non-georeferenced CDC model which was the source of this model.
END DESCRIPTION:
XS GIS Cut Line= 2
 2476190.44266456978064.769019892475148.14783308 6975563.5610958
#Sta/Elev= 30
       0   431.7   20.41     431   96.12     407  157.44     400  426.82  403.67
  605.48  402.62  665.18   398.6  740.68     405  1131.1     406 1198.46     404
 1227.38  400.71 1237.41     395 1255.78   393.2 1272.81     385  1296.2  380.27
 1325.28  379.51 1344.12  380.39 1358.23     385  1398.2     407 1747.01  403.66
 1914.01     406 2070.65     398 2189.51     402 2264.36  399.18 2324.05     405
 2422.13     405  2471.1     401 2621.18     408 2685.56  429.28 2709.69     432
#Mann= 3 ,0,0
       0    .055       0 1198.46    .035       0  1398.2    .055       0
Levee=-1,0,433.41,-1,2696,433.41,Levee 1,Levee 2
#XS Ineff= 2 , 0
       0 1198.46     404 1400.52       0     408
Permanent Ineff=
       F       F
Bank Sta=1198.46,1398.2
XS Rating Curve= 0 ,0
Exp/Cntr=0.3,0.1

Type RM Length L Ch R = 1 ,132850  ,258,225,213
BEGIN DESCRIPTION:
This cross section corresponds to cross section 132849 of the non-georeferenced CDC model which was the source of this model.
END DESCRIPTION:
XS GIS Cut Line= 2
2476429.079982526977915.322140312475298.234475176975500.17047454
#Sta/Elev= 30
       0     432    17.2     431   98.32     406  154.89     400  193.87     399
  478.93     405   678.8  400.19     874  403.01  901.59  399.02  919.96  401.85
 1033.06  405.72 1166.42     403 1224.24  396.32 1240.36     385 1274.31     380
 1327.05     382 1339.81     387 1371.94     407 1593.66  404.53 1667.37     401
  1910.7     402 2047.71     397 2109.93     397 2187.16     403 2307.83     398
 2380.64     404 2490.43  403.22 2575.66  407.49 2647.19     430 2666.79     432
#Mann= 3 ,0,0
       0    .055       0 1166.42    .035       0 1371.94    .055       0
Levee=-1,0,433.34,-1,2655,433.34,Levee 1,Levee 2
#XS Ineff= 2 , 0
       0 1166.42     403 1371.94       0     407
Permanent Ineff=
       F       F
Bank Sta=1166.42,1371.94
XS Rating Curve= 0 ,0
Exp/Cntr=0.3,0.1

Type RM Length L Ch R = 1 ,132625  ,208,209,208
BEGIN DESCRIPTION:
This cross section corresponds to cross section 132627 of the non-georeferenced CDC model which was the source of this model.
END DESCRIPTION:
XS GIS Cut Line= 2
2476672.885269176977773.963171052475442.394948016975424.75363064
#Sta/Elev= 30
       0  431.58   22.92     430   98.86     406  164.57     400  441.36  398.11
  863.49     405 1196.02  402.14 1202.85     396 1226.95     385 1283.54  380.38
 1319.73     381  1331.4  388.98 1356.29     399 1373.19     401  1379.1     407
 1720.56     403 1816.86     398 1892.29     398 1940.45   400.9 2011.91     399
 2064.83  401.74 2150.46     398 2189.73   401.8 2333.28     398 2421.12     405
 2484.07     404 2534.92     407 2579.54     414 2632.37  431.87 2651.96     432
#Mann= 3 ,0,0
       0    .055       0 1196.02    .035       0  1379.1    .055       0
Levee=-1,0,433.27,-1,2632,433.27,Levee 1,Levee 2
#XS Ineff= 2 , 0
       0 1196.02  402.14  1379.1       0     407
Permanent Ineff=
       F       F
Bank Sta=1196.02,1379.1
XS Rating Curve= 0 ,0
Exp/Cntr=0.3,0.1

Type RM Length L Ch R = 1 ,132416  ,210,211,210
BEGIN DESCRIPTION:
This cross section corresponds to cross section 132417 of the non-georeferenced CDC model which was the source of this model.
END DESCRIPTION:
XS GIS Cut Line= 2
2476851.747116186977661.932883292475621.420508596975333.31483713
#Sta/Elev= 30
       0  431.74    20.8     430   88.91     408  168.32  400.05  320.53  400.59
  389.89  402.45  466.83     399  735.99  401.64  898.22  405.86 1180.56     404
 1190.83     403 1200.99     394 1232.68     387 1286.85     381 1314.34     381
 1336.71     384 1390.49  406.75 1493.16     406 1528.27     401  1548.2     406
 1594.88     406 1731.18  403.05 2064.05     404  2348.4  398.36 2427.12     403
 2456.64     403 2517.12     406 2549.56     409 2612.48  430.82 2633.66  431.99
#Mann= 3 ,0,0
       0    .055       0 1180.56    .035       0 1390.49    .055       0
Levee=-1,0,433.22,-1,2618,433.22,Levee 1,Levee 2
#XS Ineff= 2 , 0
       0 1180.56     404 1390.49       0  406.75
Permanent Ineff=
       F       F
Bank Sta=1180.56,1390.49
XS Rating Curve= 0 ,0
Exp/Cntr=0.3,0.1

Type RM Length L Ch R = 1 ,132205  ,210,210,210
BEGIN DESCRIPTION:
This cross section corresponds to cross section 132207 of the non-georeferenced CDC model which was the source of this model.
END DESCRIPTION:
XS GIS Cut Line= 2
2477036.049241016977556.132898052475802.39980543 6975240.7113478
#Sta/Elev= 30
       0     432   21.66     430   72.71     412    97.5     406  151.01     400
  319.14     402  429.44  405.93  540.15     405  598.34     399  685.67     403
  869.08  401.32  977.05     407 1038.29     403 1185.46  404.01 1227.61  399.05
 1238.93     392 1261.56     390 1302.46     380 1317.25  379.72 1339.28  380.31
 1384.67  398.84 1400.57  399.88 1416.13  406.81 1978.39     404  2015.5     401
  2069.2     404 2366.57  398.38 2530.35     408  2601.5     430 2623.56  431.97
#Mann= 3 ,0,0
       0    .055       0 1185.46    .035       0 1416.13    .055       0
Levee=-1,0,433.17,-1,2615,433.17,Levee 1,Levee 2
#XS Ineff= 2 , 0
       0 1185.46  404.01 1416.13       0  406.81
Permanent Ineff=
       F       F
Bank Sta=1185.46,1416.13
XS Rating Curve= 0 ,0
Exp/Cntr=0.3,0.1

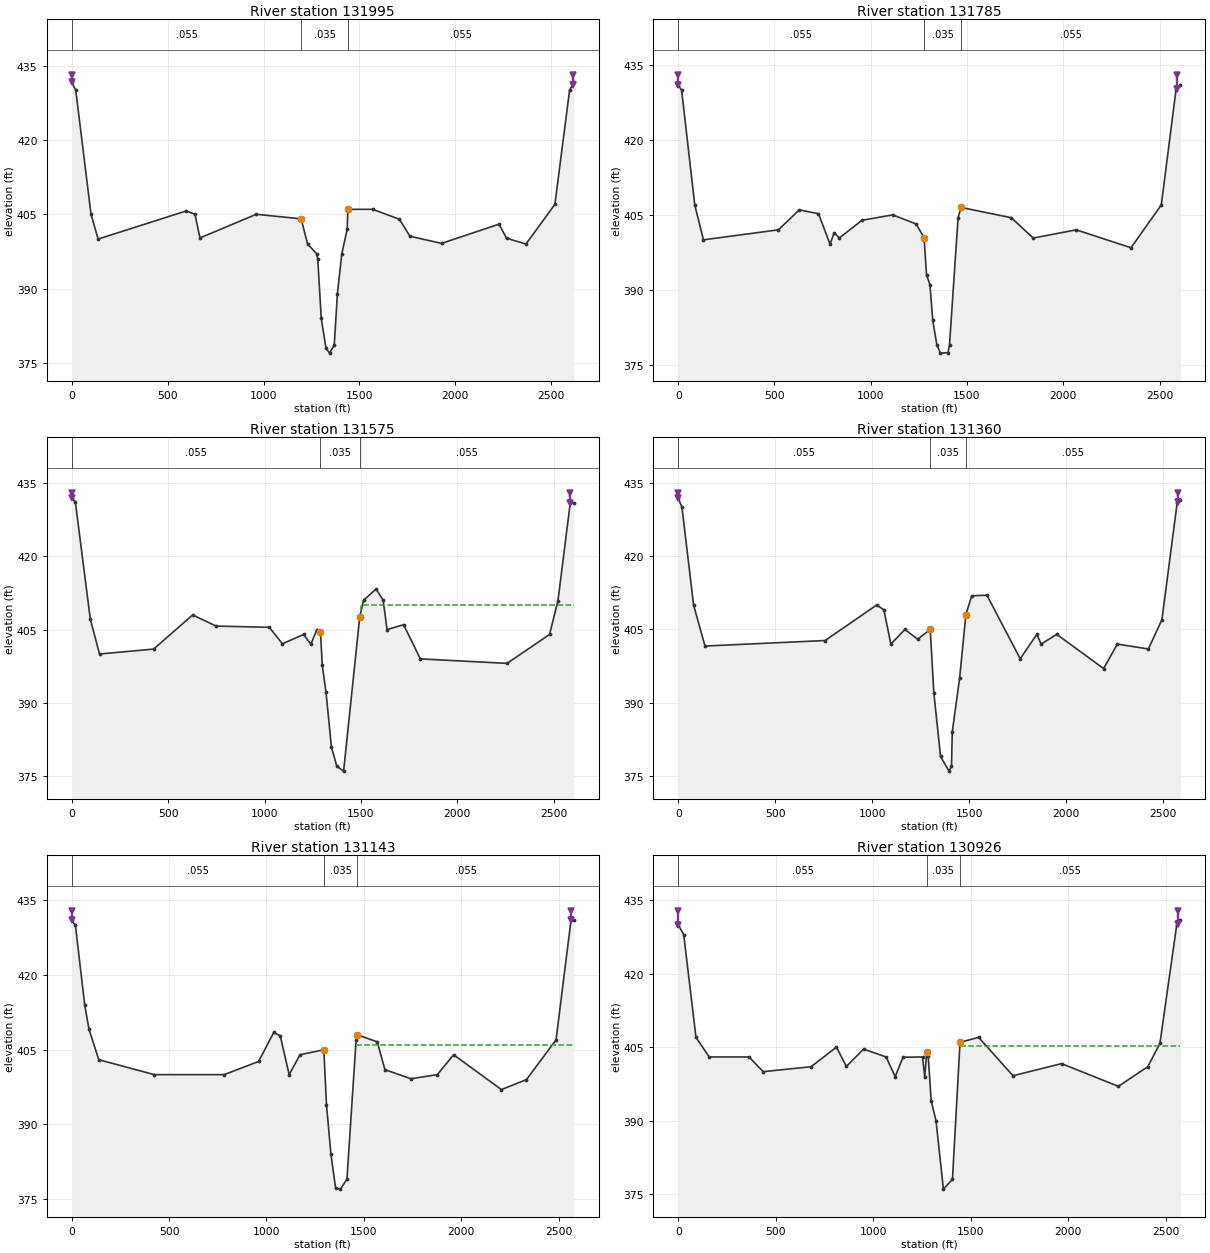
Type RM Length L Ch R = 1 ,131995  ,210,210,210
BEGIN DESCRIPTION:
This cross section corresponds to cross section 131998 of the non-georeferenced CDC model which was the source of this model.
END DESCRIPTION:
XS GIS Cut Line= 2
  2477219.5567486977448.828650712475979.97622192 6975143.2509128
#Sta/Elev= 30
       0  431.61   20.91     430  100.35     405   137.3     400  596.45  405.67
  642.35     405  668.23  400.23   962.2     405 1195.88  404.08 1229.56     399
 1276.83  397.04  1282.5     396 1300.71     384 1325.46     378 1343.88     377
 1368.45   378.6 1384.94     389  1407.8     397 1435.92     402 1439.45     406
 1568.91     406 1708.39     404 1763.25  400.57 1928.01  399.13 2227.42     403
 2266.94  400.17 2368.04     399 2518.85  406.99 2595.37     430 2617.68  431.63
#Mann= 3 ,0,0
       0    .055       0 1195.88    .035       0 1439.45    .055       0
Levee=-1,0,433.12,-1,2611,433.12,Levee 1,Levee 2
#XS Ineff= 2 , 0
       0 1195.88  404.08 1439.45       0     406
Permanent Ineff=
       F       F
Bank Sta=1195.88,1439.45
XS Rating Curve= 0 ,0
Exp/Cntr=0.3,0.1

Type RM Length L Ch R = 1 ,131785  ,211,210,211
BEGIN DESCRIPTION:
This cross section corresponds to cross section 131788 of the non-georeferenced CDC model which was the source of this model.
END DESCRIPTION:
XS GIS Cut Line= 2
2477405.853291426977343.837390882476161.534585836975051.74223755
#Sta/Elev= 30
       0     431    17.6     430   85.74     407  130.98     400  520.14     402
  628.83     406  728.55  405.24  788.56  399.11  810.08  401.44   836.7  400.37
  954.74  403.92 1114.66     405 1235.99  403.17 1277.11   400.4 1289.77     393
 1307.62     391 1322.18  383.84  1343.2     379 1361.95  377.29 1401.54  377.39
 1409.21     379 1453.51  404.35 1468.62   406.5 1729.96  404.43 1843.98  400.36
  2067.7     402 2351.96  398.41 2509.37     407 2585.47     430 2608.07     431
#Mann= 3 ,0,0
       0    .055       0 1277.11    .035       0 1468.62    .055       0
Levee=-1,0,433.07,-1,2589,433.07,Levee 1,Levee 2
#XS Ineff= 2 , 0
       0 1277.11   400.4 1468.62       0   406.5
Permanent Ineff=
       F       F
Bank Sta=1277.11,1468.62
XS Rating Curve= 0 ,0
Exp/Cntr=0.3,0.1

Type RM Length L Ch R = 1 ,131575  ,215,215,215
BEGIN DESCRIPTION:
This cross section corresponds to cross section 131579 of the non-georeferenced CDC model which was the source of this model.
END DESCRIPTION:
XS GIS Cut Line= 2
2477590.121623676977236.017724632476340.477141356974951.52819914
#Sta/Elev= 30
       0     432   18.85  431.08   96.02  407.17  143.89     400  424.31     401
  626.83     408  748.79  405.72 1024.59  405.47 1092.47  402.08 1202.31     404
  1240.1     402 1271.11     405 1289.75  404.53 1299.24  397.69 1318.66  392.14
 1346.53     381 1374.45     377 1409.86     376  1493.7  407.67 1513.17     411
 1578.33  413.33 1615.11     411 1635.15     405 1720.99     406 1807.91     399
 2257.43  398.08 2477.94     404 2521.63  410.94 2585.48     431 2603.94     431
#Mann= 3 ,0,0
       0    .055       0 1289.75    .035       0  1493.7    .055       0
Levee=-1,0,433.02,-1,2585,433.02,Levee 1,Levee 2
#XS Ineff= 2 , 0
       0 1289.75  404.53 1500.88       0     410
Permanent Ineff=
       F       F
Bank Sta=1289.75,1493.7
XS Rating Curve= 0 ,0
Exp/Cntr=0.3,0.1

Type RM Length L Ch R = 1 ,131360  ,218,217,218
BEGIN DESCRIPTION:
This cross section corresponds to cross section 131361 of the non-georeferenced CDC model which was the source of this model.
END DESCRIPTION:
XS GIS Cut Line= 2
2477777.637980916977125.75777455 2476531.28286216974857.03855872
#Sta/Elev= 30
       0   431.9   19.23     430   79.11     410  137.96   401.6  757.13  402.73
 1023.12     410 1060.12  409.02 1096.35     402 1168.58     405  1234.4     403
 1299.16     405 1317.85  392.02  1352.3     379 1396.16     376 1408.85     377
 1412.74     384 1451.07  395.16  1482.9     408  1513.1  411.89 1591.47     412
 1763.07     399 1848.86     404 1871.21     402 1951.34     404 2193.04     397
 2263.93     402 2423.91     401 2493.68     407  2572.2  430.87 2588.53  431.42
#Mann= 3 ,0,0
       0    .055       0 1299.16    .035       0  1482.9    .055       0
Levee=-1,0,432.96,-1,2576,432.96,Levee 1,Levee 2
#XS Ineff= 2 , 0
       0 1299.16     405  1482.9       0     408
Permanent Ineff=
       F       F
Bank Sta=1299.16,1482.9
XS Rating Curve= 0 ,0
Exp/Cntr=0.3,0.1

Type RM Length L Ch R = 1 ,131143  ,217,217,217
BEGIN DESCRIPTION:
This cross section corresponds to cross section 131144 of the non-georeferenced CDC model which was the source of this model.
END DESCRIPTION:
XS GIS Cut Line= 2
2477966.863324256977013.939100552476721.093834166974756.33600421
#Sta/Elev= 30
       0     431   18.76     430   66.53     414   88.47  409.12  138.89     403
  424.03     400  782.69     400  959.57  402.65 1037.22  408.48 1070.77  407.79
 1116.43     400 1172.44     404 1294.44     405 1308.05     394 1331.07     384
  1354.9  377.24 1380.05     377 1413.23     379 1460.21  406.94 1465.86     408
 1568.68   406.6 1608.44     401 1741.86  399.18 1877.45     400 1961.06     404
 2206.44     397 2335.08     399 2487.24     407  2563.9     431 2578.51     431
#Mann= 3 ,0,0
       0    .055       0 1294.44    .035       0 1465.86    .055       0
Levee=-1,0,432.91,-1,2564,432.91,Levee 1,Levee 2
#XS Ineff= 2 , 0
       0 1294.44     405 1458.44       0  405.91
Permanent Ineff=
       F       F
Bank Sta=1294.44,1465.86
XS Rating Curve= 0 ,0
Exp/Cntr=0.3,0.1

Type RM Length L Ch R = 1 ,130926  ,221,220,221
BEGIN DESCRIPTION:
This cross section corresponds to cross section 130926 of the non-georeferenced CDC model which was the source of this model.
END DESCRIPTION:
XS GIS Cut Line= 2
2478159.452506016976908.186031222476910.719767246974656.00451197
#Sta/Elev= 30
       0     430   28.07     428   90.96     407  158.86     403   363.3     403
  435.68     400  681.14     401  811.41     405  862.42  401.06  950.55  404.61
 1065.92     403 1112.81     399 1152.94  402.95 1253.03     403 1264.14     399
 1274.92     404 1281.88  403.27 1297.64     394  1322.1     390 1360.17     376
 1406.54     378 1445.32     406  1540.8     407  1717.1  399.16  1965.8  401.64
 2257.76     397 2407.97     401 2470.64  405.76 2556.91     430  2575.2     431
#Mann= 3 ,0,0
       0    .055       0 1274.92    .035       0 1445.32    .055       0
Levee=-1,0,432.85,-1,2561,432.85,Levee 1,Levee 2
#XS Ineff= 2 , 0
       0 1274.92     404 1444.21       0  405.22
Permanent Ineff=
       F       F
Bank Sta=1274.92,1445.32
XS Rating Curve= 0 ,0
Exp/Cntr=0.3,0.1

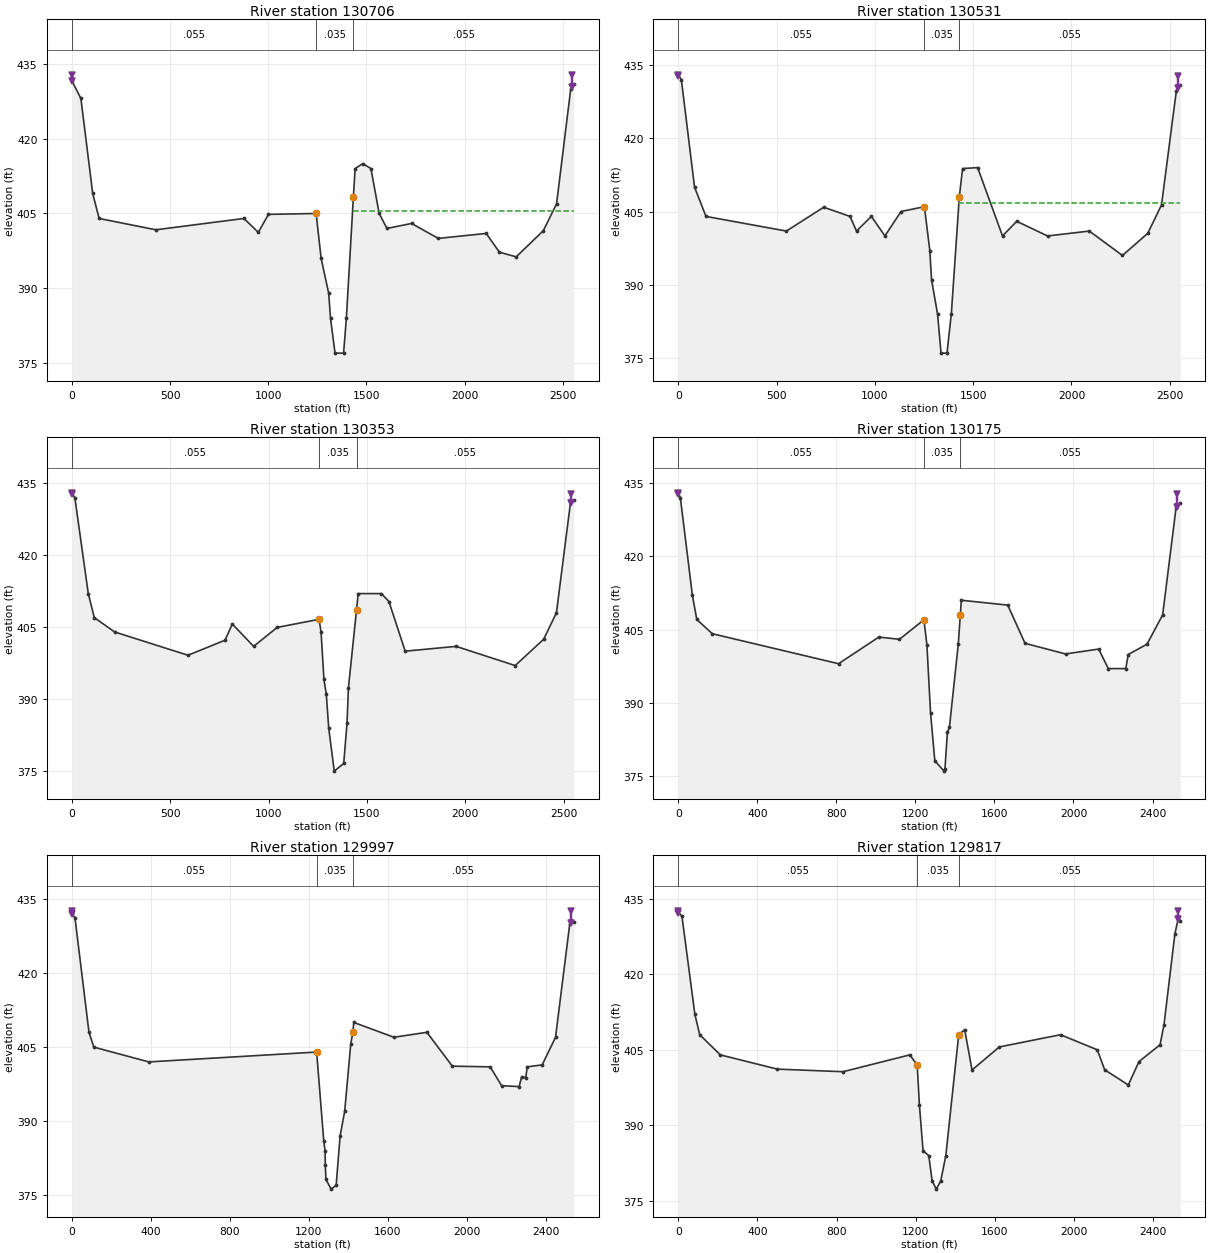
Type RM Length L Ch R = 1 ,130706  ,175,175,175
BEGIN DESCRIPTION:
This cross section corresponds to cross section 130709 of the non-georeferenced CDC model which was the source of this model.
END DESCRIPTION:
XS GIS Cut Line= 2
 2478345.9934715 6976785.35983332477102.600617086974552.85150304
#Sta/Elev= 30
       0  431.64   46.34  428.07  106.41  409.05  139.12     404  427.72  401.73
  876.29     404  949.34  401.22 1001.23  404.82 1243.58     405 1269.18     396
 1307.63     389 1316.86     384 1339.98     377 1383.45     377 1397.61     384
 1433.28  408.27 1442.12     414 1481.17     415 1522.59     414 1564.56     405
 1604.29     402 1729.53     403 1865.44     400 2109.35     401 2176.42  397.25
 2261.73   396.3 2399.91  401.54 2467.47  406.93 2539.72     430 2555.41     431
#Mann= 3 ,0,0
       0    .055       0 1243.58    .035       0 1433.28    .055       0
Levee=-1,0,432.8,-1,2546,432.8,Levee 1,Levee 2
#XS Ineff= 2 , 0
       0 1243.58     405 1429.18       0  405.58
Permanent Ineff=
       F       F
Bank Sta=1243.58,1433.28
XS Rating Curve= 0 ,0
Exp/Cntr=0.3,0.1

Type RM Length L Ch R = 1 ,130531  ,179,178,179
BEGIN DESCRIPTION:
This cross section corresponds to cross section 130531 of the non-georeferenced CDC model which was the source of this model.
END DESCRIPTION:
XS GIS Cut Line= 2
2478498.079453416976698.122474972477254.733514936974467.57969196
#Sta/Elev= 30
       0     433   15.96     432   82.88     410  141.17     404  549.98     401
  739.73  405.88   873.8     404  906.73     401  982.35     404 1051.24     400
 1133.02     405 1251.98     406 1279.62     397 1288.45     391 1318.99     384
 1336.64     376 1366.96     376 1388.95     384 1429.65     408 1446.33   413.8
 1522.69     414 1649.37     400 1721.65     403 1878.28     400 2091.04     401
  2259.3     396 2388.31  400.55 2458.12  406.36 2533.55  429.73 2553.67   430.9
#Mann= 3 ,0,0
       0    .055       0 1251.98    .035       0 1429.65    .055       0
Levee=-1,0,432.76,-1,2542,432.76,Levee 1,Levee 2
#XS Ineff= 2 , 0
       0 1251.98     406 1427.13       0  406.81
Permanent Ineff=
       F       F
Bank Sta=1251.98,1429.65
XS Rating Curve= 0 ,0
Exp/Cntr=0.3,0.1

Type RM Length L Ch R = 1 ,130353  ,178,178,178
BEGIN DESCRIPTION:
This cross section corresponds to cross section 130354 of the non-georeferenced CDC model which was the source of this model.
END DESCRIPTION:
XS GIS Cut Line= 2
2478653.27730575 6976610.30309682477409.834254596974382.89449388
#Sta/Elev= 30
       0     433   15.63     432   83.88     412  114.36     407  217.82     404
  590.48  399.15  778.58  402.28  815.74  405.66  924.01     401 1043.72  404.95
 1256.27  406.64 1266.66     404 1281.23  394.11 1293.22  391.04 1305.44     384
 1333.72     375 1381.75  376.61 1398.53  384.97  1405.6  392.33 1446.68  408.53
 1455.45     412 1573.48     412 1611.41  410.34 1694.07     400 1952.89     401
 2252.81     397 2397.56  402.48  2462.5     408 2534.05     431 2550.98  431.47
#Mann= 3 ,0,0
       0    .055       0 1256.27    .035       0 1446.68    .055       0
Levee=-1,0,432.71,-1,2534,432.71,Levee 1,Levee 2
#XS Ineff= 2 , 0
       0 1256.27  406.64 1439.11       0  405.54
Permanent Ineff=
       F       F
Bank Sta=1256.27,1446.68
XS Rating Curve= 0 ,0
Exp/Cntr=0.3,0.1

Type RM Length L Ch R = 1 ,130175  ,179,178,179
BEGIN DESCRIPTION:
This cross section corresponds to cross section 130176 of the non-georeferenced CDC model which was the source of this model.
END DESCRIPTION:
XS GIS Cut Line= 2
 2478802.53225666976511.845288472477562.755208586974294.27885747
#Sta/Elev= 30
       0     433   10.78     432   71.38  412.05   93.89  407.06  172.46  404.14
  811.15     398 1015.33  403.46 1119.48     403 1243.25     407 1258.37  401.85
 1276.59     388 1298.34  378.14 1344.61     376  1349.7  376.47    1362  383.94
 1372.28     385 1417.11     402 1427.42     408 1432.35     411 1667.32     410
 1755.04  402.17 1959.77     400 2127.56     401 2176.34     397 2264.82     397
 2276.86  399.88 2372.12     402 2451.28     408 2518.78  429.86  2540.6  430.83
#Mann= 3 ,0,0
       0    .055       0 1243.25    .035       0 1427.42    .055       0
Levee=-1,0,432.66,-1,2525,432.66,Levee 1,Levee 2
#XS Ineff= 2 , 0
       0 1243.25     407 1426.09       0  407.22
Permanent Ineff=
       F       F
Bank Sta=1243.25,1427.42
XS Rating Curve= 0 ,0
Exp/Cntr=0.3,0.1

Type RM Length L Ch R = 1 ,129997  ,181,180,181
BEGIN DESCRIPTION:
This cross section corresponds to cross section 129999 of the non-georeferenced CDC model which was the source of this model.
END DESCRIPTION:
XS GIS Cut Line= 2
2478960.443358096976428.870716882477718.399910426974210.55559972
#Sta/Elev= 30
       0     432   16.18  431.23   87.16     408  111.79     405     390     402
    1240     404 1275.97     386 1282.74     384 1283.73  381.16 1287.02   378.2
 1313.32  376.22 1338.75     377 1358.85     387 1381.96     392 1412.87  405.67
 1423.08     408  1428.1     410 1631.15     407 1798.34     408 1927.14  401.14
  2118.7     401 2176.74  397.18 2265.38     397 2277.97     399 2298.76  398.81
 2306.45     401 2382.08   401.4 2449.67     407 2521.73     430 2542.36  430.39
#Mann= 3 ,0,0
       0    .055       0    1240    .035       0 1423.08    .055       0
Levee=-1,0,432.62,-1,2527,432.62,Levee 1,Levee 2
#XS Ineff= 2 , 0
       0    1240  393.81  1428.1       0     410
Permanent Ineff=
       F       F
Bank Sta=1240,1423.08
XS Rating Curve= 0 ,0
Exp/Cntr=0.3,0.1

Type RM Length L Ch R = 1 ,129817  ,174,177,174
BEGIN DESCRIPTION:
This cross section corresponds to cross section 129822 of the non-georeferenced CDC model which was the source of this model.
END DESCRIPTION:
XS GIS Cut Line= 2
2479114.10118726 6976333.8863268  2477873.7877236974120.83727522
#Sta/Elev= 30
       0  432.17   18.51  431.59      84  412.05  108.59     408  212.53     404
  500.93  401.17  832.91  400.66 1170.21     404  1207.4     402 1218.53   394.1
 1236.96     385 1266.01     384 1282.61  379.05 1303.88  377.36 1326.42     379
 1352.02     384 1417.26     408 1447.37     409 1484.53     401 1622.39  405.57
 1931.58     408 2117.69     405 2154.64  401.04 2274.14  398.03 2328.24  402.68
 2434.56     406 2454.55     410 2509.56     428 2526.03     431 2536.92  430.62
#Mann= 3 ,0,0
       0    .055       0  1207.4    .035       0 1417.26    .055       0
Levee=-1,0,432.58,-1,2526,432.58,Levee 1,Levee 2
#XS Ineff= 2 , 0
       0  1207.4     402 1417.26       0     408
Permanent Ineff=
       F       F
Bank Sta=1207.4,1417.26
XS Rating Curve= 0 ,0
Exp/Cntr=0.3,0.1

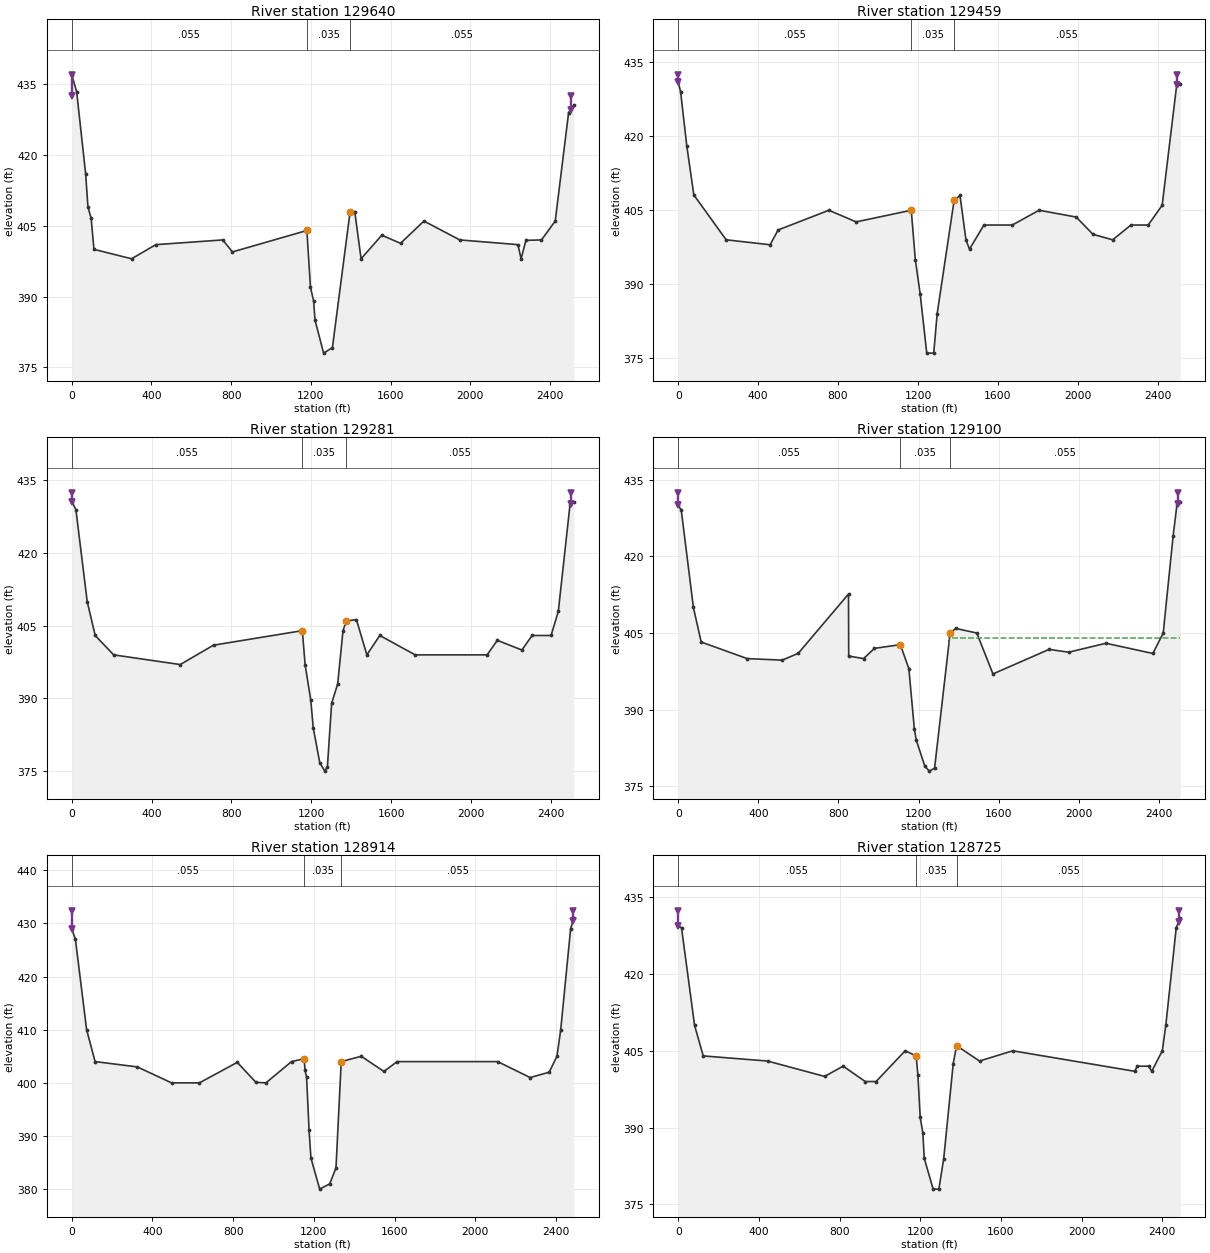
Type RM Length L Ch R = 1 ,129640  ,179,181,179
BEGIN DESCRIPTION:
This cross section corresponds to cross section 129642 of the non-georeferenced CDC model which was the source of this model.
END DESCRIPTION:
XS GIS Cut Line= 2
2479258.34728983 6976232.60700182478026.54201066 6974034.6212403
#Sta/Elev= 30
       0     437   24.51  433.41   69.65     416   81.13     409   97.11   406.6
  111.39     400     300     398  422.17     401  758.12     402  806.09  399.45
 1179.89     404 1197.75  392.01 1213.91     389 1220.76     385 1263.84     378
 1308.06  379.18 1396.79     408 1420.14     408 1451.87     398 1555.76     403
  1649.8  401.28 1767.32     406 1947.18     402 2239.03     401 2254.89     398
 2279.09  401.91 2357.25     402 2426.24     406 2493.36     429 2519.62  430.57
#Mann= 3 ,0,0
       0    .055       0 1179.89    .035       0 1396.79    .055       0
Levee=-1,0,432.54,-1,2503,432.54,Levee 1,Levee 2
#XS Ineff= 2 , 0
       0 1179.89     404 1391.82       0     406
Permanent Ineff=
       F       F
Bank Sta=1179.89,1396.79
XS Rating Curve= 0 ,0
Exp/Cntr=0.3,0.1

Type RM Length L Ch R = 1 ,129459  ,177,178,177
BEGIN DESCRIPTION:
This cross section corresponds to cross section 129463 of the non-georeferenced CDC model which was the source of this model.
END DESCRIPTION:
XS GIS Cut Line= 2
2479415.392251346976149.759070382478187.263802086973957.08399379
#Sta/Elev= 30
       0     431   11.74  429.09   43.05     418   78.07  408.11     240     399
     460     398     500     401  753.99     405  890.59  402.64  1166.4     405
 1186.69     395 1211.08     388    1244     376 1278.91     376 1296.08     384
 1381.01     407 1410.45     408 1440.13     399 1457.96   397.1 1529.99     402
 1672.08     402 1806.33     405 1992.09  403.62 2076.27  400.11 2174.69     399
 2265.93     402  2352.3     402 2422.32     406 2495.03  430.38 2513.19  430.72
#Mann= 3 ,0,0
       0    .055       0  1166.4    .035       0 1381.01    .055       0
Levee=-1,0,432.49,-1,2495,432.49,Levee 1,Levee 2
#XS Ineff= 2 , 0
       0  1166.4     405 1381.01       0     407
Permanent Ineff=
       F       F
Bank Sta=1166.4,1381.01
XS Rating Curve= 0 ,0
Exp/Cntr=0.3,0.1

Type RM Length L Ch R = 1 ,129281  ,179,181,179
BEGIN DESCRIPTION:
This cross section corresponds to cross section 129284 of the non-georeferenced CDC model which was the source of this model.
END DESCRIPTION:
XS GIS Cut Line= 2
2479573.033668346976067.985283812478344.520377346973873.39387247
#Sta/Elev= 30
       0  430.65   20.63     429   77.29     410  117.33     403  209.84     399
  543.27     397     710     401    1155     404 1168.85     397 1197.41  389.59
 1209.39     384 1242.29  376.73  1267.7     375 1280.67  375.95 1301.74     389
 1332.02     393 1358.57  403.95  1374.6     406    1426  406.27  1478.2     399
 1542.96     403 1720.22     399 2080.43     399 2131.85     402 2254.75     400
 2305.96     403 2401.08     403  2437.3     408  2495.8     430 2515.05   430.5
#Mann= 3 ,0,0
       0    .055       0    1155    .035       0  1374.6    .055       0
Levee=-1,0,432.45,-1,2501,432.45,Levee 1,Levee 2
#XS Ineff= 2 , 0
       0    1155  398.83 1358.57       0  403.95
Permanent Ineff=
       F       F
Bank Sta=1155,1374.6
XS Rating Curve= 0 ,0
Exp/Cntr=0.3,0.1

Type RM Length L Ch R = 1 ,129100  ,184,186,187
BEGIN DESCRIPTION:
This cross section corresponds to cross section 129105 of the non-georeferenced CDC model which was the source of this model.
END DESCRIPTION:
XS GIS Cut Line= 2
 2479728.11669156975976.512697712478504.646041336973788.94292589
#Sta/Elev= 30
       0     430    15.2     429   75.68     410  114.62  403.24  344.07     400
     519   399.7     599  401.03     850  412.62     851   400.5  925.27     400
  979.61     402 1108.86  402.73 1151.48     398 1178.86  386.17 1188.82     384
 1230.87     379 1253.34     378  1279.8  378.59 1357.37     405 1385.09   405.9
  1490.4     405 1571.21     397 1851.33   401.8 1949.39  401.25 2135.34     403
 2369.38     401 2421.17     405 2470.65     424 2489.51     430 2506.46   430.6
#Mann= 3 ,0,0
       0    .055       0 1108.86    .035       0 1357.37    .055       0
Levee=-1,0,432.41,-1,2494,432.41,Levee 1,Levee 2
#XS Ineff= 2 , 0
       0 1108.86  402.73 1351.81       0     404
Permanent Ineff=
       F       F
Bank Sta=1108.86,1357.37
XS Rating Curve= 0 ,0
Exp/Cntr=0.3,0.1

Type RM Length L Ch R = 1 ,128914  ,187,189,190
BEGIN DESCRIPTION:
This cross section corresponds to cross section 128916 of the non-georeferenced CDC model which was the source of this model.
END DESCRIPTION:
XS GIS Cut Line= 2
2479879.359171186975879.822930472478676.222797936973701.49920313
#Sta/Elev= 30
       0     429   18.06     427   73.58     410  115.59     404  324.71     403
  494.31     400  632.88     400  820.34  403.86  912.68  400.09  962.59     400
 1089.16     404 1152.36  404.55 1155.66  402.45 1163.83  401.06 1176.05  391.18
 1185.35  385.86 1228.92     380 1278.63     381 1309.55     384 1335.56     404
 1434.97     405 1547.17  402.14 1612.59     404 2110.87     404 2271.82     401
 2366.29     402 2404.75     405 2423.32  409.95 2472.55     429  2488.5     431
#Mann= 3 ,0,0
       0    .055       0 1152.36    .035       0 1335.56    .055       0
Levee=-1,0,432.37,-1,2484,432.37,Levee 1,Levee 2
#XS Ineff= 2 , 0
       0 1152.36  404.55 1335.56       0     404
Permanent Ineff=
       F       F
#XS Lid=6
     920  419.12  413.72   921.7  419.12  413.72  921.71  419.12  418.42
  954.29  419.12  418.42   954.3  419.12  413.72     956  419.12  413.72
Bank Sta=1152.36,1335.56
XS Rating Curve= 0 ,0
Exp/Cntr=0.3,0.1

Type RM Length L Ch R = 1 ,128725  ,189,192,193
BEGIN DESCRIPTION:
This cross section corresponds to cross section 128727 of the non-georeferenced CDC model which was the source of this model.
END DESCRIPTION:
XS GIS Cut Line= 2
2480040.092445496975795.140357052478848.293319916973609.11192071
#Sta/Elev= 30
       0  429.42   16.35     429    80.8     410  123.95     404  442.89     403
  725.92     400  817.82     402  927.52     399  980.99     399 1125.34     405
  1179.8     404 1188.28  400.37 1199.99     392 1212.95     389 1219.89  384.04
 1263.99     378 1292.43     378 1316.52  383.94 1363.62  402.48 1380.36     406
 1494.01     403  1658.6     405  2263.7     401 2276.34     402 2332.57     402
  2348.2     401 2400.46     405 2417.96     410 2469.48  428.98  2489.8  430.96
#Mann= 3 ,0,0
       0    .055       0  1179.8    .035       0 1380.36    .055       0
Levee=-1,0,432.32,-1,2482,432.32,Levee 1,Levee 2
#XS Ineff= 2 , 0
       0  1179.8     404 1380.36       0     406
Permanent Ineff=
       F       F
#XS Lid=6
     920  428.46  423.06   921.7  428.46  423.06  921.71  428.46  427.76
  954.29  428.46  427.76   954.3  428.46  423.06     956  428.46  423.06
Bank Sta=1179.8,1380.36
XS Rating Curve= 0 ,0
Exp/Cntr=0.3,0.1