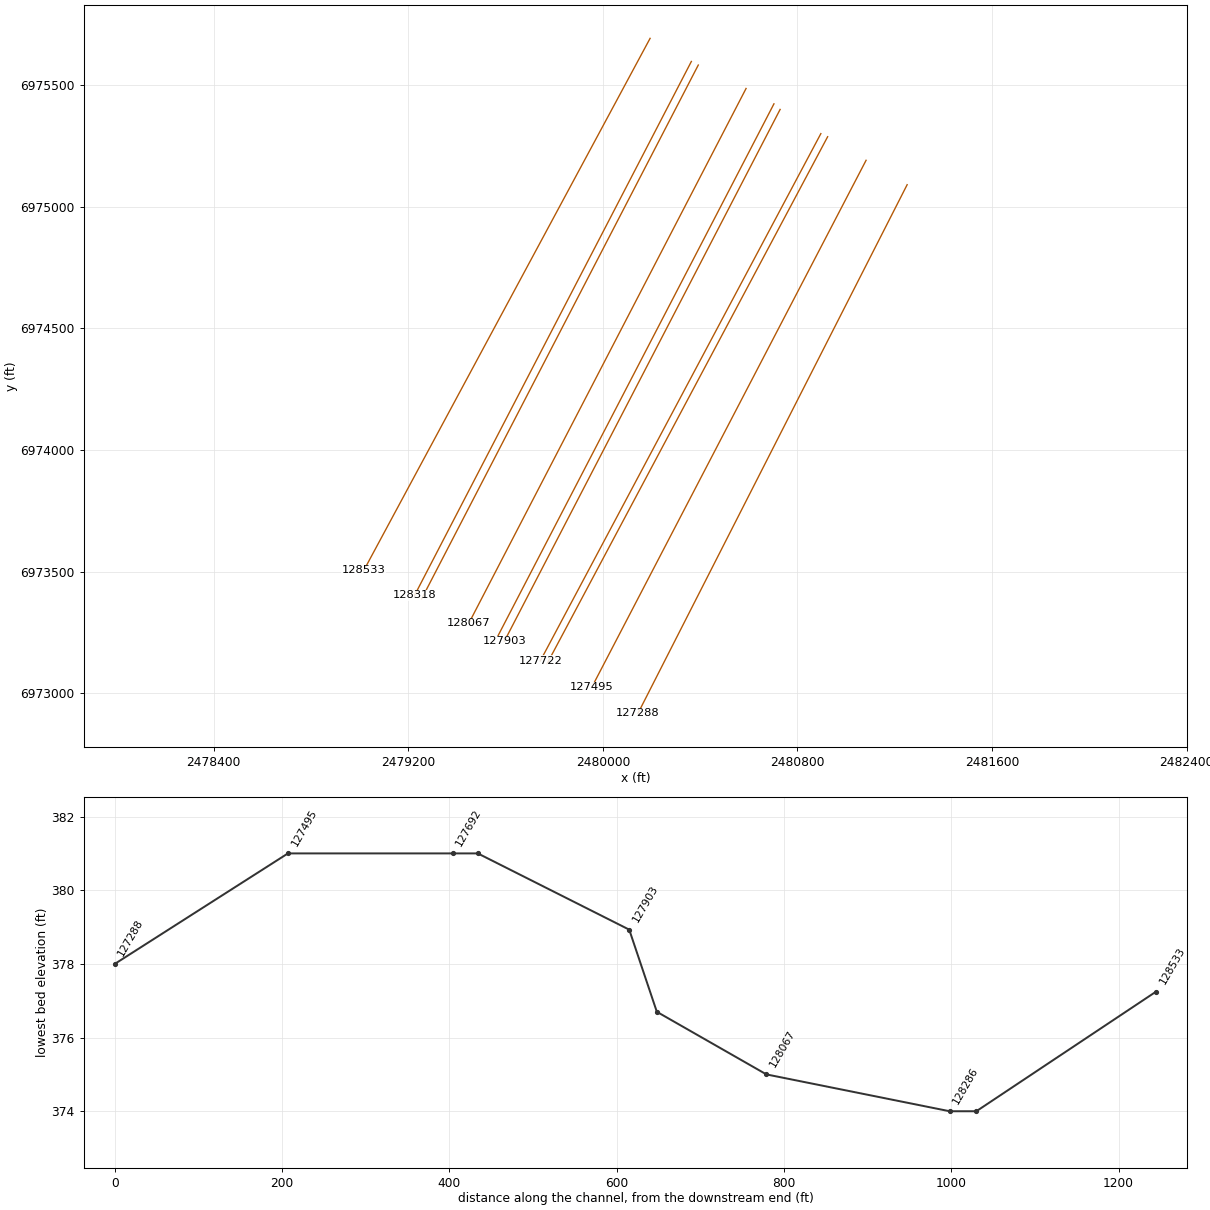
HEC-RAS study CDC_Consolidated_Model.prj: Upper Trinity CDC Consolidated Model

--- CDC_Consolidated_Model.g01 (geometry) --- (continued)

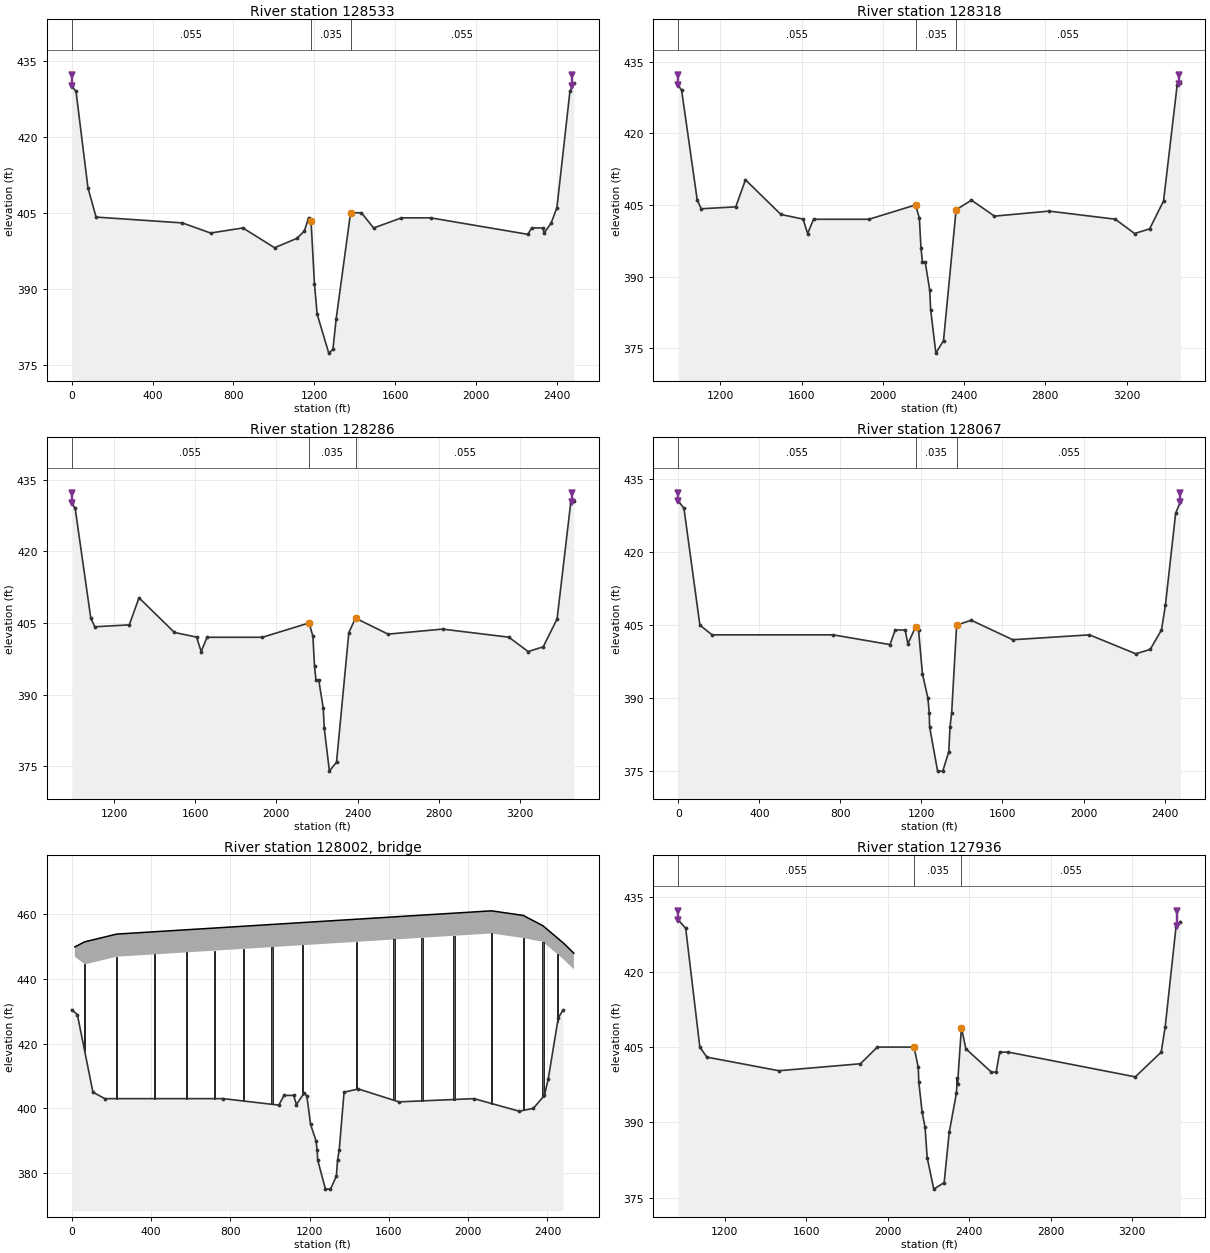
Type RM Length L Ch R = 1 ,128533  ,215,215,215
BEGIN DESCRIPTION:
This cross section corresponds to cross section 128538 of the non-georeferenced CDC model which was the source of this model.
END DESCRIPTION:
XS GIS Cut Line= 2
2480194.010116676975692.73570621  2479016.9901616973505.26468746
#Sta/Elev= 30
       0     430   21.11     429   79.81     410  120.15  404.15  546.76     403
  686.84     401  846.77     402 1003.47  398.09 1113.14  399.93 1150.96   401.4
 1171.33     404 1183.73  403.41 1200.62     391 1213.77     385 1271.52  377.25
  1292.1     378 1308.07     384 1379.35     405 1433.16     405 1493.37     402
 1631.27     404 1775.99     404 2256.18  400.74 2275.59     402 2329.77     402
 2337.53     401 2371.99     403 2400.24     406 2464.62     429 2484.03  430.67
#Mann= 3 ,0,0
       0    .055       0 1183.73    .035       0 1379.35    .055       0
Levee=-1,0,432.28,-1,2477,432.28,Levee 1,Levee 2
#XS Ineff= 2 , 0
       0 1183.73  403.41 1379.35       0     405
Permanent Ineff=
       F       F
#XS Lid=6
     920  437.81  432.41   921.7  437.81  432.41  921.71  437.81  437.11
  954.29  437.81  437.11   954.3  437.81  432.41     956  437.81  432.41
Bank Sta=1183.73,1379.35
XS Rating Curve= 0 ,0
Exp/Cntr=0.3,0.1

Type RM Length L Ch R = 1 ,128318  ,32,32,32
BEGIN DESCRIPTION:
This cross section corresponds to cross section 128323 of the non-georeferenced CDC model which was the source of this model.
END DESCRIPTION:
XS GIS Cut Line= 2
2480363.676443996975597.635502712479225.499258436973402.20091721
#Sta/Elev= 30
     992     430 1008.69     429 1085.67     406 1105.34   404.2 1275.33   404.6
 1323.13  410.26 1497.72  403.01 1606.67  402.04 1629.28  399.02  1658.4     402
 1930.85     402 2160.62     405 2179.65  402.24 2187.59     396 2195.06     393
 2208.68     393 2230.73  387.15 2235.47     383    2261     374 2298.57  376.62
 2360.66     404 2436.32     406 2549.65  402.66 2818.43  403.71 3144.73  402.02
 3239.76  399.02  3313.9     400 3382.39  405.83 3449.18     430 3464.93  430.44
#Mann= 3 ,0,0
     992    .055       0 2160.62    .035       0 2360.66    .055       0
Levee=-1,992,432.22,-1,3458,432.22,Levee 1,Levee 2
#XS Ineff= 2 , 0
       0 2160.62     405 2360.66       0     404
Permanent Ineff=
       F       F
#XS Lid=6
    1886  448.21  442.81  1887.7  448.21  442.81 1887.71  448.21  447.51
 1920.29  448.21  447.51  1920.3  448.21  442.81    1922  448.21  442.81
Bank Sta=2160.62,2360.66
XS Rating Curve= 0 ,0
Exp/Cntr=0.3,0.1

Type RM Length L Ch R = 1 ,128286  ,218,219,218
BEGIN DESCRIPTION:
This cross section corresponds to cross section 128290 of the non-georeferenced CDC model which was the source of this model.
END DESCRIPTION:
XS GIS Cut Line= 2
2480392.127502596975582.894062392479254.234437176973387.31183939
#Sta/Elev= 30
     992     430 1008.69     429 1085.67     406 1105.34   404.2 1275.33   404.6
 1323.13  410.26 1497.72  403.01 1606.67  402.04 1629.28  399.02  1658.4     402
 1930.85     402 2160.62     405 2179.65  402.24 2187.59     396 2195.06     393
 2208.68     393 2230.73  387.15 2235.47     383    2261     374 2296.08  375.89
 2356.63     403 2389.79     406 2549.65  402.66 2818.43  403.71 3144.73  402.02
 3239.76  399.02  3313.9     400 3382.39  405.83 3449.18     430 3464.93  430.44
#Mann= 3 ,0,0
     992    .055       0 2160.62    .035       0 2389.79    .055       0
Levee=-1,992,432.22,-1,3458,432.22,Levee 1,Levee 2
#XS Ineff= 2 , 0
       0 2160.62     405 2389.79       0     406
Permanent Ineff=
       F       F
#XS Lid=6
    1886  449.91  444.51  1887.7  449.91  444.51 1887.71  449.91  449.21
 1920.29  449.91  449.21  1920.3  449.91  444.51    1922  449.91  444.51
Bank Sta=2160.62,2389.79
XS Rating Curve= 0 ,0
Exp/Cntr=0.3,0.1

Type RM Length L Ch R = 1 ,128067  ,131,131,131
BEGIN DESCRIPTION:
This cross section corresponds to cross section 128158 of the non-georeferenced CDC model which was the source of this model.
END DESCRIPTION:
XS GIS Cut Line= 2
      2480588.63     6975486.541     2479448.447     6973287.122
#Sta/Elev= 30
       0  430.51   28.18     429  106.81     405  166.88     403  764.72     403
 1044.68     401 1070.78     404 1119.52     404 1133.25  401.17 1171.17  404.63
  1185.8  403.91 1204.96     395 1231.97     390 1238.34     387 1240.51  384.04
  1279.8     375 1305.21     375 1334.98     379  1340.9     384 1349.17     387
  1373.7     405 1445.75     406 1650.53     402 2029.21     403  2257.5  399.11
 2328.76     400 2384.51     404 2404.03  409.15 2454.32  427.98 2477.39  430.31
#Mann= 3 ,0,0
       0    .055       0 1171.17    .035       0  1373.7    .055       0
Levee=-1,0,432.18,-1,2477,432.18,Levee 1,Levee 2
#XS Ineff= 2 , 0
       0 1171.17  404.63  1373.7       0     405
Permanent Ineff=
       F       F
#XS Lid=6
     920  455.47  450.07   921.7  455.47  450.07  921.71  455.47  454.77
  954.29  455.47  454.77   954.3  455.47  450.07     956  455.47  450.07
Bank Sta=1171.17,1373.7
XS Rating Curve= 0 ,0
Exp/Cntr=0.3,0.1

Type RM Length L Ch R = 3 ,128002  ,,,
BEGIN DESCRIPTION:
128092.5  Sylvan Avenue Bridge
END DESCRIPTION:
Node Name=Sylvan Avenue
Bridge Culvert--1,0,-1,-1, 0
Deck Dist Width WeirC Skew NumUp NumDn MinLoCord MaxHiCord MaxSubmerge Is_Ogee
7,117,2.6,0, 18, 18, , , 0.98, 0, 0,0,,
    15.5    65.5   226.5     416     577     721     865    1009  1198.5  1435.5
    1625    1767    1928  2117.5  2277.5    2377    2483    2533
  449.96  451.53  453.92  454.64  455.25   455.8  456.35   456.9  457.62  458.52
  459.25  459.79   460.4  461.12   459.7  456.51     451  448.01
  446.96  444.53  446.92  447.64  448.25   448.8  449.35   449.9  450.62  451.52
  452.25  452.79   453.4  454.12   452.7  451.51     446  443.01
   970.5  1020.5  1181.5    1371    1532    1676    1820    1964  2153.5  2390.5
    2580    2722    2883  3072.5  3232.5    3332    3438    3490
  449.96  451.53  453.92  454.64  455.25   455.8  456.35   456.9  457.62  458.52
  459.25  459.79   460.4  461.12   459.7  456.51     451  448.01
  446.96  444.53  446.92  447.64  448.25   448.8  449.35   449.9  450.62  451.52
  452.25  452.79   453.4  454.12   452.7  451.51     446  443.01
Pier Skew, UpSta & Num, DnSta & Num=  ,65.5, 2 ,1020.5, 2 , 0 , 0 , 0 ,,
       6       6
       0     446
       6       6
       0     446
Pier Skew, UpSta & Num, DnSta & Num=  ,226.5, 2 ,1181.5, 2 , 0 , 0 , 0 ,,
       6       6
       0     448
       6       6
       0     448
Pier Skew, UpSta & Num, DnSta & Num=  ,416, 2 ,1371, 2 , 0 , 0 , 0 ,,
       6       6
       0     449
       6       6
       0     449
Pier Skew, UpSta & Num, DnSta & Num=  ,577, 2 ,1532, 2 , 0 , 0 , 0 ,,
       6       6
       0     450
       6       6
       0     450
Pier Skew, UpSta & Num, DnSta & Num=  ,721, 2 ,1676, 2 , 0 , 0 , 0 ,,
       6       6
       0     450
       6       6
       0     450
Pier Skew, UpSta & Num, DnSta & Num=  ,865, 2 ,1820, 2 , 0 , 0 , 0 ,,
       6       6
       0     450
       6       6
       0     450
Pier Skew, UpSta & Num, DnSta & Num=  ,1009, 2 ,1964, 2 , 0 , 0 , 0 ,,
       8       8
       0     451
       8       8
       0     451
Pier Skew, UpSta & Num, DnSta & Num=  ,1165, 2 ,2124, 2 , 0 , 0 , 0 ,,
       6       6
       0     451
       6       6
       0     451
Pier Skew, UpSta & Num, DnSta & Num=  ,1435.5, 2 ,2390.5, 2 , 0 , 0 , 0 ,,
       6       6
       0     452
       6       6
       0     452
Pier Skew, UpSta & Num, DnSta & Num=  ,1625, 2 ,2580, 2 , 0 , 0 , 0 ,,
       8       8
       0     453
       8       8
       0     453
Pier Skew, UpSta & Num, DnSta & Num=  ,1767, 2 ,2722, 2 , 0 , 0 , 0 ,,
       6       6
       0     453
       6       6
       0     453
Pier Skew, UpSta & Num, DnSta & Num=  ,1928, 2 ,2883, 2 , 0 , 0 , 0 ,,
       6       6
       0     454
       6       6
       0     454
Pier Skew, UpSta & Num, DnSta & Num=  ,2117.5, 2 ,3072.5, 2 , 0 , 0 , 0 ,,
       6       6
       0     455
       6       6
       0     455
Pier Skew, UpSta & Num, DnSta & Num=  ,2277.5, 2 ,3232.5, 2 , 0 , 0 , 0 ,,
       6       6
       0     455
       6       6
       0     455
Pier Skew, UpSta & Num, DnSta & Num=  ,2377, 2 ,3332, 2 , 0 , 0 , 0 ,,
       6       6
       0     453
       6       6
       0     453
Pier Skew, UpSta & Num, DnSta & Num=  ,2451, 2 ,3410, 2 , 0 , 0 , 0 ,,
       6       6
       0     450
       6       6
       0     450
BR Coef=-1 , 0 , 0 ,, 0 ,,,0.8,-1,,0,
WSPro=,,,, 1 ,,,, 0 ,,,, 0 ,,,,-1 ,-1 ,-1 , 0 , 0 , 0 , 0 , 0
BC Design=,, 0 ,, 0 ,,,,,,
BC Use User HTab Curves=0
BC User HTab FreeFlow(D)= 0

Type RM Length L Ch R = 1 ,127936  ,33,33,33
BEGIN DESCRIPTION:
This cross section corresponds to cross section 128027 of the non-georeferenced CDC model which was the source of this model.
END DESCRIPTION:
XS GIS Cut Line= 2
     2480703.253     6975423.377     2479568.338     6973235.477
#Sta/Elev= 30
   972.5  430.33 1009.15  428.67 1078.55     405  1112.9     403 1466.89  400.29
 1866.98  401.68    1950     405    2130     405 2150.62     401 2153.59     398
 2169.86  392.02 2184.25     389 2194.52     383 2226.88   376.7 2277.92     378
 2302.72     388 2338.49  395.89 2341.99  398.77  2343.8  397.69 2362.69   408.9
  2384.4  404.66 2509.45  400.03 2533.12     400 2550.39     404 2593.08     404
 3216.07  399.07 3343.47     404 3362.97     409 3416.29     429 3437.24     430
#Mann= 3 ,0,0
   972.5    .055       0    2130    .035       0 2362.69    .055       0
Levee=-1,972.5,432.15,-1,3420,432.15,Levee 1,Levee 2
#XS Ineff= 2 , 0
       0    2130  402.33 2362.69       0   408.9
Permanent Ineff=
       F       F
Bank Sta=2130,2362.69
XS Rating Curve= 0 ,0
Exp/Cntr=0.3,0.1

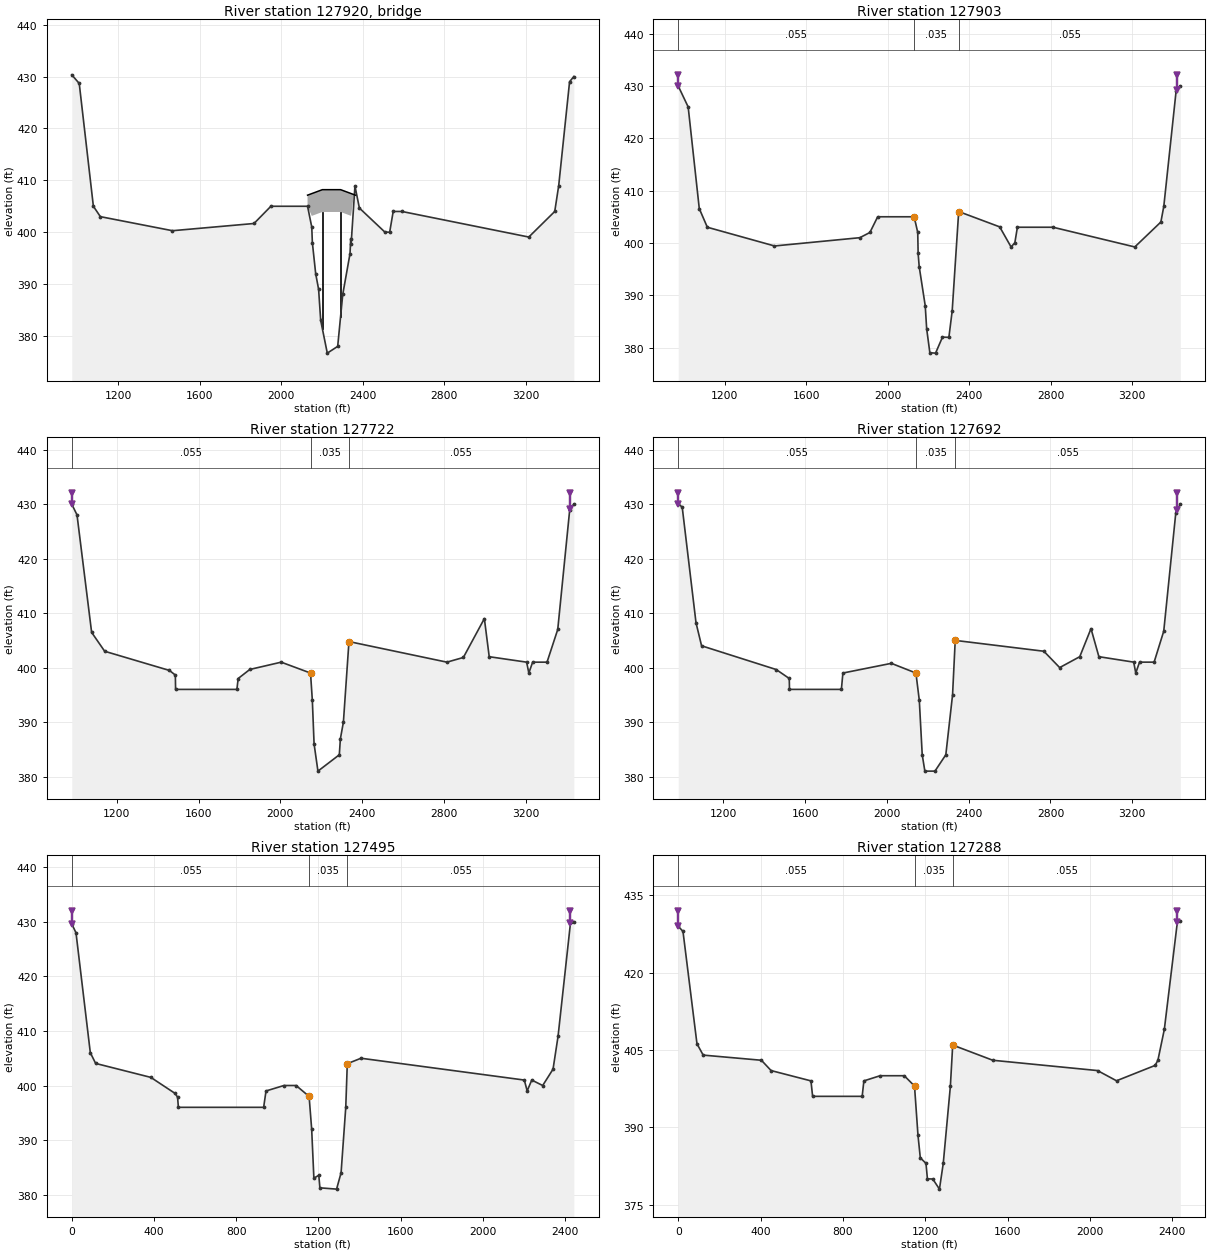
Type RM Length L Ch R = 3 ,127920  ,,,
BEGIN DESCRIPTION:
128010.5  Sylvan Avenue River Channel Bridge
END DESCRIPTION:
Node Name=Sylvan Avenue Ri
Bridge Culvert--1,0,-1,-1, 0
Deck Dist Width WeirC Skew NumUp NumDn MinLoCord MaxHiCord MaxSubmerge Is_Ogee
1,31,2.6,0, 4, 4, , , 0.95, 0, ,,,
    2130  2202.8  2292.2    2365
  407.14   408.2   408.2  407.14
  402.84   403.9   403.9  402.84
    2130  2202.8  2292.2    2365
  407.14   408.2   408.2  407.14
  402.84   403.9   403.9  402.84
Pier Skew, UpSta & Num, DnSta & Num=  ,2202.8, 2 ,2202.8, 2 , 0 , 0 , 0 ,,
       3       3
       0     404
       3       3
       0     404
Pier Skew, UpSta & Num, DnSta & Num=  ,2292.2, 2 ,2292.2, 2 , 0 , 0 , 0 ,,
       3       3
       0     404
       3       3
       0     404
BR Coef= 1 , 0 , 0 ,1.05, 0 ,,,0.8,-1,1.2,1,
WSPro=,,,, 1 ,,,, 0 ,,,, 0 ,,,,-1 ,-1 ,-1 , 0 , 0 , 0 , 0 , 0
BC Design=,, 0 ,, 0 ,,,,,,
BC HTab HWMax=431.2
BC Use User HTab Curves=0
BC User HTab FreeFlow(D)= 0

Type RM Length L Ch R = 1 ,127903  ,181,181,181
BEGIN DESCRIPTION:
This cross section corresponds to cross section 127994 of the non-georeferenced CDC model which was the source of this model.
END DESCRIPTION:
XS GIS Cut Line= 2
     2480728.619      6975400.43     2479594.769     6973213.666
#Sta/Elev= 30
   972.5     430 1021.23     426 1075.74  406.56 1115.23     403 1444.76  399.42
 1863.37     401 1912.88     402    1951     405    2130     405 2147.52     402
 2149.46     398 2154.62  395.48 2184.26     388 2191.35  383.57 2207.02     379
 2235.01  378.93 2268.95  381.99 2300.38  381.95 2316.52     387 2348.46     406
 2549.63  403.07 2605.27  399.24 2623.81     400 2636.45     403 2811.26     403
 3212.41  399.23 3340.42     404 3354.76     407    3415     429 3435.74     430
#Mann= 3 ,0,0
   972.5    .055       0    2130    .035       0 2348.46    .055       0
Levee=-1,972.5,432.14,-1,3419,432.14,Levee 1,Levee 2
#XS Ineff= 2 , 0
       0    2130     402 2348.46       0     406
Permanent Ineff=
       F       F
Bank Sta=2130,2348.46
XS Rating Curve= 0 ,0
Exp/Cntr=0.3,0.1

Type RM Length L Ch R = 1 ,127722  ,30,30,30
BEGIN DESCRIPTION:
This cross section corresponds to cross section 127779 of the non-georeferenced CDC model which was the source of this model.
END DESCRIPTION:
XS GIS Cut Line= 2
     2480896.153     6975300.951     2479742.456     6973132.701
#Sta/Elev= 30
     980     430 1005.62  428.03 1077.12  406.47 1140.96     403 1457.73  399.48
  1486.7  398.63 1487.86     396 1787.78     396 1794.02     398 1850.98  399.66
 2004.54     401 2147.93     399 2156.82     394 2165.34     386 2184.22     381
 2288.82     384 2293.96  386.92 2308.81     390 2335.97  404.78 2815.26     401
 2895.58  401.86 2998.37     409 3022.08     402 3205.13     401 3215.89     399
 3234.49     401 3304.87     401 3357.32     407 3415.92     429 3436.08     430
#Mann= 3 ,0,0
     980    .055       0 2147.93    .035       0 2335.97    .055       0
Levee=-1,980,432.08,-1,3419,432.08,Levee 1,Levee 2
#XS Ineff= 2 , 0
       0 2147.93     399 2335.97       0  404.78
Permanent Ineff=
       F       F
Bank Sta=2147.93,2335.97
XS Rating Curve= 0 ,0
Exp/Cntr=0.3,0.1

Type RM Length L Ch R = 1 ,127692  ,197,197,197
BEGIN DESCRIPTION:
This cross section corresponds to cross section 127746 of the non-georeferenced CDC model which was the source of this model.
END DESCRIPTION:
XS GIS Cut Line= 2
     2480924.092      6975288.24     2479770.232     6973121.231
#Sta/Elev= 30
     980     430  999.32  429.48  1066.9  408.23  1094.1     404 1459.27  399.64
 1522.91     398 1523.99     396  1777.8     396 1785.17     399 2022.09  400.78
 2142.24     399 2158.77     394 2173.04     384 2185.95     381 2235.24     381
 2288.46     384 2321.41     395 2334.42  404.99 2767.78     403 2845.12     400
 2943.39     402 2998.34  407.15 3036.93     402 3207.26     401 3217.18     399
  3235.7     401 3306.98     401 3354.03  406.68 3412.97   428.4 3435.06     430
#Mann= 3 ,0,0
     980    .055       0 2142.24    .035       0 2334.42    .055       0
Levee=-1,980,432.07,-1,3419,432.07,Levee 1,Levee 2
#XS Ineff= 2 , 0
       0 2142.24     399 2334.42       0  404.99
Permanent Ineff=
       F       F
Bank Sta=2142.24,2334.42
XS Rating Curve= 0 ,0
Exp/Cntr=0.3,0.1

Type RM Length L Ch R = 1 ,127495  ,207,207,207
BEGIN DESCRIPTION:
This cross section corresponds to cross section 127549 of the non-georeferenced CDC model which was the source of this model.
END DESCRIPTION:
XS GIS Cut Line= 2
     2481082.152     6975191.303     2479953.925      6973023.83
#Sta/Elev= 30
       0  429.63   20.59     428   90.24  406.02  116.18  404.05   384.7  401.49
  502.85  398.55  514.82  397.87  518.95     396  933.86     396  945.38     399
 1032.49     400 1091.81     400 1155.08     398 1167.56     392 1178.33     383
  1202.3  383.54 1207.54  381.24 1288.82     381  1310.7     384 1333.48     396
 1340.93     404 1407.63     405 2202.45     401 2216.41  399.01 2238.72     401
 2291.87     400  2342.3     403  2366.6     409 2427.72     430 2443.53     430
#Mann= 3 ,0,0
       0    .055       0 1155.08    .035       0 1340.93    .055       0
Levee=-1,0,432.03,-1,2427,432.03,Levee 1,Levee 2
#XS Ineff= 2 , 0
       0 1155.08     398 1340.93       0     404
Permanent Ineff=
       F       F
Bank Sta=1155.08,1340.93
XS Rating Curve= 0 ,0
Exp/Cntr=0.3,0.1

Type RM Length L Ch R = 1 ,127288  ,188,188,188
BEGIN DESCRIPTION:
This cross section corresponds to cross section 127352 of the non-georeferenced CDC model which was the source of this model.
END DESCRIPTION:
XS GIS Cut Line= 2
     2481250.969     6975090.898     2480144.082     6972917.049
#Sta/Elev= 30
       0     429   23.07     428   91.03   406.2   121.2     404  404.11     403
  451.13     401  644.84     399  652.91     396  893.67     396  901.99     399
   980.9     400 1098.21     400    1148     398 1164.73   388.5 1176.11  384.07
 1203.67     383 1210.73     380 1236.74  379.96 1269.14     378 1287.66     383
 1322.16  397.94 1333.55  405.95 1528.27     403 2037.25     401 2129.48  399.02
 2317.06     402 2330.57     403 2361.83     409 2425.68     430 2439.43     430
#Mann= 3 ,0,0
       0    .055       0    1148    .035       0 1333.55    .055       0
Levee=-1,0,431.99,-1,2425,431.99,Levee 1,Levee 2
#XS Ineff= 2 , 0
       0    1148     398 1333.55       0  405.95
Permanent Ineff=
       F       F
Bank Sta=1148,1333.55
XS Rating Curve= 0 ,0
Exp/Cntr=0.3,0.1