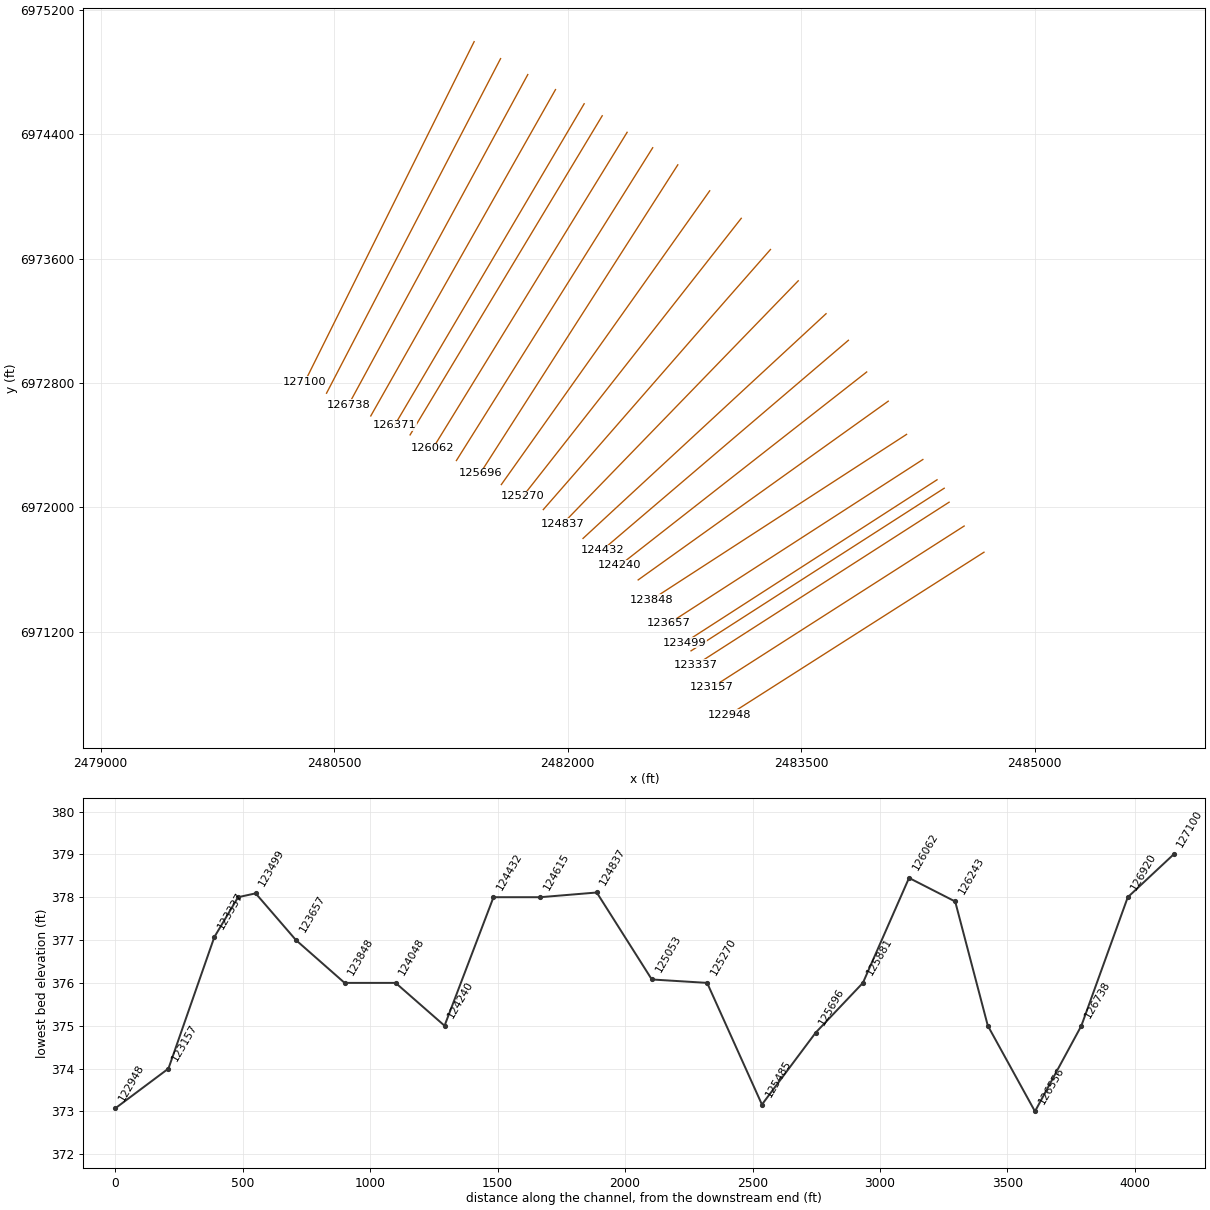
HEC-RAS study CDC_Consolidated_Model.prj: Upper Trinity CDC Consolidated Model

--- CDC_Consolidated_Model.g01 (geometry) --- (continued)

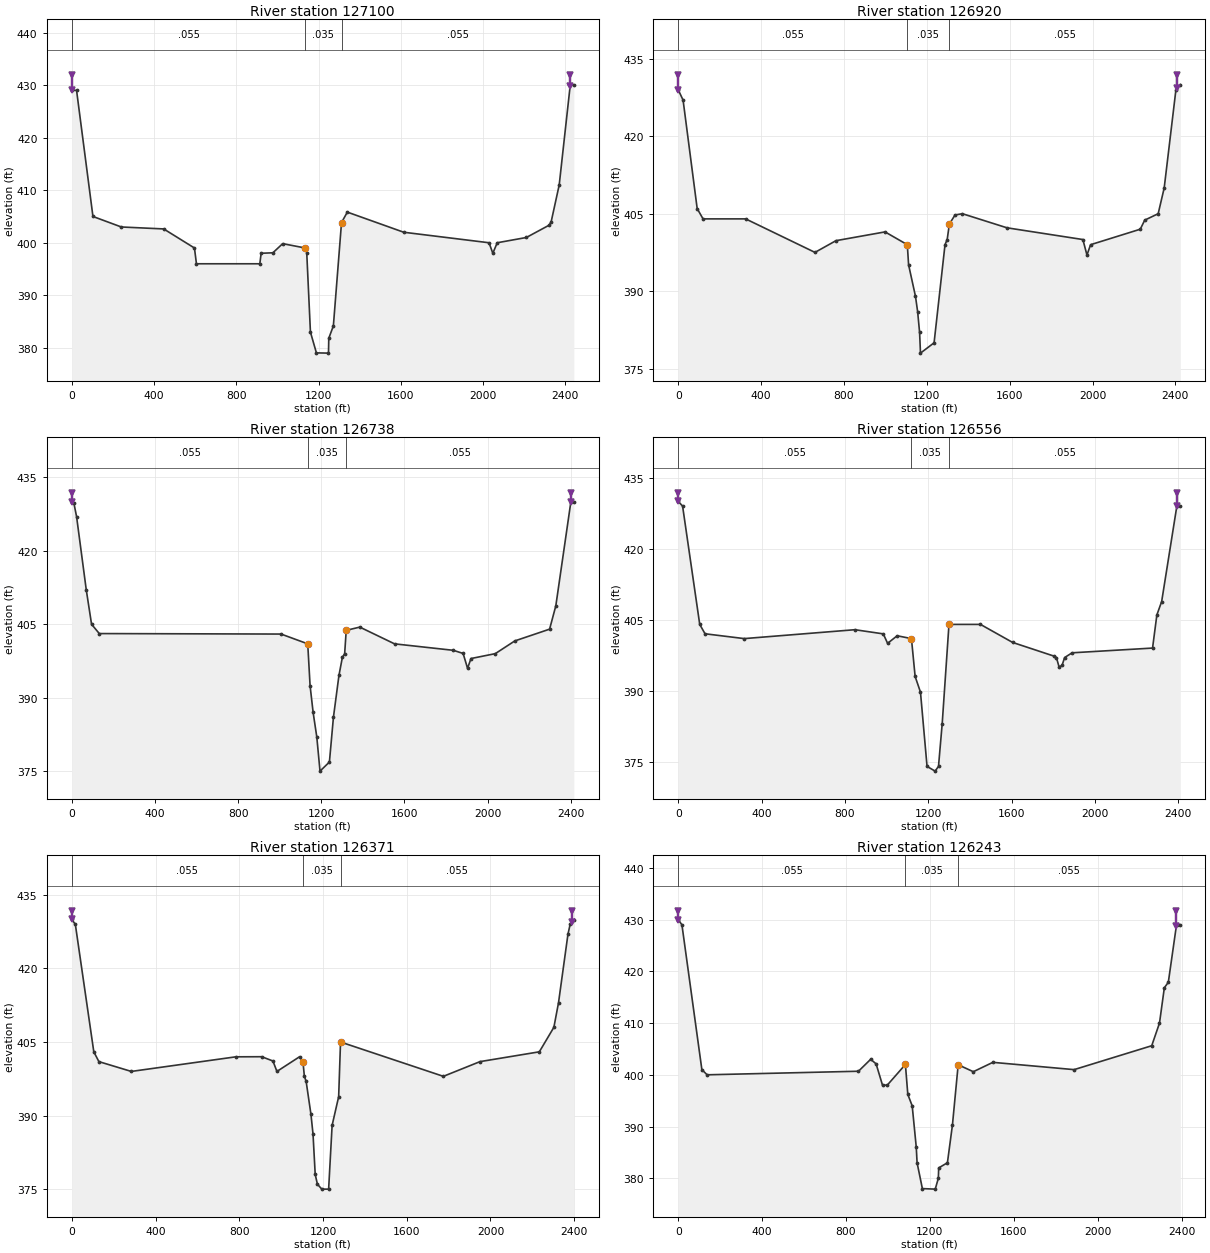
Type RM Length L Ch R = 1 ,127100  ,180,180,180
BEGIN DESCRIPTION:
This cross section corresponds to cross section 127155 of the non-georeferenced CDC model which was the source of this model.
END DESCRIPTION:
XS GIS Cut Line= 2
      2481400.01     6974993.947     2480312.725     6972808.295
#Sta/Elev= 30
       0  428.99    23.3     429  102.95     405  240.96     403  446.97  402.63
  596.46     399  606.23     396  914.32     396  920.83     398  977.78  398.09
 1025.51  399.83 1135.44     399 1142.52  398.06 1160.42     383 1189.43  379.05
 1248.19     379 1249.65  381.83 1271.94  384.18 1311.57  403.84 1339.77  405.83
 1614.04     402 2028.74     400 2047.24     398 2068.69     400 2210.08     401
 2320.98  403.34 2330.95     404 2370.02     411 2423.66     430 2441.16     430
#Mann= 3 ,0,0
       0    .055       0 1135.44    .035       0 1311.57    .055       0
Levee=-1,0,431.95,-1,2423,431.95,Levee 1,Levee 2
#XS Ineff= 2 , 0
       0 1135.44     399 1311.57       0  403.84
Permanent Ineff=
       F       F
Bank Sta=1135.44,1311.57
XS Rating Curve= 0 ,0
Exp/Cntr=0.3,0.1

Type RM Length L Ch R = 1 ,126920  ,182,182,182
BEGIN DESCRIPTION:
This cross section corresponds to cross section 126973 of the non-georeferenced CDC model which was the source of this model.
END DESCRIPTION:
XS GIS Cut Line= 2
     2481569.844     6974884.842     2480451.952     6972734.401
#Sta/Elev= 30
       0     429   23.42     427   91.44     406  119.72     404  325.38     404
  660.06  397.51  761.45  399.78  998.33  401.48 1105.83     399 1111.99   395.1
 1145.25     389 1155.74     386 1165.13     382 1169.37     378 1235.04     380
  1287.8     399  1298.3     400 1308.88     403  1336.2  404.76 1371.84     405
 1587.14  402.27 1953.34     400 1972.99     397  1990.5     399 2230.43     402
 2251.87  403.76 2316.81     405  2345.9     410 2402.44     429 2423.65     430
#Mann= 3 ,0,0
       0    .055       0 1105.83    .035       0 1308.88    .055       0
Levee=-1,0,431.9,-1,2408,431.9,Levee 1,Levee 2
#XS Ineff= 2 , 0
       0 1105.83     399 1308.88       0     403
Permanent Ineff=
       F       F
Bank Sta=1105.83,1308.88
XS Rating Curve= 0 ,0
Exp/Cntr=0.3,0.1

Type RM Length L Ch R = 1 ,126738  ,182,182,182
BEGIN DESCRIPTION:
This cross section corresponds to cross section 126791 of the non-georeferenced CDC model which was the source of this model.
END DESCRIPTION:
XS GIS Cut Line= 2
     2481744.598     6974782.275     2480593.281     6972660.014
#Sta/Elev= 30
       0     430   10.42  429.69   23.08     427   69.81     412   95.19     405
  132.34   403.1 1006.61     403 1134.74     401 1145.99  392.47 1160.64     387
 1178.23     382 1193.78     375 1238.99  376.86 1258.32     386 1284.85  394.55
 1301.27  398.23 1312.32     399 1319.86  403.76 1385.21  404.42  1552.2     401
 1834.87  399.68 1881.95  399.04  1903.3     396 1919.76     398 2036.72     399
  2130.6   401.6  2297.8     404 2327.77  408.77  2400.1     430 2414.44     430
#Mann= 3 ,0,0
       0    .055       0 1134.74    .035       0 1319.86    .055       0
Levee=-1,0,431.85,-1,2400,431.85,Levee 1,Levee 2
#XS Ineff= 2 , 0
       0 1134.74     401 1319.86       0  403.76
Permanent Ineff=
       F       F
Bank Sta=1134.74,1319.86
XS Rating Curve= 0 ,0
Exp/Cntr=0.3,0.1

Type RM Length L Ch R = 1 ,126556  ,186,185,186
BEGIN DESCRIPTION:
This cross section corresponds to cross section 126609 of the non-georeferenced CDC model which was the source of this model.
END DESCRIPTION:
XS GIS Cut Line= 2
     2481922.692     6974685.741     2480736.192       6972588.3
#Sta/Elev= 30
       0     430    20.9     429  103.18     404  128.58  402.02  316.87     401
  847.99  402.88  984.09     402  1004.9     400 1050.84   401.6  1119.3     401
 1137.01     393 1162.65  389.69 1194.21     374  1232.9     373 1249.18     374
  1266.9     383 1299.49     404 1450.58     404 1604.91  400.19 1803.54   397.3
  1815.1     397 1827.92     395 1842.03  395.33 1854.56     397  1890.5     398
 2276.55     399 2297.26     406 2320.27  408.83 2393.15     429 2409.78     429
#Mann= 3 ,0,0
       0    .055       0  1119.3    .035       0 1299.49    .055       0
Levee=-1,0,431.8,-1,2393,431.8,Levee 1,Levee 2
#XS Ineff= 2 , 0
       0  1119.3     401 1299.49       0     404
Permanent Ineff=
       F       F
Bank Sta=1119.3,1299.49
XS Rating Curve= 0 ,0
Exp/Cntr=0.3,0.1

Type RM Length L Ch R = 1 ,126371  ,129,128,127
BEGIN DESCRIPTION:
This cross section corresponds to cross section 126428 of the non-georeferenced CDC model which was the source of this model.
END DESCRIPTION:
XS GIS Cut Line= 2
     2482106.809     6974594.653     2480889.298     6972528.481
#Sta/Elev= 30
       0     430   17.01     429  105.24     403  129.53     401  284.45     399
  783.69  401.98  907.43     402  960.81  401.13  979.98     399 1088.25     402
 1104.26     401 1111.04     398 1119.41     397 1142.57  390.22 1152.37  386.22
 1162.79     378 1173.34     376 1194.32     375 1226.93     375 1243.56     388
 1274.82  393.85 1283.77     405    1775     398    1950     401 2233.37     403
 2302.87     408 2324.96     413 2370.04  426.96 2380.55     429 2398.21  429.88
#Mann= 3 ,0,0
       0    .055       0 1104.26    .035       0 1283.77    .055       0
Levee=-1,0,431.75,-1,2390,431.75,Levee 1,Levee 2
#XS Ineff= 2 , 0
       0 1104.26     401 1283.77       0     405
Permanent Ineff=
       F       F
Bank Sta=1104.26,1283.77
XS Rating Curve= 0 ,0
Exp/Cntr=0.3,0.1

Type RM Length L Ch R = 1 ,126243  ,183,181,180
BEGIN DESCRIPTION:
This cross section corresponds to cross section 126246 of the non-georeferenced CDC model which was the source of this model.
END DESCRIPTION:
XS GIS Cut Line= 2
2482222.759011926974517.456560722480988.643369916972466.37142405
#Sta/Elev= 30
       0     430   17.59     429  112.69     401  137.71     400  859.38  400.69
   917.4     403   943.3  402.12  973.88     398  996.55     398 1083.09     402
 1094.54  396.21 1115.46     394 1134.86     386 1138.74     383 1163.98     378
 1225.32   377.9 1240.11     380 1241.78     382 1283.38     383  1307.4  390.32
 1334.68  401.94 1406.91   400.6 1500.08  402.41 1887.32     401 2257.46  405.62
 2294.48     410 2317.63  416.83  2336.6  417.89 2375.67     429 2393.74     429
#Mann= 3 ,0,0
       0    .055       0 1083.09    .035       0 1334.68    .055       0
Levee=-1,0,431.7,-1,2375,431.7,Levee 1,Levee 2
#XS Ineff= 2 , 0
       0 1083.09     402 1334.68       0  401.94
Permanent Ineff=
       F       F
Bank Sta=1083.09,1334.68
XS Rating Curve= 0 ,0
Exp/Cntr=0.3,0.1

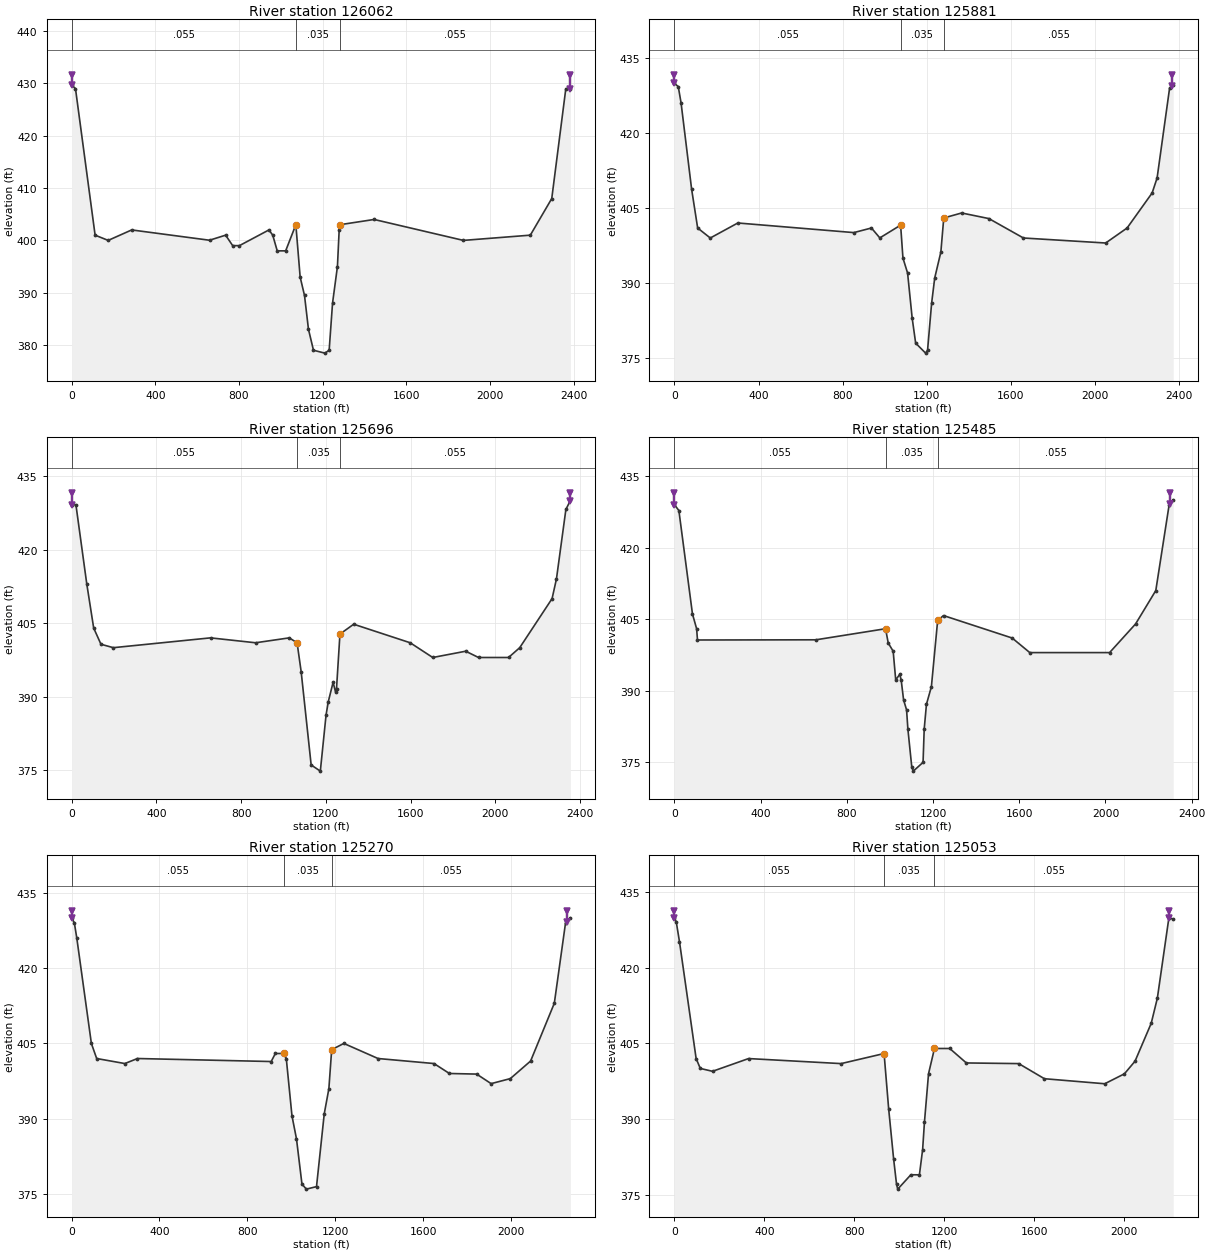
Type RM Length L Ch R = 1 ,126062  ,183,181,180
BEGIN DESCRIPTION:
This cross section corresponds to cross section 126065 of the non-georeferenced CDC model which was the source of this model.
END DESCRIPTION:
XS GIS Cut Line= 2
2482382.731132926974411.261891222481134.383892096972378.97560146
#Sta/Elev= 30
       0  429.74    18.6     429   112.4     401  174.88     400  287.28     402
  659.41  400.03  736.54     401  770.14     399  802.56     399  943.62     402
  961.81     401  983.27     398 1023.61     398 1072.27     403 1092.88     393
  1113.7  389.47 1132.67     383 1156.59     379 1210.99  378.45 1231.61     379
 1247.75     388 1271.16     395 1279.49     402 1283.27     403 1446.72     404
 1873.47     400 2193.54     401 2296.03     408 2363.27     429 2385.07     429
#Mann= 3 ,0,0
       0    .055       0 1072.27    .035       0 1283.27    .055       0
Levee=-1,0,431.65,-1,2385.07,431.65,Levee 1,Levee 2
#XS Ineff= 2 , 0
       0 1072.27     403 1283.27       0     403
Permanent Ineff=
       F       F
Bank Sta=1072.27,1283.27
XS Rating Curve= 0 ,0
Exp/Cntr=0.3,0.1

Type RM Length L Ch R = 1 ,125881  ,187,185,184
BEGIN DESCRIPTION:
This cross section corresponds to cross section 125884 of the non-georeferenced CDC model which was the source of this model.
END DESCRIPTION:
XS GIS Cut Line= 2
 2482547.0582321 6974312.0183233 2481286.24185616972301.66571672
#Sta/Elev= 30
       0  429.89   18.21  429.25   31.53     426   81.68  408.77  110.46     401
  170.51     399  301.57     402  853.52  400.08  937.28     401  977.14  399.02
 1076.11  401.57 1087.16     395 1109.26     392 1131.05     383 1147.65     378
 1194.91     376 1204.31  376.59 1223.67     386 1238.26     391 1267.52  396.19
 1281.37     403  1366.4     404 1496.14  402.88 1660.43     399 2051.73     398
 2153.66     401  2272.8     408 2296.41     411 2355.99     429 2373.01  429.53
#Mann= 3 ,0,0
       0    .055       0 1076.11    .035       0 1281.37    .055       0
Levee=-1,0,431.6,-1,2365,431.6,Levee 1,Levee 2
#XS Ineff= 2 , 0
       0 1076.11  401.57 1281.37       0     403
Permanent Ineff=
       F       F
Bank Sta=1076.11,1281.37
XS Rating Curve= 0 ,0
Exp/Cntr=0.3,0.1

Type RM Length L Ch R = 1 ,125696  ,230,211,191
BEGIN DESCRIPTION:
This cross section corresponds to cross section 125703 of the non-georeferenced CDC model which was the source of this model.
END DESCRIPTION:
XS GIS Cut Line= 2
2482708.258040936974202.146823882481438.91838801 6972219.1189658
#Sta/Elev= 30
       0  429.18   20.36  429.14   71.37  413.06  104.23     404  138.57   400.7
  197.03     400  655.75     402  868.54     401 1027.43     402 1064.42     401
 1083.61  395.11 1130.79   376.1 1174.11  374.84 1201.27  386.31 1211.77     389
 1234.43  392.95 1245.82     391 1250.51  391.63 1266.74  402.77  1331.6  404.78
 1598.39     401 1704.78     398  1860.4  399.28 1920.85     398 2062.59     398
  2115.4     400 2268.09     410 2288.73     414 2333.29  428.17 2354.49     430
#Mann= 3 ,0,0
       0    .055       0 1064.42    .035       0 1266.74    .055       0
Levee=-1,0,431.56,-1,2354,431.56,Levee 1,Levee 2
#XS Ineff= 2 , 0
       0 1064.42     401 1266.74       0  402.77
Permanent Ineff=
       F       F
Bank Sta=1064.42,1266.74
XS Rating Curve= 0 ,0
Exp/Cntr=0.3,0.1

Type RM Length L Ch R = 1 ,125485  ,236,215,196
BEGIN DESCRIPTION:
This cross section corresponds to cross section 125487 of the non-georeferenced CDC model which was the source of this model.
END DESCRIPTION:
XS GIS Cut Line= 2
2482913.179875176974035.094008392481574.781305256972147.21884713
#Sta/Elev= 30
       0     429    20.6  427.77   83.68  406.08  102.92     403  106.93  400.64
  656.51  400.68  979.48     403     992     400 1014.87  398.29 1026.66  392.28
 1045.57  393.45 1052.05  392.25 1063.23  388.07 1077.03     386 1083.07     382
 1101.23     374 1108.18  373.16 1153.54     375 1158.82  381.96  1169.3  387.17
 1192.21  390.86 1221.31  404.75 1248.39  405.76 1567.11  401.05  1648.7     398
    2019     398 2139.51     404 2233.38     411 2295.41     429 2314.17     430
#Mann= 3 ,0,0
       0    .055       0  979.48    .035       0 1221.31    .055       0
Levee=-1,0,431.48,-1,2299,431.48,Levee 1,Levee 2
#XS Ineff= 2 , 0
       0  979.48     403 1221.31       0  404.75
Permanent Ineff=
       F       F
Bank Sta=979.48,1221.31
XS Rating Curve= 0 ,0
Exp/Cntr=0.3,0.1

Type RM Length L Ch R = 1 ,125270  ,237,217,197
BEGIN DESCRIPTION:
This cross section corresponds to cross section 125272 of the non-georeferenced CDC model which was the source of this model.
END DESCRIPTION:
XS GIS Cut Line= 2
2483115.78576916 6973858.38734082481713.872234436972072.37188397
#Sta/Elev= 30
       0     430   12.39  429.03   23.55     426   90.01     405  114.13     402
  242.27     401  299.81     402  908.66   401.4   927.4     403  966.16     403
  977.28     402 1003.14  390.59 1023.71     386 1048.62     377 1068.67     376
 1114.87   376.5  1150.1     391 1171.15     396 1183.92  403.77 1239.35     405
 1394.93     402  1649.7     401 1719.82  399.02 1843.78   398.9 1909.76     397
 1997.11     398 2089.45   401.5 2197.42     413 2248.48     429 2270.51     430
#Mann= 3 ,0,0
       0    .055       0  966.16    .035       0 1183.92    .055       0
Levee=-1,0,431.4,-1,2253,431.4,Levee 1,Levee 2
#XS Ineff= 2 , 0
       0  966.16     403 1183.92       0  403.77
Permanent Ineff=
       F       F
Bank Sta=966.16,1183.92
XS Rating Curve= 0 ,0
Exp/Cntr=0.3,0.1

Type RM Length L Ch R = 1 ,125053  ,237,216,197
BEGIN DESCRIPTION:
This cross section corresponds to cross section 125056 of the non-georeferenced CDC model which was the source of this model.
END DESCRIPTION:
XS GIS Cut Line= 3
2483303.535393696973657.967137962483017.832881096973332.51109597
2481844.329978766971986.26674122
#Sta/Elev= 30
       0  429.98    8.23   429.1   22.41  425.21    96.5     402   115.1  400.04
  169.51  399.47  329.75     402  741.42     401  932.67     403  953.04  392.02
  975.14  382.07  988.24     377  993.51  376.08 1051.74  378.93 1089.85  378.92
 1104.19  383.93 1112.26  389.36  1130.5     399 1156.83     404 1224.75     404
 1298.63  401.13  1531.8     401  1645.9     398 1914.37     397 2001.84  398.97
 2049.16  401.48 2121.12     409 2148.47     414 2199.95     430 2218.98  429.68
#Mann= 3 ,0,0
       0    .055       0  932.67    .035       0 1156.83    .055       0
Levee=-1,0,431.33,-1,2200,431.33,Levee 1,Levee 2
#XS Ineff= 2 , 0
       0  932.67     403 1156.83       0     404
Permanent Ineff=
       F       F
Bank Sta=932.67,1156.83
XS Rating Curve= 0 ,0
Exp/Cntr=0.3,0.1

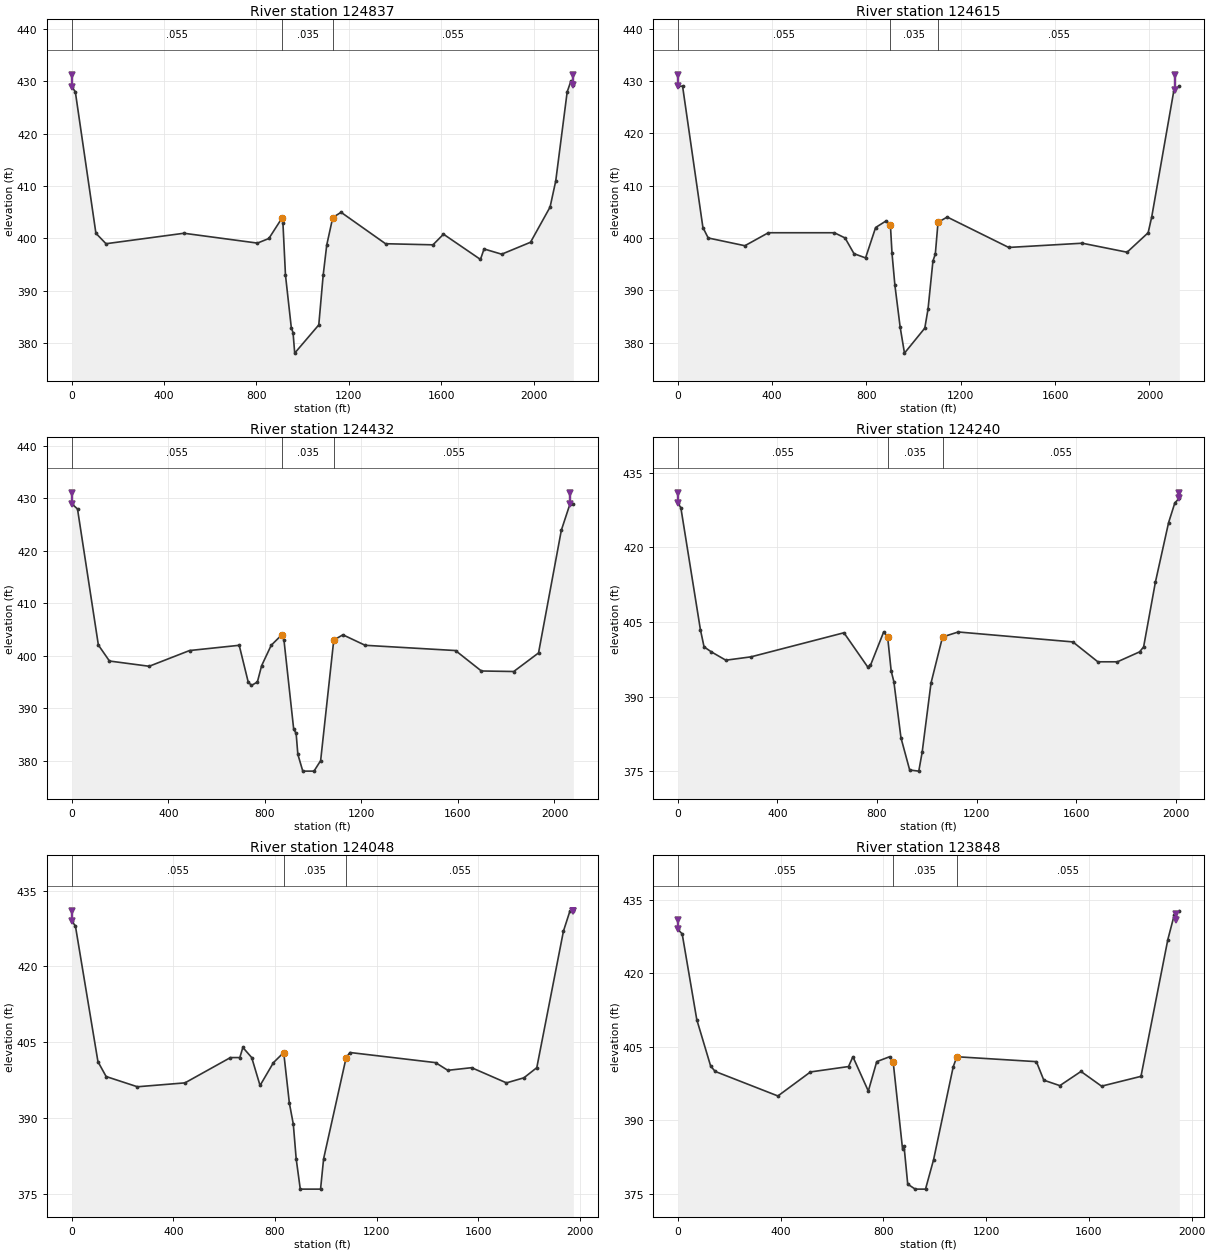
Type RM Length L Ch R = 1 ,124837  ,243,222,202
BEGIN DESCRIPTION:
This cross section corresponds to cross section 124841 of the non-georeferenced CDC model which was the source of this model.
END DESCRIPTION:
XS GIS Cut Line= 2
2483481.850325766973456.607632552481970.100724586971896.13896872
#Sta/Elev= 30
       0     429   15.54     428  104.63     401  148.33     399  485.87     401
   804.3  399.12  853.79     400  911.21  403.94  914.65     403  925.73     393
   950.9     383  958.58     382  965.68  378.11 1069.99   383.5 1088.94  392.96
  1104.5  398.76 1130.49     404  1166.5     405 1359.12     399  1564.5  398.79
 1610.14  400.82 1770.24     396 1785.81     398 1862.11     397 1987.09  399.28
 2071.75     406 2096.29  410.98 2145.89     428 2161.61     430 2172.66  429.32
#Mann= 3 ,0,0
       0    .055       0  911.21    .035       0 1130.49    .055       0
Levee=-1,0,431.25,-1,2172,431.25,Levee 1,Levee 2
#XS Ineff= 2 , 0
       0  911.21  403.94 1130.49       0     404
Permanent Ineff=
       F       F
Bank Sta=911.21,1130.49
XS Rating Curve= 0 ,0
Exp/Cntr=0.3,0.1

Type RM Length L Ch R = 1 ,124615  ,200,183,167
BEGIN DESCRIPTION:
This cross section corresponds to cross section 124626 of the non-georeferenced CDC model which was the source of this model.
END DESCRIPTION:
XS GIS Cut Line= 2
2483660.513026186973245.091979462482099.492198086971800.90261063
#Sta/Elev= 30
       0     429   20.63     429  106.81     402  129.28     400  284.84  398.52
  384.27     401  664.14     401  709.48     400  747.38     397  796.39  396.19
  839.02     402  883.51  403.26  901.61  402.57  908.43  397.11  920.68     391
  942.93     383  961.38     378 1047.42  382.77 1061.15  386.39 1081.98  395.58
 1092.17  396.95 1103.57     403 1142.68     404 1403.34  398.19 1714.97     399
 1905.16  397.28 1994.36     401 2009.47     404 2102.74     428 2126.61     429
#Mann= 3 ,0,0
       0    .055       0  901.61    .035       0 1103.57    .055       0
Levee=-1,0,431.17,-1,2109,431.17,Levee 1,Levee 2
#XS Ineff= 2 , 0
       0  901.61  402.57 1103.57       0     403
Permanent Ineff=
       F       F
Bank Sta=901.61,1103.57
XS Rating Curve= 0 ,0
Exp/Cntr=0.3,0.1

Type RM Length L Ch R = 1 ,124432  ,211,192,176
BEGIN DESCRIPTION:
This cross section corresponds to cross section 124434 of the non-georeferenced CDC model which was the source of this model.
END DESCRIPTION:
XS GIS Cut Line= 2
2483804.166282186973074.455509722482223.224562176971725.38340472
#Sta/Elev= 30
       0     429   23.87     428   110.3  402.05  156.21     399  320.79     398
  488.11     401  693.85     402  731.06     395  744.63  394.34  769.08     395
  786.73  398.11  826.32     402  870.26     404  879.26     403  919.56     386
  929.71  385.19  936.75  381.21  957.25     378 1003.67     378  1031.2     380
 1085.58     403 1123.54     404 1215.58     402 1589.96     401 1697.14   397.1
 1831.23     397 1933.96  400.54 2028.55  423.96 2064.59     429 2078.31     429
#Mann= 3 ,0,0
       0    .055       0  870.26    .035       0 1085.58    .055       0
Levee=-1,0,431.08,-1,2064,431.08,Levee 1,Levee 2
#XS Ineff= 2 , 0
       0  870.26     404 1085.58       0     403
Permanent Ineff=
       F       F
Bank Sta=870.26,1085.58
XS Rating Curve= 0 ,0
Exp/Cntr=0.3,0.1

Type RM Length L Ch R = 1 ,124240  ,211,192,176
BEGIN DESCRIPTION:
This cross section corresponds to cross section 124243 of the non-georeferenced CDC model which was the source of this model.
END DESCRIPTION:
XS GIS Cut Line= 2
2483921.602727096972870.755129712482336.794544996971629.19232413
#Sta/Elev= 30
       0     429   12.62     428   90.99  403.49  105.75     400   134.9     399
   193.2  397.32  294.45     398  667.11  402.84  762.01     396  773.37  396.26
   826.6     403   842.5     402  856.72  395.15  867.55     393  895.99  381.71
  930.99  375.22  967.54     375  981.14  378.82 1016.58  392.72 1062.86     402
 1126.05     403 1585.82     401 1686.18     397 1764.77     397 1853.82     399
 1869.86     400 1917.05     413 1970.08     425 1995.34     429 2013.23  429.89
#Mann= 3 ,0,0
       0    .055       0   842.5    .035       0 1062.86    .055       0
Levee=-1,0,431,-1,2013,431,Levee 1,Levee 2
#XS Ineff= 2 , 0
       0   842.5     402 1062.86       0     402
Permanent Ineff=
       F       F
Bank Sta=842.5,1062.86
XS Rating Curve= 0 ,0
Exp/Cntr=0.3,0.1

Type RM Length L Ch R = 1 ,124048  ,220,200,183
BEGIN DESCRIPTION:
This cross section corresponds to cross section 124052 of the non-georeferenced CDC model which was the source of this model.
END DESCRIPTION:
XS GIS Cut Line= 2
2484060.052909496972683.077027382482453.743458096971534.35393113
#Sta/Elev= 30
       0     429   14.46     428  103.16  401.19  135.44  398.25  258.43  396.23
  445.73     397  624.84     402   661.7     402  673.62     404  708.46     402
  741.31  396.48  794.01     401  834.44     403  856.72     393  872.26  388.83
  883.53     382   899.7     376  979.51     376  991.54     382 1080.29     402
 1095.34     403 1432.32     401 1480.51  399.48  1574.2     400 1711.39     397
 1780.08     398 1830.77     400 1935.77     427 1961.05  430.93 1974.79     431
#Mann= 3 ,0,0
       0    .055       0  834.44    .035       0 1080.29    .055       0
Levee=-1,0,430.91,-1,1974,430.91,Levee 1,Levee 2
#XS Ineff= 2 , 0
       0  834.44     403 1080.29       0     402
Permanent Ineff=
       F       F
Bank Sta=834.44,1080.29
XS Rating Curve= 0 ,0
Exp/Cntr=0.3,0.1

Type RM Length L Ch R = 1 ,123848  ,191,191,191
BEGIN DESCRIPTION:
This cross section corresponds to cross section 123861 of the non-georeferenced CDC model which was the source of this model.
END DESCRIPTION:
XS GIS Cut Line= 2
2484177.643553586972469.601076382482540.137642266971407.27971022
#Sta/Elev= 30
       0     429   17.38  428.06   74.29  410.55  128.09  401.11  145.95     400
  389.83     395  516.55   399.9  664.69     401  681.67     403  741.68     396
   774.4     402  824.37     403  838.25     402  874.93  384.18  880.81  384.71
  895.01  377.01  924.17     376  964.22     376   995.6     382 1072.08  400.96
 1086.37     403 1395.65     402 1424.54  398.22 1486.91  397.11  1569.2     400
 1649.23     397 1802.64     399 1907.12  426.89 1932.53     432 1951.91  432.76
#Mann= 3 ,0,0
       0    .055       0  838.25    .035       0 1086.37    .055       0
Levee=-1,0,430.83,-1,1938,430.83,Levee 1,Levee 2
#XS Ineff= 2 , 0
       0  824.37     403 1086.37       0     403
Permanent Ineff=
       F       F
Bank Sta=838.25,1086.37
XS Rating Curve= 0 ,0
Exp/Cntr=0.3,0.1

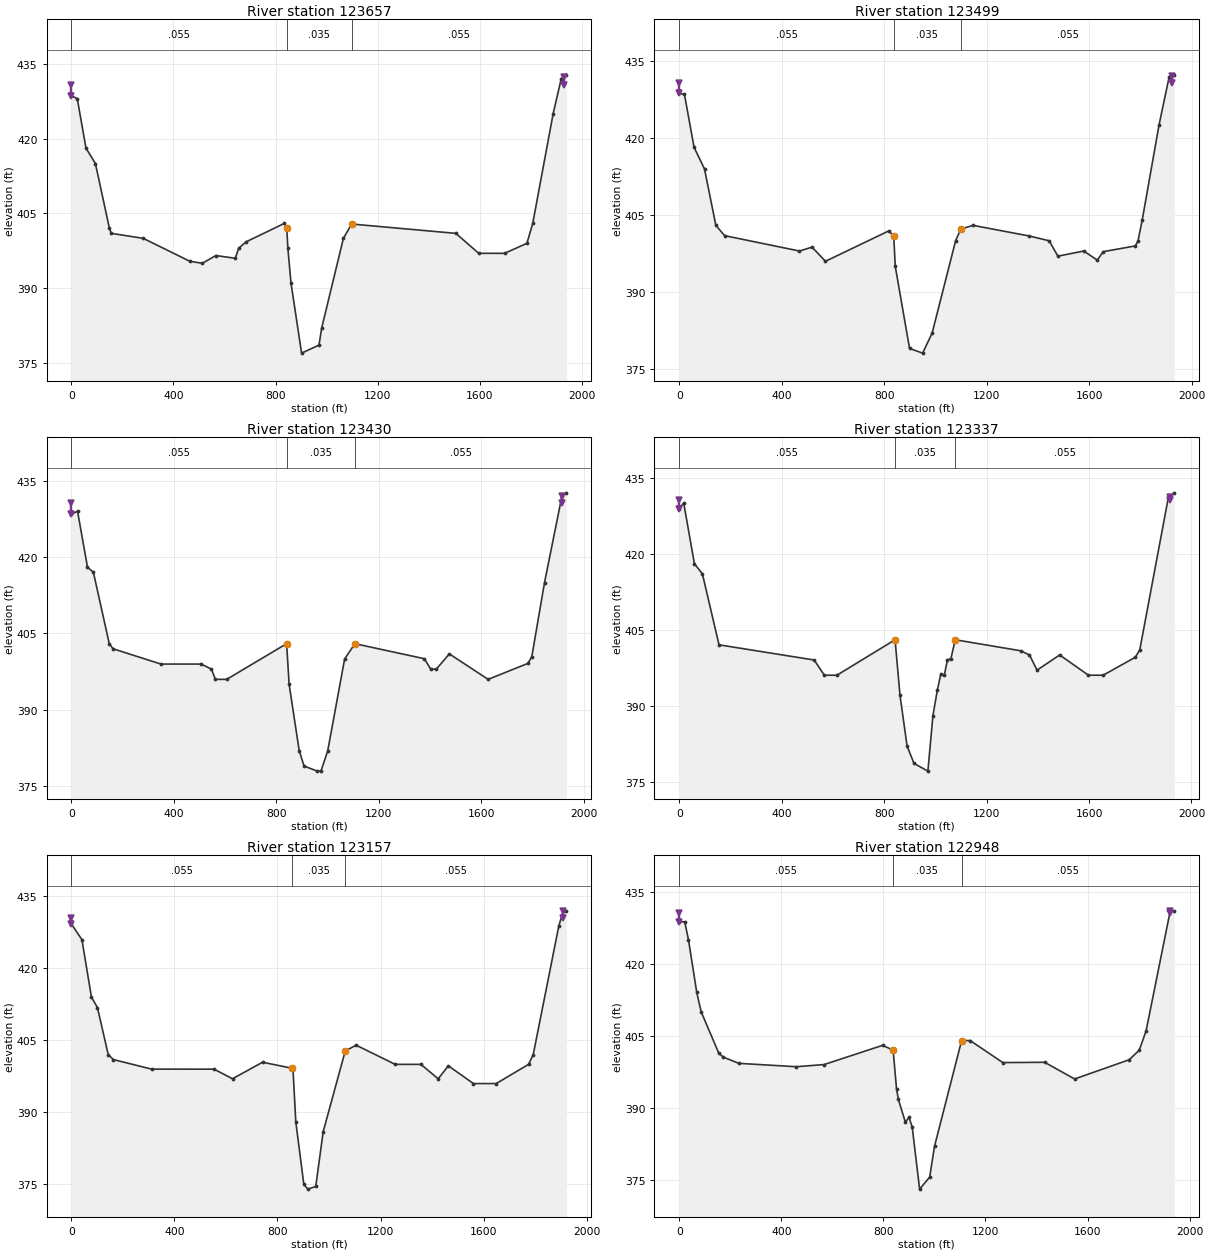
Type RM Length L Ch R = 1 ,123657  ,158,158,158
BEGIN DESCRIPTION:
This cross section corresponds to cross section 123661 of the non-georeferenced CDC model which was the source of this model.
END DESCRIPTION:
XS GIS Cut Line= 2
2484282.355286426972308.107632962482652.965828696971255.20127422
#Sta/Elev= 30
       0  428.58   22.93     428    57.1  418.07   94.03     415  148.94     402
  156.34     401  281.56     400  463.89  395.41  513.09     395  566.28  396.56
  642.19     396  655.29     398  684.55   399.3  834.38     403  843.96  402.05
  848.17  398.05  860.29  391.12  901.97     377  970.22  378.61  980.59     382
  1065.8     400 1098.14  402.87 1506.55     401 1596.03     397 1697.24     397
 1784.96     399 1807.83     403 1887.85     425 1919.53     432 1939.98  432.77
#Mann= 3 ,0,0
       0    .055       0  843.96    .035       0 1098.14    .055       0
Levee=-1,0,430.76,-1,1930,430.76,Levee 1,Levee 2
#XS Ineff= 2 , 0
       0  843.96  402.05 1098.14       0  402.87
Permanent Ineff=
       F       F
Bank Sta=843.96,1098.14
XS Rating Curve= 0 ,0
Exp/Cntr=0.3,0.1

Type RM Length L Ch R = 1 ,123499  ,69,69,69
BEGIN DESCRIPTION:
This cross section corresponds to cross section 123511 of the non-georeferenced CDC model which was the source of this model.
END DESCRIPTION:
XS GIS Cut Line= 2
2484373.445655446972177.868064052482749.959729166971130.54994872
#Sta/Elev= 30
       0  428.79   20.38  428.55   57.87  418.23   98.65     414     143     403
  177.09     401  469.29     398  518.45  398.76  570.69     396  817.27  401.91
  837.03     401  843.15     395  898.85     379  949.87  378.09  987.03     382
 1078.63     400 1098.89   402.3 1147.29     403 1366.07  400.93 1443.69     400
 1477.78     397 1578.69     398 1631.77  396.22 1654.24  397.87 1780.33     399
 1790.49     400 1806.69     404  1872.7  422.63  1912.2     432 1931.99  432.36
#Mann= 3 ,0,0
       0    .055       0  837.03    .035       0 1098.89    .055       0
Levee=-1,0,430.7,-1,1923,430.7,Levee 1,Levee 2
#XS Ineff= 2 , 0
       0  837.03     401 1098.89       0   402.3
Permanent Ineff=
       F       F
Bank Sta=837.03,1098.89
XS Rating Curve= 0 ,0
Exp/Cntr=0.3,0.1

Type RM Length L Ch R = 1 ,123430  ,93,93,93
BEGIN DESCRIPTION:
This cross section corresponds to cross section 123441 of the non-georeferenced CDC model which was the source of this model.
END DESCRIPTION:
XS GIS Cut Line= 2
2484419.400287936972123.47315972 2482793.39402556971078.38765147
#Sta/Elev= 30
       0  428.36   23.87     429   62.75     418   85.83     417  147.75     403
  162.58     402  349.47     399  506.63     399  546.84     398  562.18     396
  606.21     396  840.19     403  850.09     395  889.43     382  908.21     379
  960.09     378  974.22     378 1000.82     382 1066.73     400 1106.87     403
 1378.13  400.05  1402.8     398 1424.59     398 1475.56     401 1626.94     396
 1782.36  399.13 1797.63  400.47 1847.24     415 1915.02   431.9  1932.9  432.59
#Mann= 3 ,0,0
       0    .055       0  840.19    .035       0 1106.87    .055       0
Levee=-1,0,430.68,-1,1915,430.68,Levee 1,Levee 2
#XS Ineff= 2 , 0
       0  840.19     403 1106.87       0     403
Permanent Ineff=
       F       F
Bank Sta=840.19,1106.87
XS Rating Curve= 0 ,0
Exp/Cntr=0.3,0.1

Type RM Length L Ch R = 1 ,123337  ,180,180,180
BEGIN DESCRIPTION:
This cross section corresponds to cross section 123341 of the non-georeferenced CDC model which was the source of this model.
END DESCRIPTION:
XS GIS Cut Line= 2
2484450.962888846972033.776488722482824.870012436970988.82451038
#Sta/Elev= 30
       0  428.88   17.44     430   59.31     418    90.5     416  155.37     402
  526.96     399  566.62     396  615.64     396   842.7     403  862.02     392
  889.71     382   916.6   378.6  970.86  377.07  990.54     388 1007.59     393
 1021.23  396.21 1035.11     396 1046.84     399 1060.86   399.3 1077.65     403
 1332.82  400.83 1367.56     400 1397.04     397 1485.37     400 1597.88     396
 1655.21     396 1780.86  399.55 1798.08     401 1909.49  430.99  1932.9     432
#Mann= 3 ,0,0
       0    .055       0   842.7    .035       0 1077.65    .055       0
Levee=-1,0,430.64,-1,1916,430.64,Levee 1,Levee 2
#XS Ineff= 2 , 0
       0   842.7     403 1077.65       0     403
Permanent Ineff=
       F       F
Bank Sta=842.7,1077.65
XS Rating Curve= 0 ,0
Exp/Cntr=0.3,0.1

Type RM Length L Ch R = 1 ,123157  ,209,209,209
BEGIN DESCRIPTION:
This cross section corresponds to cross section 123161 of the non-georeferenced CDC model which was the source of this model.
END DESCRIPTION:
XS GIS Cut Line= 2
2484547.569651016971880.619642792482929.25136533 6970843.9386453
#Sta/Elev= 30
       0  429.24   40.76     426   77.83     414  101.07  411.83  142.99     402
  163.25     401  310.96  399.01  553.85     399  625.49     397  742.12  400.45
  858.26  399.17  860.39  398.73  871.16     388  902.23     375  917.77     374
  948.55  374.55  977.52     386 1063.09   402.8 1105.41     404 1256.91     400
 1356.72     400 1423.79     397 1463.39   399.7 1560.57     396 1649.11     396
 1774.66     400 1792.69     402  1892.3  428.88  1909.7     432 1921.89     432
#Mann= 3 ,0,0
       0    .055       0  858.26    .035       0 1063.09    .055       0
Levee=-1,0,430.58,-1,1909,430.58,Levee 1,Levee 2
#XS Ineff= 2 , 0
       0  858.26  399.17 1063.09       0   402.8
Permanent Ineff=
       F       F
Bank Sta=858.26,1063.09
XS Rating Curve= 0 ,0
Exp/Cntr=0.3,0.1

Type RM Length L Ch R = 1 ,122948  ,62,62,62
BEGIN DESCRIPTION:
This cross section corresponds to cross section 122961 of the non-georeferenced CDC model which was the source of this model.
END DESCRIPTION:
XS GIS Cut Line= 2
2484674.958175756971712.272866642483039.899109936970668.48919305
#Sta/Elev= 30
       0  428.71   21.36  428.73   36.18     425   68.72     414   85.77     410
  154.34  401.45  171.91  400.56   233.9  399.25  459.03  398.55  567.73     399
  796.81     403  838.09     402  851.41     394  858.76  391.74  886.07     387
  900.42     388  912.88     386  941.92  373.07  981.26  375.57 1000.35     382
 1106.63     404 1139.99     404  1267.9  399.41 1431.71  399.47 1549.36     396
 1763.13     400 1802.71     402 1829.32     406 1924.05     431 1939.82     431
#Mann= 3 ,0,0
       0    .055       0  838.09    .035       0 1106.63    .055       0
Levee=-1,0,430.51,-1,1924,430.51,Levee 1,Levee 2
#XS Ineff= 2 , 0
       0  838.09     402 1106.63       0     404
Permanent Ineff=
       F       F
Bank Sta=838.09,1106.63
XS Rating Curve= 0 ,0
Exp/Cntr=0.3,0.1