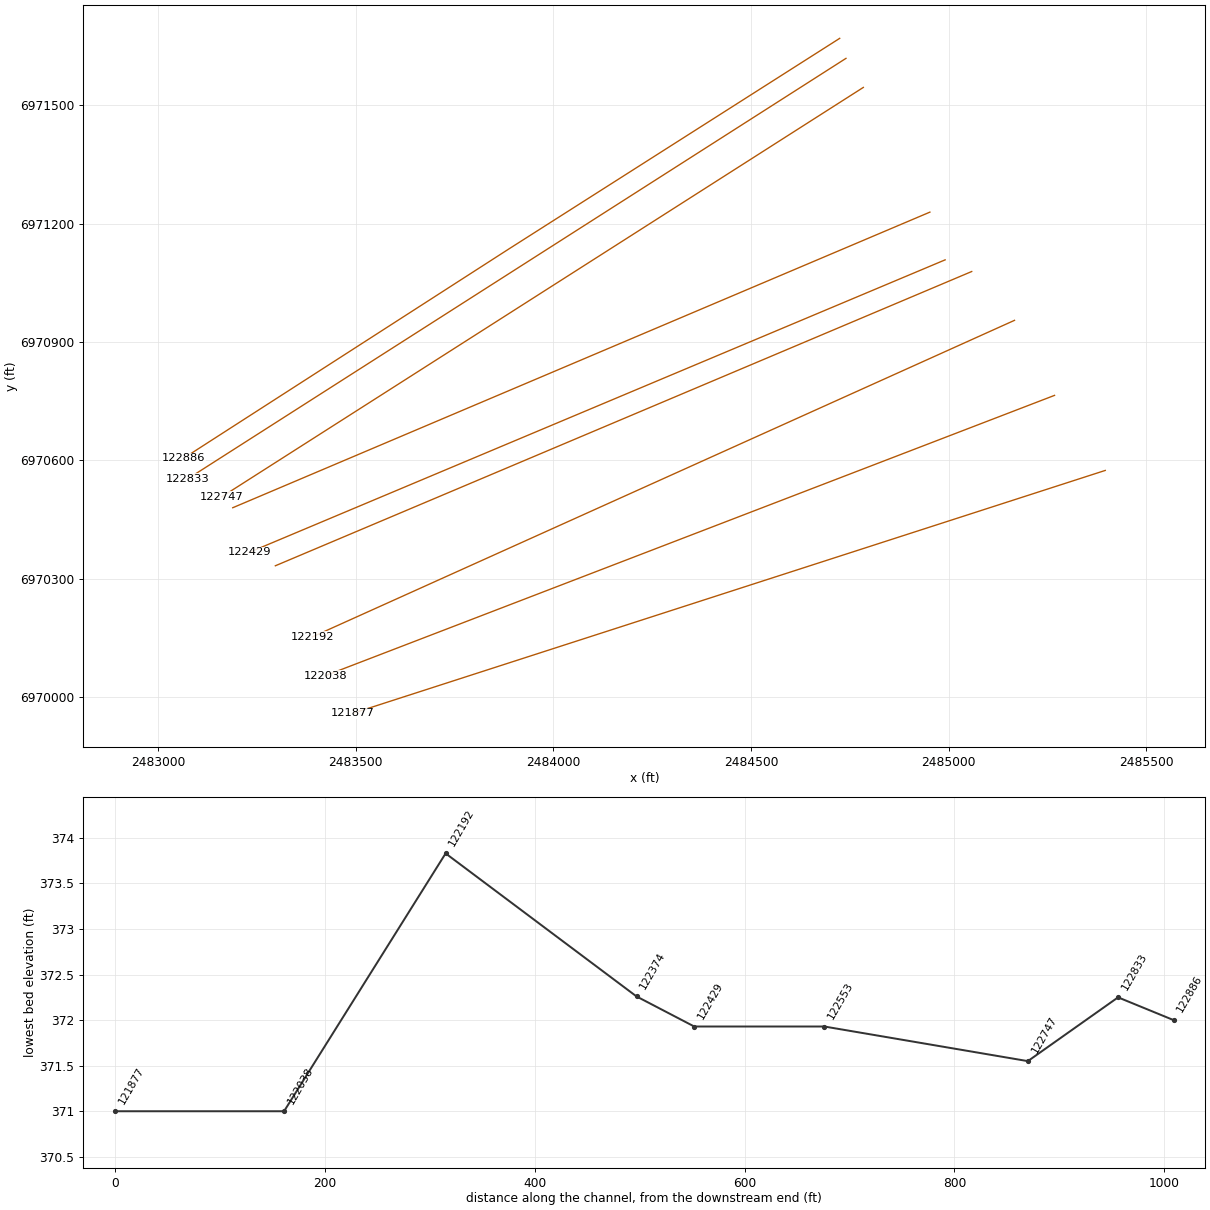
HEC-RAS study CDC_Consolidated_Model.prj: Upper Trinity CDC Consolidated Model

--- CDC_Consolidated_Model.g01 (geometry) --- (continued)

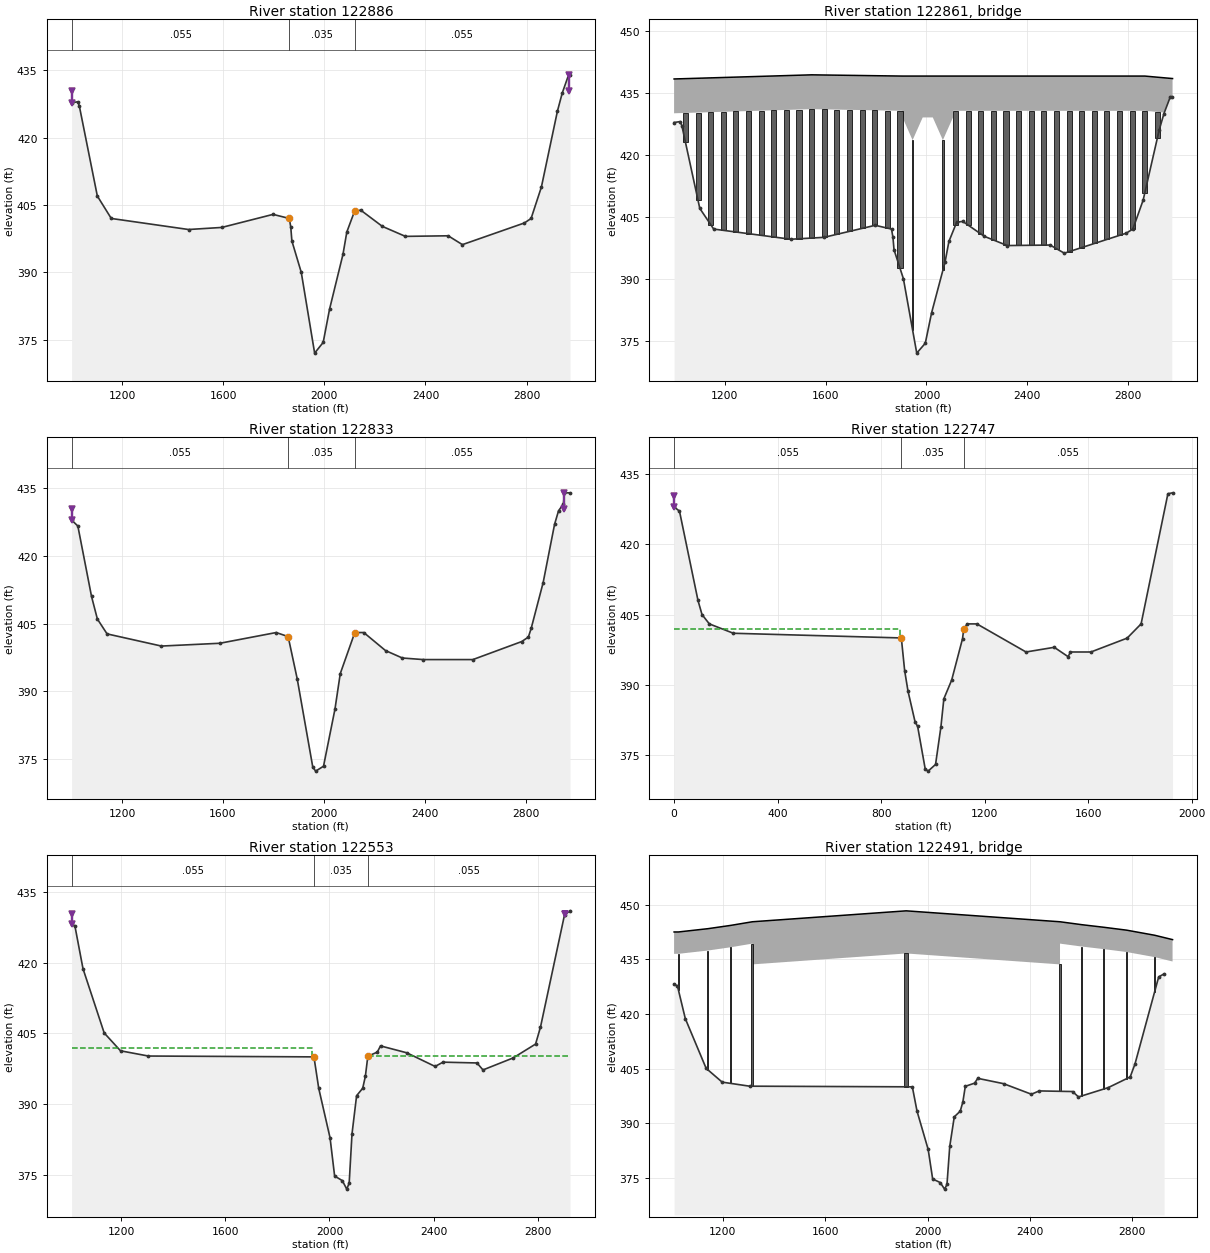
Type RM Length L Ch R = 1 ,122886  ,53,53,53
BEGIN DESCRIPTION:
This cross section corresponds to cross section 122886 of the non-georeferenced CDC model which was the source of this model.
END DESCRIPTION:
XS GIS Cut Line= 3
2484724.366213416971669.354973472483889.88559893 6971137.4951448
2483064.119205836970605.48111697
#Sta/Elev= 30
    1000  427.77 1024.62     428  1030.8     427 1101.83     407 1156.98     402
 1462.67  399.54 1593.93     400 1796.95  402.91 1861.45     402 1867.17     400
 1871.39     397 1908.54     390 1961.47     372 1995.29  374.39 2020.29  381.75
 2073.53     394 2088.85     399 2119.76  403.67 2143.92  403.85 2229.23  400.24
  2320.5  398.01 2489.74  398.14 2546.06  396.17  2791.3     401 2817.74     402
 2858.48     409  2922.1  425.96 2940.95  429.94 2966.27     434 2971.87     434
#Mann= 3 ,0,0
    1000    .055       0 1861.45    .035       0 2119.76    .055       0
Levee=-1,1000,430.48,-1,2966,430.48,Levee 1,Levee 2
#XS Ineff= 2 , 0
       0 1861.45     402 2119.76       0  403.67
Permanent Ineff=
       F       F
Bank Sta=1861.45,2119.76
XS Rating Curve= 0 ,0
Exp/Cntr=0.3,0.1

Type RM Length L Ch R = 3 ,122861  ,,,
BEGIN DESCRIPTION:
122860  Continental Avenue
END DESCRIPTION:
Node Name=Continental Ave.
Bridge Culvert--1,0,-1,-1, 0
Deck Dist Width WeirC Skew NumUp NumDn MinLoCord MaxHiCord MaxSubmerge Is_Ogee
1.5,48,2.6,0, 12, 12, , , 0.95, 0, ,,,
    1000    1545    1905    1905    1945    1985    2025    2065    2105    2105
    2865    2975
   438.3   439.3     439     439     439     439     439     439     439     439
     439   438.4
     430     431   430.6     429   423.5     429     429   423.5     429   430.6
   430.6     430
    1000    1545    1905    1905    1945    1985    2025    2065    2105    2105
    2865    2975
   438.3   439.3     439     439     439     439     439     439     439     439
     439   438.4
     430     431   430.6     429   423.5     429     429   423.5     429   430.6
   430.6     430
Pier Skew, UpSta & Num, DnSta & Num=  ,1045, 5 ,1045, 5 , 3 , 3 , 0 ,,
     5.5     2.5     3.5     3.5      20
     390     426     426   427.6   430.2
     5.5     2.5     3.5     3.5      20
     390     426     426   427.6   430.2
Pier Skew, UpSta & Num, DnSta & Num=  ,1095, 5 ,1095, 5 , 3 , 3 , 0 ,,
     5.5     2.5     3.5     3.5      20
   390.1   426.1   426.1   427.7   430.3
     5.5     2.5     3.5     3.5      20
   390.1   426.1   426.1   427.7   430.3
Pier Skew, UpSta & Num, DnSta & Num=  ,1145, 5 ,1145, 5 , 3 , 3 , 0 ,,
     5.5     2.5     3.5     3.5      20
   390.2   426.2   426.2   427.8   430.4
     5.5     2.5     3.5     3.5      20
   390.2   426.2   426.2   427.8   430.4
Pier Skew, UpSta & Num, DnSta & Num=  ,1195, 5 ,1195, 5 , 3 , 3 , 0 ,,
     5.5     2.5     3.5     3.5      20
   390.3   426.3   426.3   427.9   430.5
     5.5     2.5     3.5     3.5      20
   390.3   426.3   426.3   427.9   430.5
Pier Skew, UpSta & Num, DnSta & Num=  ,1245, 5 ,1245, 5 , 3 , 3 , 0 ,,
     5.5     2.5     3.5     3.5      20
   390.4   426.4   426.4     428   430.6
     5.5     2.5     3.5     3.5      20
   390.4   426.4   426.4     428   430.6
Pier Skew, UpSta & Num, DnSta & Num=  ,1295, 5 ,1295, 5 , 3 , 3 , 0 ,,
     5.5     2.5     3.5     3.5      20
   390.4   426.4   426.4     428   430.6
     5.5     2.5     3.5     3.5      20
   390.4   426.4   426.4     428   430.6
Pier Skew, UpSta & Num, DnSta & Num=  ,1345, 5 ,1345, 5 , 3 , 3 , 0 ,,
     5.5     2.5     3.5     3.5      20
   390.5   426.5   426.5   428.1   430.7
     5.5     2.5     3.5     3.5      20
   390.5   426.5   426.5   428.1   430.7
Pier Skew, UpSta & Num, DnSta & Num=  ,1395, 5 ,1395, 5 , 3 , 3 , 0 ,,
     5.5     2.5     3.5     3.5      20
   390.6   426.6   426.6   428.2   430.8
     5.5     2.5     3.5     3.5      20
   390.6   426.6   426.6   428.2   430.8
Pier Skew, UpSta & Num, DnSta & Num=  ,1445, 5 ,1445, 5 , 3 , 3 , 0 ,,
     5.5     2.5     3.5     3.5      20
   390.7   426.7   426.7   428.3   430.9
     5.5     2.5     3.5     3.5      20
   390.7   426.7   426.7   428.3   430.9
Pier Skew, UpSta & Num, DnSta & Num=  ,1495, 5 ,1495, 5 , 3 , 3 , 0 ,,
     5.5     2.5     3.5     3.5      20
   390.8   426.8   426.8   428.4     431
     5.5     2.5     3.5     3.5      20
   390.8   426.8   426.8   428.4     431
Pier Skew, UpSta & Num, DnSta & Num=  ,1545, 5 ,1545, 5 , 3 , 3 , 0 ,,
     5.5     2.5     3.5     3.5      20
   390.9   426.9   426.9   428.5   431.1
     5.5     2.5     3.5     3.5      20
   390.9   426.9   426.9   428.5   431.1
Pier Skew, UpSta & Num, DnSta & Num=  ,1595, 5 ,1595, 5 , 3 , 3 , 0 ,,
     5.5     2.5     3.5     3.5      20
   390.8   426.8   426.8   428.4     431
     5.5     2.5     3.5     3.5      20
   390.8   426.8   426.8   428.4     431
Pier Skew, UpSta & Num, DnSta & Num=  ,1645, 5 ,1645, 5 , 3 , 3 , 0 ,,
     5.5     2.5     3.5     3.5      20
   390.8   426.8   426.8   428.4     431
     5.5     2.5     3.5     3.5      20
   390.8   426.8   426.8   428.4     431
Pier Skew, UpSta & Num, DnSta & Num=  ,1695, 5 ,1695, 5 , 3 , 3 , 0 ,,
     5.5     2.5     3.5     3.5      20
   390.7   426.7   426.7   428.3   430.9
     5.5     2.5     3.5     3.5      20
   390.7   426.7   426.7   428.3   430.9
Pier Skew, UpSta & Num, DnSta & Num=  ,1745, 5 ,1745, 5 , 3 , 3 , 0 ,,
     5.5     2.5     3.5     3.5      20
   390.7   426.7   426.7   428.3   430.9
     5.5     2.5     3.5     3.5      20
   390.7   426.7   426.7   428.3   430.9
Pier Skew, UpSta & Num, DnSta & Num=  ,1795, 5 ,1795, 5 , 3 , 3 , 0 ,,
     5.5     2.5     3.5     3.5      20
   390.6   426.6   426.6   428.2   430.8
     5.5     2.5     3.5     3.5      20
   390.6   426.6   426.6   428.2   430.8
Pier Skew, UpSta & Num, DnSta & Num=  ,1845, 5 ,1845, 5 , 3 , 3 , 0 ,,
     5.5     2.5     3.5     3.5      20
   390.6   426.6   426.6   428.2   430.8
     5.5     2.5     3.5     3.5      20
   390.6   426.6   426.6   428.2   430.8
Pier Skew, UpSta & Num, DnSta & Num=  ,1895, 5 ,1895, 5 , 3 , 3 , 0 ,,
     5.5     2.5     3.5     3.5      20
   390.5   426.5   426.5   428.1   430.7
     5.5     2.5     3.5     3.5      20
   390.5   426.5   426.5   428.1   430.7
Pier Skew, UpSta & Num, DnSta & Num=  ,1945, 6 ,1945, 6 , 5 , 5 , 0 ,,
       6       6    5.25     2.5     3.5     3.5
     370   387.5   387.5   420.5   420.5     425
       6       6    5.25     2.5     3.5     3.5
     370   387.5   387.5   420.5   420.5     425
Pier Skew, UpSta & Num, DnSta & Num=  ,2065, 6 ,2065, 6 , 5 , 5 , 0 ,,
       6       6    5.25     2.5     3.5     3.5
     370   387.5   387.5   420.5   420.5     425
       6       6    5.25     2.5     3.5     3.5
     370   387.5   387.5   420.5   420.5     425
Pier Skew, UpSta & Num, DnSta & Num=  ,2115, 5 ,2115, 5 , 3 , 3 , 0 ,,
     5.5     2.5     3.5     3.5      20
   390.5   426.5   426.5   428.1   430.7
     5.5     2.5     3.5     3.5      20
   390.5   426.5   426.5   428.1   430.7
Pier Skew, UpSta & Num, DnSta & Num=  ,2165, 5 ,2165, 5 , 3 , 3 , 0 ,,
     5.5     2.5     3.5     3.5      20
   390.5   426.5   426.5   428.1   430.7
     5.5     2.5     3.5     3.5      20
   390.5   426.5   426.5   428.1   430.7
Pier Skew, UpSta & Num, DnSta & Num=  ,2215, 5 ,2215, 5 , 3 , 3 , 0 ,,
     5.5     2.5     3.5     3.5      20
   390.5   426.5   426.5   428.1   430.7
     5.5     2.5     3.5     3.5      20
   390.5   426.5   426.5   428.1   430.7
Pier Skew, UpSta & Num, DnSta & Num=  ,2265, 5 ,2265, 5 , 3 , 3 , 0 ,,
     5.5     2.5     3.5     3.5      20
   390.5   426.5   426.5   428.1   430.7
     5.5     2.5     3.5     3.5      20
   390.5   426.5   426.5   428.1   430.7
Pier Skew, UpSta & Num, DnSta & Num=  ,2315, 5 ,2315, 5 , 3 , 3 , 0 ,,
     5.5     2.5     3.5     3.5      20
   390.5   426.5   426.5   428.1   430.7
     5.5     2.5     3.5     3.5      20
   390.5   426.5   426.5   428.1   430.7
Pier Skew, UpSta & Num, DnSta & Num=  ,2365, 5 ,2365, 5 , 3 , 3 , 0 ,,
     5.5     2.5     3.5     3.5      20
   390.5   426.5   426.5   428.1   430.7
     5.5     2.5     3.5     3.5      20
   390.5   426.5   426.5   428.1   430.7
Pier Skew, UpSta & Num, DnSta & Num=  ,2415, 5 ,2415, 5 , 3 , 3 , 0 ,,
     5.5     2.5     3.5     3.5      20
   390.5   426.5   426.5   428.1   430.7
     5.5     2.5     3.5     3.5      20
   390.5   426.5   426.5   428.1   430.7
Pier Skew, UpSta & Num, DnSta & Num=  ,2465, 5 ,2465, 5 , 3 , 3 , 0 ,,
     5.5     2.5     3.5     3.5      20
   390.5   426.5   426.5   428.1   430.7
     5.5     2.5     3.5     3.5      20
   390.5   426.5   426.5   428.1   430.7
Pier Skew, UpSta & Num, DnSta & Num=  ,2515, 5 ,2515, 5 , 3 , 3 , 0 ,,
     5.5     2.5     3.5     3.5      20
   390.5   426.5   426.5   428.1   430.7
     5.5     2.5     3.5     3.5      20
   390.5   426.5   426.5   428.1   430.7
Pier Skew, UpSta & Num, DnSta & Num=  ,2565, 5 ,2565, 5 , 3 , 3 , 0 ,,
     5.5     2.5     3.5     3.5      20
   390.5   426.5   426.5   428.1   430.7
     5.5     2.5     3.5     3.5      20
   390.5   426.5   426.5   428.1   430.7
Pier Skew, UpSta & Num, DnSta & Num=  ,2615, 5 ,2615, 5 , 3 , 3 , 0 ,,
     5.5     2.5     3.5     3.5      20
   390.5   426.5   426.5   428.1   430.7
     5.5     2.5     3.5     3.5      20
   390.5   426.5   426.5   428.1   430.7
Pier Skew, UpSta & Num, DnSta & Num=  ,2665, 5 ,2665, 5 , 3 , 3 , 0 ,,
     5.5     2.5     3.5     3.5      20
   390.5   426.5   426.5   428.1   430.7
     5.5     2.5     3.5     3.5      20
   390.5   426.5   426.5   428.1   430.7
Pier Skew, UpSta & Num, DnSta & Num=  ,2715, 5 ,2715, 5 , 3 , 3 , 0 ,,
     5.5     2.5     3.5     3.5      20
   390.5   426.5   426.5   428.1   430.7
     5.5     2.5     3.5     3.5      20
   390.5   426.5   426.5   428.1   430.7
Pier Skew, UpSta & Num, DnSta & Num=  ,2765, 5 ,2765, 5 , 3 , 3 , 0 ,,
     5.5     2.5     3.5     3.5      20
   390.5   426.5   426.5   428.1   430.7
     5.5     2.5     3.5     3.5      20
   390.5   426.5   426.5   428.1   430.7
Pier Skew, UpSta & Num, DnSta & Num=  ,2815, 5 ,2815, 5 , 3 , 3 , 0 ,,
     5.5     2.5     3.5     3.5      20
   390.5   426.5   426.5   428.1   430.7
     5.5     2.5     3.5     3.5      20
   390.5   426.5   426.5   428.1   430.7
Pier Skew, UpSta & Num, DnSta & Num=  ,2865, 5 ,2865, 5 , 3 , 3 , 0 ,,
     5.5     2.5     3.5     3.5      20
   390.5   426.5   426.5   428.1   430.7
     5.5     2.5     3.5     3.5      20
   390.5   426.5   426.5   428.1   430.7
Pier Skew, UpSta & Num, DnSta & Num=  ,2915, 5 ,2915, 5 , 3 , 3 , 0 ,,
     5.5     2.5     3.5     3.5      20
   390.3   426.3   426.3   427.9   430.5
     5.5     2.5     3.5     3.5      20
   390.3   426.3   426.3   427.9   430.5
BR Coef= 1 , 1 , 1 ,0.9, 0 ,,,0.8,-1,0.33,1,
WSPro=,,,, 1 ,,,, 0 ,,,, 0 ,,,,-1 ,-1 ,-1 , 0 , 0 , 0 , 0 , 0
BC Design=,, 0 ,, 0 ,,,,,,
BC HTab HWMax=432
BC Use User HTab Curves=0
BC User HTab FreeFlow(D)= 0

Type RM Length L Ch R = 1 ,122833  ,86,86,86
BEGIN DESCRIPTION:
This cross section corresponds to cross section 122834 of the non-georeferenced CDC model which was the source of this model.
END DESCRIPTION:
XS GIS Cut Line= 2
2484740.22707409 6971618.61426132483075.269446026970553.79716522
#Sta/Elev= 30
    1000  427.97 1024.84  426.63  1079.1     411 1102.22     406 1140.66   402.7
 1356.11     400 1587.92  400.62 1811.19     403 1858.61   402.1 1894.47  392.75
 1956.41   373.1 1967.82  372.25 1998.86  373.34 2044.21     386 2065.27  393.89
 2122.85     403 2158.44     403 2244.62     399 2311.43  397.35 2394.45     397
 2591.01     397 2784.71     401 2811.03     402 2822.12   403.9 2869.72   414.1
 2914.87     427 2930.58     430 2949.98  431.54 2954.24     434 2976.34     434
#Mann= 3 ,0,0
    1000    .055       0 1858.61    .035       0 2122.85    .055       0
Levee=-1,1000,430.46,-1,2954,430.46,Levee 1,Levee 2
#XS Ineff= 2 , 0
       0 1858.61   402.1 2122.85       0     403
Permanent Ineff=
       F       F
Bank Sta=1858.61,2122.85
XS Rating Curve= 0 ,0
Exp/Cntr=0.3,0.1

Type RM Length L Ch R = 1 ,122747  ,255,194,137
BEGIN DESCRIPTION:
This cross section corresponds to cross section 122760 of the non-georeferenced CDC model which was the source of this model.
END DESCRIPTION:
XS GIS Cut Line= 2
2484784.139387856971545.035340222483161.140993426970508.11779463
#Sta/Elev= 30
       0     428   20.88  427.08   92.37     408  107.86     405   136.2     403
  229.15     401  878.01     400   890.9     393  903.76  388.64  930.98   382.1
  941.03  381.09  970.32     372  981.58  371.55 1010.24  372.98 1030.93     381
 1042.29     387 1072.54     391 1114.49  399.85 1119.01  401.86 1132.56     403
 1169.92     403 1359.72     397 1468.86     398 1522.36     396 1531.54     397
  1610.6     397 1750.44  399.96 1804.38     403 1907.95   430.8 1925.96     431
#Mann= 3 ,0,0
       0    .055       0  878.01    .035       0 1119.01    .055       0
Levee=-1,0,430.42,-1,1926,430.42,Levee 1,Levee 2
#XS Ineff= 2 , 0
       0     873     402 1119.01       0  401.86
Permanent Ineff=
       F       F
Bank Sta=878.01,1119.01
XS Rating Curve= 0 ,0
Exp/Cntr=0.3,0.1

Type RM Length L Ch R = 1 ,122553  ,124,124,124
BEGIN DESCRIPTION:
This cross section corresponds to cross section 122562 of the non-georeferenced CDC model which was the source of this model.
--------------------------------------------------------------------
CDC DAL051805-1 Woodall Rogers Extension (Margaret Hunt Hill Bridge)
--------------------------------------------------------------------
END DESCRIPTION:
XS GIS Cut Line= 2
   2484952.58716   6971229.09232   2483188.57776   6970480.22018
#Sta/Elev= 30
    1009  428.17 1022.05   427.7 1052.84  418.72 1134.25  405.08 1196.96  401.29
    1304  400.18 1940.35     400 1958.72  393.32 2002.27  382.81 2019.78  374.72
 2049.41  373.73 2066.38  371.93 2075.75  373.21 2086.59  383.66 2104.25  391.76
 2127.69  393.34  2137.9  395.86 2147.41  400.14  2183.7  401.01 2196.13  402.33
 2296.92  400.87 2405.91  397.97 2436.36  398.88 2566.83  398.71  2589.9  397.23
 2705.59  399.77 2792.02  402.72 2810.77  406.29 2903.41  430.18 2924.53     431
#Mann= 3 ,0,0
    1009    .055       0 1940.35    .035       0 2147.41    .055       0
Levee=-1,1009,430.25,-1,2907,430.25,Levee 1,Levee 2
#XS Ineff= 2 , 0
         1934.17401.7998 2147.41        400.1407
Permanent Ineff=
       F       F
Bank Sta=1940.35,2147.41
XS Rating Curve= 0 ,0
Exp/Cntr=0.3,0.1

Type RM Length L Ch R = 3 ,122491  ,,,
BEGIN DESCRIPTION:
122500  Woodall Rodgers Freeway
-----------------------------------------------------------------------
CDC DAL051805-1 Woodall Rogers Extension (Margaret Hunt Hill Bridge)
-----------------------------------------------------------------------
END DESCRIPTION:
Node Name=Woodall Rogers
Bridge Culvert--1,0,-1,-1, 0
Deck Dist Width WeirC Skew NumUp NumDn MinLoCord MaxHiCord MaxSubmerge Is_Ogee
2,120,2.6,0, 14, 14, , , 0.95, 0, 0,0,,
    1009    1026    1141    1230    1315    1315  1916.3  2517.6  2517.6  2602.6
  2687.6  2777.6  2887.6  2957.6
   442.5   442.5   443.4   444.3   445.3   445.3   448.3   445.3   445.3   444.5
   443.8     443   441.6   440.4
   436.5   436.5   437.4   438.3   439.3   433.6   436.6   433.6   439.3   438.5
   437.8     437   435.6   434.4
    1009    1026    1141    1230    1315    1315  1916.3  2517.6  2517.6  2602.6
  2687.6  2777.6  2887.6  2957.6
   442.5   442.5   443.4   444.3   445.3   445.3   448.3   445.3   445.3   444.5
   443.8     443   441.6   440.4
   436.5   436.5   437.4   438.3   439.3   433.6   436.6   433.6   439.3   438.5
   437.8     437   435.6   434.4
Pier Skew, UpSta & Num, DnSta & Num=  ,1026, 2 ,1026, 2 , 0 , 0 , 0 ,,
     3.5     3.5
       0     440
     3.5     3.5
       0     440
Pier Skew, UpSta & Num, DnSta & Num=  ,1141, 2 ,1141, 2 , 0 , 0 , 0 ,,
     3.5     3.5
       0     440
     3.5     3.5
       0     440
Pier Skew, UpSta & Num, DnSta & Num=  ,1230, 2 ,1230, 2 , 0 , 0 , 0 ,,
     3.5     3.5
       0     440
     3.5     3.5
       0     440
Pier Skew, UpSta & Num, DnSta & Num=  ,1315, 2 ,1315, 2 , 0 , 0 , 0 ,,
       8       8
       0     440
       8       8
       0     440
Pier Skew, UpSta & Num, DnSta & Num=  ,1916.3, 2 ,1916.3, 2 , 0 , 0 , 0 ,,
      16      16
       0     440
      16      16
       0     440
Pier Skew, UpSta & Num, DnSta & Num=  ,2517.6, 2 ,2517.6, 2 , 0 , 0 , 0 ,,
       8       8
       0     440
       8       8
       0     440
Pier Skew, UpSta & Num, DnSta & Num=  ,2602.6, 2 ,2602.6, 2 , 0 , 0 , 0 ,,
     3.5     3.5
       0     440
     3.5     3.5
       0     440
Pier Skew, UpSta & Num, DnSta & Num=  ,2687.6, 2 ,2687.6, 2 , 0 , 0 , 0 ,,
     3.5     3.5
       0     440
     3.5     3.5
       0     440
Pier Skew, UpSta & Num, DnSta & Num=  ,2777.6, 2 ,2777.6, 2 , 0 , 0 , 0 ,,
     3.5     3.5
       0     440
     3.5     3.5
       0     440
Pier Skew, UpSta & Num, DnSta & Num=  ,2887.6, 2 ,2887.6, 2 , 0 , 0 , 0 ,,
     3.5     3.5
       0     440
     3.5     3.5
       0     440
BR Coef=-1 , 1 , 1 ,1.05, 0 ,,,0.8,-1,1.2,1,
WSPro=,,,, 1 ,,,, 0 ,,,, 0 ,,,,-1 ,-1 ,-1 , 0 , 0 , 0 , 0 , 0
BC Design=,, 0 ,, 0 ,,,,,,
BC Use User HTab Curves=0
BC User HTab FreeFlow(D)= 0

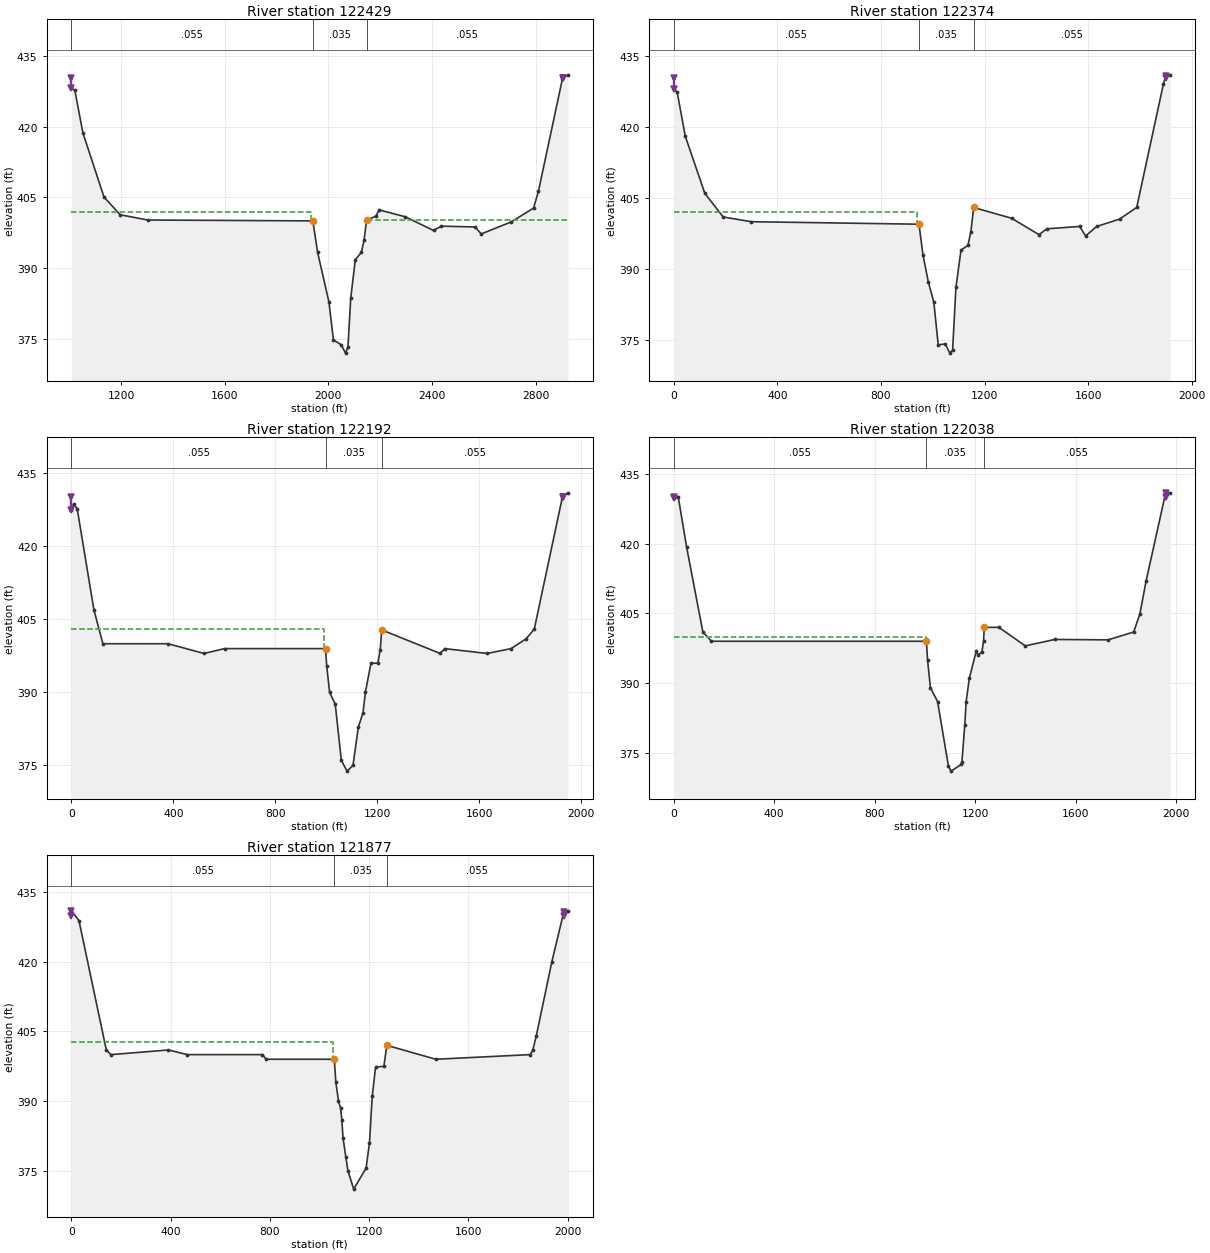
Type RM Length L Ch R = 1 ,122429  ,29,55,81
BEGIN DESCRIPTION:
This cross section corresponds to cross section 122438 of the non-georeferenced CDC model which was the source of this model.
---------------------------------------------------------------------
CDC DAL051805-1 Woodall Rogers Extension (Margaret Hunt Hill Bridge)
---------------------------------------------------------------------
END DESCRIPTION:
XS GIS Cut Line= 2
   2484991.10834   6971108.17262    2483229.8749   6970366.88336
#Sta/Elev= 30
    1009  428.17 1022.05   427.7 1052.84  418.72 1134.25  405.08 1196.96  401.29
    1304  400.18 1940.35     400 1958.72  393.32 2002.27  382.81 2019.78  374.72
 2049.41  373.73 2066.38  371.93 2075.75  373.21 2086.59  383.66 2104.25  391.76
 2127.69  393.34  2137.9  395.86 2147.41  400.14  2183.7  401.01 2196.13  402.33
 2296.92  400.87 2405.91  397.97 2436.36  398.88 2566.83  398.71  2589.9  397.23
 2705.59  399.77 2792.02  402.72 2810.77  406.29 2903.41  430.18 2924.53     431
#Mann= 3 ,0,0
    1009    .055       0 1940.35    .035       0 2147.41    .055       0
Levee=-1,1009,430.25,-1,2907,430.25,Levee 1,Levee 2
#XS Ineff= 2 , 0
         1934.17401.7998 2147.41        400.1407
Permanent Ineff=
       F       F
Bank Sta=1940.35,2147.41
XS Rating Curve= 0 ,0
Exp/Cntr=0.3,0.1

Type RM Length L Ch R = 1 ,122374  ,201,182,168
BEGIN DESCRIPTION:
This cross section corresponds to cross section 122390 of the non-georeferenced CDC model which was the source of this model.
END DESCRIPTION:
XS GIS Cut Line= 2
   2485058.35428   6971078.62944   2483296.37911   6970333.17841
#Sta/Elev= 30
       0     428   13.24  427.33   44.47  418.04  119.83     406  190.68     401
  299.26     400  946.94  399.47  962.23     393  983.05  387.25 1004.24     383
 1021.14     374 1048.35   374.2  1066.1  372.26 1076.74  372.93 1089.58  386.14
 1109.12     394 1135.73     395 1147.34  397.91 1158.14     403 1304.12  400.73
 1410.54  397.26 1440.27   398.5 1567.66     399 1590.19     397 1633.22     399
 1721.26  400.55 1787.53     403 1890.44     429 1899.58  430.93 1916.91     431
#Mann= 3 ,0,0
       0    .055       0  946.94    .035       0 1158.14    .055       0
Levee=-1,0,430.23,-1,1899,430.23,Levee 1,Levee 2
#XS Ineff= 2 , 0
       0  938.54  402.08 1158.14       0     403
Permanent Ineff=
       F       F
Bank Sta=946.94,1158.14
XS Rating Curve= 0 ,0
Exp/Cntr=0.3,0.1

Type RM Length L Ch R = 1 ,122192  ,179,154,137
BEGIN DESCRIPTION:
This cross section corresponds to cross section 122206 of the non-georeferenced CDC model which was the source of this model.
END DESCRIPTION:
XS GIS Cut Line= 2
2485166.659620176970954.970575472483390.683841416970153.37080072
#Sta/Elev= 30
       0  427.43    8.47  428.72   22.46  427.73   87.84     407  123.25     400
  379.15     400  519.95     398  601.04     399     997     399 1001.99  395.33
 1013.11     390 1035.27   387.6 1059.04  376.06 1081.55  373.83 1104.84     375
 1125.92  382.89 1144.34  385.83 1153.51     390 1175.38     396 1202.55     396
 1211.98   398.8 1217.55  402.84 1447.39     398  1464.9     399 1631.46     398
 1725.26     399 1784.13     401 1816.42     403 1926.28  429.98  1948.5     431
#Mann= 3 ,0,0
       0    .055       0     997    .035       0 1217.55    .055       0
Levee=-1,0,430.13,-1,1931,430.13,Levee 1,Levee 2
#XS Ineff= 2 , 0
       0  993.03     403 1217.55       0  402.84
Permanent Ineff=
       F       F
Bank Sta=997,1217.55
XS Rating Curve= 0 ,0
Exp/Cntr=0.3,0.1

Type RM Length L Ch R = 1 ,122038  ,187,161,144
BEGIN DESCRIPTION:
This cross section corresponds to cross section 122045 of the non-georeferenced CDC model which was the source of this model.
END DESCRIPTION:
XS GIS Cut Line= 2
2485267.943538346970764.867609222483422.764485936970054.74173288
#Sta/Elev= 30
       0   429.9    18.2     430   50.89  419.38  115.93     401     150     399
 1006.15     399 1010.65     395 1022.17     389 1050.72     386 1093.72  372.12
  1104.1     371 1145.39  372.44 1147.66     373 1159.09     381 1164.32  385.94
  1177.1     391 1204.37  396.81 1213.43     396 1227.39  396.77 1233.73     399
 1236.57     402 1294.76     402 1399.84     398 1517.43  399.39  1729.9   399.3
 1831.74     401 1856.32  404.89 1881.11     412 1959.09     431 1977.11     431
#Mann= 3 ,0,0
       0    .055       0 1006.15    .035       0 1236.57    .055       0
Levee=-1,0,430.03,-1,1959,430.03,Levee 1,Levee 2
#XS Ineff= 2 , 0
       0 1005.13     400 1236.57       0     402
Permanent Ineff=
       F       F
Bank Sta=1006.15,1236.57
XS Rating Curve= 0 ,0
Exp/Cntr=0.3,0.1

Type RM Length L Ch R = 1 ,121877  ,197,170,151
BEGIN DESCRIPTION:
This cross section corresponds to cross section 121884 of the non-georeferenced CDC model which was the source of this model.
END DESCRIPTION:
XS GIS Cut Line= 2
2485396.303845916970574.726913382483491.89623743 6969959.2652178
#Sta/Elev= 30
       0     431   30.15  428.89  140.45     401  159.13     400  391.05     401
  466.82     400     770     400     785     399 1059.57     399 1065.88     394
 1076.43     390 1085.12  388.44  1089.8     386 1094.78     382 1105.68  378.03
 1114.41     375 1137.64     371  1187.8  375.54 1201.42     381 1212.47     391
 1225.95  397.35 1259.45  397.46 1271.26     402 1468.78     399 1849.86     400
  1859.9     401 1873.69     404 1936.56     420 1985.86     431 2001.39     431
#Mann= 3 ,0,0
       0    .055       0 1059.57    .035       0 1271.26    .055       0
Levee=-1,0,429.93,-1,1985,429.93,Levee 1,Levee 2
#XS Ineff= 2 , 0
       0 1055.09  402.73 1271.26       0     402
Permanent Ineff=
       F       F
Bank Sta=1059.57,1271.26
XS Rating Curve= 0 ,0
Exp/Cntr=0.3,0.1