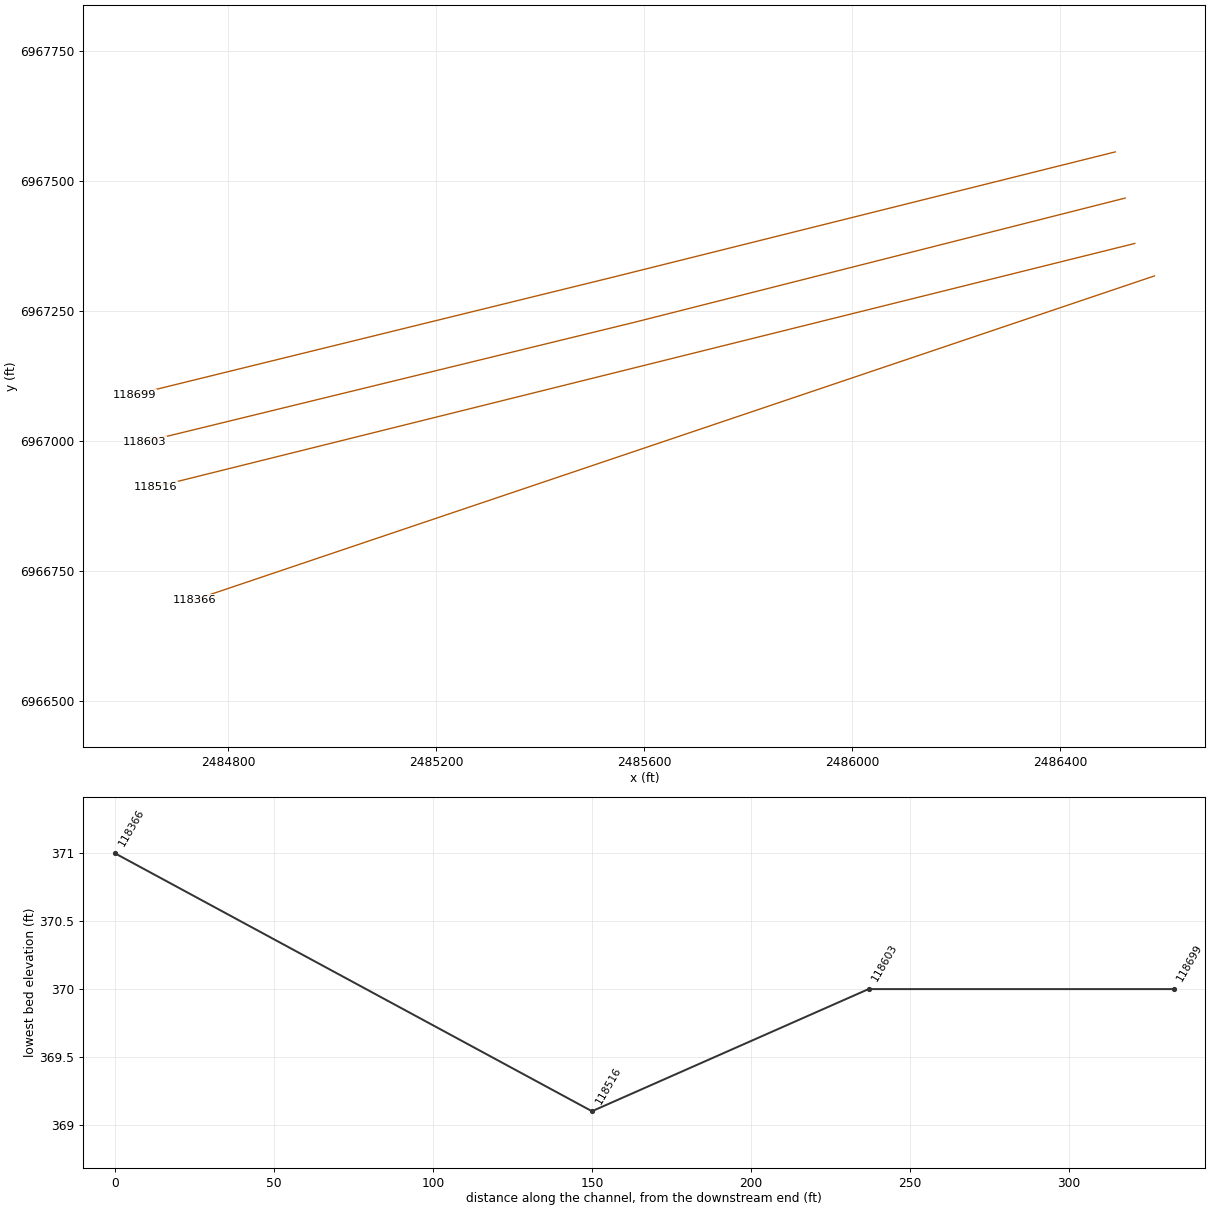
HEC-RAS study CDC_Consolidated_Model.prj: Upper Trinity CDC Consolidated Model

--- CDC_Consolidated_Model.g01 (geometry) --- (continued)

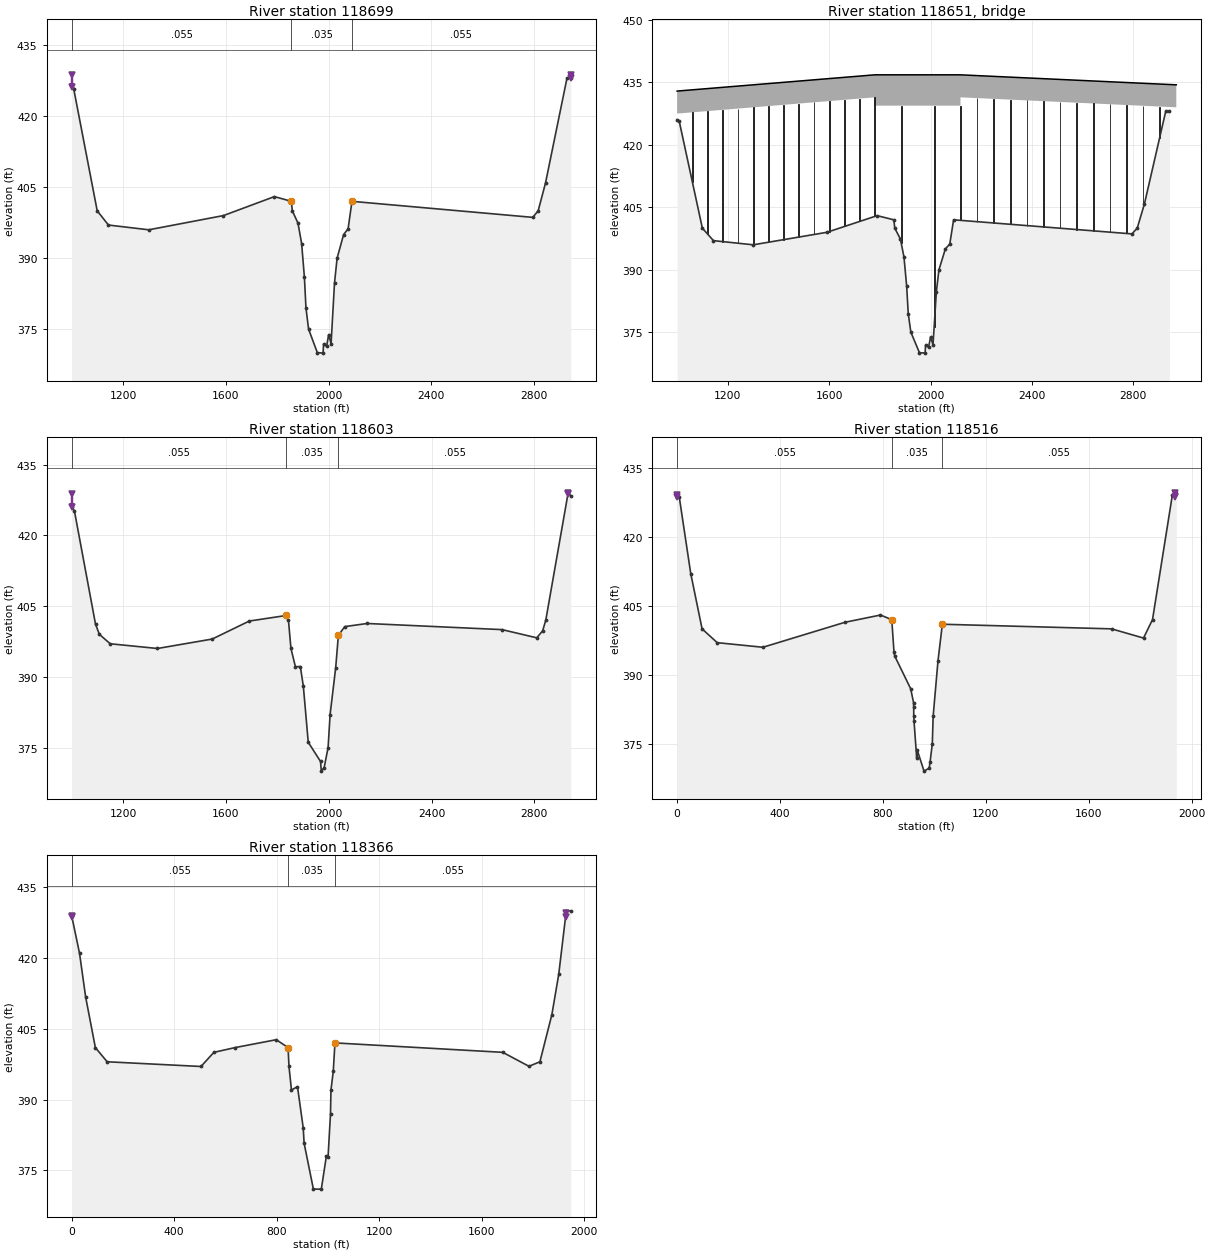
Type RM Length L Ch R = 1 ,118699  ,96,96,96
BEGIN DESCRIPTION:
This cross section corresponds to cross section 118703 of the non-georeferenced CDC model which was the source of this model.
END DESCRIPTION:
XS GIS Cut Line= 3
2486505.268163416967556.82415655 2485541.73728216967316.33808896
2484619.903495856967089.75816154
#Sta/Elev= 30
    1000     426 1008.54   425.6 1099.55     400 1143.31     397 1300.31     396
  1590.9     399 1789.14     403 1855.04     402 1858.71     400 1880.92  397.39
 1895.01  393.08 1905.76     386 1911.86  379.51 1922.09  375.05 1955.96  370.12
  1978.4     370  1980.3  371.91 1992.21  371.44 2000.14   373.9 2009.57     372
 2022.88  384.76 2032.98     390 2058.33     395 2075.81   396.2 2090.86     402
 2794.45  398.62 2815.41     400 2843.94  405.86 2927.65     428 2942.36     428
#Mann= 3 ,0,0
    1000    .055       0 1855.04    .035       0 2090.86    .055       0
Levee=-1,1000,428.67,-1,2942,428.67,Levee 1,Levee 2
#XS Ineff= 2 , 0
       0 1855.04     402 2090.86       0     402
Permanent Ineff=
       F       F
Bank Sta=1855.04,2090.86
XS Rating Curve= 0 ,0
Exp/Cntr=0.3,0.1

Type RM Length L Ch R = 3 ,118651  ,,,
BEGIN DESCRIPTION:
118657  IH 30
END DESCRIPTION:
Node Name=IH 30
Bridge Culvert--1,0,-1,-1, 0
Deck Dist Width WeirC Skew NumUp NumDn MinLoCord MaxHiCord MaxSubmerge Is_Ogee
4,88,2.6,0, 6, 6, , , 0.95, 0, ,,,
    1000    1780    1780    2118    2118  2969.5
   432.9   436.8   436.8   436.8   436.8   434.4
   427.5   431.4   429.4   429.4   431.4     429
    1000    1780    1780    2118    2118  2969.5
   432.9   436.8   436.8   436.8   436.8   434.4
   427.5   431.4   429.4   429.4   431.4     429
Pier Skew, UpSta & Num, DnSta & Num=  ,1060, 2 ,1060, 2 , 0 , 0 , 0 ,,
       3       3
     380   431.5
       3       3
     380   431.5
Pier Skew, UpSta & Num, DnSta & Num=  ,1120, 2 ,1120, 2 , 0 , 0 , 0 ,,
       3       3
       0     432
       3       3
       0     432
Pier Skew, UpSta & Num, DnSta & Num=  ,1180, 2 ,1180, 2 , 0 , 0 , 0 ,,
       3       3
       0   431.5
       3       3
       0   431.5
Pier Skew, UpSta & Num, DnSta & Num=  ,1240, 2 ,1240, 2 , 0 , 0 , 0 ,,
       3       3
       0   431.5
       3       3
       0   431.5
Pier Skew, UpSta & Num, DnSta & Num=  ,1300, 2 ,1300, 2 , 0 , 0 , 0 ,,
       3       3
       0   431.5
       3       3
       0   431.5
Pier Skew, UpSta & Num, DnSta & Num=  ,1360, 2 ,1360, 2 , 0 , 0 , 0 ,,
       3       3
       0   431.5
       3       3
       0   431.5
Pier Skew, UpSta & Num, DnSta & Num=  ,1420, 2 ,1420, 2 , 0 , 0 , 0 ,,
       3       3
       0   431.5
       3       3
       0   431.5
Pier Skew, UpSta & Num, DnSta & Num=  ,1480, 2 ,1480, 2 , 0 , 0 , 0 ,,
       3       3
       0   431.5
       3       3
       0   431.5
Pier Skew, UpSta & Num, DnSta & Num=  ,1540, 2 ,1540, 2 , 0 , 0 , 0 ,,
       3       3
       0   431.5
       3       3
       0   431.5
Pier Skew, UpSta & Num, DnSta & Num=  ,1600, 2 ,1600, 2 , 0 , 0 , 0 ,,
       3       3
       0   431.5
       3       3
       0   431.5
Pier Skew, UpSta & Num, DnSta & Num=  ,1660, 2 ,1660, 2 , 0 , 0 , 0 ,,
       3       3
       0   431.5
       3       3
       0   431.5
Pier Skew, UpSta & Num, DnSta & Num=  ,1720, 2 ,1720, 2 , 0 , 0 , 0 ,,
       3       3
       0   431.5
       3       3
       0   431.5
Pier Skew, UpSta & Num, DnSta & Num=  ,1780, 2 ,1780, 2 , 0 , 0 , 0 ,,
       3       3
       0   431.5
       3       3
       0   431.5
Pier Skew, UpSta & Num, DnSta & Num=  ,1884, 2 ,1884, 2 , 0 , 0 , 0 ,,
       4       4
       0   431.5
       4       4
       0   431.5
Pier Skew, UpSta & Num, DnSta & Num=  ,2014, 2 ,2014, 2 , 0 , 0 , 0 ,,
       4       4
       0   431.5
       4       4
       0   431.5
Pier Skew, UpSta & Num, DnSta & Num=  ,2118, 2 ,2118, 2 , 0 , 0 , 0 ,,
       3       3
       0   431.5
       3       3
       0   431.5
Pier Skew, UpSta & Num, DnSta & Num=  ,2183.5, 2 ,2183.5, 2 , 0 , 0 , 0 ,,
       3       3
       0   431.5
       3       3
       0   431.5
Pier Skew, UpSta & Num, DnSta & Num=  ,2249, 2 ,2249, 2 , 0 , 0 , 0 ,,
       3       3
       0   431.5
       3       3
       0   431.5
Pier Skew, UpSta & Num, DnSta & Num=  ,2314.5, 2 ,2314.5, 2 , 0 , 0 , 0 ,,
       3       3
       0   431.5
       3       3
       0   431.5
Pier Skew, UpSta & Num, DnSta & Num=  ,2380, 2 ,2380, 2 , 0 , 0 , 0 ,,
       3       3
       0   431.5
       3       3
       0   431.5
Pier Skew, UpSta & Num, DnSta & Num=  ,2445.5, 2 ,2445.5, 2 , 0 , 0 , 0 ,,
       3       3
       0   431.5
       3       3
       0   431.5
Pier Skew, UpSta & Num, DnSta & Num=  ,2511, 2 ,2511, 2 , 0 , 0 , 0 ,,
       3       3
       0   431.5
       3       3
       0   431.5
Pier Skew, UpSta & Num, DnSta & Num=  ,2576.5, 2 ,2576.5, 2 , 0 , 0 , 0 ,,
       3       3
       0   431.5
       3       3
       0   431.5
Pier Skew, UpSta & Num, DnSta & Num=  ,2642, 2 ,2642, 2 , 0 , 0 , 0 ,,
       3       3
       0   431.5
       3       3
       0   431.5
Pier Skew, UpSta & Num, DnSta & Num=  ,2707.5, 2 ,2707.5, 2 , 0 , 0 , 0 ,,
       3       3
       0   431.5
       3       3
       0   431.5
Pier Skew, UpSta & Num, DnSta & Num=  ,2773, 2 ,2773, 2 , 0 , 0 , 0 ,,
       3       3
       0   431.5
       3       3
       0   431.5
Pier Skew, UpSta & Num, DnSta & Num=  ,2838.5, 2 ,2838.5, 2 , 0 , 0 , 0 ,,
       3       3
       0   431.5
       3       3
       0   431.5
Pier Skew, UpSta & Num, DnSta & Num=  ,2904, 2 ,2904, 2 , 0 , 0 , 0 ,,
       3       3
       0   431.5
       3       3
       0   431.5
BR Coef= 1 , 1 , 1 ,1.05, 0 ,,,0.8,-1,1.2,1,
WSPro=,,,, 1 ,,,, 0 ,,,, 0 ,,,,-1 ,-1 ,-1 , 0 , 0 , 0 , 0 , 0
BC Design=,, 0 ,, 0 ,,,,,,
BC HTab HWMax=431
BC Use User HTab Curves=0
BC User HTab FreeFlow(D)= 0

Type RM Length L Ch R = 1 ,118603  ,87,87,87
BEGIN DESCRIPTION:
This cross section corresponds to cross section 118611 of the non-georeferenced CDC model which was the source of this model.
END DESCRIPTION:
XS GIS Cut Line= 3
2486524.275999436967467.967706962485581.777228276967229.20867005
2484640.08422977 6966999.3538148
#Sta/Elev= 30
    1000     426 1010.89  425.16  1092.9  401.17  1107.9     399 1150.16     397
 1333.92     396 1546.73     398 1691.27  401.82 1835.14     403 1843.32     402
 1853.07  396.01  1870.5  392.13 1889.64  392.17 1901.31     388 1920.37  376.12
  1968.1  372.05 1971.25     370 1982.26  370.76 1997.59     375 2005.39     382
  2027.2  391.96 2037.53  398.79 2062.46  400.64 2149.59   401.3 2674.44     400
 2809.19  398.26 2832.16  399.76 2844.29     402 2931.32     429 2941.61  428.37
#Mann= 3 ,0,0
    1000    .055       0 1835.14    .035       0 2037.53    .055       0
Levee=-1,1000,428.65,-1,2931,428.65,Levee 1,Levee 2
#XS Ineff= 2 , 0
       0 1835.14     403 2037.53       0  398.79
Permanent Ineff=
       F       F
Bank Sta=1835.14,2037.53
XS Rating Curve= 0 ,0
Exp/Cntr=0.3,0.1

Type RM Length L Ch R = 1 ,118516  ,136,150,196
BEGIN DESCRIPTION:
This cross section corresponds to cross section 118533 of the non-georeferenced CDC model which was the source of this model.
END DESCRIPTION:
XS GIS Cut Line= 2
2486542.889479256967380.72378697 2484660.11076456966912.27656113
#Sta/Elev= 30
       0     429    8.37  428.61   52.96     412   96.99     400  155.78     397
  333.45     396  651.98  401.42  790.28     403  834.24     402  842.91     395
  845.99  394.07  907.74     387  918.92     384  919.54   383.1  919.74     381
  920.74     380  931.08     372  932.79  373.77  959.61   369.1  979.62  369.75
  982.94     371  991.83     375  995.11     381 1013.87     393 1030.88     401
 1688.51     400 1812.74     398 1847.73     402  1924.7     429 1940.18  429.54
#Mann= 3 ,0,0
       0    .055       0  834.24    .035       0 1030.88    .055       0
Levee=-1,0,428.63,-1,1936,428.63,Levee 1,Levee 2
#XS Ineff= 2 , 0
       0  834.24     402 1030.88       0     401
Permanent Ineff=
       F       F
Bank Sta=834.24,1030.88
XS Rating Curve= 0 ,0
Exp/Cntr=0.3,0.1

Type RM Length L Ch R = 1 ,118366  ,64,86,116
BEGIN DESCRIPTION:
This cross section corresponds to cross section 118381 of the non-georeferenced CDC model which was the source of this model.
END DESCRIPTION:
XS GIS Cut Line= 2
2486580.577067916967318.21406947 2484735.38259566966695.15297963
#Sta/Elev= 30
       0     429   30.83     421   54.73  411.72   92.64     401  138.64     398
  504.62     397  555.07     400  637.14     401  798.45  402.68  844.47  401.01
  848.04     397  857.72     392  881.19  392.73  903.53     384  907.09  380.73
  943.24     371  974.22     371  993.91     378 1000.45  377.77 1010.02  386.98
  1011.8     392 1020.85     396 1027.41     402  1682.2     400 1784.33  397.04
 1827.01     398 1873.69  407.99 1900.52  416.55 1929.91     430 1947.55     430
#Mann= 3 ,0,0
       0    .055       0  844.47    .035       0 1027.41    .055       0
Levee=-1,0,428.6,-1,1929,428.6,Levee 1,Levee 2
#XS Ineff= 2 , 0
       0  844.47  401.01 1027.41       0     402
Permanent Ineff=
       F       F
Bank Sta=844.47,1027.41
XS Rating Curve= 0 ,0
Exp/Cntr=0.3,0.1