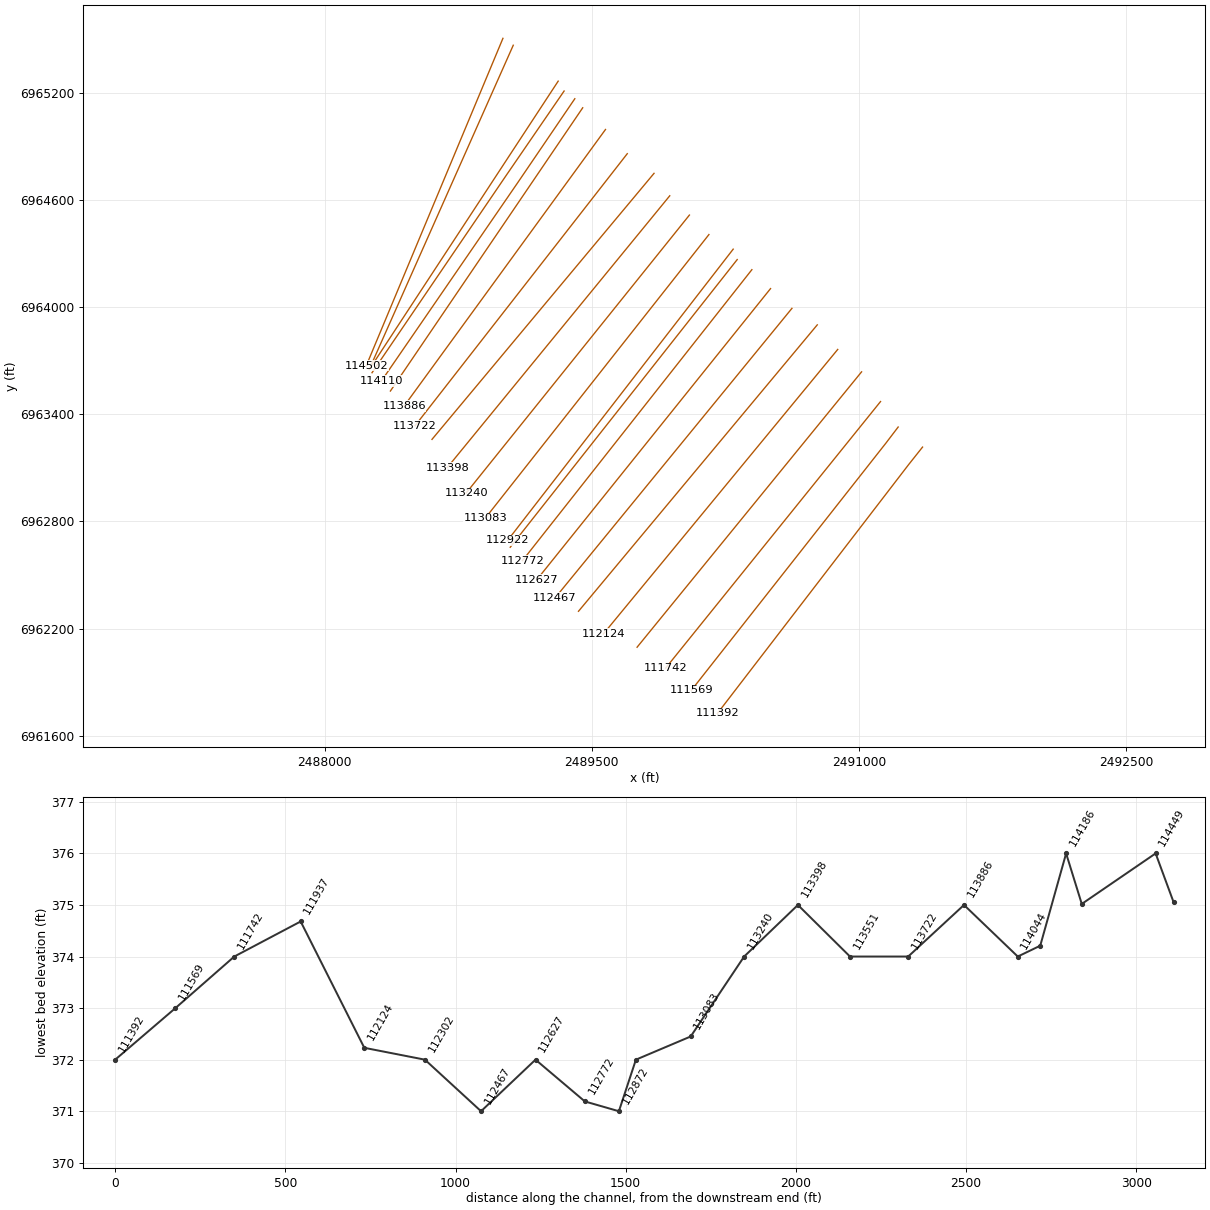
HEC-RAS study CDC_Consolidated_Model.prj: Upper Trinity CDC Consolidated Model

--- CDC_Consolidated_Model.g01 (geometry) --- (continued)

Type RM Length L Ch R = 3 ,114533  ,,,
BEGIN DESCRIPTION:
114541  IH 35E South Bound
END DESCRIPTION:
Node Name=IH 35E SB
Bridge Culvert--1,0,-1,-1, 0
Deck Dist Width WeirC Skew NumUp NumDn MinLoCord MaxHiCord MaxSubmerge Is_Ogee
2,58,2.6,0, 11, 11, , , 0.95, 0, ,,,
      32     188     604     634     674     734     794     834     864    1834
    2034
     430   431.3   433.8   433.8   433.8   433.8   433.8   433.7   433.5   431.8
   430.3
   424.7     426   428.5   428.2     425   426.8     425   428.3     428   426.5
     425
      32     188     604     634     674     734     794     834     864    1834
    2034
     430   431.3   433.8   433.8   433.8   433.8   433.8   433.7   433.5   431.8
   430.3
   424.7     426   428.5   428.2     425   426.8     425   428.3     428   426.5
     425
Pier Skew, UpSta & Num, DnSta & Num=  ,84, 2 ,84, 2 , 0 , 0 , 0 ,,
     2.5     2.5
     370     430
     2.5     2.5
     370     430
Pier Skew, UpSta & Num, DnSta & Num=  ,136, 2 ,136, 2 , 0 , 0 , 0 ,,
     2.5     2.5
     370     430
     2.5     2.5
     370     430
Pier Skew, UpSta & Num, DnSta & Num=  ,188, 2 ,188, 2 , 0 , 0 , 0 ,,
     2.5     2.5
     370     430
     2.5     2.5
     370     430
Pier Skew, UpSta & Num, DnSta & Num=  ,240, 2 ,240, 2 , 0 , 0 , 0 ,,
     2.5     2.5
     370     430
     2.5     2.5
     370     430
Pier Skew, UpSta & Num, DnSta & Num=  ,292, 2 ,292, 2 , 0 , 0 , 0 ,,
     2.5     2.5
     370     430
     2.5     2.5
     370     430
Pier Skew, UpSta & Num, DnSta & Num=  ,344, 2 ,344, 2 , 0 , 0 , 0 ,,
     2.5     2.5
     370     430
     2.5     2.5
     370     430
Pier Skew, UpSta & Num, DnSta & Num=  ,396, 2 ,396, 2 , 0 , 0 , 0 ,,
     2.5     2.5
     370     430
     2.5     2.5
     370     430
Pier Skew, UpSta & Num, DnSta & Num=  ,448, 2 ,448, 2 , 0 , 0 , 0 ,,
     2.5     2.5
     370     430
     2.5     2.5
     370     430
Pier Skew, UpSta & Num, DnSta & Num=  ,500, 2 ,500, 2 , 0 , 0 , 0 ,,
     2.5     2.5
     370     430
     2.5     2.5
     370     430
Pier Skew, UpSta & Num, DnSta & Num=  ,552, 2 ,552, 2 , 0 , 0 , 0 ,,
     2.5     2.5
     370     430
     2.5     2.5
     370     430
Pier Skew, UpSta & Num, DnSta & Num=  ,604, 4 ,604, 4 , 0 , 0 , 0 ,,
      20      20     2.5     2.5
     370     399     399     430
      20      20     2.5     2.5
     370     399     399     430
Pier Skew, UpSta & Num, DnSta & Num=  ,674, 4 ,674, 4 , 0 , 0 , 0 ,,
       4       4       3       3
     370     398     398     430
       4       4       3       3
     370     398     398     430
Pier Skew, UpSta & Num, DnSta & Num=  ,794, 4 ,794, 4 , 0 , 0 , 0 ,,
       4       4       3       3
     370     398     398     430
       4       4       3       3
     370     398     398     430
Pier Skew, UpSta & Num, DnSta & Num=  ,864, 2 ,864, 2 , 0 , 0 , 0 ,,
     2.5     2.5
     370     430
     2.5     2.5
     370     430
Pier Skew, UpSta & Num, DnSta & Num=  ,916, 2 ,916, 2 , 0 , 0 , 0 ,,
     2.5     2.5
     370     430
     2.5     2.5
     370     430
Pier Skew, UpSta & Num, DnSta & Num=  ,968, 2 ,968, 2 , 0 , 0 , 0 ,,
     2.5     2.5
     370     430
     2.5     2.5
     370     430
Pier Skew, UpSta & Num, DnSta & Num=  ,1020, 2 ,1020, 2 , 0 , 0 , 0 ,,
     2.5     2.5
     370     430
     2.5     2.5
     370     430
Pier Skew, UpSta & Num, DnSta & Num=  ,1072, 2 ,1072, 2 , 0 , 0 , 0 ,,
     2.5     2.5
     370     430
     2.5     2.5
     370     430
Pier Skew, UpSta & Num, DnSta & Num=  ,1124, 2 ,1124, 2 , 0 , 0 , 0 ,,
     2.5     2.5
     370     430
     2.5     2.5
     370     430
Pier Skew, UpSta & Num, DnSta & Num=  ,1176, 2 ,1176, 2 , 0 , 0 , 0 ,,
     2.5     2.5
     370     430
     2.5     2.5
     370     430
Pier Skew, UpSta & Num, DnSta & Num=  ,1228, 2 ,1228, 2 , 0 , 0 , 0 ,,
     2.5     2.5
     370     430
     2.5     2.5
     370     430
Pier Skew, UpSta & Num, DnSta & Num=  ,1280, 2 ,1280, 2 , 0 , 0 , 0 ,,
     2.5     2.5
     370     430
     2.5     2.5
     370     430
Pier Skew, UpSta & Num, DnSta & Num=  ,1332, 2 ,1332, 2 , 0 , 0 , 0 ,,
     2.5     2.5
     370     430
     2.5     2.5
     370     430
Pier Skew, UpSta & Num, DnSta & Num=  ,1384, 2 ,1384, 2 , 0 , 0 , 0 ,,
     2.5     2.5
     370     430
     2.5     2.5
     370     430
Pier Skew, UpSta & Num, DnSta & Num=  ,1436, 2 ,1436, 2 , 0 , 0 , 0 ,,
     2.5     2.5
     370     430
     2.5     2.5
     370     430
Pier Skew, UpSta & Num, DnSta & Num=  ,1488, 2 ,1488, 2 , 0 , 0 , 0 ,,
     2.5     2.5
     370     430
     2.5     2.5
     370     430
Pier Skew, UpSta & Num, DnSta & Num=  ,1540, 2 ,1540, 2 , 0 , 0 , 0 ,,
     2.5     2.5
     370     430
     2.5     2.5
     370     430
Pier Skew, UpSta & Num, DnSta & Num=  ,1592, 2 ,1592, 2 , 0 , 0 , 0 ,,
     2.5     2.5
     370     430
     2.5     2.5
     370     430
Pier Skew, UpSta & Num, DnSta & Num=  ,1644, 2 ,1644, 2 , 0 , 0 , 0 ,,
     2.5     2.5
     370     430
     2.5     2.5
     370     430
Pier Skew, UpSta & Num, DnSta & Num=  ,1696, 2 ,1696, 2 , 0 , 0 , 0 ,,
     2.5     2.5
     370     430
     2.5     2.5
     370     430
Pier Skew, UpSta & Num, DnSta & Num=  ,1748, 2 ,1748, 2 , 0 , 0 , 0 ,,
     2.5     2.5
     370     430
     2.5     2.5
     370     430
Pier Skew, UpSta & Num, DnSta & Num=  ,1800, 2 ,1800, 2 , 0 , 0 , 0 ,,
     2.5     2.5
     370     430
     2.5     2.5
     370     430
Pier Skew, UpSta & Num, DnSta & Num=  ,1852, 2 ,1852, 2 , 0 , 0 , 0 ,,
     2.5     2.5
     370     430
     2.5     2.5
     370     430
Pier Skew, UpSta & Num, DnSta & Num=  ,1904, 2 ,1904, 2 , 0 , 0 , 0 ,,
     2.5     2.5
     370     430
     2.5     2.5
     370     430
Pier Skew, UpSta & Num, DnSta & Num=  ,1956, 2 ,1956, 2 , 0 , 0 , 0 ,,
     2.5     2.5
     370     430
     2.5     2.5
     370     430
BR Coef= 1 , 1 , 1 ,1.05, 0 ,,,0.8,-1,1.2,1,
WSPro=,,,, 1 ,,,, 0 ,,,, 0 ,,,,-1 ,-1 ,-1 , 0 , 0 , 0 , 0 , 0
BC Design=,, 0 ,, 0 ,,,,,,
BC HTab HWMax=427
BC Use User HTab Curves=0
BC User HTab FreeFlow(D)= 0

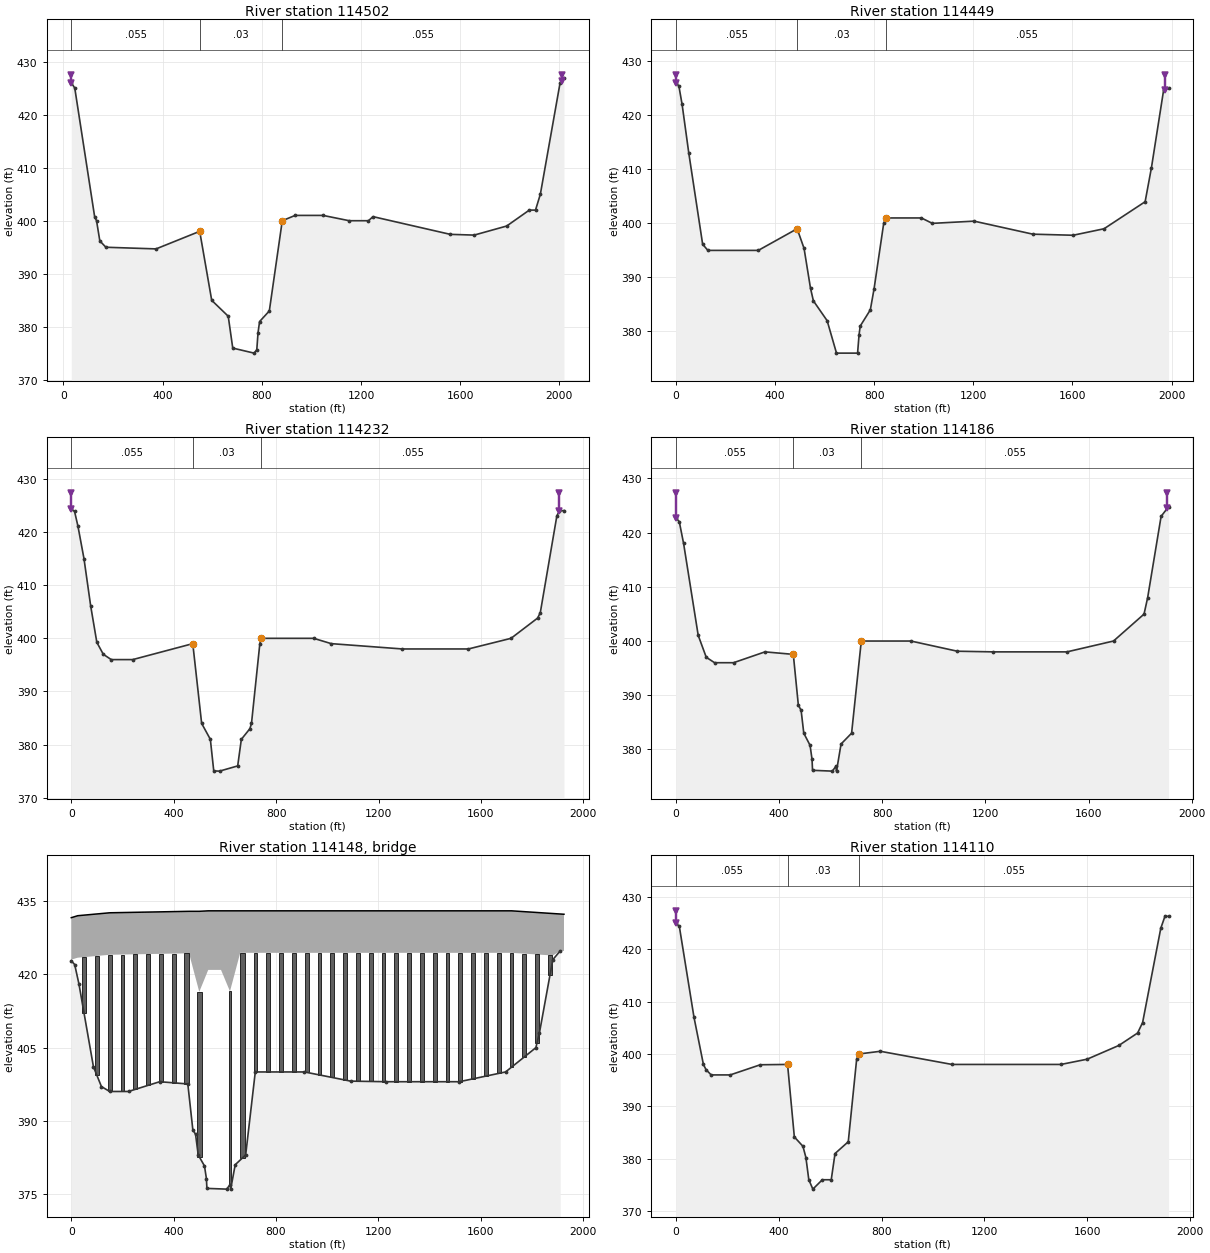
Type RM Length L Ch R = 1 ,114502  ,53,53,45
BEGIN DESCRIPTION:
This cross section corresponds to cross section 114510 of the non-georeferenced CDC model which was the source of this model.
END DESCRIPTION:
XS GIS Cut Line= 2
 2489001.16507456965504.510019722488234.023892256963672.24465539
#Sta/Elev= 30
      32     426   45.96     425  126.22  400.72  133.77     400     147   396.2
  171.46     395  373.73  394.69  549.72     398   598.1     385  664.72     382
  682.92     376  769.05  375.05  779.89   375.7  784.94  378.93  791.17     381
  830.39     383  882.59     400  934.49     401  1046.9     401 1152.42     400
 1230.11     400 1248.32  400.77 1559.98  397.43 1656.25  397.29 1787.45     399
 1878.55     402 1903.58     402 1923.16     405 2002.75     426 2018.38  426.94
#Mann= 3 ,0,0
      32    .055       0  549.72     .03       0  882.59    .055       0
Levee=-1,32,427.49,-1,2009,427.49,Levee 1,Levee 2
#XS Ineff= 2 , 0
       0  549.72     398  882.59       0     400
Permanent Ineff=
       F       F
Bank Sta=549.72,882.59
XS Rating Curve= 0 ,0
Exp/Cntr=0.3,0.1

Type RM Length L Ch R = 1 ,114449  ,253,217,132
BEGIN DESCRIPTION:
This cross section corresponds to cross section 114457 of the non-georeferenced CDC model which was the source of this model.
END DESCRIPTION:
XS GIS Cut Line= 2
2489059.135430996965465.897892222488250.031406166963650.35920046
#Sta/Elev= 30
       0     426      12  425.42   25.12     422   52.06     413  107.97  396.14
  129.04     395  332.49     395  489.22     399  517.13  395.37  543.11     388
   554.8  385.67  610.25     382  647.98     376  733.05     376  738.98  379.37
  743.63     381  784.46     384   799.7  387.93  838.42     400  846.98     401
  990.49     401 1034.59     400 1203.09  400.41 1440.16     398 1602.51   397.8
 1727.29     399 1893.12     404 1918.59  410.29 1967.62  424.61 1987.67  425.02
#Mann= 3 ,0,0
       0    .055       0  489.22     .03       0  846.98    .055       0
Levee=-1,0,427.47,-1,1972,427.47,Levee 1,Levee 2
#XS Ineff= 2 , 0
       0  489.22     399  846.98       0     401
Permanent Ineff=
       F       F
Bank Sta=489.22,846.98
XS Rating Curve= 0 ,0
Exp/Cntr=0.3,0.1

Type RM Length L Ch R = 1 ,114232  ,46,46,46
BEGIN DESCRIPTION:
This cross section corresponds to cross section 114243 of the non-georeferenced CDC model which was the source of this model.
END DESCRIPTION:
XS GIS Cut Line= 2
2489311.322590686965264.811024052488254.654756526963656.61115646
#Sta/Elev= 30
       0  424.27   12.68  423.88   26.02  421.08   49.48     415    75.7  406.09
    99.7  399.25  124.94     397  155.97     396  239.94     396  474.46     399
  509.09     384  543.09     381  556.39  375.06  579.06  375.02  649.86     376
  664.14     381  697.52     383   703.8     384  736.39     399  741.97     400
  946.74     400 1015.36     399 1293.26     398 1550.97     398 1717.43     400
 1821.07   403.8 1831.75  404.82 1896.35     423 1905.91  423.97 1924.28  424.03
#Mann= 3 ,0,0
       0    .055       0  474.46     .03       0  741.97    .055       0
Levee=-1,0,427.37,-1,1906,427.37,Levee 1,Levee 2
#XS Ineff= 2 , 0
       0  474.46     399  741.97       0     400
Permanent Ineff=
       F       F
Bank Sta=474.46,741.97
XS Rating Curve= 0 ,0
Exp/Cntr=0.3,0.1

Type RM Length L Ch R = 1 ,114186  ,76,76,76
BEGIN DESCRIPTION:
This cross section corresponds to cross section 114183 of the non-georeferenced CDC model which was the source of this model.
END DESCRIPTION:
XS GIS Cut Line= 3
2489344.551526846965209.516515212489018.155854176964735.25138763
2488266.25676742 6963632.7818078
#Sta/Elev= 30
       0  422.76   13.22     422   29.92     418   86.53  401.05  117.78     397
   150.1     396  223.49     396  345.43     398  455.26  397.54  474.78  388.19
  485.56  387.21   495.9     383  520.33  380.75  527.88  378.17  529.83  376.15
  606.78     376  620.73  376.92  622.76     376  640.43     381  681.29     383
  718.87     400  911.11     400 1091.26  398.12 1230.37     398 1516.21     398
 1696.75     400 1815.13  404.97 1829.09     408 1881.28     423 1910.19  424.78
#Mann= 3 ,0,0
       0    .055       0  455.26     .03       0  718.87    .055       0
Levee=-1,0,427.34,-1,1906,427.34,Levee 1,Levee 2
#XS Ineff= 2 , 0
       0  455.26  397.54  718.87       0     400
Permanent Ineff=
       F       F
Bank Sta=455.26,718.87
XS Rating Curve= 0 ,0
Exp/Cntr=0.3,0.1

Type RM Length L Ch R = 3 ,114148  ,,,
BEGIN DESCRIPTION:
114149.5  IH 35E North Bound/Cadiz Street
END DESCRIPTION:
Node Name=IH 35E NB
Bridge Culvert--1,0,-1,-1, 0
Deck Dist Width WeirC Skew NumUp NumDn MinLoCord MaxHiCord MaxSubmerge Is_Ogee
1,74,2.6,0, 11, 11, , , 0.95, 0, ,,,
       0      25     150     460     500     535     585     620     660    1720
    1925
   431.6     432   432.6   432.9   432.9     433     433     433     433     433
   432.3
     423   423.4     424   424.3   416.4   420.9   420.9   416.5   424.4   424.4
   423.7
       0      25     150     460     500     535     585     620     660    1720
    1925
   431.6     432   432.6   432.9   432.9     433     433     433     433     433
   432.3
     423   423.4     424   424.3   416.4   420.9   420.9   416.5   424.4   424.4
   423.7
Pier Skew, UpSta & Num, DnSta & Num=  ,50, 6 ,50, 6 , 4 , 4 , 0 ,,
     4.5     2.5     2.5       4       4      15
     394     418   420.5   420.5     422   423.8
     4.5     2.5     2.5       4       4      15
     394     418   420.5   420.5     422   423.8
Pier Skew, UpSta & Num, DnSta & Num=  ,100, 6 ,100, 6 , 4 , 4 , 0 ,,
     4.5     2.5     2.5       4       4      15
     394   418.2   420.8   420.8   422.2     424
     4.5     2.5     2.5       4       4      15
     394   418.2   420.8   420.8   422.2     424
Pier Skew, UpSta & Num, DnSta & Num=  ,150, 6 ,150, 6 , 4 , 4 , 0 ,,
     4.5     2.5     2.5       4       4      15
     394   418.5     421     421   422.5   424.3
     4.5     2.5     2.5       4       4      15
     394   418.5     421     421   422.5   424.3
Pier Skew, UpSta & Num, DnSta & Num=  ,200, 6 ,200, 6 , 4 , 4 , 0 ,,
     4.5     2.5     2.5       4       4      15
     394   418.5     421     421   422.5   424.3
     4.5     2.5     2.5       4       4      15
     394   418.5     421     421   422.5   424.3
Pier Skew, UpSta & Num, DnSta & Num=  ,250, 6 ,250, 6 , 4 , 4 , 0 ,,
     4.5     2.5     2.5       4       4      15
     394   418.5     421     421   422.5   424.3
     4.5     2.5     2.5       4       4      15
     394   418.5     421     421   422.5   424.3
Pier Skew, UpSta & Num, DnSta & Num=  ,300, 6 ,300, 6 , 4 , 4 , 0 ,,
     4.5     2.5     2.5       4       4      15
     394   418.5     421     421   422.5   424.3
     4.5     2.5     2.5       4       4      15
     394   418.5     421     421   422.5   424.3
Pier Skew, UpSta & Num, DnSta & Num=  ,350, 6 ,350, 6 , 4 , 4 , 0 ,,
     4.5     2.5     2.5       4       4      15
     394   418.5     421     421   422.5   424.3
     4.5     2.5     2.5       4       4      15
     394   418.5     421     421   422.5   424.3
Pier Skew, UpSta & Num, DnSta & Num=  ,400, 6 ,400, 6 , 4 , 4 , 0 ,,
     4.5     2.5     2.5       4       4      15
     394   418.5     421     421   422.5   424.3
     4.5     2.5     2.5       4       4      15
     394   418.5     421     421   422.5   424.3
Pier Skew, UpSta & Num, DnSta & Num=  ,450, 8 ,450, 8 , 6 , 6 , 0 ,,
    18.5    18.5     4.5     2.5     2.5       4       4      15
     370     399     399   418.5     421     421   422.5   424.3
    18.5    18.5     4.5     2.5     2.5       4       4      15
     370     399     399   418.5     421     421   422.5   424.3
Pier Skew, UpSta & Num, DnSta & Num=  ,500, 6 ,500, 6 , 5 , 5 , 0 ,,
      20      20       8       3       5       5
     370     385     385   413.5   413.5     417
      20      20       8       3       5       5
     370     385     385   413.5   413.5     417
Pier Skew, UpSta & Num, DnSta & Num=  ,620, 4 ,620, 4 , 3 , 3 , 0 ,,
       8       3       5       5
   383.5   413.5   413.5     417
       8       3       5       5
   383.5   413.5   413.5     417
Pier Skew, UpSta & Num, DnSta & Num=  ,670, 8 ,670, 8 , 6 , 6 , 0 ,,
    18.5    18.5     4.5     2.5     2.5       4       4      15
     370     399     399     419   421.5   421.5     423   424.5
    18.5    18.5     4.5     2.5     2.5       4       4      15
     370     399     399     419   421.5   421.5     423   424.5
Pier Skew, UpSta & Num, DnSta & Num=  ,720, 6 ,720, 6 , 4 , 4 , 0 ,,
     4.5     2.5     2.5       4       4      15
     394     419   421.5   421.5     423   424.5
     4.5     2.5     2.5       4       4      15
     394     419   421.5   421.5     423   424.5
Pier Skew, UpSta & Num, DnSta & Num=  ,770, 6 ,770, 6 , 4 , 4 , 0 ,,
     4.5     2.5     2.5       4       4      15
     394     419   421.5   421.5     423   424.5
     4.5     2.5     2.5       4       4      15
     394     419   421.5   421.5     423   424.5
Pier Skew, UpSta & Num, DnSta & Num=  ,820, 6 ,820, 6 , 4 , 4 , 0 ,,
     4.5     2.5     2.5       4       4      15
     394     419   421.5   421.5     423   424.5
     4.5     2.5     2.5       4       4      15
     394     419   421.5   421.5     423   424.5
Pier Skew, UpSta & Num, DnSta & Num=  ,870, 6 ,870, 6 , 4 , 4 , 0 ,,
     4.5     2.5     2.5       4       4      15
     394     419   421.5   421.5     423   424.5
     4.5     2.5     2.5       4       4      15
     394     419   421.5   421.5     423   424.5
Pier Skew, UpSta & Num, DnSta & Num=  ,920, 6 ,920, 6 , 4 , 4 , 0 ,,
     4.5     2.5     2.5       4       4      15
     394     419   421.5   421.5     423   424.5
     4.5     2.5     2.5       4       4      15
     394     419   421.5   421.5     423   424.5
Pier Skew, UpSta & Num, DnSta & Num=  ,970, 6 ,970, 6 , 4 , 4 , 0 ,,
     4.5     2.5     2.5       4       4      15
     394     419   421.5   421.5     423   424.5
     4.5     2.5     2.5       4       4      15
     394     419   421.5   421.5     423   424.5
Pier Skew, UpSta & Num, DnSta & Num=  ,1020, 6 ,1020, 6 , 4 , 4 , 0 ,,
     4.5     2.5     2.5       4       4      15
     394     419   421.5   421.5     423   424.5
     4.5     2.5     2.5       4       4      15
     394     419   421.5   421.5     423   424.5
Pier Skew, UpSta & Num, DnSta & Num=  ,1070, 6 ,1070, 6 , 4 , 4 , 0 ,,
     4.5     2.5     2.5       4       4      15
     394     419   421.5   421.5     423   424.5
     4.5     2.5     2.5       4       4      15
     394     419   421.5   421.5     423   424.5
Pier Skew, UpSta & Num, DnSta & Num=  ,1120, 6 ,1120, 6 , 4 , 4 , 0 ,,
     4.5     2.5     2.5       4       4      15
     394     419   421.5   421.5     423   424.5
     4.5     2.5     2.5       4       4      15
     394     419   421.5   421.5     423   424.5
Pier Skew, UpSta & Num, DnSta & Num=  ,1170, 6 ,1170, 6 , 4 , 4 , 0 ,,
     4.5     2.5     2.5       4       4      15
     394     419   421.5   421.5     423   424.5
     4.5     2.5     2.5       4       4      15
     394     419   421.5   421.5     423   424.5
Pier Skew, UpSta & Num, DnSta & Num=  ,1220, 6 ,1220, 6 , 4 , 4 , 0 ,,
     4.5     2.5     2.5       4       4      15
     394     419   421.5   421.5     423   424.5
     4.5     2.5     2.5       4       4      15
     394     419   421.5   421.5     423   424.5
Pier Skew, UpSta & Num, DnSta & Num=  ,1270, 6 ,1270, 6 , 4 , 4 , 0 ,,
     4.5     2.5     2.5       4       4      15
     394     419   421.5   421.5     423   424.5
     4.5     2.5     2.5       4       4      15
     394     419   421.5   421.5     423   424.5
Pier Skew, UpSta & Num, DnSta & Num=  ,1320, 6 ,1320, 6 , 4 , 4 , 0 ,,
     4.5     2.5     2.5       4       4      15
     394     419   421.5   421.5     423   424.5
     4.5     2.5     2.5       4       4      15
     394     419   421.5   421.5     423   424.5
Pier Skew, UpSta & Num, DnSta & Num=  ,1370, 6 ,1370, 6 , 4 , 4 , 0 ,,
     4.5     2.5     2.5       4       4      15
     394     419   421.5   421.5     423   424.5
     4.5     2.5     2.5       4       4      15
     394     419   421.5   421.5     423   424.5
Pier Skew, UpSta & Num, DnSta & Num=  ,1420, 6 ,1420, 6 , 4 , 4 , 0 ,,
     4.5     2.5     2.5       4       4      15
     394     419   421.5   421.5     423   424.5
     4.5     2.5     2.5       4       4      15
     394     419   421.5   421.5     423   424.5
Pier Skew, UpSta & Num, DnSta & Num=  ,1470, 6 ,1470, 6 , 4 , 4 , 0 ,,
     4.5     2.5     2.5       4       4      15
     394     419   421.5   421.5     423   424.5
     4.5     2.5     2.5       4       4      15
     394     419   421.5   421.5     423   424.5
Pier Skew, UpSta & Num, DnSta & Num=  ,1520, 6 ,1520, 6 , 4 , 4 , 0 ,,
     4.5     2.5     2.5       4       4      15
     394     419   421.5   421.5     423   424.5
     4.5     2.5     2.5       4       4      15
     394     419   421.5   421.5     423   424.5
Pier Skew, UpSta & Num, DnSta & Num=  ,1570, 6 ,1570, 6 , 4 , 4 , 0 ,,
     4.5     2.5     2.5       4       4      15
     394     419   421.5   421.5     423   424.5
     4.5     2.5     2.5       4       4      15
     394     419   421.5   421.5     423   424.5
Pier Skew, UpSta & Num, DnSta & Num=  ,1620, 6 ,1620, 6 , 4 , 4 , 0 ,,
     4.5     2.5     2.5       4       4      15
     394     419   421.5   421.5     423   424.5
     4.5     2.5     2.5       4       4      15
     394     419   421.5   421.5     423   424.5
Pier Skew, UpSta & Num, DnSta & Num=  ,1670, 6 ,1670, 6 , 4 , 4 , 0 ,,
     4.5     2.5     2.5       4       4      15
     394     419   421.5   421.5     423   424.5
     4.5     2.5     2.5       4       4      15
     394     419   421.5   421.5     423   424.5
Pier Skew, UpSta & Num, DnSta & Num=  ,1720, 6 ,1720, 6 , 4 , 4 , 0 ,,
     4.5     2.5     2.5       4       4      15
     394     419   421.5   421.5     423   424.5
     4.5     2.5     2.5       4       4      15
     394     419   421.5   421.5     423   424.5
Pier Skew, UpSta & Num, DnSta & Num=  ,1770, 6 ,1770, 6 , 4 , 4 , 0 ,,
     4.5     2.5     2.5       4       4      15
     394   418.8   421.3   421.3   422.8   424.5
     4.5     2.5     2.5       4       4      15
     394   418.8   421.3   421.3   422.8   424.5
Pier Skew, UpSta & Num, DnSta & Num=  ,1820, 6 ,1820, 6 , 4 , 4 , 0 ,,
     4.5     2.5     2.5       4       4      15
     394   418.6   421.1   421.1   422.6   424.3
     4.5     2.5     2.5       4       4      15
     394   418.6   421.1   421.1   422.6   424.3
Pier Skew, UpSta & Num, DnSta & Num=  ,1870, 6 ,1870, 6 , 4 , 4 , 0 ,,
     4.5     2.5     2.5       4       4      15
     394   418.5     421     421   422.5   424.2
     4.5     2.5     2.5       4       4      15
     394   418.5     421     421   422.5   424.2
BR Coef= 1 , 1 , 1 ,1.05, 0 ,,,0.8,0,1.2,1,
WSPro=,,,, 1 ,,,, 0 ,,,, 0 ,,,,-1 ,-1 ,-1 , 0 , 0 , 0 , 0 , 0
BC Design=,, 0 ,, 0 ,,,,,,
BC HTab HWMax=426
BC Use User HTab Curves=0
BC User HTab FreeFlow(D)= 0

Type RM Length L Ch R = 1 ,114110  ,66,66,66
BEGIN DESCRIPTION:
This cross section corresponds to cross section 114116 of the non-georeferenced CDC model which was the source of this model.
END DESCRIPTION:
XS GIS Cut Line= 3
2489404.716760846965166.469357222489083.904082276964696.21340796
2488319.08638617 6963586.6657583
#Sta/Elev= 30
       0     425   13.46  424.33   70.45     407  107.14     398   117.4     397
   137.3     396  211.32     396   328.5  397.94  434.51     398   460.9  384.17
  494.39  382.38  505.88  380.24  517.17     376  532.99  374.21  569.78     376
  604.46     376  619.16     381  670.71  383.25  703.32     399  712.62     400
  795.43  400.51 1074.39     398 1498.36     398 1600.05     399 1723.33  401.62
 1796.52     404 1815.93     406  1886.7     424 1902.99  426.29 1916.87  426.25
#Mann= 3 ,0,0
       0    .055       0  434.51     .03       0  712.62    .055       0
Levee=-1,0,427.31,-1,1917,427.31,Levee 1,Levee 2
#XS Ineff= 2 , 0
       0  434.51     398  712.62       0     400
Permanent Ineff=
       F       F
Bank Sta=434.51,712.62
XS Rating Curve= 0 ,0
Exp/Cntr=0.3,0.1

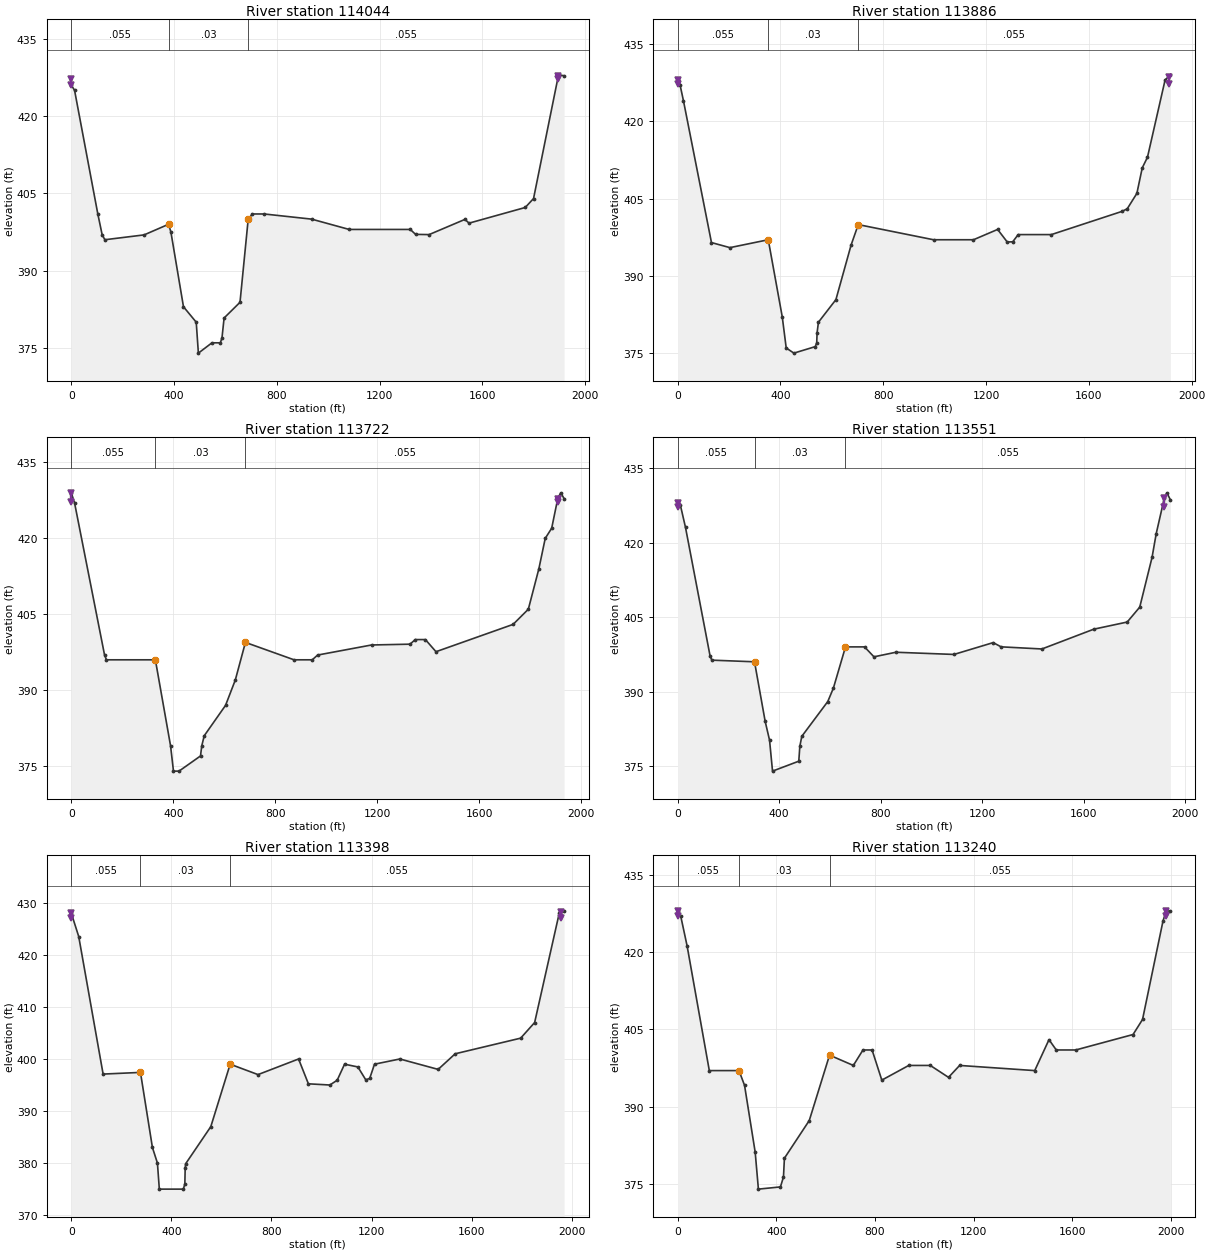
Type RM Length L Ch R = 1 ,114044  ,164,158,144
BEGIN DESCRIPTION:
This cross section corresponds to cross section 114054 of the non-georeferenced CDC model which was the source of this model.
END DESCRIPTION:
XS GIS Cut Line= 2
 2489449.06969056965115.777201382488369.448162086963530.28266896
#Sta/Elev= 30
       0     426   12.67     425   103.2     401  119.97     397  130.52     396
  283.34  396.94  378.51     399  387.64  397.51  436.62     383  486.26     380
  494.64     374  547.42     376   580.3     376  586.61     377  594.77  380.82
  656.67  383.86  688.59     400  705.01     401  750.86     401  935.42     400
 1081.46     398 1319.42     398  1340.2  397.04 1392.82     397 1532.23  399.95
 1548.25  399.22 1766.93  402.26 1799.31     404 1896.56     428 1918.17  427.82
#Mann= 3 ,0,0
       0    .055       0  378.51     .03       0  688.59    .055       0
Levee=-1,0,427.28,-1,1896,427.28,Levee 1,Levee 2
#XS Ineff= 2 , 0
       0  378.51     399  688.59       0     400
Permanent Ineff=
       F       F
Bank Sta=378.51,688.59
XS Rating Curve= 0 ,0
Exp/Cntr=0.3,0.1

Type RM Length L Ch R = 1 ,113886  ,170,164,150
BEGIN DESCRIPTION:
This cross section corresponds to cross section 113890 of the non-georeferenced CDC model which was the source of this model.
---------------------------------------------------------------------
Approx. location of CDC DAL052209-1, Dallas Water Utilities East Bank - West Bank Interceptor Connector.
This CDC was for temporary floodway encroachnment of an outlet shaft riser in the right overbank. Because of the temporary nature of this encroachment, no permanent modification.
------------------------
END DESCRIPTION:
XS GIS Cut Line= 2
2489576.951652596964994.299754052488446.323992586963446.08992396
#Sta/Elev= 30
       0     428    9.53  427.02   22.54     424  131.64  396.45  203.44  395.47
   352.6     397  407.17     382  422.42     376  452.23     375  535.44  376.26
  541.11     377  542.55  378.96   547.8     381  615.76  385.38  675.03     396
   702.7  399.94  995.52     397    1151     397 1244.84     399 1282.24  396.57
 1303.67   396.6 1324.82     398 1453.95     398  1728.1  402.49 1749.02     403
 1786.64     406 1807.54  410.95 1827.81     413 1896.38     428  1917.1     429
#Mann= 3 ,0,0
       0    .055       0   352.6     .03       0   702.7    .055       0
Levee=-1,0,427.22,-1,1910,427.22,Levee 1,Levee 2
#XS Ineff= 2 , 0
       0   352.6     397   702.7       0  399.94
Permanent Ineff=
       F       F
Bank Sta=352.6,702.7
XS Rating Curve= 0 ,0
Exp/Cntr=0.3,0.1

Type RM Length L Ch R = 1 ,113722  ,179,171,158
BEGIN DESCRIPTION:
This cross section corresponds to cross section 113726 of the non-georeferenced CDC model which was the source of this model.
END DESCRIPTION:
XS GIS Cut Line= 2
2489699.221421186964858.81380455  2488508.1247226963336.41429029
#Sta/Elev= 30
       0     429   12.81     427  130.22     397  137.78     396  329.73     396
  389.36     379  400.76     374  422.52     374   506.8     377  511.71     379
  521.52     381  605.07     387  643.26     392     683  399.44  873.72     396
  945.18     396   966.2  396.94 1177.76  398.93 1328.73  399.09 1349.19     400
 1388.94     400 1430.46   397.6 1732.93     403 1792.73     406  1834.1     414
 1859.01     420  1884.3     422 1908.72     428 1920.18     429 1932.98  427.86
#Mann= 3 ,0,0
       0    .055       0  329.73     .03       0     683    .055       0
Levee=-1,0,427.16,-1,1908,427.16,Levee 1,Levee 2
#XS Ineff= 2 , 0
       0  329.73     396     683       0  399.44
Permanent Ineff=
       F       F
Bank Sta=329.73,683
XS Rating Curve= 0 ,0
Exp/Cntr=0.3,0.1

Type RM Length L Ch R = 1 ,113551  ,153,153,160
BEGIN DESCRIPTION:
This cross section corresponds to cross section 113563 of the non-georeferenced CDC model which was the source of this model.
END DESCRIPTION:
XS GIS Cut Line= 2
2489849.427485596964748.770389472488602.897826436963259.59521821
#Sta/Elev= 30
       0     428   10.75  427.55   31.04  423.03  127.68  397.23  134.76  396.33
  303.02     396  345.03     384  362.25  380.23  373.99     374  477.48     376
  481.63     379  489.32     381   591.7     388  613.78  390.69  661.55     399
  736.56     399  773.74     397  860.14  397.92 1088.96  397.48 1243.67  399.86
  1274.6  399.01 1435.61  398.58  1639.9  402.56 1771.76     404 1821.16     407
 1869.63     417 1886.12   421.8 1918.34     429 1928.06     430 1942.03  428.59
#Mann= 3 ,0,0
       0    .055       0  303.02     .03       0  661.55    .055       0
Levee=-1,0,427.1,-1,1918,427.1,Levee 1,Levee 2
#XS Ineff= 2 , 0
       0  303.02     396  661.55       0     399
Permanent Ineff=
       F       F
Bank Sta=303.02,661.55
XS Rating Curve= 0 ,0
Exp/Cntr=0.3,0.1

Type RM Length L Ch R = 1 ,113398  ,158,158,165
BEGIN DESCRIPTION:
This cross section corresponds to cross section 113405 of the non-georeferenced CDC model which was the source of this model.
END DESCRIPTION:
XS GIS Cut Line= 2
2489937.678293356964623.190588132488688.124690096963101.02270071
#Sta/Elev= 30
       0     428   29.66  423.52  127.12   397.1  276.37  397.42  324.16     383
   344.2     380  351.77     375  447.84     375  453.76     376  455.07     379
  457.04  379.88  557.45     387  634.86     399  746.16     397  908.25     400
  947.51  395.23 1033.35     395 1062.56  395.92 1092.04     399 1145.25  398.47
 1176.77     396 1192.47  396.26 1211.71     399 1313.06     400 1466.04     398
 1534.18     401 1795.73     404 1851.65     407 1949.97     428 1969.36  428.46
#Mann= 3 ,0,0
       0    .055       0  276.37     .03       0  634.86    .055       0
Levee=-1,0,427.04,-1,1957,427.04,Levee 1,Levee 2
#XS Ineff= 2 , 0
       0  276.37  397.42  634.86       0     399
Permanent Ineff=
       F       F
Bank Sta=276.37,634.86
XS Rating Curve= 0 ,0
Exp/Cntr=0.3,0.1

Type RM Length L Ch R = 1 ,113240  ,157,157,165
BEGIN DESCRIPTION:
This cross section corresponds to cross section 113247 of the non-georeferenced CDC model which was the source of this model.
END DESCRIPTION:
XS GIS Cut Line= 2
2490048.098020026964515.226237132488794.401052336962958.90782747
#Sta/Elev= 30
       0     428   12.46     427   38.31  421.22  128.48     397  248.81     397
  271.36  394.14  314.53  381.17  327.57     374  417.01  374.43  429.29  376.37
  433.07     380  533.83  387.31  616.05     400  712.57     398  751.65     401
  788.62     401  828.07  395.15  937.37     398 1024.64     398 1098.54  395.69
 1143.65     398 1448.19     397 1506.05     403 1535.56     401 1614.49     401
 1846.98     404 1885.41  406.92  1968.3     426 1981.44     428 1998.47     428
#Mann= 3 ,0,0
       0    .055       0  248.81     .03       0  616.05    .055       0
Levee=-1,0,426.99,-1,1981,426.99,Levee 1,Levee 2
#XS Ineff= 2 , 0
       0  248.81     397  616.05       0     400
Permanent Ineff=
       F       F
Bank Sta=248.81,616.05
XS Rating Curve= 0 ,0
Exp/Cntr=0.3,0.1

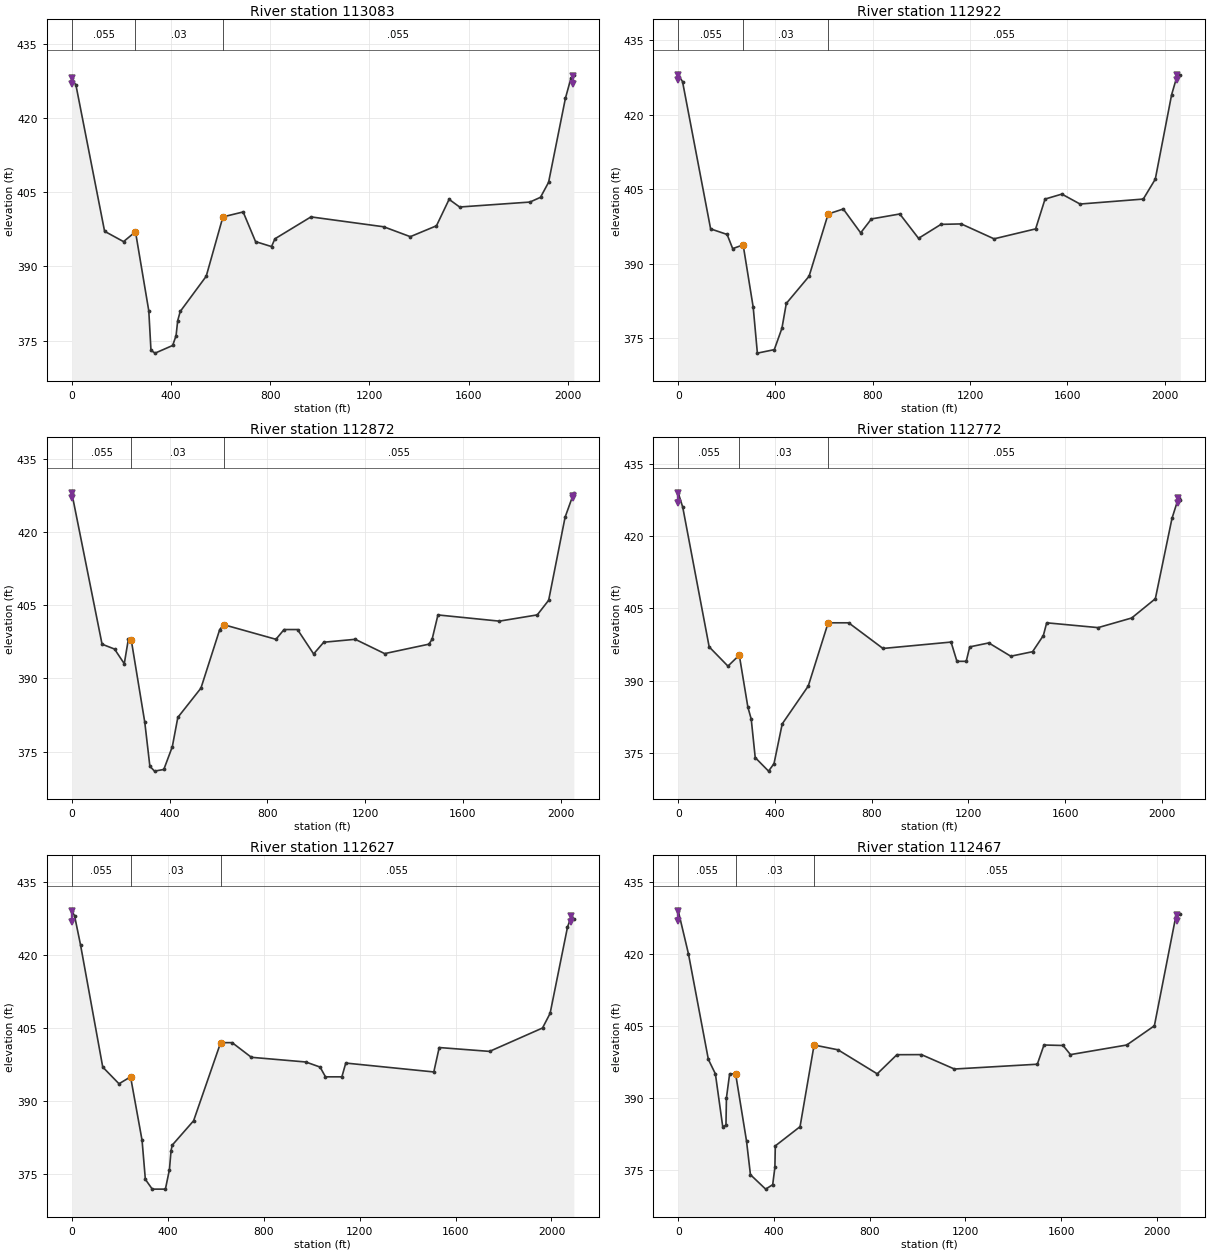
Type RM Length L Ch R = 1 ,113083  ,163,161,171
BEGIN DESCRIPTION:
This cross section corresponds to cross section 113089 of the non-georeferenced CDC model which was the source of this model.
END DESCRIPTION:
XS GIS Cut Line= 2
2490157.562368016964406.050274392488901.632465186962818.00489405
#Sta/Elev= 30
       0     428   16.95  426.62  132.37  397.09  208.78     395  256.92     397
   310.6     381  319.38  373.01  336.11  372.45  406.88     374  420.65     376
  427.11     379  437.31  380.87  542.19     388  609.52     400   691.1     401
  741.18     395  805.51     394  819.21  395.57  964.58     400 1258.04     398
 1365.13     396 1470.67   398.2 1521.62  403.55 1564.09     402 1847.49     403
 1890.19  403.96 1922.83     407 1990.72     424 2012.71     428 2024.66  428.73
#Mann= 3 ,0,0
       0    .055       0  256.92     .03       0  609.52    .055       0
Levee=-1,0,426.93,-1,2021,426.93,Levee 1,Levee 2
#XS Ineff= 2 , 0
       0  256.92     397  609.52       0     400
Permanent Ineff=
       F       F
Bank Sta=256.92,609.52
XS Rating Curve= 0 ,0
Exp/Cntr=0.3,0.1

Type RM Length L Ch R = 1 ,112922  ,51,50,47
BEGIN DESCRIPTION:
This cross section corresponds to cross section 112933 of the non-georeferenced CDC model which was the source of this model.
END DESCRIPTION:
XS GIS Cut Line= 2
2490293.858683356964324.458245962489027.251636516962693.69379097
#Sta/Elev= 30
       0     428   17.65  426.64  133.17     397  200.99  395.88  223.94  393.03
  266.95  393.78  308.35  381.22  325.48     372  395.03   372.7  426.44     377
  444.44     382  538.09  387.47  616.61     400  678.79     401  750.28   396.2
  794.44     399  911.21     400  988.31   395.1 1080.61  397.91  1163.9     398
 1298.87     395 1469.84     397 1508.53     403 1577.69     404 1652.59     402
 1912.56     403 1961.91     407 2029.13     424 2052.91     428 2064.87  427.93
#Mann= 3 ,0,0
       0    .055       0  266.95     .03       0  616.61    .055       0
Levee=-1,0,426.88,-1,2053,426.88,Levee 1,Levee 2
#XS Ineff= 2 , 0
       0  266.95  393.78  616.61       0     400
Permanent Ineff=
       F       F
Bank Sta=266.95,616.61
XS Rating Curve= 0 ,0
Exp/Cntr=0.3,0.1

Type RM Length L Ch R = 1 ,112872  ,101,100,94
BEGIN DESCRIPTION:
This cross section corresponds to cross section 112883 of the non-georeferenced CDC model which was the source of this model.
END DESCRIPTION:
XS GIS Cut Line= 2
2490316.314018996964266.055803722489042.149572586962655.81591396
#Sta/Elev= 30
       0     428  123.87     397  174.99     396  214.69     393  231.41     398
  243.56  397.78  298.62     381  319.42     372  338.41     371  376.45  371.34
  411.18     376  433.75     382  528.29     388  605.11     400  621.05     401
  834.96     398  868.28     400  923.23     400  989.15     395 1030.54   397.4
 1159.31     398 1279.67  395.07 1460.42     397 1473.67     398 1497.57  402.99
 1748.68  401.72 1903.81     403 1950.39     406 2017.53     423 2053.38     428
#Mann= 3 ,0,0
       0    .055       0  243.56     .03       0  621.05    .055       0
Levee=-1,0,426.86,-1,2048,426.86,Levee 1,Levee 2
#XS Ineff= 2 , 0
       0  243.56  397.78  621.05       0     401
Permanent Ineff=
       F       F
Bank Sta=243.56,621.05
XS Rating Curve= 0 ,0
Exp/Cntr=0.3,0.1

Type RM Length L Ch R = 1 ,112772  ,147,145,136
BEGIN DESCRIPTION:
This cross section corresponds to cross section 112783 of the non-georeferenced CDC model which was the source of this model.
END DESCRIPTION:
XS GIS Cut Line= 2
2490398.666216496964209.519499472489110.571351776962580.52735063
#Sta/Elev= 30
       0     429    18.7     426  127.97     397  205.67     393  252.48  395.29
  288.11  384.47   301.9     382  318.44     374  373.57  371.19  396.22  372.76
  430.07     381  537.74  388.86  620.04     402   704.9     402  846.83  396.67
 1128.53     398 1152.76     394 1191.24     394 1205.72     397 1284.53  397.82
 1375.39  395.06 1465.62     396 1510.24  399.36 1524.04     402 1736.65     401
 1875.59     403 1973.46     407 2042.24  423.68 2069.49     428 2076.73  427.57
#Mann= 3 ,0,0
       0    .055       0  252.48     .03       0  620.04    .055       0
Levee=-1,0,426.82,-1,2069,426.82,Levee 1,Levee 2
#XS Ineff= 2 , 0
       0  252.48  395.29  620.04       0     402
Permanent Ineff=
       F       F
Bank Sta=252.48,620.04
XS Rating Curve= 0 ,0
Exp/Cntr=0.3,0.1

Type RM Length L Ch R = 1 ,112627  ,160,160,152
BEGIN DESCRIPTION:
This cross section corresponds to cross section 112633 of the non-georeferenced CDC model which was the source of this model.
END DESCRIPTION:
XS GIS Cut Line= 2
2490503.479655186964103.604028882489190.717516936962473.11319539
#Sta/Elev= 30
       0     429   11.53     428   36.63     422  129.14     397  196.92  393.58
  245.15     395  293.08     382  306.81     374  335.69     372  390.38     372
  407.25     376  413.76  379.82  418.69     381  507.94     386  620.72     402
  668.74     402   748.8     399  975.71  398.04 1035.27     397 1057.82     395
 1126.22     395 1142.42  397.82 1509.46     396 1532.04     401 1741.86  400.21
  1962.7     405 1994.37     408 2066.85  425.65 2083.29     428 2093.35  427.31
#Mann= 3 ,0,0
       0    .055       0  245.15     .03       0  620.72    .055       0
Levee=-1,0,426.77,-1,2083,426.77,Levee 1,Levee 2
#XS Ineff= 2 , 0
       0  245.15     395  620.72       0     402
Permanent Ineff=
       F       F
Bank Sta=245.15,620.72
XS Rating Curve= 0 ,0
Exp/Cntr=0.3,0.1

Type RM Length L Ch R = 1 ,112467  ,167,165,158
BEGIN DESCRIPTION:
This cross section corresponds to cross section 112473 of the non-georeferenced CDC model which was the source of this model.
END DESCRIPTION:
XS GIS Cut Line= 2
2490623.760910666963993.177084392489293.577547436962371.72068164
#Sta/Elev= 30
       0  428.93   42.57     420  125.85     398  155.18     395  185.88     384
  199.36  384.31  201.37     390  214.76     395  239.71     395  285.27  381.01
  301.65     374   365.2     371  394.59  371.93   403.8  375.52  405.48     380
  508.87     384  567.49     401   667.4     400  831.27     395  913.55  398.98
  1015.9     399 1153.68     396 1500.05     397 1527.83     401 1607.64   400.9
 1638.59     399 1873.66     401 1989.12     405 2079.25  427.93 2097.43  428.19
#Mann= 3 ,0,0
       0    .055       0  239.71     .03       0  567.49    .055       0
Levee=-1,0,426.71,-1,2084,426.71,Levee 1,Levee 2
#XS Ineff= 2 , 0
       0  239.71     395  567.49       0     401
Permanent Ineff=
       F       F
Bank Sta=239.71,567.49
XS Rating Curve= 0 ,0
Exp/Cntr=0.3,0.1

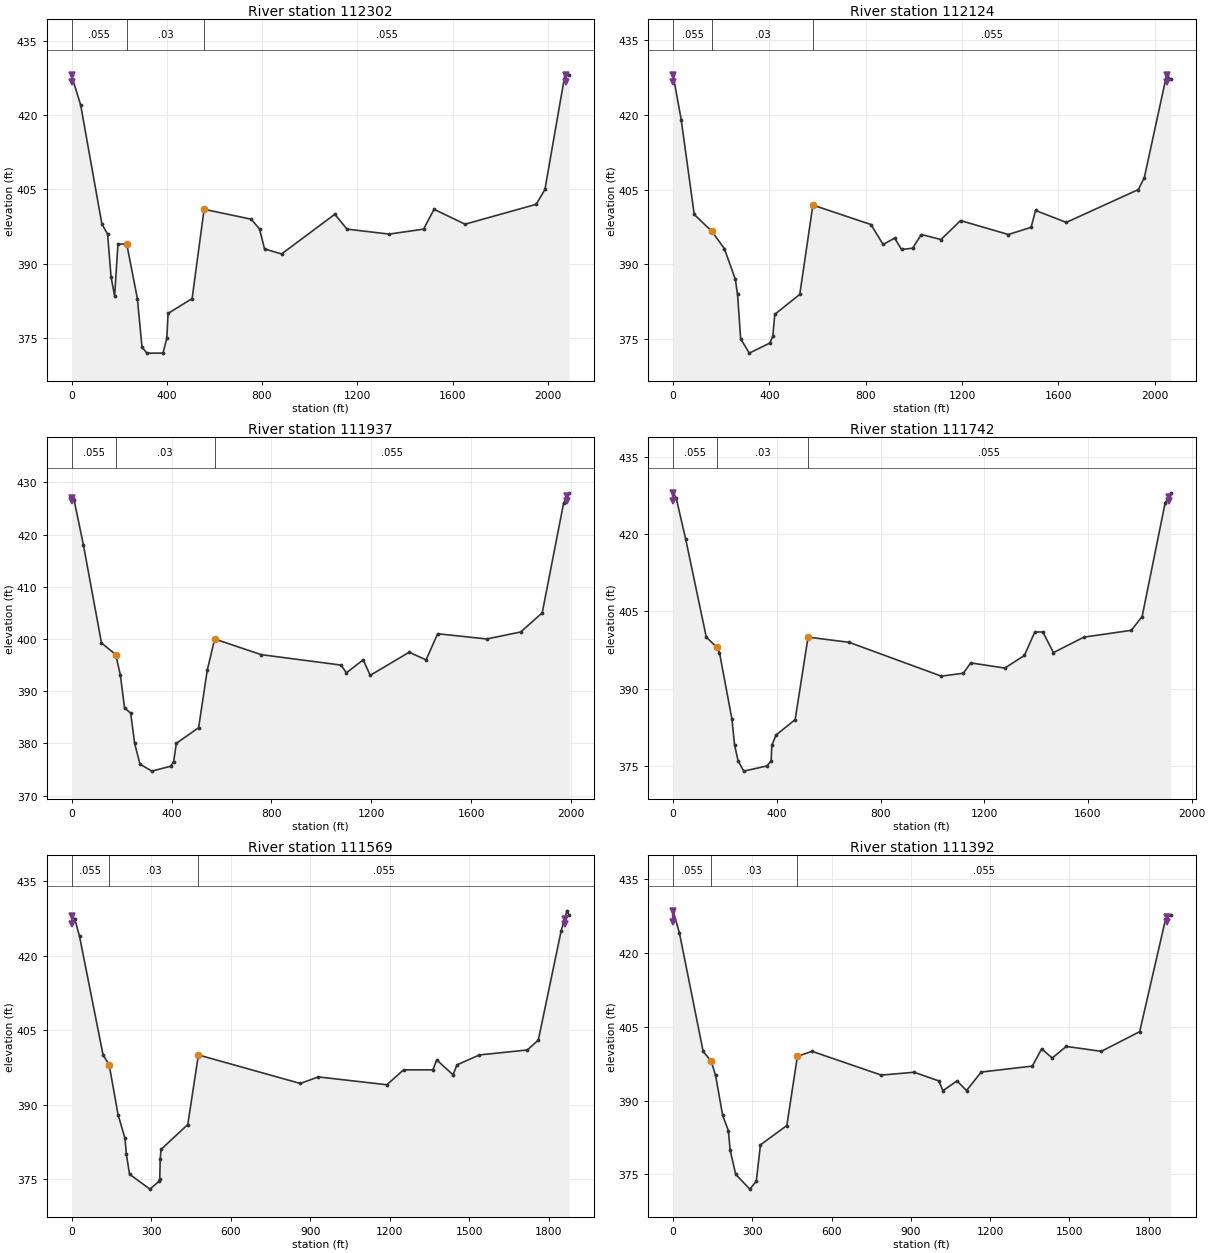
Type RM Length L Ch R = 1 ,112302  ,171,178,178
BEGIN DESCRIPTION:
This cross section corresponds to cross section 112314 of the non-georeferenced CDC model which was the source of this model.
END DESCRIPTION:
XS GIS Cut Line= 2
 2490765.76784456963900.621167142489425.391588246962297.35960989
#Sta/Elev= 30
       0     428    38.4     422  127.59     398  151.42     396  166.09  387.32
  180.89  383.51   194.9  393.98  231.78     394  276.48     383  295.85  373.24
  316.24     372  383.87     372  400.23     375  405.22     380   506.4     383
  556.71     401  755.16     399  789.55     397  810.59     393  882.26     392
 1105.74     400 1156.82     397 1333.92     396 1478.43     397 1522.47     401
 1652.56     398 1951.43     402 1988.18     405  2071.8     428 2089.75  428.11
#Mann= 3 ,0,0
       0    .055       0  231.78     .03       0  556.71    .055       0
Levee=-1,0,426.65,-1,2078,426.65,Levee 1,Levee 2
#XS Ineff= 2 , 0
       0  231.78     394  556.71       0     401
Permanent Ineff=
       F       F
Bank Sta=231.78,556.71
XS Rating Curve= 0 ,0
Exp/Cntr=0.3,0.1

Type RM Length L Ch R = 1 ,112124  ,179,187,186
BEGIN DESCRIPTION:
This cross section corresponds to cross section 112127 of the non-georeferenced CDC model which was the source of this model.
END DESCRIPTION:
XS GIS Cut Line= 2
 2490880.62424216963762.998410882489564.565850596962169.94122955
#Sta/Elev= 30
       0     428   33.87     419   87.93  400.02  161.35  396.62  213.19  393.17
  258.73     387  267.87  384.01  280.73  375.12  316.62  372.23  402.15  374.26
  414.07  375.59  422.44     380   526.2     384  580.66   401.9  821.69     398
  872.53     394  920.37  395.29   948.9     393  995.04  393.26 1031.01     396
  1112.8     395 1193.89  398.79 1392.66     396 1486.98  397.45  1505.5  400.82
 1633.13  398.43 1932.04     405 1957.15  407.41 2049.87     428 2066.36  427.09
#Mann= 3 ,0,0
       0    .055       0  161.35     .03       0  580.66    .055       0
Levee=-1,0,426.58,-1,2050,426.58,Levee 1,Levee 2
#XS Ineff= 2 , 0
       0  161.35  396.62  580.66       0   401.9
Permanent Ineff=
       F       F
Bank Sta=161.35,580.66
XS Rating Curve= 0 ,0
Exp/Cntr=0.3,0.1

Type RM Length L Ch R = 1 ,111937  ,188,195,195
BEGIN DESCRIPTION:
This cross section corresponds to cross section 111940 of the non-georeferenced CDC model which was the source of this model.
END DESCRIPTION:
XS GIS Cut Line= 2
2491014.563278686963637.590197132489754.250182516962096.10738772
#Sta/Elev= 30
       0     427   10.68  426.53   47.58     418  119.83  399.23  176.65  397.01
  195.33  393.11     212  386.81  236.68  385.78  252.48     380  273.91  376.02
  321.38  374.68  396.63  375.62  408.66  376.51  419.27     380  508.55     383
  543.01     394  572.67     400  758.77     397 1078.08     395 1099.93  393.52
 1166.95     396 1195.26  393.03 1351.08  397.46 1418.68     396 1465.03     401
 1661.76     400 1797.28  401.34 1883.45     405 1968.94     426 1991.12     428
#Mann= 3 ,0,0
       0    .055       0  176.65     .03       0  572.67    .055       0
Levee=-1,0,426.52,-1,1984,426.52,Levee 1,Levee 2
#XS Ineff= 2 , 0
       0  176.65  397.01  572.67       0     400
Permanent Ineff=
       F       F
Bank Sta=176.65,572.67
XS Rating Curve= 0 ,0
Exp/Cntr=0.3,0.1

Type RM Length L Ch R = 1 ,111742  ,163,173,176
BEGIN DESCRIPTION:
This cross section corresponds to cross section 111754 of the non-georeferenced CDC model which was the source of this model.
END DESCRIPTION:
XS GIS Cut Line= 2
2491121.001714086963471.335936472489914.719349746961979.32382864
#Sta/Elev= 30
       0     428   11.94     427    48.8     419  128.19     400  169.41     398
     179     397     227  384.11  237.16   379.1  250.82     376  272.58     374
  361.75     375  378.38     376  380.78     379  397.05     381   470.8     384
  520.58     400  678.19     399 1034.57  392.43 1119.38     393 1147.71     395
  1279.3     394 1354.72  396.44 1394.93     401    1426     401  1466.7     397
 1584.32     400 1767.02  401.32 1808.77     404 1897.27     426 1918.65  427.92
#Mann= 3 ,0,0
       0    .055       0  169.41     .03       0  520.58    .055       0
Levee=-1,0,426.45,-1,1911,426.45,Levee 1,Levee 2
#XS Ineff= 2 , 0
       0  169.41     398  520.58       0     400
Permanent Ineff=
       F       F
Bank Sta=169.41,520.58
XS Rating Curve= 0 ,0
Exp/Cntr=0.3,0.1

Type RM Length L Ch R = 1 ,111569  ,166,177,180
BEGIN DESCRIPTION:
This cross section corresponds to cross section 111577 of the non-georeferenced CDC model which was the source of this model.
END DESCRIPTION:
XS GIS Cut Line= 3
2491220.013983256963328.716471052491151.802833596963239.47222696
2490058.986777756961855.05373597
#Sta/Elev= 30
       0     428   12.39  427.32   30.07  423.87   118.9     400  141.96     398
  175.38     388  201.58   383.2  206.79     380  218.63     376   295.4     373
  330.62  374.62  332.58     375  334.25  378.98  337.23  380.98  438.21     386
  478.37     400  862.75  394.26  930.19  395.58  1188.9     394 1251.87     397
 1362.39     397 1376.84     399 1438.53     396 1453.08     398 1537.67     400
 1718.68     401 1760.04     403 1846.16     425 1868.17     429 1876.09   428.1
#Mann= 3 ,0,0
       0    .055       0  141.96     .03       0  478.37    .055       0
Levee=-1,0,426.39,-1,1859,426.39,Levee 1,Levee 2
#XS Ineff= 2 , 0
       0  141.96     398  478.37       0     400
Permanent Ineff=
       F       F
Bank Sta=141.96,478.37
XS Rating Curve= 0 ,0
Exp/Cntr=0.3,0.1

Type RM Length L Ch R = 1 ,111392  ,170,180,183
BEGIN DESCRIPTION:
This cross section corresponds to cross section 111400 of the non-georeferenced CDC model which was the source of this model.
END DESCRIPTION:
XS GIS Cut Line= 3
2491356.869352586963216.411905632491279.748115756963119.73591788
2490205.440225016961725.84238021
#Sta/Elev= 30
       0  428.55   24.06  424.07  113.78     400  144.13     398  160.71  395.18
  187.78     387  209.46  383.87  216.09  379.92  237.18     375  290.67     372
  315.11   373.6  330.76     381  430.68  384.92  470.69     399  526.22     400
  788.31  395.17  912.72  395.75 1005.54     394 1021.69     392 1074.93     394
 1110.82  392.03 1166.44  395.79 1359.86     397 1395.17   400.5 1435.51  398.64
 1488.26     401 1621.14     400 1766.37     404 1864.99     427 1883.52  427.77
#Mann= 3 ,0,0
       0    .055       0  144.13     .03       0  470.69    .055       0
Levee=-1,0,426.32,-1,1870,426.32,Levee 1,Levee 2
#XS Ineff= 2 , 0
       0  144.13     398  470.69       0     399
Permanent Ineff=
       F       F
Bank Sta=144.13,470.69
XS Rating Curve= 0 ,0
Exp/Cntr=0.3,0.1