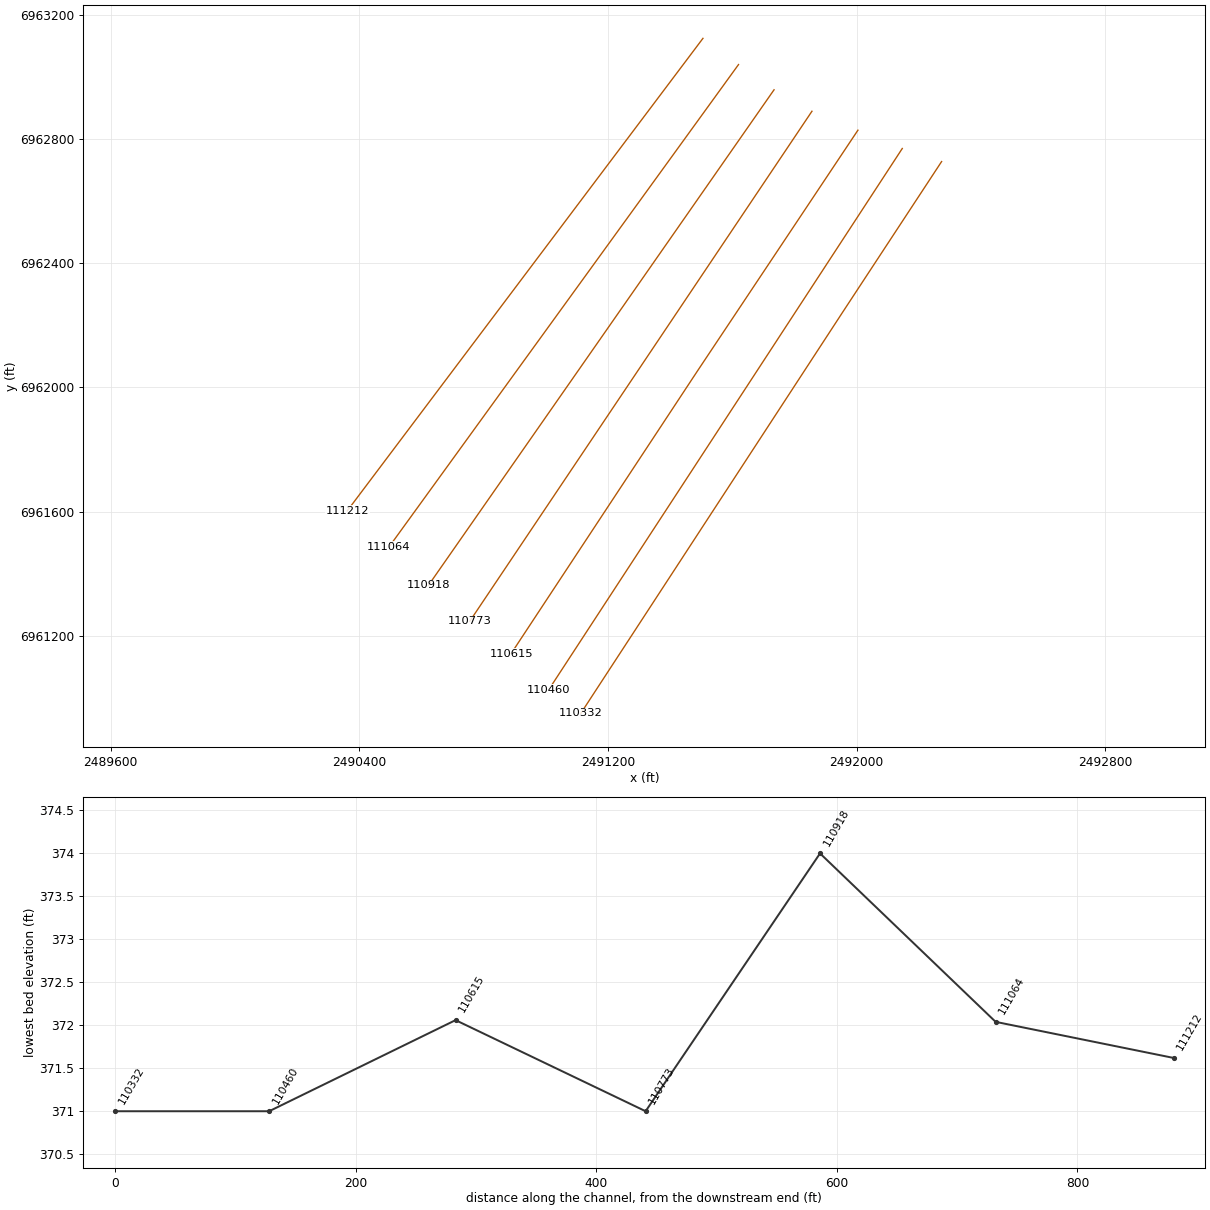
HEC-RAS study CDC_Consolidated_Model.prj: Upper Trinity CDC Consolidated Model

--- CDC_Consolidated_Model.g01 (geometry) --- (continued)

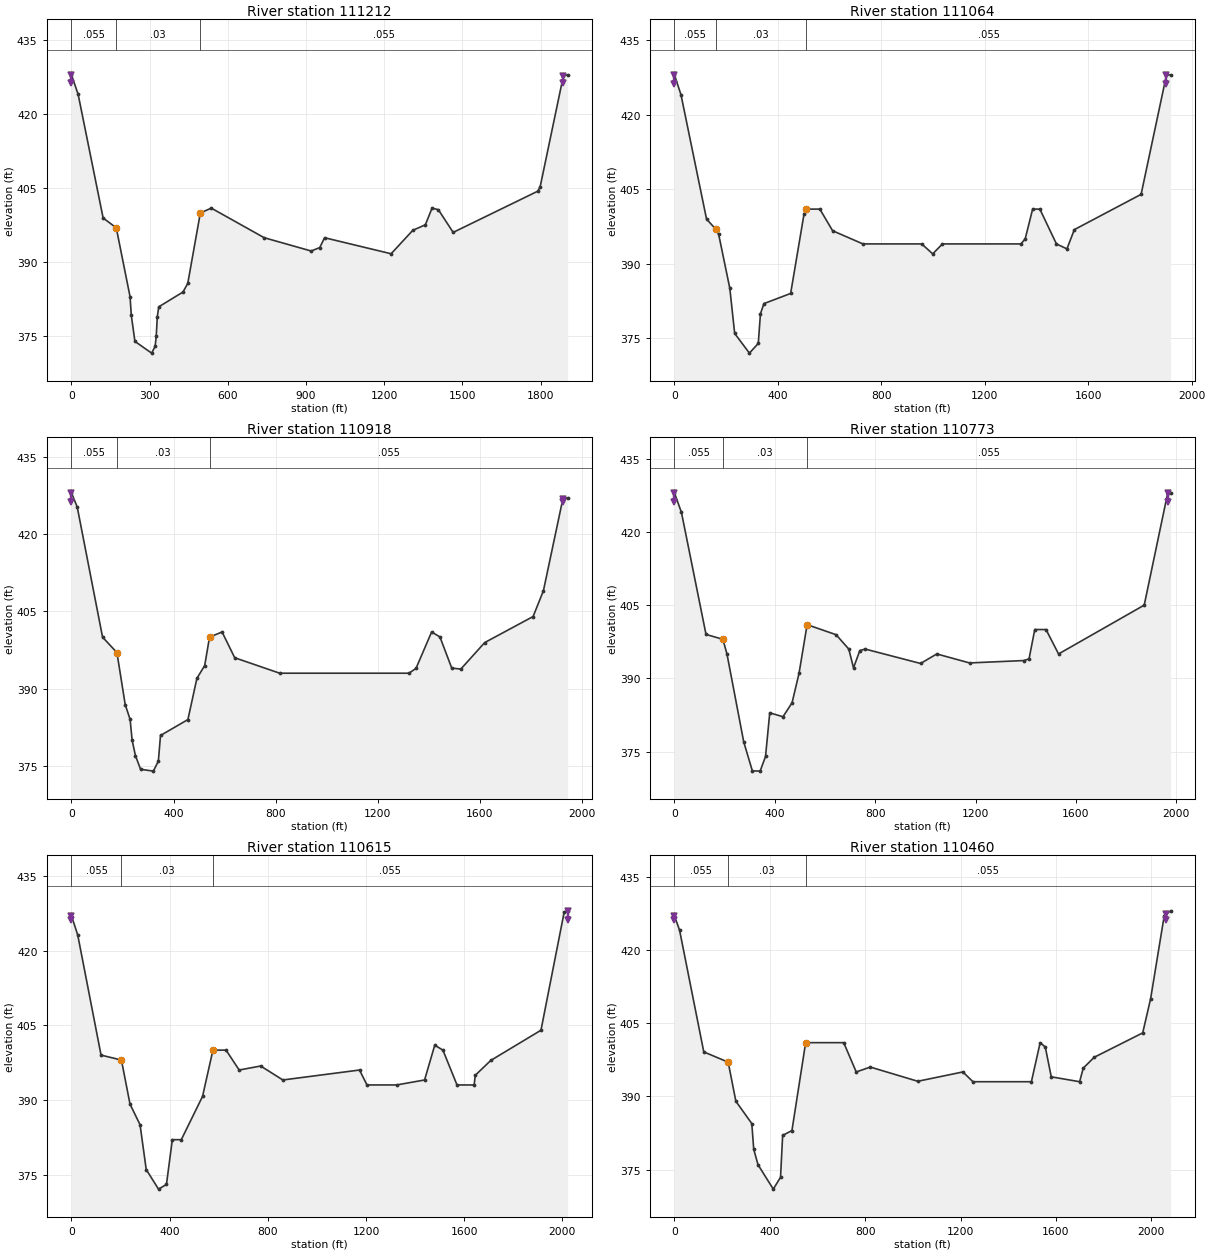
Type RM Length L Ch R = 1 ,111212  ,141,148,158
BEGIN DESCRIPTION:
This cross section corresponds to cross section 111223 of the non-georeferenced CDC model which was the source of this model.
END DESCRIPTION:
XS GIS Cut Line= 2
2491505.803766016963123.907497472490361.193850526961602.09394005
#Sta/Elev= 30
       0     428    25.6  424.04  121.46     399  171.91     397  224.82  383.05
  229.69  379.25  243.46     374  307.66  371.62  321.13     373  325.25     375
  329.39     379  335.04     381  427.97     384  446.33  385.75  494.45     400
  536.45     401  739.67     395  919.73  392.31  952.78     393  971.38     395
  1226.7  391.75 1309.88   396.5 1358.12  397.62 1383.79     401 1407.96  400.68
 1464.87  396.08 1790.08  404.44  1798.9  405.37 1887.96  427.82 1904.22     428
#Mann= 3 ,0,0
       0    .055       0  171.91     .03       0  494.45    .055       0
Levee=-1,0,426.26,-1,1888,426.26,Levee 1,Levee 2
#XS Ineff= 2 , 0
       0  171.91     397  494.45       0     400
Permanent Ineff=
       F       F
Bank Sta=171.91,494.45
XS Rating Curve= 0 ,0
Exp/Cntr=0.3,0.1

Type RM Length L Ch R = 1 ,111064  ,139,146,155
BEGIN DESCRIPTION:
This cross section corresponds to cross section 111076 of the non-georeferenced CDC model which was the source of this model.
END DESCRIPTION:
XS GIS Cut Line= 2
2491620.244810076963039.485422212490495.36385775 6961485.5400393
#Sta/Elev= 30
       0     428   25.37     424  124.15     399  159.13     397  170.77     396
  214.14  385.08  232.97     376  289.91  372.04  324.23     374  332.58  379.95
  346.09     382  449.35  384.04  501.08     400   510.4     401  562.25     401
  611.55  396.65  728.77     394     956     394  998.62     392 1036.25     394
 1339.61     394  1356.1     395 1384.95     401 1412.83     401 1476.98     394
 1517.53     393 1546.14  396.87 1804.32  403.97 1902.49     428 1918.36     428
#Mann= 3 ,0,0
       0    .055       0  159.13     .03       0   510.4    .055       0
Levee=-1,0,426.21,-1,1902,426.21,Levee 1,Levee 2
#XS Ineff= 2 , 0
       0  159.13     397   510.4       0     401
Permanent Ineff=
       F       F
Bank Sta=159.13,510.4
XS Rating Curve= 0 ,0
Exp/Cntr=0.3,0.1

Type RM Length L Ch R = 1 ,110918  ,139,145,156
BEGIN DESCRIPTION:
This cross section corresponds to cross section 110929 of the non-georeferenced CDC model which was the source of this model.
END DESCRIPTION:
XS GIS Cut Line= 2
2491734.502455596962958.187684552490622.644771166961362.42939313
#Sta/Elev= 30
       0     428   22.54  425.25  121.83     400  178.19     397  210.66   386.9
  229.88  384.04  237.64  380.03  250.71  377.01   270.8  374.36  320.85     374
  340.54  375.92  348.97  380.92  456.36     384  491.65     392  522.21  394.49
  541.18     400   590.3     401  639.85     396  816.19     393 1322.74     393
 1350.46  393.93 1411.69     401 1444.28  400.04 1490.49     394 1526.15   393.8
 1619.65  398.94 1809.53     404 1849.88     409 1926.89     427 1944.91  426.97
#Mann= 3 ,0,0
       0    .055       0  178.19     .03       0  541.18    .055       0
Levee=-1,0,426.17,-1,1926,426.17,Levee 1,Levee 2
#XS Ineff= 2 , 0
       0  178.19     397  541.18       0     400
Permanent Ineff=
       F       F
Bank Sta=178.19,541.18
XS Rating Curve= 0 ,0
Exp/Cntr=0.3,0.1

Type RM Length L Ch R = 1 ,110773  ,151,158,156
BEGIN DESCRIPTION:
This cross section corresponds to cross section 110783 of the non-georeferenced CDC model which was the source of this model.
END DESCRIPTION:
XS GIS Cut Line= 2
2491856.513366436962889.141890882490755.759334336961247.08382329
#Sta/Elev= 30
       0     428   27.95     424  125.87     399  192.97     398  209.34     395
  276.06     377  310.46  371.06  341.52     371  362.98     374  379.81  382.94
  432.56  382.14  468.69     385  496.41     391  528.68     401  644.23  398.94
  694.71     396  713.52  392.15  738.71   395.7  760.05     396  980.71  393.05
 1045.39     395 1175.82  393.16 1392.65  393.65 1412.91     394 1435.72     400
 1480.49     400 1530.51     395 1871.77     405 1965.53     428 1976.87     428
#Mann= 3 ,0,0
       0    .055       0  192.97     .03       0  528.68    .055       0
Levee=-1,0,426.12,-1,1965,426.12,Levee 1,Levee 2
#XS Ineff= 2 , 0
       0  192.97     398  528.68       0     401
Permanent Ineff=
       F       F
Bank Sta=192.97,528.68
XS Rating Curve= 0 ,0
Exp/Cntr=0.3,0.1

Type RM Length L Ch R = 1 ,110615  ,149,155,154
BEGIN DESCRIPTION:
This cross section corresponds to cross section 110626 of the non-georeferenced CDC model which was the source of this model.
END DESCRIPTION:
XS GIS Cut Line= 3
2492004.450078436962828.175149312491486.999997826962051.00019446
2490888.592730086961142.50004296
#Sta/Elev= 30
       0     427   25.47  423.15  120.48     399  203.55     398  238.48  389.15
  279.41     385  304.54     376  354.62  372.06  386.99     373   410.9     382
  447.43     382  533.96  390.69  576.31     400   629.8     400   683.2     396
  770.85  396.81  861.22     394 1173.56     396 1203.87     393 1325.07     393
 1438.63     394 1480.12     401 1513.32     400 1570.74     393 1640.61     393
 1645.12  394.94 1708.35  397.93 1912.82     404 2007.57  427.78 2021.55     428
#Mann= 3 ,0,0
       0    .055       0  203.55     .03       0  576.31    .055       0
Levee=-1,0,426.07,-1,2021,426.07,Levee 1,Levee 2
#XS Ineff= 2 , 0
       0  203.55     398  576.31       0     400
Permanent Ineff=
       F       F
Bank Sta=203.55,576.31
XS Rating Curve= 0 ,0
Exp/Cntr=0.3,0.1

Type RM Length L Ch R = 1 ,110460  ,83,128,183
BEGIN DESCRIPTION:
This cross section corresponds to cross section 110470 of the non-georeferenced CDC model which was the source of this model.
END DESCRIPTION:
XS GIS Cut Line= 2
2492147.141066016962769.199217382491009.789994276961026.54981555
#Sta/Elev= 30
       0     427   21.73     424  123.11  399.11  225.46     397  257.69     389
  324.52  384.43  332.61  379.17  350.57     376  414.63     371  445.05  373.43
  453.89     382  492.87     383  550.38     401  710.05     401  762.46     395
  821.63     396 1020.55  393.09 1209.75     395 1252.02     393 1497.19     393
 1533.89     401 1555.38  400.11 1580.44     394 1699.44     393 1714.57  395.78
 1760.46     398 1963.98     403 1997.18     410 2054.22     427 2080.96     428
#Mann= 3 ,0,0
       0    .055       0  225.46     .03       0  550.38    .055       0
Levee=-1,0,426.02,-1,2063,426.02,Levee 1,Levee 2
#XS Ineff= 2 , 0
       0  225.46     397  550.38       0     401
Permanent Ineff=
       F       F
Bank Sta=225.46,550.38
XS Rating Curve= 0 ,0
Exp/Cntr=0.3,0.1

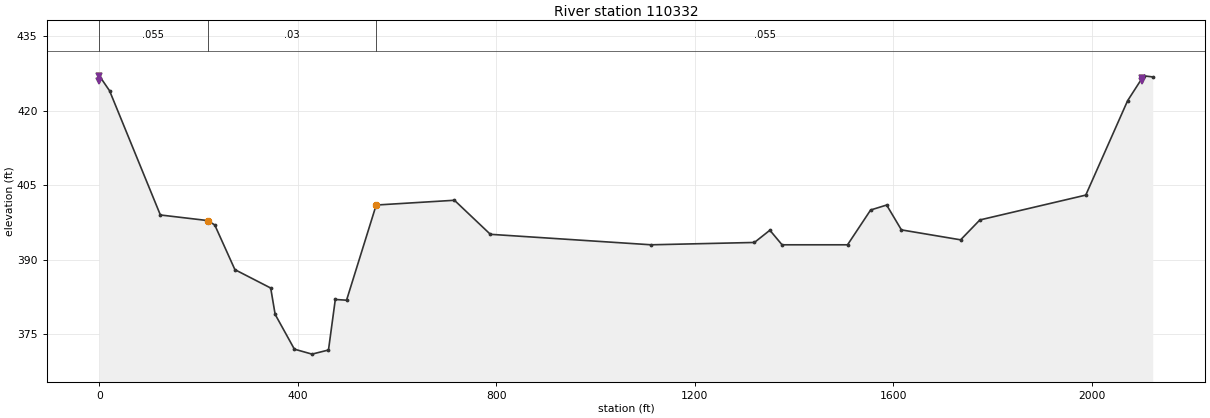
Type RM Length L Ch R = 1 ,110332  ,83,127,182
BEGIN DESCRIPTION:
This cross section corresponds to cross section 110342 of the non-georeferenced CDC model which was the source of this model.
END DESCRIPTION:
XS GIS Cut Line= 3
2492273.650655516962727.05494471 2491954.00004816962240.00014456
 2491112.69628456960949.94695038
#Sta/Elev= 30
       0     427   20.59     424  122.98     399  217.96  397.88  232.53     397
   273.2     388  345.31   384.3  354.28     379  393.01     372  428.56     371
  461.76  371.83  475.51     382  498.18  381.85  557.89     401  715.55  401.96
  787.93  395.11 1111.98     393 1320.06  393.47 1351.18  395.93 1375.77     393
 1507.71     393 1554.21     400 1586.49     401 1616.28     396 1735.57     394
 1774.34     398 1987.74     403  2072.1     422 2104.33     427 2122.72  426.78
#Mann= 3 ,0,0
       0    .055       0  217.96     .03       0  557.89    .055       0
Levee=-1,0,425.98,-1,2102,425.98,Levee 1,Levee 2
#XS Ineff= 2 , 0
       0  217.96  397.88  557.89       0     401
Permanent Ineff=
       F       F
Bank Sta=217.96,557.89
XS Rating Curve= 0 ,0
Exp/Cntr=0.3,0.1