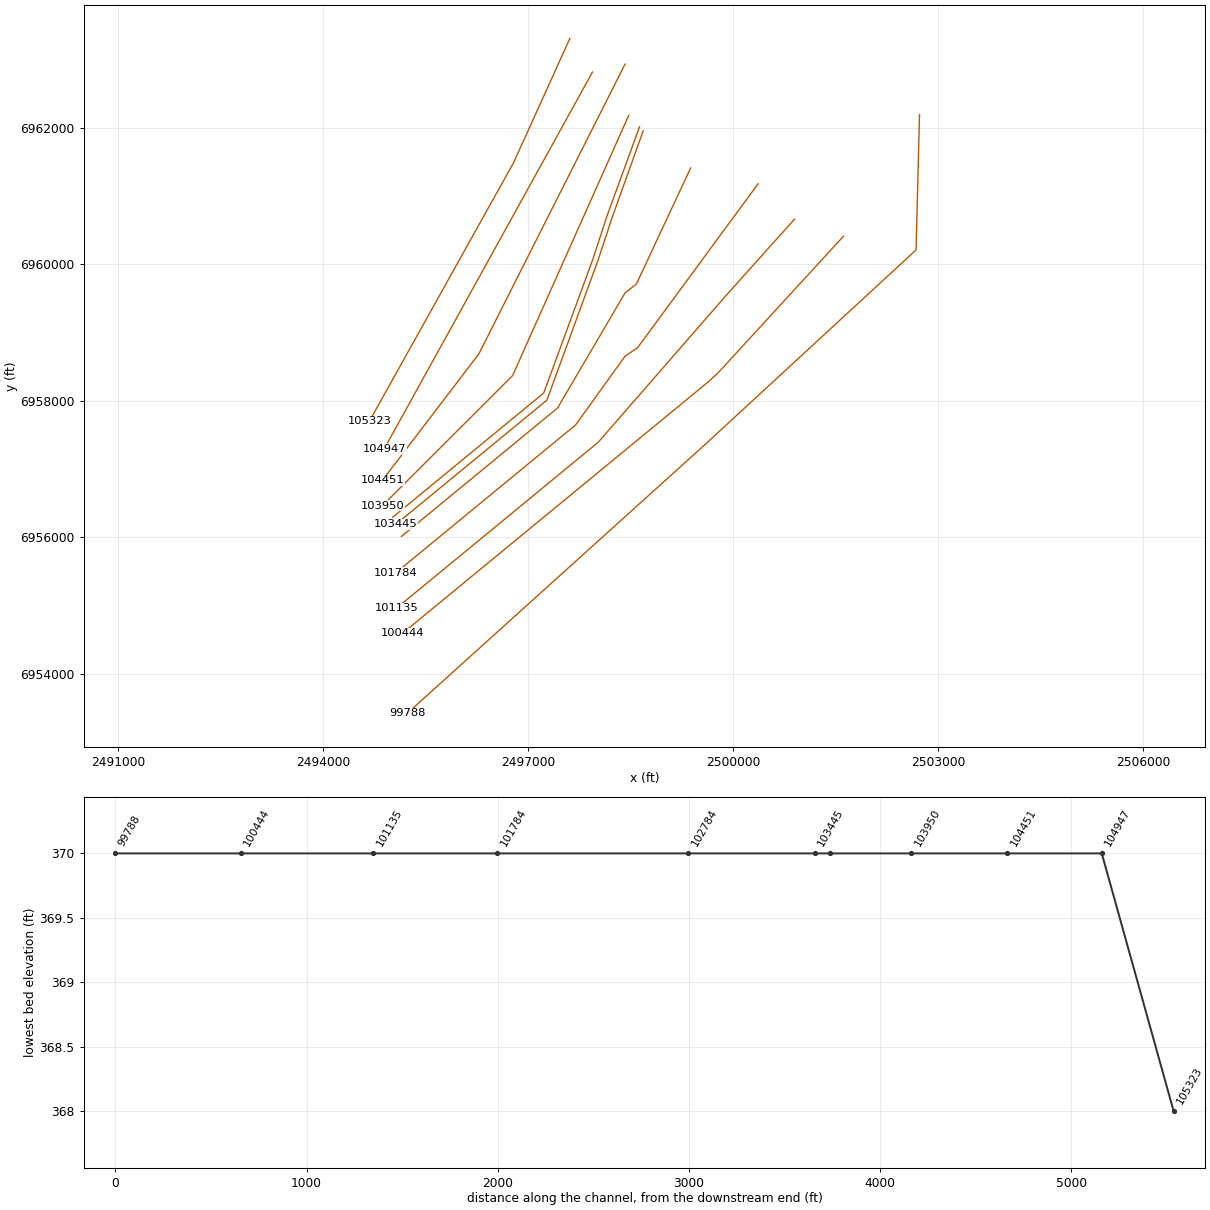
HEC-RAS study CDC_Consolidated_Model.prj: Upper Trinity CDC Consolidated Model

--- CDC_Consolidated_Model.g01 (geometry) --- (continued)

Type RM Length L Ch R = 3 ,105358  ,,,
BEGIN DESCRIPTION:
105358  Martin Luther King Jr. Boulevard
END DESCRIPTION:
Node Name=MLK Blvd.
Bridge Culvert--1,0,-1,-1, 0
Deck Dist Width WeirC Skew NumUp NumDn MinLoCord MaxHiCord MaxSubmerge Is_Ogee
1,67,2.6,0, 56, 56, , , 0.95, 0, ,,,
    1100    1141    1191    1241    1291    1341    1391    1441    1491    1541
    1598    1598    1641    1691    1741    1791    1841    1891    1941    1964
    1964    1991    2041    2091    2141    2191    2241    2291    2341    2391
    2441    2491    2541    2591    2641    2691    2741    2791    2841    2891
    2941    2991    3041    3091    3141    3191    3241    3291    3341    3391
    3441    3491    3541    3591    3641    3686
   425.1   425.5     426   426.5   426.9   427.3   427.7   428.1   428.4   428.7
     429     429   429.3   429.5   429.7   429.9     430   430.1   430.2   430.2
   430.2   430.3   430.3   430.4   430.3   430.3   430.2   430.1     430   429.9
   429.7   429.5   429.3   429.1   428.9   428.7   428.5   428.3   428.1   427.9
   427.7   427.5   427.3   427.1   426.9   426.7   426.5   426.3   426.1   425.9
   425.7   425.5   425.2   424.9   424.3   423.7
   418.7   419.1   419.6   420.1   420.5   420.9   421.3   421.7     422   422.3
   422.6   420.4   420.7   420.9   421.1   421.3   421.4   421.5   421.6   421.6
   423.8   423.9   423.9     424   423.9   423.9   423.8   423.7   423.6   423.5
   423.3   423.1   422.9   422.7   422.5   422.3   422.1   421.9   421.7   421.5
   421.3   421.1   420.9   420.7   420.5   420.3   420.1   419.9   419.7   419.5
   419.3   419.1   418.8   418.5   418.3   417.3
    1100    1141    1191    1241    1291    1341    1391    1441    1491    1541
    1598    1598    1641    1691    1741    1791    1841    1891    1941    1964
    1964    1991    2041    2091    2141    2191    2241    2291    2341    2391
    2441    2491    2541    2591    2641    2691    2741    2791    2841    2891
    2941    2991    3041    3091    3141    3191    3241    3291    3341    3391
    3441    3491    3541    3591    3641    3686
   425.1   425.5     426   426.5   426.9   427.3   427.7   428.1   428.4   428.7
     429     429   429.3   429.5   429.7   429.9     430   430.1   430.2   430.2
   430.2   430.3   430.3   430.4   430.3   430.3   430.2   430.1     430   429.9
   429.7   429.5   429.3   429.1   428.9   428.7   428.5   428.3   428.1   427.9
   427.7   427.5   427.3   427.1   426.9   426.7   426.5   426.3   426.1   425.9
   425.7   425.5   425.2   424.9   424.3   423.7
   418.7   419.1   419.6   420.1   420.5   420.9   421.3   421.7     422   422.3
   422.6   420.4   420.7   420.9   421.1   421.3   421.4   421.5   421.6   421.6
   423.8   423.9   423.9     424   423.9   423.9   423.8   423.7   423.6   423.5
   423.3   423.1   422.9   422.7   422.5   422.3   422.1   421.9   421.7   421.5
   421.3   421.1   420.9   420.7   420.5   420.3   420.1   419.9   419.7   419.5
   419.3   419.1   418.8   418.5   418.3   417.3
Pier Skew, UpSta & Num, DnSta & Num=  ,1145, 2 ,1145, 2 , 0 , 0 , 0 ,,
     2.5     2.5
       0   420.5
     2.5     2.5
       0   420.5
Pier Skew, UpSta & Num, DnSta & Num=  ,1190, 2 ,1190, 2 , 0 , 0 , 0 ,,
     2.5     2.5
       0   421.5
     2.5     2.5
       0   421.5
Pier Skew, UpSta & Num, DnSta & Num=  ,1241, 2 ,1241, 2 , 0 , 0 , 0 ,,
     2.5     2.5
       0     423
     2.5     2.5
       0     423
Pier Skew, UpSta & Num, DnSta & Num=  ,1292, 2 ,1292, 2 , 0 , 0 , 0 ,,
     2.5     2.5
       0     424
     2.5     2.5
       0     424
Pier Skew, UpSta & Num, DnSta & Num=  ,1343, 2 ,1343, 2 , 0 , 0 , 0 ,,
     2.5     2.5
       0   422.5
     2.5     2.5
       0   422.5
Pier Skew, UpSta & Num, DnSta & Num=  ,1394, 2 ,1394, 2 , 0 , 0 , 0 ,,
     2.5     2.5
       0   422.5
     2.5     2.5
       0   422.5
Pier Skew, UpSta & Num, DnSta & Num=  ,1445, 2 ,1445, 2 , 0 , 0 , 0 ,,
     2.5     2.5
       0   422.5
     2.5     2.5
       0   422.5
Pier Skew, UpSta & Num, DnSta & Num=  ,1496, 2 ,1496, 2 , 0 , 0 , 0 ,,
     2.5     2.5
       0   424.5
     2.5     2.5
       0   424.5
Pier Skew, UpSta & Num, DnSta & Num=  ,1547, 2 ,1547, 2 , 0 , 0 , 0 ,,
     2.5     2.5
       0   424.5
     2.5     2.5
       0   424.5
Pier Skew, UpSta & Num, DnSta & Num=  ,1598, 2 ,1598, 2 , 0 , 0 , 0 ,,
       3       3
       0     424
       3       3
       0     424
Pier Skew, UpSta & Num, DnSta & Num=  ,1711, 2 ,1711, 2 , 0 , 0 , 0 ,,
       4       4
       0     424
       4       4
       0     424
Pier Skew, UpSta & Num, DnSta & Num=  ,1851, 2 ,1851, 2 , 0 , 0 , 0 ,,
       4       4
       0   423.5
       4       4
       0   423.5
Pier Skew, UpSta & Num, DnSta & Num=  ,1964, 2 ,1964, 2 , 0 , 0 , 0 ,,
       3       3
       0   423.5
       3       3
       0   423.5
Pier Skew, UpSta & Num, DnSta & Num=  ,2015, 2 ,2015, 2 , 0 , 0 , 0 ,,
     2.5     2.5
       0     424
     2.5     2.5
       0     424
Pier Skew, UpSta & Num, DnSta & Num=  ,2066, 2 ,2066, 2 , 0 , 0 , 0 ,,
     2.5     2.5
       0     424
     2.5     2.5
       0     424
Pier Skew, UpSta & Num, DnSta & Num=  ,2117, 2 ,2117, 2 , 0 , 0 , 0 ,,
     2.5     2.5
       0     424
     2.5     2.5
       0     424
Pier Skew, UpSta & Num, DnSta & Num=  ,2168, 2 ,2168, 2 , 0 , 0 , 0 ,,
     2.5     2.5
       0     424
     2.5     2.5
       0     424
Pier Skew, UpSta & Num, DnSta & Num=  ,2219, 2 ,2219, 2 , 0 , 0 , 0 ,,
     2.5     2.5
       0     424
     2.5     2.5
       0     424
Pier Skew, UpSta & Num, DnSta & Num=  ,2270, 2 ,2270, 2 , 0 , 0 , 0 ,,
     2.5     2.5
       0     424
     2.5     2.5
       0     424
Pier Skew, UpSta & Num, DnSta & Num=  ,2321, 2 ,2321, 2 , 0 , 0 , 0 ,,
     2.5     2.5
       0     424
     2.5     2.5
       0     424
Pier Skew, UpSta & Num, DnSta & Num=  ,2372, 2 ,2372, 2 , 0 , 0 , 0 ,,
     2.5     2.5
       0     425
     2.5     2.5
       0     425
Pier Skew, UpSta & Num, DnSta & Num=  ,2423, 2 ,2423, 2 , 0 , 0 , 0 ,,
     2.5     2.5
       0     424
     2.5     2.5
       0     424
Pier Skew, UpSta & Num, DnSta & Num=  ,2423, 2 ,2423, 2 , 0 , 0 , 0 ,,
     2.5     2.5
       0     424
     2.5     2.5
       0     424
Pier Skew, UpSta & Num, DnSta & Num=  ,2474, 2 ,2474, 2 , 0 , 0 , 0 ,,
     2.5     2.5
       0     424
     2.5     2.5
       0     424
Pier Skew, UpSta & Num, DnSta & Num=  ,2525, 2 ,2525, 2 , 0 , 0 , 0 ,,
     2.5     2.5
       0     424
     2.5     2.5
       0     424
Pier Skew, UpSta & Num, DnSta & Num=  ,2576, 2 ,2576, 2 , 0 , 0 , 0 ,,
     2.5     2.5
       0     424
     2.5     2.5
       0     424
Pier Skew, UpSta & Num, DnSta & Num=  ,2627, 2 ,2627, 2 , 0 , 0 , 0 ,,
     2.5     2.5
       0     424
     2.5     2.5
       0     424
Pier Skew, UpSta & Num, DnSta & Num=  ,2678, 2 ,2678, 2 , 0 , 0 , 0 ,,
     2.5     2.5
       0     424
     2.5     2.5
       0     424
Pier Skew, UpSta & Num, DnSta & Num=  ,2729, 2 ,2729, 2 , 0 , 0 , 0 ,,
     2.5     2.5
       0     424
     2.5     2.5
       0     424
Pier Skew, UpSta & Num, DnSta & Num=  ,2780, 2 ,2780, 2 , 0 , 0 , 0 ,,
     2.5     2.5
       0     424
     2.5     2.5
       0     424
Pier Skew, UpSta & Num, DnSta & Num=  ,2831, 2 ,2831, 2 , 0 , 0 , 0 ,,
     2.5     2.5
       0     424
     2.5     2.5
       0     424
Pier Skew, UpSta & Num, DnSta & Num=  ,2882, 2 ,2882, 2 , 0 , 0 , 0 ,,
     2.5     2.5
       0     424
     2.5     2.5
       0     424
Pier Skew, UpSta & Num, DnSta & Num=  ,2933, 2 ,2933, 2 , 0 , 0 , 0 ,,
     2.5     2.5
       0     424
     2.5     2.5
       0     424
Pier Skew, UpSta & Num, DnSta & Num=  ,2984, 2 ,2984, 2 , 0 , 0 , 0 ,,
     2.5     2.5
       0     424
     2.5     2.5
       0     424
Pier Skew, UpSta & Num, DnSta & Num=  ,3035, 2 ,3035, 2 , 0 , 0 , 0 ,,
     2.5     2.5
       0     424
     2.5     2.5
       0     424
Pier Skew, UpSta & Num, DnSta & Num=  ,3086, 2 ,3086, 2 , 0 , 0 , 0 ,,
     2.5     2.5
       0     424
     2.5     2.5
       0     424
Pier Skew, UpSta & Num, DnSta & Num=  ,3137, 2 ,3137, 2 , 0 , 0 , 0 ,,
     2.5     2.5
       0     424
     2.5     2.5
       0     424
Pier Skew, UpSta & Num, DnSta & Num=  ,3188, 2 ,3188, 2 , 0 , 0 , 0 ,,
     2.5     2.5
       0     423
     2.5     2.5
       0     423
Pier Skew, UpSta & Num, DnSta & Num=  ,3239, 2 ,3239, 2 , 0 , 0 , 0 ,,
     2.5     2.5
       0     423
     2.5     2.5
       0     423
Pier Skew, UpSta & Num, DnSta & Num=  ,3290, 2 ,3290, 2 , 0 , 0 , 0 ,,
     2.5     2.5
       0     423
     2.5     2.5
       0     423
Pier Skew, UpSta & Num, DnSta & Num=  ,3341, 2 ,3341, 2 , 0 , 0 , 0 ,,
     2.5     2.5
       0     423
     2.5     2.5
       0     423
Pier Skew, UpSta & Num, DnSta & Num=  ,3392, 2 ,3392, 2 , 0 , 0 , 0 ,,
     2.5     2.5
       0     423
     2.5     2.5
       0     423
Pier Skew, UpSta & Num, DnSta & Num=  ,3443, 2 ,3443, 2 , 0 , 0 , 0 ,,
     2.5     2.5
       0     423
     2.5     2.5
       0     423
Pier Skew, UpSta & Num, DnSta & Num=  ,3494, 2 ,3494, 2 , 0 , 0 , 0 ,,
     2.5     2.5
       0     422
     2.5     2.5
       0     422
Pier Skew, UpSta & Num, DnSta & Num=  ,3545, 2 ,3545, 2 , 0 , 0 , 0 ,,
     2.5     2.5
       0     422
     2.5     2.5
       0     422
Pier Skew, UpSta & Num, DnSta & Num=  ,3596, 2 ,3596, 2 , 0 , 0 , 0 ,,
     2.5     2.5
       0     422
     2.5     2.5
       0     422
Pier Skew, UpSta & Num, DnSta & Num=  ,3641, 2 ,3641, 2 , 0 , 0 , 0 ,,
     2.5     2.5
       0     421
     2.5     2.5
       0     421
BR Coef= 1 , 0 , 0 ,1.05, 0 ,,,0.8,-1,0.5,1,
WSPro=,,,, 1 ,,,, 0 ,,,, 0 ,,,,-1 ,-1 ,-1 , 0 , 0 , 0 , 0 , 0
BC Design=,, 0 ,, 0 ,,,,,,
BC HTab HWMax=425.1
BC Use User HTab Curves=0
BC User HTab FreeFlow(D)= 0

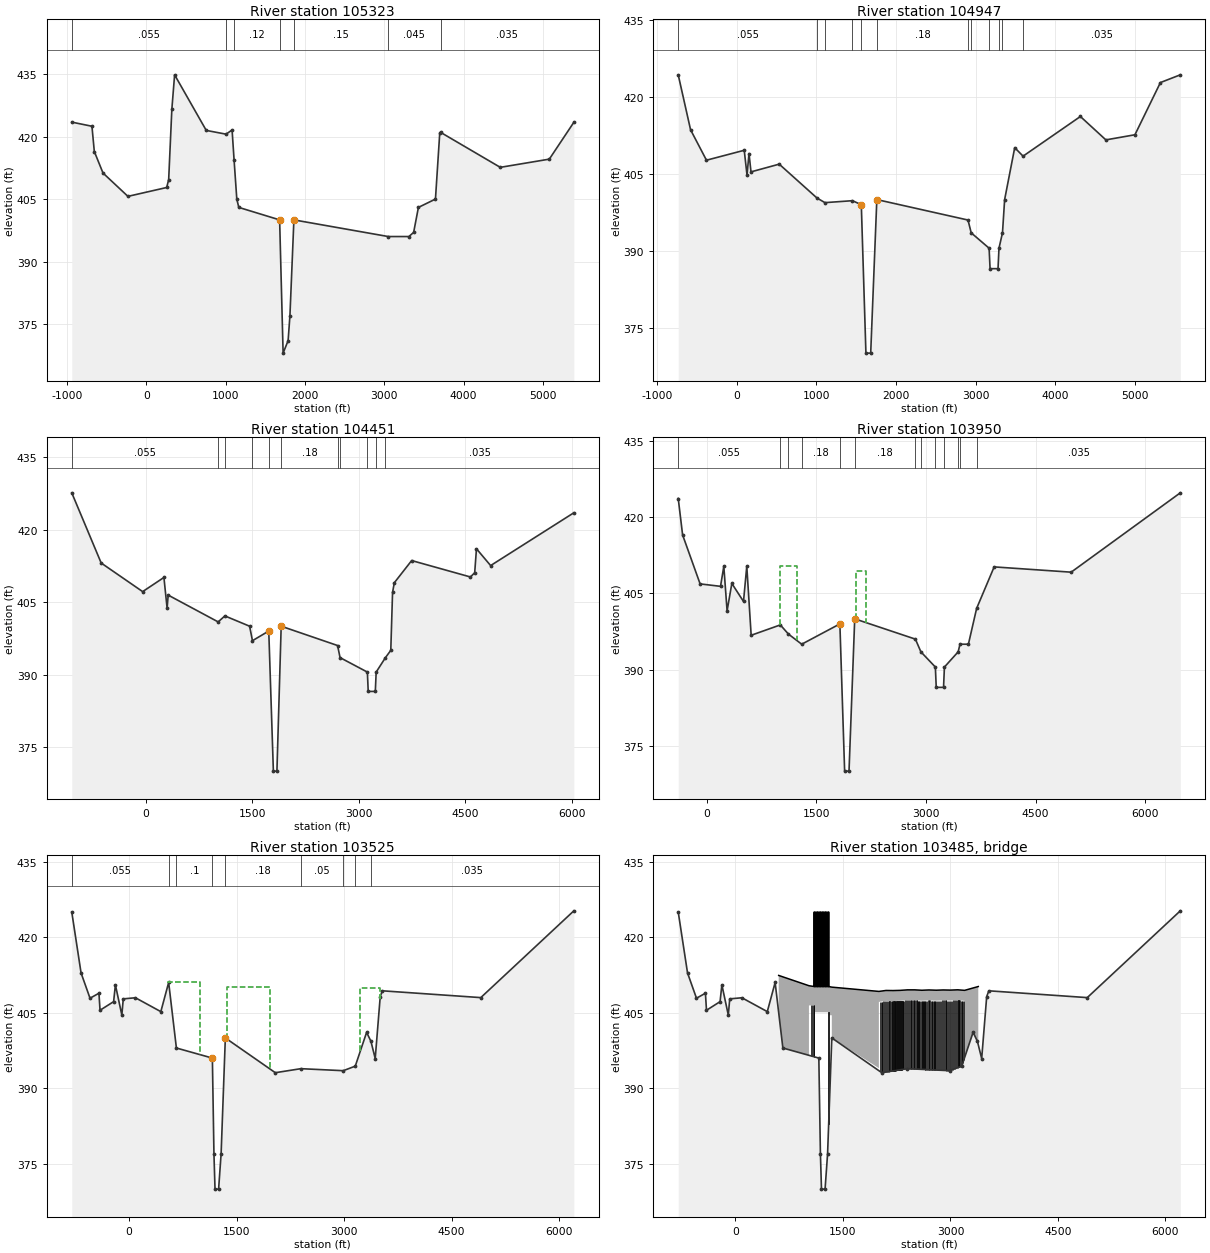
Type RM Length L Ch R = 1 ,105323  ,371,376,371
BEGIN DESCRIPTION:
This cross section corresponds to cross section 105329 of the non-georeferenced CDC model which was the source of this model.
END DESCRIPTION:
XS GIS Cut Line= 5
2497610.953412376963307.519125162496810.204246436961539.38966914
2496786.953964836961488.050861052495485.697381026959152.43742205
2494677.763821916957702.28492949
#Sta/Elev= 30
    -941  423.48 -686.63  422.49  -656.7  416.42 -546.97  411.25 -232.74  405.65
  256.06  407.78  280.99  409.68   320.9  426.56  355.81  434.84  754.83  421.49
 1004.22  420.59 1080.57  421.59 1105.56  414.42    1140     405    1165     403
    1680     400    1724     368    1787     371    1810     377    1860     400
    3050     396    3310     396    3370     397    3430     403    3645     405
 3699.25   420.9 3709.25  421.03 4462.38  412.62 5080.81  414.59 5390.03  423.44
#Mann= 7 ,-1,0
    -941    .055       0 1004.22    .035       0 1105.56     .12       0
    1680     .05       0    1860     .15       0    3050    .045       0
 3709.25    .035       0
Bank Sta=1680,1860
XS Rating Curve= 0 ,0
Exp/Cntr=0.5,0.3

Type RM Length L Ch R = 1 ,104947  ,458,496,507
BEGIN DESCRIPTION:
This cross section corresponds to cross section 104960 of the non-georeferenced CDC model which was the source of this model.
END DESCRIPTION:
XS GIS Cut Line= 4
2497940.818556286962813.605106412497102.651824276961295.63523538
2495815.433926256958964.40695822 2494893.07836256957293.96609882
#Sta/Elev= 30
    -734  424.36 -579.22  413.64 -379.51  407.69   94.82  409.63  129.77  404.78
  154.73     409   179.7  405.41  534.19  406.92 1008.52   400.3 1108.44   399.4
 1453.18  399.78    1565     399    1623     370    1683     370    1760     400
    2905     396    2945   393.5    3170   390.5    3182   386.5    3282   386.5
    3294   390.5    3338   393.5    3365     400 3491.63  410.14 3596.55  408.48
 4316.38  416.23 4636.33  411.66 5001.27  412.66 5321.21  422.86 5571.17  424.37
#Mann= 12 ,-1,0
    -734    .055       0 1008.52    .035       0 1108.44     .12       0
 1453.18     .15       0    1565     .05       0    1760     .18       0
    2905    .035       0    2945    .045       0    3170    .025       0
    3294    .045       0    3338    .035       0 3596.55    .035       0
Bank Sta=1565,1760
XS Rating Curve= 0 ,0
Exp/Cntr=0.3,0.1

Type RM Length L Ch R = 1 ,104451  ,485,501,557
BEGIN DESCRIPTION:
This cross section corresponds to cross section 104446 of the non-georeferenced CDC model which was the source of this model.
END DESCRIPTION:
XS GIS Cut Line= 4
      2498417.52     6962930.227     2497488.694     6961087.646
     2496278.738     6958687.364     2494868.815     6956837.172
#Sta/Elev= 30
   -1047  427.61 -632.31  413.08  -47.75  407.16  252.02  410.09  296.99  403.72
  311.98  406.44 1016.44  400.89 1111.37  402.13    1460     400    1500     397
    1730     399    1795     370    1845     370    1905     400    2700     396
    2735   393.5    3120   390.5    3132   386.5    3232   386.5    3244   390.5
    3375   393.5    3450     395    3475     407    3500     409 3744.38  413.59
    4573  410.19  4632.9  411.07 4657.86  416.03 4857.52  412.55 6030.57  423.48
#Mann= 11 ,-1,0
   -1047    .055       0 1016.44    .035       0 1111.37     .12       0
    1500     .18       0    1730     .05       0    1905     .18       0
    2700    .035       0    2735    .045       0    3120    .025       0
    3244    .045       0    3375    .035       0
Bank Sta=1730,1905
XS Rating Curve= 0 ,0
Exp/Cntr=0.5,0.3

Type RM Length L Ch R = 1 ,103950  ,368,425,468
BEGIN DESCRIPTION:
This cross section corresponds to cross section 103960 of the non-georeferenced CDC model which was the source of this model.
END DESCRIPTION:
XS GIS Cut Line= 4
     2498472.582     6962182.447     2497907.944     6960916.173
      2496771.71     6958368.023     2494868.707     6956465.174
#Sta/Elev= 30
    -389   423.7 -329.15  416.52  -89.76  406.88  189.52   406.4  234.41  410.35
  279.29  401.57  344.13  406.97  503.72  403.42   548.6  410.38  608.45  396.76
 1007.46   398.8    1118     397    1300     395    1822     399    1887     370
    1947     370    2025     400    2855     396    2930   393.5    3128   390.5
    3140   386.5    3240   386.5    3252   390.5    3440   393.5    3465     395
    3580     395 3692.46  402.05 3932.25  410.23 4985.72  409.19 6478.55  424.82
#Mann= 13 ,-1,0
    -389    .055       0 1007.46    .035       0    1118     .12       0
    1300     .18       0    1822     .05       0    2025     .18       0
    2855    .035       0    2930    .045       0    3128    .025       0
    3252    .045       0    3440    .035       0    3465     .07       0
 3692.46    .035       0
#XS Ineff= 2 ,-1
    1000    1230   410.5    2040    2180   409.5
Permanent Ineff=
       F       F
Bank Sta=1822,2025
XS Rating Curve= 0 ,0
Exp/Cntr=0.3,0.1

Type RM Length L Ch R = 1 ,103525  ,80,80,80
BEGIN DESCRIPTION:
This cross section corresponds to cross section 103533 of the non-georeferenced CDC model which was the source of this model.
END DESCRIPTION:
XS GIS Cut Line= 6
     2498629.399     6962012.983     2498169.986     6960751.477
     2498152.041     6960702.201     2497945.705      6960070.38
     2497227.258     6958113.184     2495017.814     6956294.577
#Sta/Elev= 30
    -799  424.98 -669.24  412.89 -544.46  407.88 -419.69  408.87 -404.72  405.49
 -215.06   407.2 -190.11  410.53 -100.27  404.54  -80.31  407.75   89.38  407.97
  443.74  405.22  553.09     411     661     398    1163     396    1185     377
    1200     370    1250     370    1285     377    1344     400  2041.5   393.1
  2398.2   393.9  2989.1   393.5  3156.9   394.4 3315.54  401.11  3375.5  399.34
 3435.43  395.91 3505.35   408.2 3535.32  409.35  4908.7     408 6207.18  425.22
#Mann= 9 ,-1,0
    -799    .055       0  553.09    .035       0     661      .1       0
    1163     .05       0    1344     .18       0  2398.2     .05       0
  2989.1     .18       0  3156.9      .1       0  3375.5    .035       0
#XS Ineff= 3 ,-1
     550     995     411    1374    1971   410.1    3227    3500     410
Permanent Ineff=
       F       F       F
Bank Sta=1163,1344
XS Rating Curve= 0 ,0
Exp/Cntr=0.5,0.3

Type RM Length L Ch R = 3 ,103485  ,,,
BEGIN DESCRIPTION:
103493  Burlington Northern Santa Fe Railroad
END DESCRIPTION:
Node Name=BNSF RR
Bridge Culvert--1,0,-1,-1, 0
Deck Dist Width WeirC Skew NumUp NumDn MinLoCord MaxHiCord MaxSubmerge Is_Ogee
30,20,2.6,0, 61, 61, , , 0.95, 0, 2.5,2.5,,
     603    1025    1025    1099    1099    1100    1100    1122    1122    1123
    1123    1144    1144    1145    1145    1166    1166    1167    1167    1188
    1188    1189    1189    1210    1210    1211    1211    1232    1232    1233
    1233    1254    1254    1255    1255    1276    1276    1277    1277    1299
    1299    1300    1300    1344    1344    2001    2001    2100    2200    2300
    2400    2500    2600    2700    2800    2900    3000    3100    3197    3197
    3388
   412.4  410.36  410.36   410.2     425     425   410.2   410.2     425     425
   410.2   410.2     425     425   410.2   410.2     425     425   410.2   410.2
     425     425   410.2   410.2     425     425   410.2   410.2     425     425
   410.2   410.2     425     425   410.2   410.2     425     425   410.2   410.2
     425     425   410.2  410.08  410.08  409.23  409.23  409.42   409.4  409.44
  409.54  409.54  409.46  409.52  409.47  409.52  409.49  409.55  409.44  409.44
   410.2
     390     390  406.45  406.45   405.1   405.1   405.1   405.1   405.1   405.1
   405.1   405.1   405.1   405.1   405.1   405.1   405.1   405.1   405.1   405.1
   405.1   405.1   405.1   405.1   405.1   405.1   405.1   405.1   405.1   405.1
   405.1   405.1   405.1   405.1   405.1   405.1   405.1   405.1   405.1   405.1
   405.1   405.1  404.52  404.49     394     394  407.15  407.34  407.32  407.36
  407.46  407.46  407.38  407.44  407.39  407.44  407.41  407.47  407.36     390
     390
     603    1025    1025    1099    1099    1100    1100    1122    1122    1123
    1123    1144    1144    1145    1145    1166    1166    1167    1167    1188
    1188    1189    1189    1210    1210    1211    1211    1232    1232    1233
    1233    1254    1254    1255    1255    1276    1276    1277    1277    1299
    1299    1300    1300    1344    1344    2001    2001    2100    2200    2300
    2400    2500    2600    2700    2800    2900    3000    3100    3197    3197
    3388
   412.4  410.36  410.36   410.2     425     425   410.2   410.2     425     425
   410.2   410.2     425     425   410.2   410.2     425     425   410.2   410.2
     425     425   410.2   410.2     425     425   410.2   410.2     425     425
   410.2   410.2     425     425   410.2   410.2     425     425   410.2   410.2
     425     425   410.2  410.08  410.08  409.23  409.23  409.42   409.4  409.44
  409.54  409.54  409.46  409.52  409.47  409.52  409.49  409.55  409.44  409.44
   410.2
     390     390  406.45  406.45   405.1   405.1   405.1   405.1   405.1   405.1
   405.1   405.1   405.1   405.1   405.1   405.1   405.1   405.1   405.1   405.1
   405.1   405.1   405.1   405.1   405.1   405.1   405.1   405.1   405.1   405.1
   405.1   405.1   405.1   405.1   405.1   405.1   405.1   405.1   405.1   405.1
   405.1   405.1  404.52  404.49     394     394  407.15  407.34  407.32  407.36
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Pier Skew, UpSta & Num, DnSta & Num=  ,1038, 2 ,1038, 2 , 0 , 0 , 0 ,,
       1       1
       0     407
       1       1
       0     407
Pier Skew, UpSta & Num, DnSta & Num=  ,1050.7, 2 ,1050.7, 2 , 0 , 0 , 0 ,,
       1       1
       0     407
       1       1
       0     407
Pier Skew, UpSta & Num, DnSta & Num=  ,1063.8, 2 ,1063.8, 2 , 0 , 0 , 0 ,,
       1       1
       0     407
       1       1
       0     407
Pier Skew, UpSta & Num, DnSta & Num=  ,1077, 2 ,1077, 2 , 0 , 0 , 0 ,,
       1       1
       0     407
       1       1
       0     407
Pier Skew, UpSta & Num, DnSta & Num=  ,1090.3, 2 ,1090.3, 2 , 0 , 0 , 0 ,,
       1       1
       0     407
       1       1
       0     407
Pier Skew, UpSta & Num, DnSta & Num=  ,1099, 2 ,1099, 2 , 0 , 0 , 0 ,,
       6       6
       0     407
       6       6
       0     407
Pier Skew, UpSta & Num, DnSta & Num=  ,1300, 2 ,1300, 2 , 0 , 0 , 0 ,,
       6       6
       0     407
       6       6
       0     407
Pier Skew, UpSta & Num, DnSta & Num=  ,2013.8, 2 ,2013.8, 2 , 0 , 0 , 0 ,,
       1       1
       0     500
       1       1
       0     500
Pier Skew, UpSta & Num, DnSta & Num=  ,2027.5, 2 ,2027.5, 2 , 0 , 0 , 0 ,,
       1       1
       0     500
       1       1
       0     500
Pier Skew, UpSta & Num, DnSta & Num=  ,2041.5, 2 ,2041.5, 2 , 0 , 0 , 0 ,,
       1       1
       0     500
       1       1
       0     500
Pier Skew, UpSta & Num, DnSta & Num=  ,2041.5, 2 ,2041.5, 2 , 0 , 0 , 0 ,,
       1       1
       0     500
       1       1
       0     500
Pier Skew, UpSta & Num, DnSta & Num=  ,2055.5, 2 ,2055.5, 2 , 0 , 0 , 0 ,,
       1       1
       0     500
       1       1
       0     500
Pier Skew, UpSta & Num, DnSta & Num=  ,2069.2, 2 ,2069.2, 2 , 0 , 0 , 0 ,,
       1       1
       0     500
       1       1
       0     500
Pier Skew, UpSta & Num, DnSta & Num=  ,2083.7, 2 ,2083.7, 2 , 0 , 0 , 0 ,,
       1       1
       0     500
       1       1
       0     500
Pier Skew, UpSta & Num, DnSta & Num=  ,2097.1, 2 ,2097.1, 2 , 0 , 0 , 0 ,,
       1       1
       0     500
       1       1
       0     500
Pier Skew, UpSta & Num, DnSta & Num=  ,2111.3, 2 ,2111.3, 2 , 0 , 0 , 0 ,,
       1       1
       0     500
       1       1
       0     500
Pier Skew, UpSta & Num, DnSta & Num=  ,2125.3, 2 ,2125.3, 2 , 0 , 0 , 0 ,,
       1       1
       0     500
       1       1
       0     500
Pier Skew, UpSta & Num, DnSta & Num=  ,2136, 2 ,2136, 2 , 0 , 0 , 0 ,,
       1       1
       0     500
       1       1
       0     500
Pier Skew, UpSta & Num, DnSta & Num=  ,2149.2, 2 ,2149.2, 2 , 0 , 0 , 0 ,,
       1       1
       0     500
       1       1
       0     500
Pier Skew, UpSta & Num, DnSta & Num=  ,2163.8, 2 ,2163.8, 2 , 0 , 0 , 0 ,,
       1       1
       0     500
       1       1
       0     500
Pier Skew, UpSta & Num, DnSta & Num=  ,2177.5, 2 ,2177.5, 2 , 0 , 0 , 0 ,,
       1       1
       0     500
       1       1
       0     500
Pier Skew, UpSta & Num, DnSta & Num=  ,2188.4, 2 ,2188.4, 2 , 0 , 0 , 0 ,,
       1       1
       0     500
       1       1
       0     500
Pier Skew, UpSta & Num, DnSta & Num=  ,2192.3, 2 ,2192.3, 2 , 0 , 0 , 0 ,,
       1       1
       0     500
       1       1
       0     500
Pier Skew, UpSta & Num, DnSta & Num=  ,2204.8, 2 ,2204.8, 2 , 0 , 0 , 0 ,,
       1       1
       0     500
       1       1
       0     500
Pier Skew, UpSta & Num, DnSta & Num=  ,2219.1, 2 ,2219.1, 2 , 0 , 0 , 0 ,,
       1       1
       0     500
       1       1
       0     500
Pier Skew, UpSta & Num, DnSta & Num=  ,2229.1, 2 ,2229.1, 2 , 0 , 0 , 0 ,,
       1       1
       0     500
       1       1
       0     500
Pier Skew, UpSta & Num, DnSta & Num=  ,2233.4, 2 ,2233.4, 2 , 0 , 0 , 0 ,,
       1       1
       0     500
       1       1
       0     500
Pier Skew, UpSta & Num, DnSta & Num=  ,2246.6, 2 ,2246.6, 2 , 0 , 0 , 0 ,,
       1       1
       0     500
       1       1
       0     500
Pier Skew, UpSta & Num, DnSta & Num=  ,2260.9, 2 ,2260.9, 2 , 0 , 0 , 0 ,,
       1       1
       0     500
       1       1
       0     500
Pier Skew, UpSta & Num, DnSta & Num=  ,2274.9, 2 ,2274.9, 2 , 0 , 0 , 0 ,,
       1       1
       0     500
       1       1
       0     500
Pier Skew, UpSta & Num, DnSta & Num=  ,2288.4, 2 ,2288.4, 2 , 0 , 0 , 0 ,,
       1       1
       0     500
       1       1
       0     500
Pier Skew, UpSta & Num, DnSta & Num=  ,2302.4, 2 ,2302.4, 2 , 0 , 0 , 0 ,,
       1       1
       0     500
       1       1
       0     500
Pier Skew, UpSta & Num, DnSta & Num=  ,2316.8, 2 ,2316.8, 2 , 0 , 0 , 0 ,,
       1       1
       0     500
       1       1
       0     500
Pier Skew, UpSta & Num, DnSta & Num=  ,2330.1, 2 ,2330.1, 2 , 0 , 0 , 0 ,,
       1       1
       0     500
       1       1
       0     500
Pier Skew, UpSta & Num, DnSta & Num=  ,2342.8, 2 ,2342.8, 2 , 0 , 0 , 0 ,,
       1       1
       0     500
       1       1
       0     500
Pier Skew, UpSta & Num, DnSta & Num=  ,2356.2, 2 ,2356.2, 2 , 0 , 0 , 0 ,,
       1       1
       0     500
       1       1
       0     500
Pier Skew, UpSta & Num, DnSta & Num=  ,2370.9, 2 ,2370.9, 2 , 0 , 0 , 0 ,,
       1       1
       0     500
       1       1
       0     500
Pier Skew, UpSta & Num, DnSta & Num=  ,2385, 2 ,2385, 2 , 0 , 0 , 0 ,,
       1       1
       0     500
       1       1
       0     500
Pier Skew, UpSta & Num, DnSta & Num=  ,2398.2, 2 ,2398.2, 2 , 0 , 0 , 0 ,,
       1       1
       0     500
       1       1
       0     500
Pier Skew, UpSta & Num, DnSta & Num=  ,2412.3, 2 ,2412.3, 2 , 0 , 0 , 0 ,,
       1       1
       0     500
       1       1
       0     500
Pier Skew, UpSta & Num, DnSta & Num=  ,2426.6, 2 ,2426.6, 2 , 0 , 0 , 0 ,,
       1       1
       0     500
       1       1
       0     500
Pier Skew, UpSta & Num, DnSta & Num=  ,2439.9, 2 ,2439.9, 2 , 0 , 0 , 0 ,,
       1       1
       0     500
       1       1
       0     500
Pier Skew, UpSta & Num, DnSta & Num=  ,2450.6, 2 ,2450.6, 2 , 0 , 0 , 0 ,,
       1       1
       0     500
       1       1
       0     500
Pier Skew, UpSta & Num, DnSta & Num=  ,2454.9, 2 ,2454.9, 2 , 0 , 0 , 0 ,,
       1       1
       0     500
       1       1
       0     500
Pier Skew, UpSta & Num, DnSta & Num=  ,2467.4, 2 ,2467.4, 2 , 0 , 0 , 0 ,,
       1       1
       0     500
       1       1
       0     500
Pier Skew, UpSta & Num, DnSta & Num=  ,2481, 2 ,2481, 2 , 0 , 0 , 0 ,,
       1       1
       0     500
       1       1
       0     500
Pier Skew, UpSta & Num, DnSta & Num=  ,2492, 2 ,2492, 2 , 0 , 0 , 0 ,,
       1       1
       0     500
       1       1
       0     500
Pier Skew, UpSta & Num, DnSta & Num=  ,2495.8, 2 ,2495.8, 2 , 0 , 0 , 0 ,,
       1       1
       0     500
       1       1
       0     500
Pier Skew, UpSta & Num, DnSta & Num=  ,2509.6, 2 ,2509.6, 2 , 0 , 0 , 0 ,,
       1       1
       0     500
       1       1
       0     500
Pier Skew, UpSta & Num, DnSta & Num=  ,2523, 2 ,2523, 2 , 0 , 0 , 0 ,,
       1       1
       0     500
       1       1
       0     500
Pier Skew, UpSta & Num, DnSta & Num=  ,2532.9, 2 ,2532.9, 2 , 0 , 0 , 0 ,,
       1       1
       0     500
       1       1
       0     500
Pier Skew, UpSta & Num, DnSta & Num=  ,2537.3, 2 ,2537.3, 2 , 0 , 0 , 0 ,,
       1       1
       0     500
       1       1
       0     500
Pier Skew, UpSta & Num, DnSta & Num=  ,2547.9, 2 ,2547.9, 2 , 0 , 0 , 0 ,,
       1       1
       0     500
       1       1
       0     500
Pier Skew, UpSta & Num, DnSta & Num=  ,2551.6, 2 ,2551.6, 2 , 0 , 0 , 0 ,,
       1       1
       0     500
       1       1
       0     500
Pier Skew, UpSta & Num, DnSta & Num=  ,2559.6, 2 ,2559.6, 2 , 0 , 0 , 0 ,,
       1       1
       0     500
       1       1
       0     500
Pier Skew, UpSta & Num, DnSta & Num=  ,2563.1, 2 ,2563.1, 2 , 0 , 0 , 0 ,,
       1       1
       0     500
       1       1
       0     500
Pier Skew, UpSta & Num, DnSta & Num=  ,2577.4, 2 ,2577.4, 2 , 0 , 0 , 0 ,,
       1       1
       0     500
       1       1
       0     500
Pier Skew, UpSta & Num, DnSta & Num=  ,2590.4, 2 ,2590.4, 2 , 0 , 0 , 0 ,,
       1       1
       0     500
       1       1
       0     500
Pier Skew, UpSta & Num, DnSta & Num=  ,2601.6, 2 ,2601.6, 2 , 0 , 0 , 0 ,,
       1       1
       0     500
       1       1
       0     500
Pier Skew, UpSta & Num, DnSta & Num=  ,2605.6, 2 ,2605.6, 2 , 0 , 0 , 0 ,,
       1       1
       0     500
       1       1
       0     500
Pier Skew, UpSta & Num, DnSta & Num=  ,2616, 2 ,2616, 2 , 0 , 0 , 0 ,,
       1       1
       0     500
       1       1
       0     500
Pier Skew, UpSta & Num, DnSta & Num=  ,2619.4, 2 ,2619.4, 2 , 0 , 0 , 0 ,,
       1       1
       0     500
       1       1
       0     500
Pier Skew, UpSta & Num, DnSta & Num=  ,2629.4, 2 ,2629.4, 2 , 0 , 0 , 0 ,,
       1       1
       0     500
       1       1
       0     500
Pier Skew, UpSta & Num, DnSta & Num=  ,2632.9, 2 ,2632.9, 2 , 0 , 0 , 0 ,,
       1       1
       0     500
       1       1
       0     500
Pier Skew, UpSta & Num, DnSta & Num=  ,2646.5, 2 ,2646.5, 2 , 0 , 0 , 0 ,,
       1       1
       0     500
       1       1
       0     500
Pier Skew, UpSta & Num, DnSta & Num=  ,2646.5, 2 ,2646.5, 2 , 0 , 0 , 0 ,,
       1       1
       0     500
       1       1
       0     500
Pier Skew, UpSta & Num, DnSta & Num=  ,2660.6, 2 ,2660.6, 2 , 0 , 0 , 0 ,,
       1       1
       0     500
       1       1
       0     500
Pier Skew, UpSta & Num, DnSta & Num=  ,2674.4, 2 ,2674.4, 2 , 0 , 0 , 0 ,,
       1       1
       0     500
       1       1
       0     500
Pier Skew, UpSta & Num, DnSta & Num=  ,2688.9, 2 ,2688.9, 2 , 0 , 0 , 0 ,,
       1       1
       0     500
       1       1
       0     500
Pier Skew, UpSta & Num, DnSta & Num=  ,2699.1, 2 ,2699.1, 2 , 0 , 0 , 0 ,,
       1       1
       0     500
       1       1
       0     500
Pier Skew, UpSta & Num, DnSta & Num=  ,2702.5, 2 ,2702.5, 2 , 0 , 0 , 0 ,,
       1       1
       0     500
       1       1
       0     500
Pier Skew, UpSta & Num, DnSta & Num=  ,2715.9, 2 ,2715.9, 2 , 0 , 0 , 0 ,,
       1       1
       0     500
       1       1
       0     500
Pier Skew, UpSta & Num, DnSta & Num=  ,2730.5, 2 ,2730.5, 2 , 0 , 0 , 0 ,,
       1       1
       0     500
       1       1
       0     500
Pier Skew, UpSta & Num, DnSta & Num=  ,2740.9, 2 ,2740.9, 2 , 0 , 0 , 0 ,,
       1       1
       0     500
       1       1
       0     500
Pier Skew, UpSta & Num, DnSta & Num=  ,2744.5, 2 ,2744.5, 2 , 0 , 0 , 0 ,,
       1       1
       0     500
       1       1
       0     500
Pier Skew, UpSta & Num, DnSta & Num=  ,2758.6, 2 ,2758.6, 2 , 0 , 0 , 0 ,,
       1       1
       0     500
       1       1
       0     500
Pier Skew, UpSta & Num, DnSta & Num=  ,2768.3, 2 ,2768.3, 2 , 0 , 0 , 0 ,,
       1       1
       0     500
       1       1
       0     500
Pier Skew, UpSta & Num, DnSta & Num=  ,2772.3, 2 ,2772.3, 2 , 0 , 0 , 0 ,,
       1       1
       0     500
       1       1
       0     500
Pier Skew, UpSta & Num, DnSta & Num=  ,2779.4, 2 ,2779.4, 2 , 0 , 0 , 0 ,,
       1       1
       0     500
       1       1
       0     500
Pier Skew, UpSta & Num, DnSta & Num=  ,2783, 2 ,2783, 2 , 0 , 0 , 0 ,,
       1       1
       0     500
       1       1
       0     500
Pier Skew, UpSta & Num, DnSta & Num=  ,2796.8, 2 ,2796.8, 2 , 0 , 0 , 0 ,,
       1       1
       0     500
       1       1
       0     500
Pier Skew, UpSta & Num, DnSta & Num=  ,2810.9, 2 ,2810.9, 2 , 0 , 0 , 0 ,,
       1       1
       0     500
       1       1
       0     500
Pier Skew, UpSta & Num, DnSta & Num=  ,2824.7, 2 ,2824.7, 2 , 0 , 0 , 0 ,,
       1       1
       0     500
       1       1
       0     500
Pier Skew, UpSta & Num, DnSta & Num=  ,2838.4, 2 ,2838.4, 2 , 0 , 0 , 0 ,,
       1       1
       0     500
       1       1
       0     500
Pier Skew, UpSta & Num, DnSta & Num=  ,2852.5, 2 ,2852.5, 2 , 0 , 0 , 0 ,,
       1       1
       0     500
       1       1
       0     500
Pier Skew, UpSta & Num, DnSta & Num=  ,2866.1, 2 ,2866.1, 2 , 0 , 0 , 0 ,,
       1       1
       0     500
       1       1
       0     500
Pier Skew, UpSta & Num, DnSta & Num=  ,2879.7, 2 ,2879.7, 2 , 0 , 0 , 0 ,,
       1       1
       0     500
       1       1
       0     500
Pier Skew, UpSta & Num, DnSta & Num=  ,2894.7, 2 ,2894.7, 2 , 0 , 0 , 0 ,,
       1       1
       0     500
       1       1
       0     500
Pier Skew, UpSta & Num, DnSta & Num=  ,2907.2, 2 ,2907.2, 2 , 0 , 0 , 0 ,,
       1       1
       0     500
       1       1
       0     500
Pier Skew, UpSta & Num, DnSta & Num=  ,2921.7, 2 ,2921.7, 2 , 0 , 0 , 0 ,,
       1       1
       0     500
       1       1
       0     500
Pier Skew, UpSta & Num, DnSta & Num=  ,2932.1, 2 ,2932.1, 2 , 0 , 0 , 0 ,,
       1       1
       0     500
       1       1
       0     500
Pier Skew, UpSta & Num, DnSta & Num=  ,2936.3, 2 ,2936.3, 2 , 0 , 0 , 0 ,,
       1       1
       0     500
       1       1
       0     500
Pier Skew, UpSta & Num, DnSta & Num=  ,2948.8, 2 ,2948.8, 2 , 0 , 0 , 0 ,,
       1       1
       0     500
       1       1
       0     500
Pier Skew, UpSta & Num, DnSta & Num=  ,2963.2, 2 ,2963.2, 2 , 0 , 0 , 0 ,,
       1       1
       0     500
       1       1
       0     500
Pier Skew, UpSta & Num, DnSta & Num=  ,2976.8, 2 ,2976.8, 2 , 0 , 0 , 0 ,,
       1       1
       0     500
       1       1
       0     500
Pier Skew, UpSta & Num, DnSta & Num=  ,2989.1, 2 ,2989.1, 2 , 0 , 0 , 0 ,,
       1       1
       0     500
       1       1
       0     500
Pier Skew, UpSta & Num, DnSta & Num=  ,3002.9, 2 ,3002.9, 2 , 0 , 0 , 0 ,,
       1       1
       0     500
       1       1
       0     500
Pier Skew, UpSta & Num, DnSta & Num=  ,3017.3, 2 ,3017.3, 2 , 0 , 0 , 0 ,,
       1       1
       0     500
       1       1
       0     500
Pier Skew, UpSta & Num, DnSta & Num=  ,3031.3, 2 ,3031.3, 2 , 0 , 0 , 0 ,,
       1       1
       0     500
       1       1
       0     500
Pier Skew, UpSta & Num, DnSta & Num=  ,3045.2, 2 ,3045.2, 2 , 0 , 0 , 0 ,,
       1       1
       0     500
       1       1
       0     500
Pier Skew, UpSta & Num, DnSta & Num=  ,3058.8, 2 ,3058.8, 2 , 0 , 0 , 0 ,,
       1       1
       0     500
       1       1
       0     500
Pier Skew, UpSta & Num, DnSta & Num=  ,3073.1, 2 ,3073.1, 2 , 0 , 0 , 0 ,,
       1       1
       0     500
       1       1
       0     500
Pier Skew, UpSta & Num, DnSta & Num=  ,3087.2, 2 ,3087.2, 2 , 0 , 0 , 0 ,,
       1       1
       0     500
       1       1
       0     500
Pier Skew, UpSta & Num, DnSta & Num=  ,3101, 2 ,3101, 2 , 0 , 0 , 0 ,,
       1       1
       0     500
       1       1
       0     500
Pier Skew, UpSta & Num, DnSta & Num=  ,3111.5, 2 ,3111.5, 2 , 0 , 0 , 0 ,,
       1       1
       0     500
       1       1
       0     500
Pier Skew, UpSta & Num, DnSta & Num=  ,3115.2, 2 ,3115.2, 2 , 0 , 0 , 0 ,,
       1       1
       0     500
       1       1
       0     500
Pier Skew, UpSta & Num, DnSta & Num=  ,3128.4, 2 ,3128.4, 2 , 0 , 0 , 0 ,,
       1       1
       0     500
       1       1
       0     500
Pier Skew, UpSta & Num, DnSta & Num=  ,3142.5, 2 ,3142.5, 2 , 0 , 0 , 0 ,,
       1       1
       0     500
       1       1
       0     500
Pier Skew, UpSta & Num, DnSta & Num=  ,3156.9, 2 ,3156.9, 2 , 0 , 0 , 0 ,,
       1       1
       0     500
       1       1
       0     500
Pier Skew, UpSta & Num, DnSta & Num=  ,3166.6, 2 ,3166.6, 2 , 0 , 0 , 0 ,,
       1       1
       0     500
       1       1
       0     500
Pier Skew, UpSta & Num, DnSta & Num=  ,3170.3, 2 ,3170.3, 2 , 0 , 0 , 0 ,,
       1       1
       0     500
       1       1
       0     500
Pier Skew, UpSta & Num, DnSta & Num=  ,3184, 2 ,3184, 2 , 0 , 0 , 0 ,,
       1       1
       0     500
       1       1
       0     500
Abutment Skew #Up #Dn= , 2 , 2
    1025    1055
     405     395
    1025    1055
     405     395
Abutment Skew #Up #Dn= , 2 , 2
    1328    1344
     395     403
    1328    1344
     395     403
Abutment Skew #Up #Dn= , 2 , 2
    2001    2020
     402     395
    2001    2020
     402     395
Abutment Skew #Up #Dn= , 2 , 2
    3170    3197
     395     404
    3170    3197
     395     404
BR Coef= 1 , 1 , 1 ,2.5, 0 ,,,0.8,0,1.2,1,
WSPro=,,,, 1 ,,,, 0 ,,,, 0 ,,,,-1 ,-1 ,-1 , 0 , 0 , 0 , 0 , 0
BC Design=,, 0 ,, 0 ,,,,,,
BC HTab HWMax=424.1
BC Use User HTab Curves=0
BC User HTab FreeFlow(D)= 0

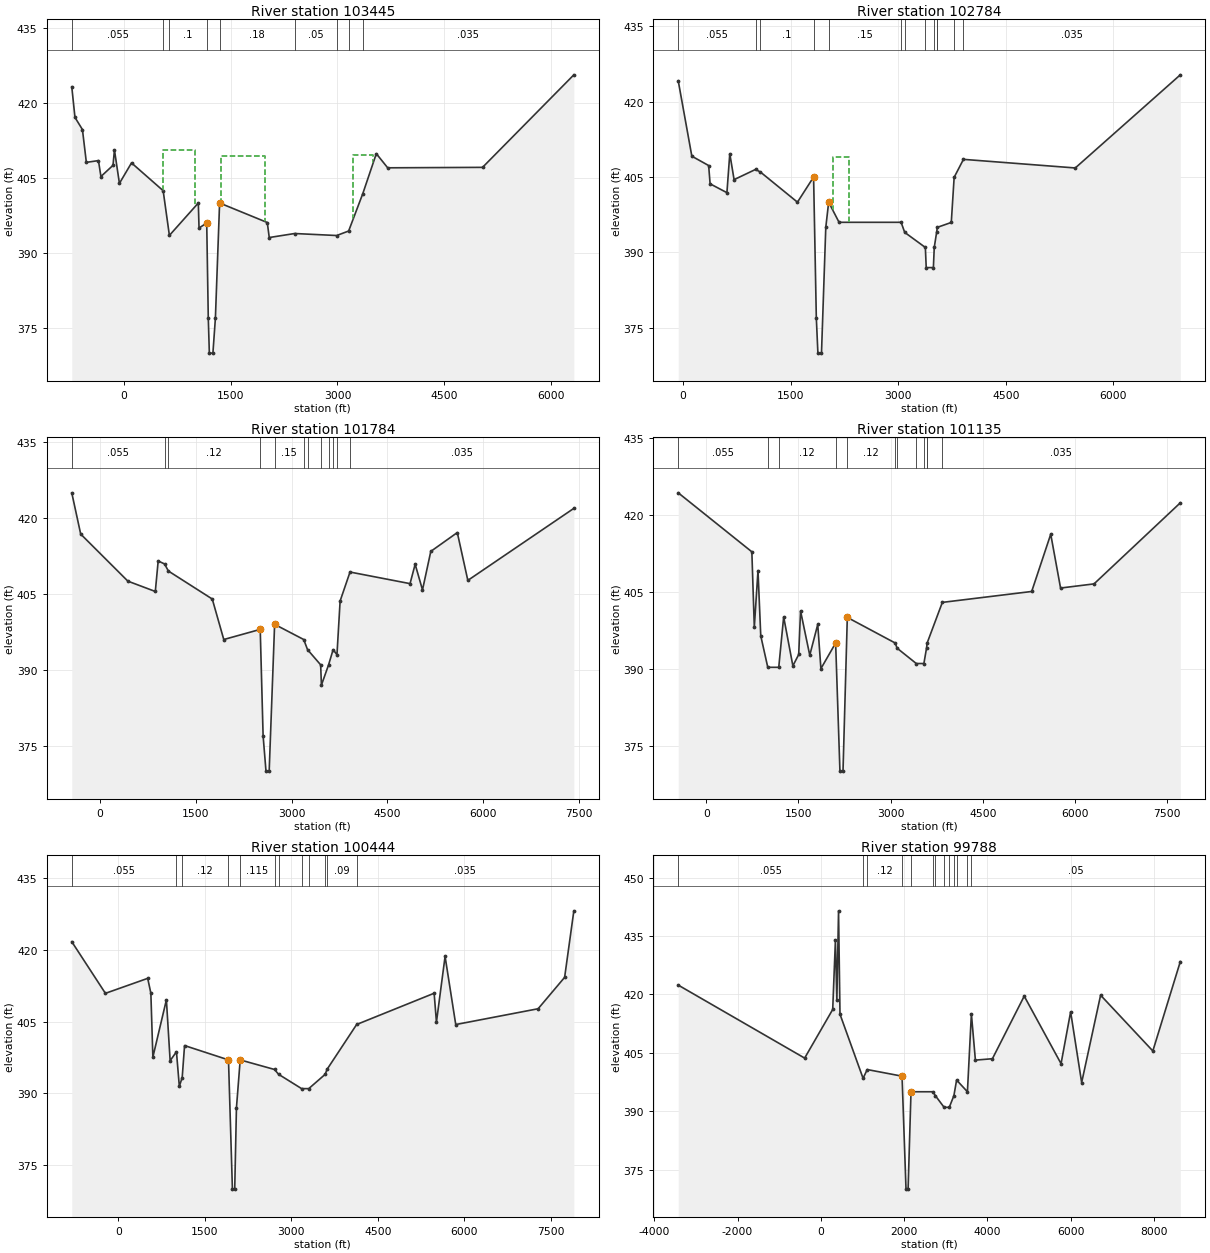
Type RM Length L Ch R = 1 ,103445  ,719,661,425
BEGIN DESCRIPTION:
This cross section corresponds to cross section 103453 of the non-georeferenced CDC model which was the source of this model.
END DESCRIPTION:
XS GIS Cut Line= 6
     2498683.557     6961954.457      2498248.78     6960740.998
     2498232.667     6960696.026      2498025.46     6960068.354
     2497274.505     6958009.815     2495062.379     6956188.999
#Sta/Elev= 30
    -733  423.23 -688.03   417.1 -583.12  414.67 -528.16  408.12 -358.29  408.47
 -323.32  405.29 -153.45  407.53 -133.47   410.6  -63.52  403.92  106.35  408.01
     551  402.46  638.56  393.52    1045     400    1055     395    1163     396
    1185     377    1200     370    1250     370    1285     377    1344     400
  2013.8   396.1  2041.5   393.1  2398.2   393.9  2989.1   393.5  3156.9   394.4
 3356.13  401.88 3545.81  409.86 3705.54  407.03 5038.25  407.12 6321.06  425.61
#Mann= 9 ,-1,0
    -733    .055       0     551    .035       0  638.56      .1       0
    1163     .05       0    1344     .18       0  2398.2     .05       0
  2989.1     .18       0  3156.9      .1       0 3356.13    .035       0
#XS Ineff= 3 ,-1
     550    1005   410.5    1364    1981   409.3    3217    3500   409.5
Permanent Ineff=
       F       F       F
Bank Sta=1163,1344
XS Rating Curve= 0 ,0
Exp/Cntr=0.5,0.3

Type RM Length L Ch R = 1 ,102784  ,650,1000,450
BEGIN DESCRIPTION:
This cross section corresponds to cross section 102800 of the non-georeferenced CDC model which was the source of this model.
END DESCRIPTION:
XS GIS Cut Line= 6
     2499376.889     6961409.065     2498927.311     6960445.812
     2498583.981     6959710.203     2498418.534     6959581.046
     2497429.134     6957893.363     2495145.084     6956013.347
#Sta/Elev= 30
     -67  424.12  122.64  409.14   357.2  407.28  377.17  403.65  611.72  401.89
  651.65  409.64  711.54  404.48 1010.94  406.51    1078     406    1595     400
    1820     405    1858     377    1880     370    1930     370    1990     395
    2030     400    2175     396    3040     396    3090     394    3378     391
    3390     387    3490     387    3502     391    3535     394    3545     395
 3739.45  395.97 3779.38  404.94 3909.14  408.51 5468.13   406.8 6932.26  425.31
#Mann= 13 ,-1,0
     -67    .055       0 1010.94    .035       0    1078      .1       0
    1820     .05       0    2030     .15       0    3040    .035       0
    3090    .045       0    3378    .025       0    3502    .045       0
    3535    .035       0    3545     .18       0 3779.38      .1       0
 3909.14    .035       0
#XS Ineff= 1 ,-1
    2090    2310     409
Permanent Ineff=
       F
Bank Sta=1820,2030
XS Rating Curve= 0 ,0
Exp/Cntr=0.3,0.1

Type RM Length L Ch R = 1 ,101784  ,470,649,490
BEGIN DESCRIPTION:
This cross section corresponds to cross section 101800 of the non-georeferenced CDC model which was the source of this model.
END DESCRIPTION:
XS GIS Cut Line= 6
     2500365.418     6961179.017      2499500.35     6960001.736
     2498602.051     6958779.231     2498416.973     6958651.489
     2497694.165     6957646.337     2495061.087     6955479.034
#Sta/Elev= 30
    -437  424.98 -297.39  416.83  440.56  407.53  869.36  405.49  914.24  411.52
 1013.96  410.93 1073.84  409.53    1760     404    1940     396    2510     398
    2555     377    2600     370    2650     370    2735     399    3190     396
    3250     394    3455     391    3467     387    3579     391    3650     394
    3710     393 3759.32  403.61 3914.08  409.33 4852.78  407.04 4932.67  410.87
 5047.51   405.8 5177.33  413.41 5591.76  417.13 5756.54  407.68 7414.27  421.91
#Mann= 12 ,-1,0
    -437    .055       0 1013.96    .035       0 1073.84     .12       0
    2510     .05       0    2735     .15       0    3190    .035       0
    3250    .045       0    3455    .025       0    3579    .045       0
    3650    .035       0    3710      .1       0 3914.08    .035       0
Bank Sta=2510,2735
XS Rating Curve= 0 ,0
Exp/Cntr=0.3,0.1

Type RM Length L Ch R = 1 ,101135  ,666,691,575
BEGIN DESCRIPTION:
This cross section corresponds to cross section 101138 of the non-georeferenced CDC model which was the source of this model.
END DESCRIPTION:
XS GIS Cut Line= 5
     2500897.395     6960659.699     2499940.766      6959592.11
     2499885.148     6959530.041     2498024.872     6957392.517
     2495071.834     6954961.852
#Sta/Elev= 30
    -458  424.31  740.73   412.8  780.69  398.08  840.63  409.14  885.58  396.41
    1000  390.26 1178.77  390.26 1258.73  400.09 1408.66  390.54 1503.62  392.76
  1533.6  401.26 1683.53  392.62 1813.47  398.62    1865     390    2105     395
    2175     370    2225     370    2295     400    3075     395    3105     394
    3418     391    3542     391    3585     394    3595     395 3842.47  402.93
 5297.37  405.06 5607.35  416.23 5767.35  405.73 6312.32  406.54 7717.25  422.36
#Mann= 12 ,-1,0
    -458    .055       0    1000    .035       0 1178.77     .12       0
    2105     .05       0    2295     .12       0    3075    .035       0
    3105    .045       0    3418    .025       0    3542    .045       0
    3585    .035       0    3595     .12       0 3842.47    .035       0
Bank Sta=2105,2295
XS Rating Curve= 0 ,0
Exp/Cntr=0.5,0.3

Type RM Length L Ch R = 1 ,100444  ,668,656,593
BEGIN DESCRIPTION:
This cross section corresponds to cross section 100453 of the non-georeferenced CDC model which was the source of this model.
END DESCRIPTION:
XS GIS Cut Line= 6
2501613.253074696960409.431191942500392.66394502 6959078.3420978
2499777.05395576 6958407.00092082499625.413511016958269.17934605
2498047.089567936956970.050710722495158.359485286954592.31831519
#Sta/Elev= 30
    -806   421.7  -222.4  410.91  510.84  414.04  565.71  410.94  600.62  397.58
  835.06  409.55   899.9  396.84 1009.63   398.7  1059.4  391.46 1109.18  393.32
    1150     400    1912     397    1980     370    2020     370    2050     387
    2115     397    2710     395    2780     394    3180     391    3304     391
    3590     394    3620     395 4134.65   404.4  5478.5  410.93 5518.47   404.9
 5668.34  418.62 5853.18  404.39 7281.94  407.69 7741.56  414.25 7901.44  428.15
#Mann= 12 ,-1,0
    -806    .055       0 1009.63    .035       0 1109.18     .12       0
    1912     .05       0    2115    .115       0    2710    .035       0
    2780    .045       0    3180    .025       0    3304    .045       0
    3590    .035       0    3620     .09       0 4134.65    .035       0
Bank Sta=1912,2115
XS Rating Curve= 0 ,0
Exp/Cntr=0.3,0.1

Type RM Length L Ch R = 1 ,99788   ,525,645,520
BEGIN DESCRIPTION:
This cross section corresponds to cross section 99800 of the non-georeferenced CDC model which was the source of this model.
END DESCRIPTION:
XS GIS Cut Line= 6
     2502725.591     6962190.787     2502675.486      6960209.14
     2500863.027     6958536.192        2499592.        6957363.
     2498129.923     6956042.248      2495229.41       6953422.1
#Sta/Elev= 30
   -3425  422.38 -389.21  403.64  284.84  416.13  349.75  433.93   384.7  418.57
  424.64  441.45   459.6   414.9 1013.83  398.45 1113.79   400.7    1950     399
    2045     370    2095     370    2165     395    2690     395    2750     394
    2960     391    3084     391    3195     394    3260     398    3520     395
    3615     415 3711.18  403.12  4120.2  403.48  4883.7  419.55 5768.39  402.21
 5998.31  415.51 6263.22  397.36 6718.05  419.79 7972.61  405.47 8632.38  428.42
#Mann= 13 ,-1,0
   -3425    .055       0 1013.83    .035       0 1113.79     .12       0
    1950     .05       0    2165     .11       0    2690    .035       0
    2750    .045       0    2960    .025       0    3084    .045       0
    3195    .035       0    3260    .075       0    3520    .035       0
    3615     .05       0
Bank Sta=1950,2165
XS Rating Curve= 0 ,0
Exp/Cntr=0.3,0.1