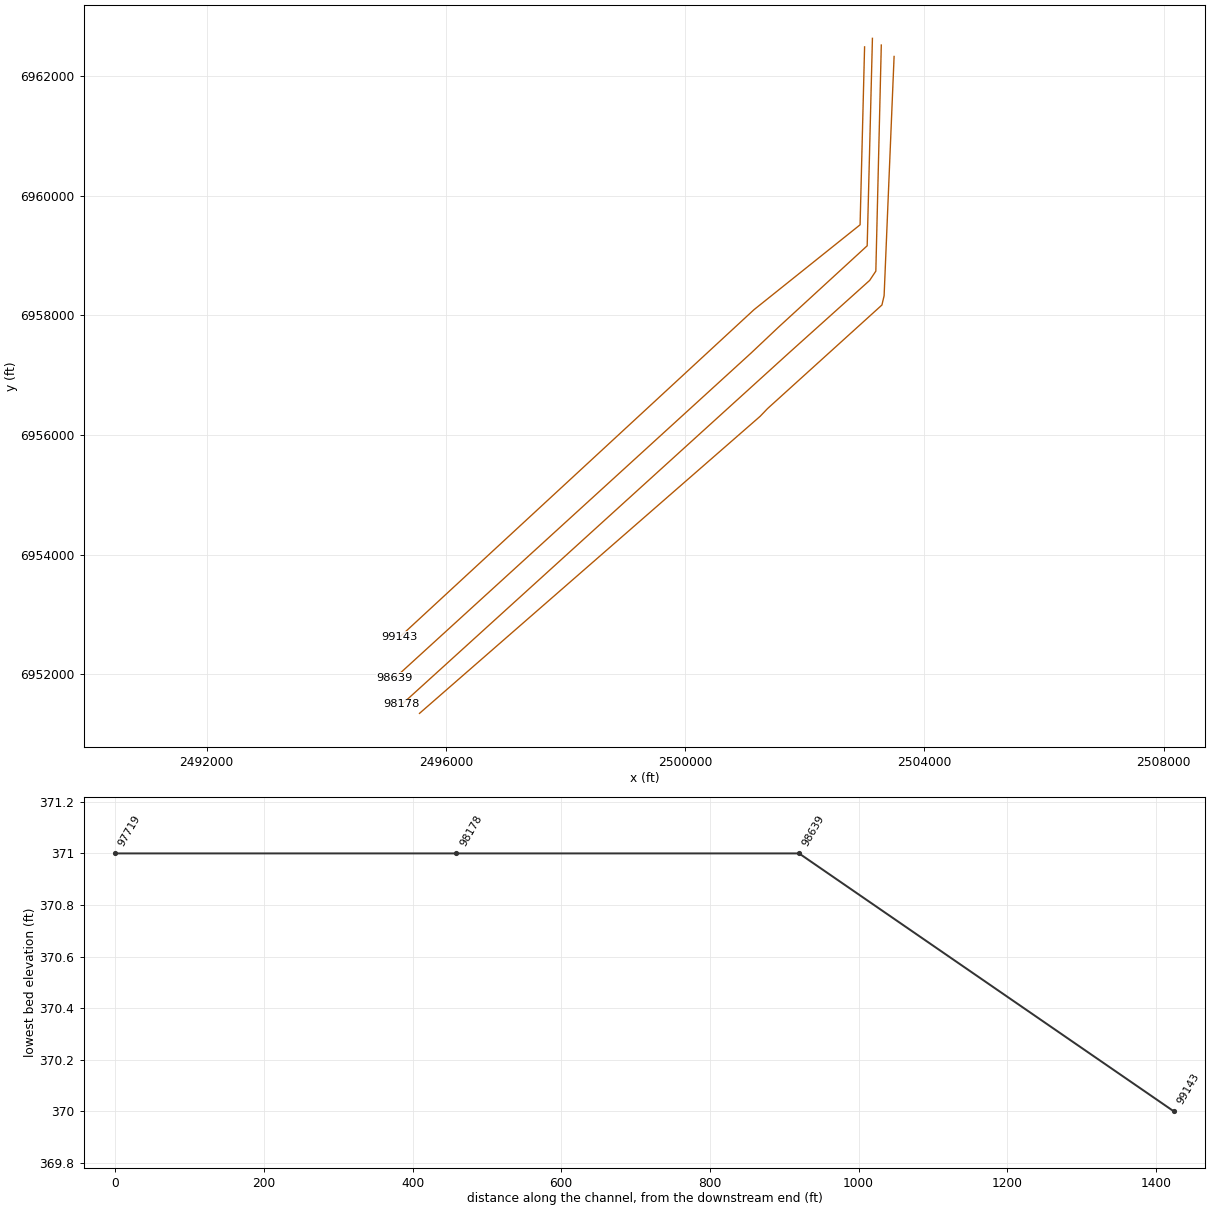
HEC-RAS study CDC_Consolidated_Model.prj: Upper Trinity CDC Consolidated Model

--- CDC_Consolidated_Model.g01 (geometry) --- (continued)

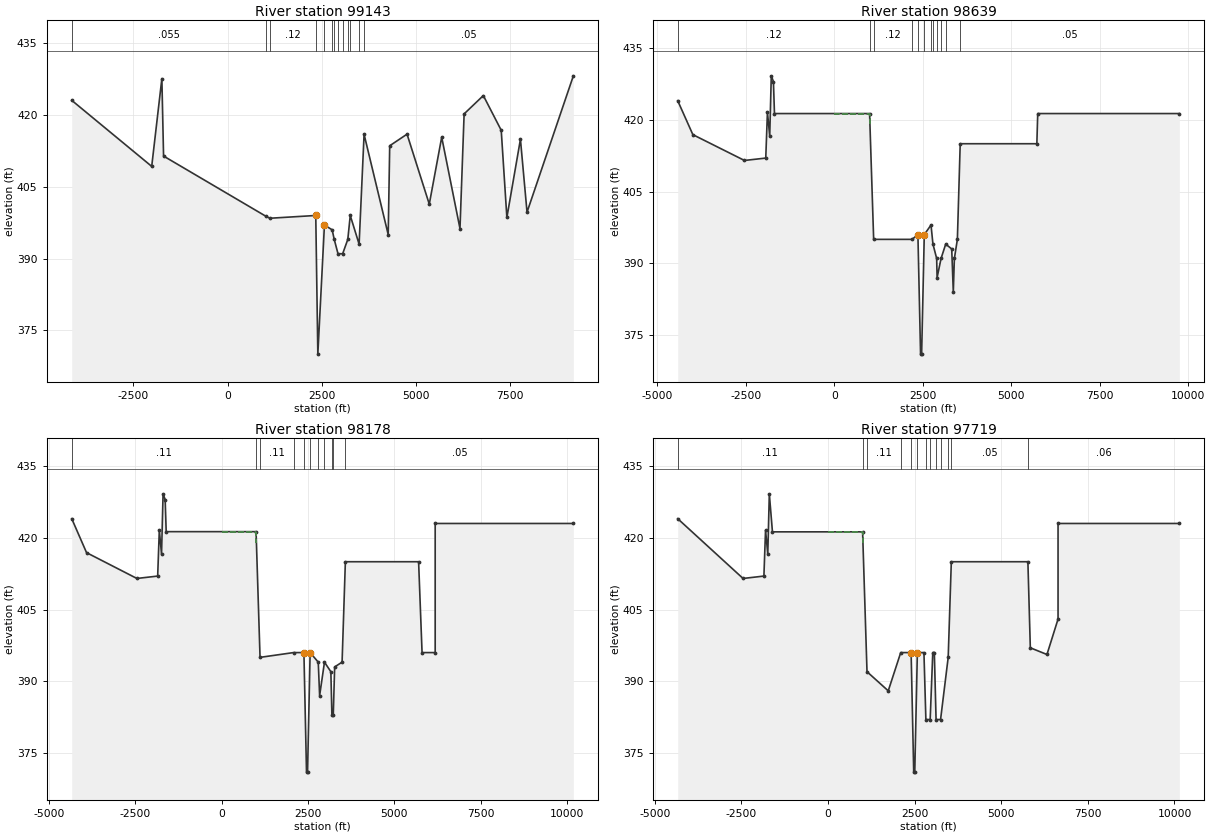
Type RM Length L Ch R = 1 ,99143   ,504,504,504
BEGIN DESCRIPTION:
This cross section corresponds to cross section 99167 of the non-georeferenced CDC model which was the source of this model.
END DESCRIPTION:
XS GIS Cut Line= 6
     2503000.309      6962489.31     2502925.109     6959515.174
     2501233.853     6958162.546     2501151.076     6958096.343
     2498106.956     6955284.563     2495229.134     6952626.388
#Sta/Elev= 30
   -4134  423.08-2012.51  409.27-1742.96  427.63-1698.03  411.43 1011.51  398.86
 1122.68  398.42    2340     399    2395     370    2570     397    2775     396
    2830     394    2930     391    3054     391    3190     394    3255     399
    3490     393 3622.07  415.97 4261.92  395.01 4301.91  413.58 4761.82  416.01
 5351.67  401.37 5681.48  415.37 6166.19  396.26 6276.13  420.25 6785.83  424.08
 7260.55  416.82 7410.46  398.58 7770.25  414.94 7945.15  399.69 9174.43  428.21
#Mann= 13 ,-1,0
   -4134    .055       0 1011.51    .035       0 1122.68     .12       0
    2340     .05       0    2570     .11       0    2775    .035       0
    2830    .045       0    2930    .025       0    3054    .045       0
    3190    .035       0    3255    .055       0    3490    .035       0
 3622.07     .05       0
Bank Sta=2340,2570
XS Rating Curve= 0 ,0
Exp/Cntr=0.3,0.1

Type RM Length L Ch R = 1 ,98639   ,426,461,426
BEGIN DESCRIPTION:
This cross section corresponds to cross section 98653 of the non-georeferenced CDC model which was the source of this model.
END DESCRIPTION:
XS GIS Cut Line= 6
2503131.473756076962631.840896292503043.805952436959164.58109856
2501557.483137676957801.134678472501104.000120766957373.00003605
2498102.618984436954636.207281312495146.912972046951941.06313519
#Sta/Elev= 30
 -4420.8     424 -3992.6   416.9   -2535   411.5 -1933.3     412   -1886   421.6
 -1821.5   416.6 -1777.1   429.2 -1716.7     428 -1687.2  421.31    1000  421.31
    1115     395    2200     395    2365     396    2440     371    2470     371
    2545     396    2735     398    2790     394    2895     391    2907     387
    3019     391    3150     394    3320     393    3365     384    3395     391
    3480     395    3560     415    5725     415    5750  421.31    9750  421.31
#Mann= 12 ,-1,0
 -4420.8     .12       0    1000    .035       0    1115     .12       0
    2200      .1       0    2365     .05       0    2545      .1       0
    2735    .035       0    2790    .045       0    2895    .025       0
    3019    .045       0    3150    .035       0    3560     .05       0
#XS Ineff= 2 , 0
       0    1010  421.31               0
Permanent Ineff=
       F       F
Bank Sta=2365,2545
XS Rating Curve= 0 ,0
Exp/Cntr=0.3,0.1

Type RM Length L Ch R = 1 ,98178   ,459,459,459
BEGIN DESCRIPTION:
This cross section corresponds to cross section 98188 of the non-georeferenced CDC model which was the source of this model.
END DESCRIPTION:
XS GIS Cut Line= 6
2503279.707383516962519.870319712503188.462487256958740.97728696
2503085.105738586958585.883108972501739.999833026957378.00002605
2498225.032125416954187.862377462495263.055077756951499.61165085
#Sta/Elev= 30
 -4335.8     424 -3907.6   416.9   -2450   411.5 -1848.3     412   -1801   421.6
 -1736.5   416.6 -1692.1   429.2 -1631.7     428 -1601.8  421.29    1000  421.29
    1115     395    2085     396    2385     396    2460     371    2490     371
    2565     396    2800     394    2840     387    2980     394    3165     392
    3195     383    3235     383    3275     393    3490     394    3585     415
    5705     415    5805     396    6185     396    6185     423   10185     423
#Mann= 11 ,-1,0
 -4335.8     .11       0    1000    .035       0    1115     .11       0
    2085    .035       0    2385     .05       0    2565    .035       0
    2800    .045       0    2980    .035       0    3195     .03       0
    3235    .035       0    3585     .05       0
#XS Ineff= 2 , 0
       0    1010  421.29    3585       0     415
Permanent Ineff=
       F       F
Bank Sta=2385,2565
XS Rating Curve= 0 ,0
Exp/Cntr=0.3,0.1

Type RM Length L Ch R = 1 ,97719   ,453,453,453
BEGIN DESCRIPTION:
This cross section corresponds to cross section 97730 of the non-georeferenced CDC model which was the source of this model.
END DESCRIPTION:
XS GIS Cut Line= 6
  2503493.8309716962329.053772212503326.771593846958329.73007797
2503290.253950336958174.746135972501378.919518416956444.58096114
2501253.823640026956314.080565962495558.926483836951349.54818465
#Sta/Elev= 30
 -4335.8     424   -2450   411.5 -1848.3     412   -1801   421.6 -1736.5   416.6
 -1692.1   429.2 -1601.8  421.25    1000  421.25    1127     392    1740     388
    2100     396    2400     396    2475     371    2505     371    2580     396
    2770     396    2826     382    2950     382    3025     396    3070     396
    3120     382    3250     382    3470     395    3560     415    5770     415
    5840     397    6320   395.6    6640     403    6640     423   10140     423
#Mann= 13 ,-1,0
 -4335.8     .11       0    1000    .035       0    1127     .11       0
    2100    .035       0    2400     .05       0    2580    .035       0
    2826     .03       0    2950    .045       0    3120     .03       0
    3250    .045       0    3470    .035       0    3560     .05       0
    5770     .06       0
#XS Ineff= 2 , 0
       0    1010  421.25    3560       0     415
Permanent Ineff=
       F       F
Bank Sta=2400,2580
XS Rating Curve= 0 ,0
Exp/Cntr=0.3,0.1