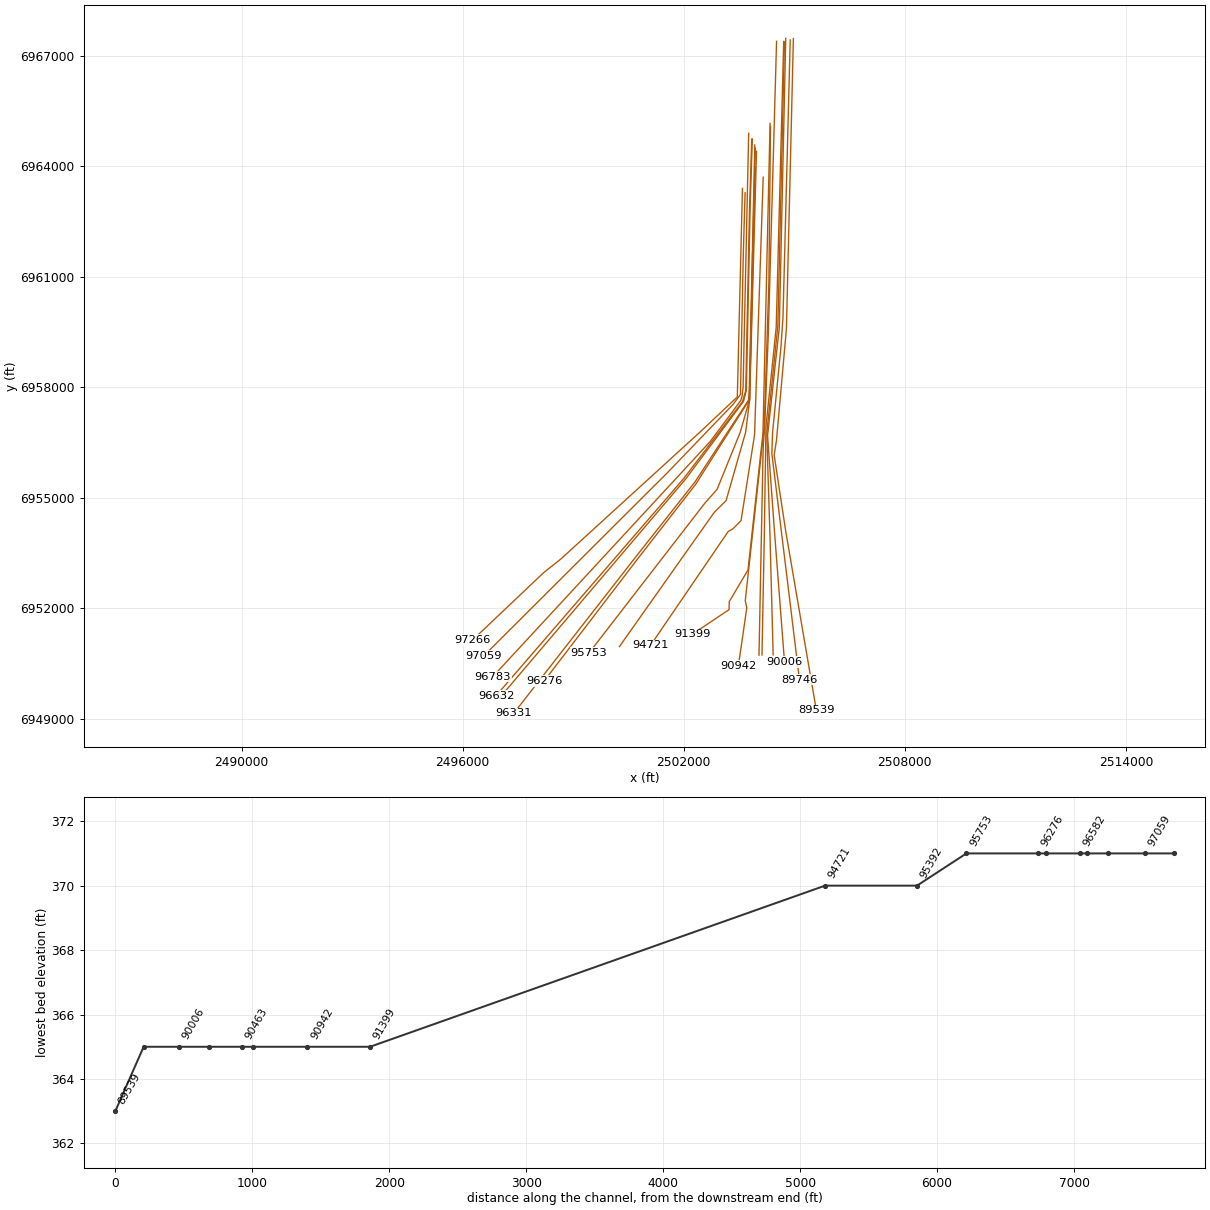
HEC-RAS study CDC_Consolidated_Model.prj: Upper Trinity CDC Consolidated Model

--- CDC_Consolidated_Model.g01 (geometry) --- (continued)

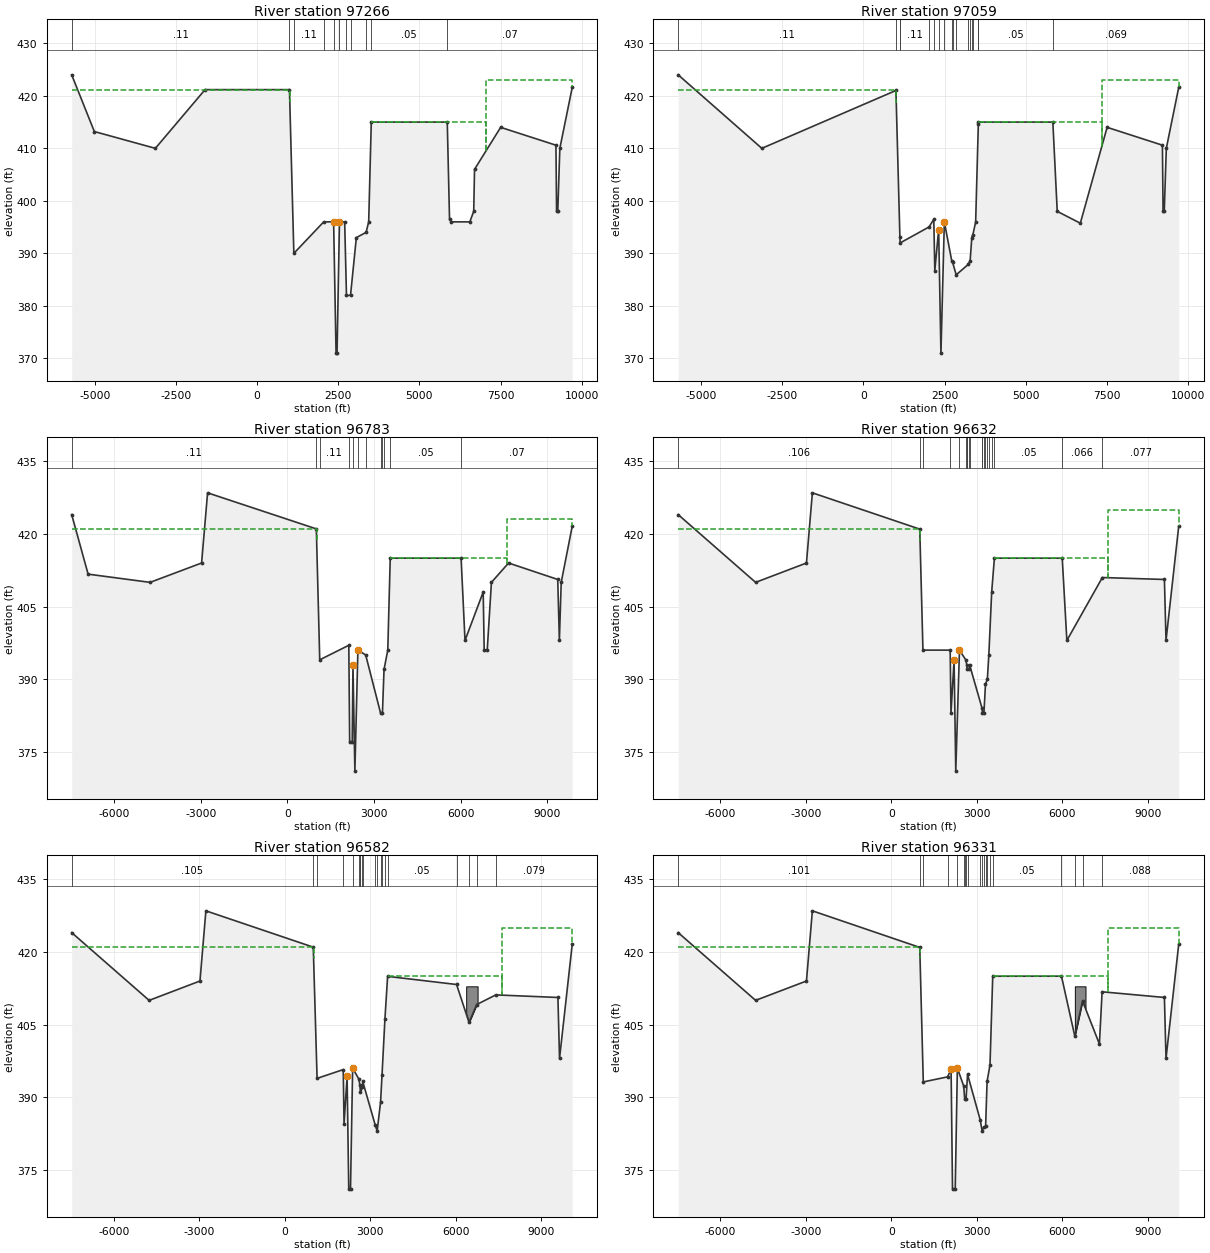
Type RM Length L Ch R = 1 ,97266   ,192,207,231
BEGIN DESCRIPTION:
97280  Interstate Highway 45
END DESCRIPTION:
XS GIS Cut Line= 6
2503592.941665176963399.714688632503453.373374766957739.80901371
2502459.073526086956803.52742171 2498661.00008556953338.00023206
2498206.081703996952979.208954892496270.172190016951144.20376663
#Sta/Elev= 30
 -5707.3     424 -5010.2   413.2 -3130.4     410   -1600  421.18    1000  421.18
    1135     390    2055     396    2360     396    2435     371    2465     371
    2540     396    2700     396    2756     382    2880     382    3060     393
    3360     394    3440     396    3520     415    5860     415    5930   396.5
    5990     396    6555     396    6675     398    6700     406  7504.1     414
    9207   410.6    9227     398  9263.5     398  9327.3     410  9708.9   421.6
#Mann= 11 ,-1,0
 -5707.3     .11       0    1000    .035       0    1135     .11       0
    2055    .035       0    2360     .05       0    2540    .035       0
    2756     .03       0    2880     .08       0    3360    .035       0
    3520     .05       0    5860     .07       0
#XS Ineff= 3 ,-1
-5707.63    1010  421.18    3520    7060     415    7060  9708.9     423
Permanent Ineff=
       F       F       F
Bank Sta=2360,2540
XS Rating Curve= 0 ,0
Exp/Cntr=0.3,0.1

Type RM Length L Ch R = 1 ,97059   ,256,276,307
BEGIN DESCRIPTION:
This cross section corresponds to cross section 97043 of the non-georeferenced CDC model which was the source of this model.
Interpolated cross-section.
Valley storage site set at elev. 398.0
END DESCRIPTION:
XS GIS Cut Line= 6
2503664.699395696963280.515780052503618.062349836961696.86343555
2503539.001156246957808.523443222503343.114080856957542.85009006
2501556.796459266955684.176313972496575.17978209 6950716.0792948
#Sta/Elev= 30
 -5707.3     424 -3130.4     410    1000  421.02 1122.33  393.04 1130.59  391.99
  2020.5  395.03 2166.25  396.49 2197.35  386.72 2315.53  394.53 2386.13     371
 2491.13     396 2722.55  388.46 2743.54  388.35 2855.39  385.91 3224.99  387.88
 3285.76  388.62 3337.17  393.02 3369.64  393.56 3455.35  395.95 3538.16  414.67
 3541.06     415 5833.22     415    5968     398 6679.26  395.74  7505.1     414
    9208   410.6    9228     398  9264.5     398  9328.3     410  9709.9   421.6
#Mann= 18 ,-1,0
 -5707.3     .11       0    1000    .035       0 1122.33    .108       0
 1130.59     .11       0  2020.5    .046       0 2166.25    .046       0
 2315.53     .05       0 2491.13    .035       0 2722.55    .053       0
 2743.54    .058       0 2855.39    .074       0 3224.99    .039       0
 3285.76    .061       0 3337.17    .036       0 3369.64    .036       0
 3538.16     .05       0 3541.06     .05       0 5833.22    .069       0
#XS Ineff= 3 ,-1
 -5707.3 1010.37  421.02 3541.06 7333.65     415 7333.65  9709.9     423
Permanent Ineff=
       F       F       F
Bank Sta=2315.53,2491.13
XS Rating Curve= 0 ,0
Exp/Cntr=0.3,0.1

Type RM Length L Ch R = 1 ,96783   ,142,151,166
BEGIN DESCRIPTION:
This cross section corresponds to cross section 96795 of the non-georeferenced CDC model which was the source of this model.
Valley storage site set at elev. 398.0
END DESCRIPTION:
XS GIS Cut Line= 6
2503762.070263926964895.099493132503609.511185826957989.04014255
2503582.772722246957761.765334642503548.151400426957643.06380038
2502717.860410096956529.663796222496819.159937176950149.87307814
#Sta/Elev= 30
 -7474.3     424 -6905.8   411.7   -4758     410 -2974.4     414   -2767   428.5
    1000  421.05    1118     394    2125     397    2155     377    2243     377
    2269     393    2335     371    2440     396    2710     395    3225     383
    3290     383    3345     392    3475     396    3560     415    6015     415
    6150     398    6780     408    6815     396    6920     396    7065     410
  7659.5     414  9362.4   410.6  9418.9     398  9482.7     410  9864.3   421.6
#Mann= 12 ,-1,0
 -7474.3     .11       0    1000    .035       0    1118     .11       0
    2125     .05       0    2269     .05       0    2440    .035       0
    2710     .08       0    3225     .03       0    3290     .08       0
    3345    .035       0    3560     .05       0    6015     .07       0
#XS Ineff= 3 ,-1
 -7474.3    1010   421.1    3560    7620     415    7620  9864.3     423
Permanent Ineff=
       F       F       F
Bank Sta=2269,2440
XS Rating Curve= 0 ,0
Exp/Cntr=0.3,0.1

Type RM Length L Ch R = 1 ,96632   ,47,50,55
BEGIN DESCRIPTION:
This cross section corresponds to cross section 96617 of the non-georeferenced CDC model which was the source of this model.
Interpolated cross-section.
Valley storage site set at elev. 398.0
END DESCRIPTION:
XS GIS Cut Line= 6
 2503845.88341656964736.677237792503785.267067916962844.38640296
2503682.659005436957913.329007882503593.552884436957611.08650213
2502000.415650766955527.412519892496904.831681856949629.13527447
#Sta/Elev= 30
 -7474.3     424   -4758     410 -2974.4     414   -2767   428.5    1000     421
    1112     396    2067     396    2095     383    2204     394    2263     371
    2393     396    2613     394    2648     393    2666     392    2738     392
    2746     393    3185     384    3199     383    3251     383    3306     389
    3372     390    3423     395    3523     408    3618     415    5998     415
    6160     398    7405     411  9581.8   410.6  9638.3     398 10083.7   421.6
#Mann= 20 ,-1,0
 -7474.3    .106       0    1000    .035       0    1112    .106       0
    2067    .052       0    2393    .058       0    2613    .062       0
    2648    .059       0    2666    .066       0    2738     .06       0
    2746    .075       0    3185    .031       0    3199    .037       0
    3251    .068       0    3306    .044       0    3372    .054       0
    3423     .04       0    3523    .047       0    3618     .05       0
    5998    .066       0    7405    .077       0
#XS Ineff= 3 ,-1
 -7474.3    1011     421    3618    7617     415    7617 10083.7     425
Permanent Ineff=
       F       F       F
Bank Sta=2204,2393
XS Rating Curve= 0 ,0
Exp/Cntr=0.3,0.1

Type RM Length L Ch R = 1 ,96582   ,237,251,276
BEGIN DESCRIPTION:
This cross section corresponds to cross section 96570 of the non-georeferenced CDC model which was the source of this model.
Interpolated cross-section.
Project fill pad set at elev. 412.9
END DESCRIPTION:
XS GIS Cut Line= 6
2503860.322035916964739.850787882503800.795252086962866.05958797
2503698.475574856957923.246310892503621.083669256957618.44409896
2502050.502164756955511.377775042497000.907605176949570.62587705
#Sta/Elev= 30
 -7474.3     424   -4758     410 -2974.4     414   -2767   428.5    1000  420.99
  1133.8  393.88 2051.65   395.7 2079.25   384.5 2186.68  394.28 2244.11     371
 2305.79     371 2380.79     396 2601.26  393.71 2635.49  392.43 2654.37  391.01
 2726.31  392.02 2734.21  393.25 3174.49  384.21 3240.63     383  3361.1     389
 3412.43  394.67 3513.22  406.12  3607.9  414.96 6026.58  413.28    6464  405.43
    6734  409.14 7403.55  411.13  9581.8   410.6  9638.3     398 10083.7   421.6
#Mann= 20 ,-1,0
 -7474.3    .105       0    1000    .035       0  1133.8    .105       0
 2051.65    .053       0 2380.79    .064       0 2601.26     .06       0
 2635.49    .054       0 2654.37     .06       0 2726.31    .056       0
 2734.21    .075       0 3174.49    .031       0 3240.63    .065       0
  3361.1    .058       0 3412.43    .039       0 3513.22    .046       0
  3607.9     .05       0 6026.58    .066       0    6464    .045       0
    6734    .066       0 7403.55    .079       0
#XS Ineff= 3 ,-1
 -7474.3 1010.84  420.99 3608.42 7616.01     415 7616.01 10083.7     425
Permanent Ineff=
       F       F       F
#Block Obstruct= 1 ,-1
    6364    6764   412.9
Bank Sta=2186.68,2380.79
XS Rating Curve= 0 ,0
Exp/Cntr=0.3,0.1

Type RM Length L Ch R = 1 ,96331   ,52,55,61
BEGIN DESCRIPTION:
This cross section corresponds to cross section 96333 of the non-georeferenced CDC model which was the source of this model.
Interpolated cross-section.
Project fill pad set at elev. 412.9
END DESCRIPTION:
XS GIS Cut Line= 6
2503927.899656686964577.079459882503778.208026926957972.07889038
2503760.089296766957655.85806613 2502301.93013966955428.83430497
2500702.207289166953404.962040382497385.182099076949152.96923205
#Sta/Elev= 30
 -7474.3     424   -4758     410 -2974.4     414   -2767   428.5    1000  420.94
 1123.95  393.15 1974.23  394.19 2099.32  395.72 2148.88     371 2244.21     371
 2319.21     396 2541.74  392.29 2576.66  389.57 2623.56  389.55 2676.45  394.71
 3121.49  385.28 3188.34     383 3244.06  383.85 3310.11  383.99    3362  393.28
 3463.88  396.64 3559.58  414.99 5970.98     415    6440  402.57    6710  409.86
 7301.65  400.99 7396.24  411.77  9581.8   410.6  9638.3     398 10083.7   421.6
#Mann= 20 ,-1,0
 -7474.3    .101       0    1000    .035       0 1123.95    .101       0
 1974.23    .056       0 2319.21    .094       0 2541.74    .047       0
 2576.66     .03       0 2623.56    .048       0 2676.45    .079       0
 3121.49    .031       0 3188.34    .048       0 3244.06    .059       0
 3310.11    .076       0    3362    .036       0 3463.88    .043       0
 3559.58     .05       0 5970.98    .061       0    6440    .045       0
    6710    .061       0 7396.24    .088       0
#XS Ineff= 3 ,-1
 -7474.3 1010.16  420.94 3559.66 7610.99     415 7610.99 10083.7     425
Permanent Ineff=
       F       F       F
#Block Obstruct= 1 ,-1
    6440    6814   412.9
Bank Sta=2099.32,2319.21
XS Rating Curve= 0 ,0
Exp/Cntr=0.3,0.1

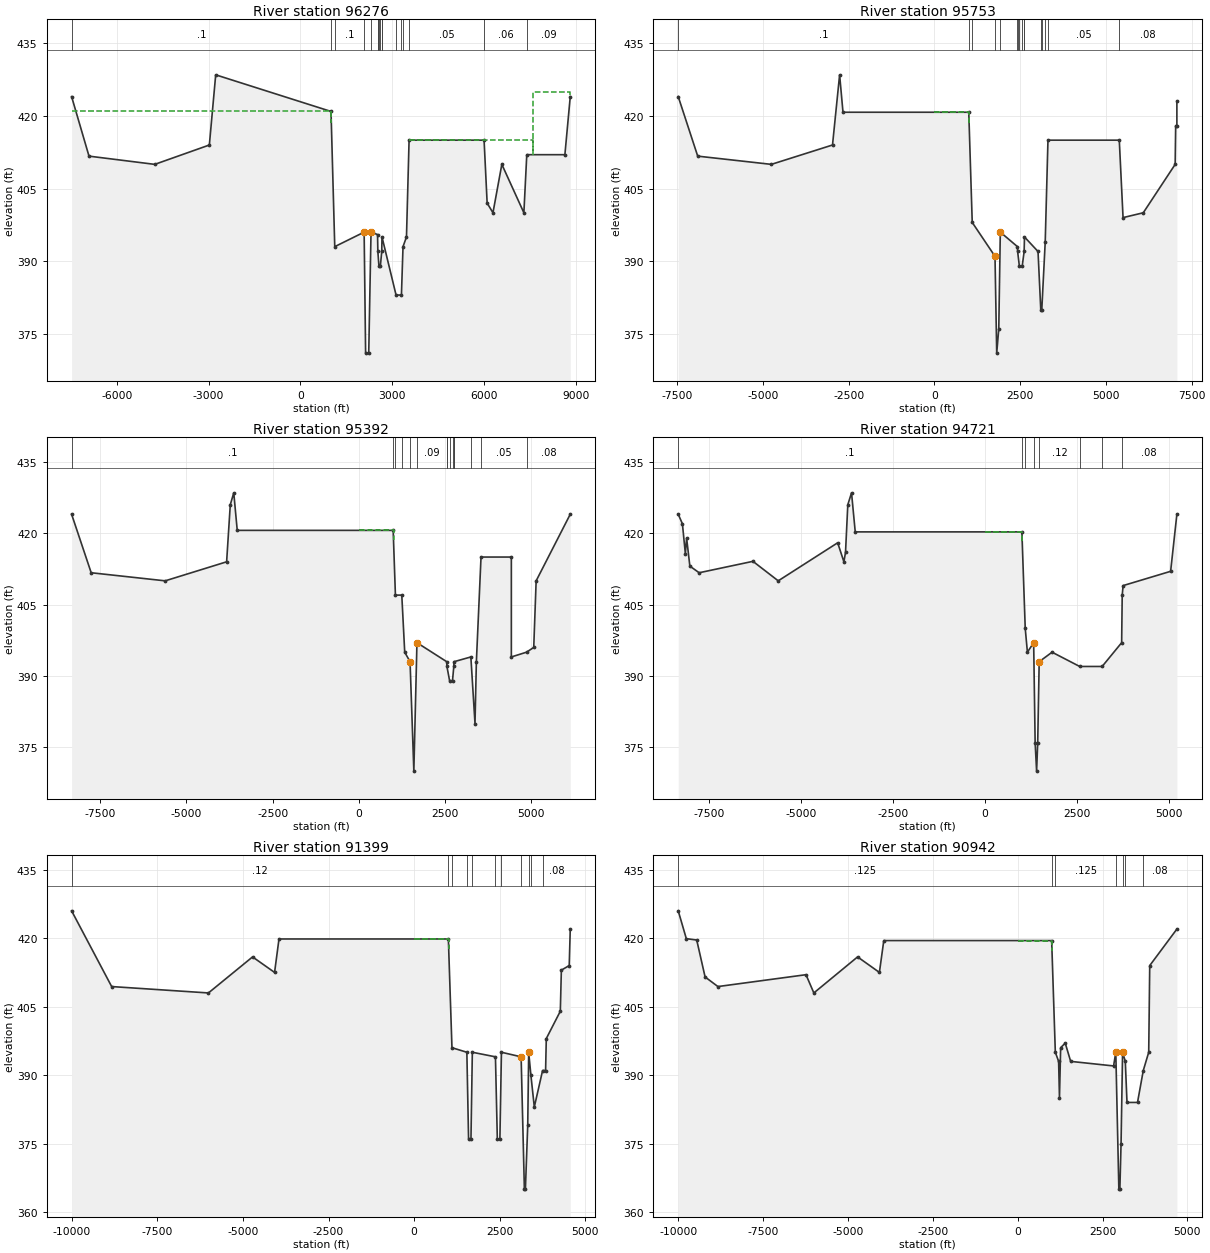
Type RM Length L Ch R = 1 ,96276   ,551,523,541
BEGIN DESCRIPTION:
This cross section corresponds to cross section 96286 of the non-georeferenced CDC model which was the source of this model.
---------------------------------------------------------------------
CDC DAL060603-1 Sargent Road Switching Station
Project located between cross-section 96286 - 97280
---------------------------------------------------------------------
END DESCRIPTION:
XS GIS Cut Line= 6
2503943.072854676964493.52385272  2503857.5428426961204.80306797
2503784.109589936957670.334743222502325.959619086955372.37017904
2500759.000154586953358.00019205 2498211.39698216950030.88873605
#Sta/Elev= 30
 -7474.3     424 -6905.8   411.7   -4758     410 -2974.4     414   -2767   428.5
    1000  420.93    1122     393    2082     396    2130     371    2232     371
    2307     396    2520   395.5    2530     392    2565     389    2612     389
    2657     392    2665     395    3125     383    3300     383    3352     393
    3465     395    3550     415    6000     415    6100     402    6290     400
    6580     410    7300     400    7395     412  8639.7     412    8815     424
#Mann= 17 ,-1,0
 -7474.3      .1       0    1000    .035       0    1122      .1       0
    2082     .05       0    2307      .1       0    2520    .035       0
    2530    .045       0    2565    .025       0    2612    .045       0
    2657    .035       0    2665     .08       0    3125     .03       0
    3300     .08       0    3352    .035       0    3550     .05       0
    6000     .06       0    7395     .09       0
#XS Ineff= 3 ,-1
 -7474.3    1010  420.93    3550    7610     415    7610    8815     425
Permanent Ineff=
       F       F       F
Bank Sta=2082,2307
XS Rating Curve= 0 ,0
Exp/Cntr=0.3,0.1

Type RM Length L Ch R = 1 ,95753   ,371,361,551
BEGIN DESCRIPTION:
This cross section corresponds to cross section 95764 of the non-georeferenced CDC model which was the source of this model.
END DESCRIPTION:
XS GIS Cut Line= 6
2503940.632570836963980.929405472503785.946856596957665.95647113
  2503532.122233 6956778.74236632502904.049998346955230.04762904
2502577.320993016954863.45321788  2499431.4099626950795.85341346
#Sta/Elev= 30
 -7474.3     424 -6905.8   411.7   -4758     410 -2974.4     414   -2767   428.5
 -2668.5  420.77    1000  420.77    1101     398    1765     391    1815     371
    1875     376    1920     396    2420     393    2425     392    2475     389
    2559     389    2615     392    2625     395    3020     392    3100     380
    3130     380    3230     394    3310     415    5390     415    5500     399
    6090     400    7020     410    7035     418    7070     418    7070     423
#Mann= 16 ,-1,0
 -7474.3      .1       0    1000    .035       0    1101      .1       0
    1765     .05       0    1920      .1       0    2420    .035       0
    2425    .045       0    2475    .025       0    2559    .045       0
    2615    .035       0    2625     .07       0    3100     .03       0
    3130     .07       0    3230    .035       0    3310     .05       0
    5390     .08       0
#XS Ineff= 2 , 0
       0    1010  420.77    3310       0     414
Permanent Ineff=
       F       F
Bank Sta=1765,1920
XS Rating Curve= 0 ,0
Exp/Cntr=0.3,0.1

Type RM Length L Ch R = 1 ,95392   ,672,671,672
BEGIN DESCRIPTION:
This cross section corresponds to cross section 95404 of the non-georeferenced CDC model which was the source of this model.
END DESCRIPTION:
XS GIS Cut Line= 6
2503974.323776426964404.533873222503787.854989266957653.29015788
2503681.05959916 6956787.12030232503149.05574194 6954925.8130013
 2502828.99995166954609.999984642500254.303657416950965.49250989
#Sta/Elev= 30
 -8334.3     424 -7765.8   411.7   -5618     410 -3834.4     414 -3728.2     426
   -3627   428.5 -3526.5  420.61    1000  420.61    1065     407    1250     407
    1335     395    1490     393    1600     370    1690     397    2555     393
    2560     392    2638     389    2722     389    2760     392    2765     393
    3255     394    3375     380    3415     393    3550     415    4430     415
    4430     394    4870     395    5080     396    5150     410    6140     424
#Mann= 15 ,-1,0
 -8334.3      .1       0    1000    .035       0    1065     .05       0
    1250     .09       0    1490     .05       0    1690     .09       0
    2555    .035       0    2560    .045       0    2638    .025       0
    2722    .045       0    2760    .035       0    2765     .07       0
    3255    .035       0    3550     .05       0    4870     .08       0
#XS Ineff= 2 , 0
       0    1010  420.61    3550       0     414
Permanent Ineff=
       F       F
Bank Sta=1490,1690
XS Rating Curve= 0 ,0
Exp/Cntr=0.3,0.1

Type RM Length L Ch R = 1 ,94721   ,398,3322,825
BEGIN DESCRIPTION:
This cross section corresponds to cross section 94735 of the non-georeferenced CDC model which was the source of this model.
END DESCRIPTION:
XS GIS Cut Line= 6
2504156.01107708 6963702.80922682503921.452163016956708.67459305
2503554.861032666954383.266842312503334.37558126 6954160.1432728
2503204.229844186954086.056150632501103.495856676951005.49242988
#Sta/Elev= 30
 -8334.3     424 -8220.9     422 -8140.3   415.7 -8106.5     419 -8018.5   413.1
 -7765.8   411.7 -6304.7   414.1   -5618     410 -4003.4     418 -3834.4     414
 -3790.3     416 -3728.2     426   -3627   428.5 -3526.5  420.29    1000  420.29
    1091     400    1150     395    1320     397    1360     376    1400     370
    1430     376    1470     393    1820     395    2570     392    3180     392
    3710     397    3725     407    3750     409    5040     412    5210     424
#Mann= 8 ,-1,0
 -8334.3      .1       0    1000    .035       0    1091      .1       0
    1320     .05       0    1470     .12       0    2570     .07       0
    3180     .05       0    3710     .08       0
#XS Ineff= 2 , 0
       0    1010  420.29               0
Permanent Ineff=
       F       F
Bank Sta=1320,1470
XS Rating Curve= 0 ,0
Exp/Cntr=0.3,0.1

Type RM Length L Ch R = 1 ,91399   ,383,457,471
BEGIN DESCRIPTION:
This cross section corresponds to cross section 91392 of the non-georeferenced CDC model which was the source of this model.
END DESCRIPTION:
XS GIS Cut Line= 6
   2504342.24297   6965162.82826   2504150.13018   6956764.49994
   2503743.90122   6953045.74938    2503235.9765   6952188.19315
   2503229.17796   6951967.29792   2502228.39518   6951298.10208
#Sta/Elev= 30
-10004.4     426 -8834.4   409.4   -6008     408 -4718.9   415.9 -4076.1   412.5
   -3947  419.83    1000  419.83    1105     396    1540     395    1590     376
    1660     376    1700     395    2375     394    2430     376    2505     376
    2550     395    3125     394    3220     365    3250     365    3318     379
    3346     395    3410     390    3510     383    3752     391    3840     391
    3860     398    4270     404    4300     413    4530     414    4560     422
#Mann= 11 ,-1,0
-10004.4     .12       0    1000    .035       0    1105     .12       0
    1540     .06       0    1700     .12       0    2375     .06       0
    2550     .12       0    3125     .06       0    3346     .08       0
    3410     .07       0    3752     .08       0
#XS Ineff= 2 , 0
       0    1010  419.83               0
Permanent Ineff=
       F       F
Bank Sta=3125,3346
XS Rating Curve= 0 ,0
Exp/Cntr=0.3,0.1

Type RM Length L Ch R = 1 ,90942   ,304,395,416
BEGIN DESCRIPTION:
This cross section corresponds to cross section 90927 of the non-georeferenced CDC model which was the source of this model.
END DESCRIPTION:
XS GIS Cut Line= 6
  2504354.0497236965083.502987712504309.855585666960828.45605163
2504183.951309926956933.582607812503669.470711596952209.84336764
2503710.463739846952014.089822132503482.644313576950439.94762921
#Sta/Elev= 30
-10004.4     426 -9765.9   419.9 -9459.2   419.6 -9212.6   411.5 -8834.4   409.4
 -6239.3     412   -6008     408 -4718.9   415.9 -4076.1   412.5   -3947  419.48
    1000  419.48    1108     395    1205     393    1230     385    1265     396
    1400     397    1560     393    2825     392    2890     395    2980     365
    3010     365    3045     375    3090     395    3170     393    3220     384
    3530     384    3700     391    3860     395    3890     414    4690     422
#Mann= 7 ,-1,0
-10004.4    .125       0    1000    .035       0    1108    .125       0
    2890     .06       0    3090     .08       0    3170     .07       0
    3700     .08       0
#XS Ineff= 2 , 0
       0    1010  419.48               0
Permanent Ineff=
       F       F
Bank Sta=2890,3090
XS Rating Curve= 0 ,0
Exp/Cntr=0.3,0.1

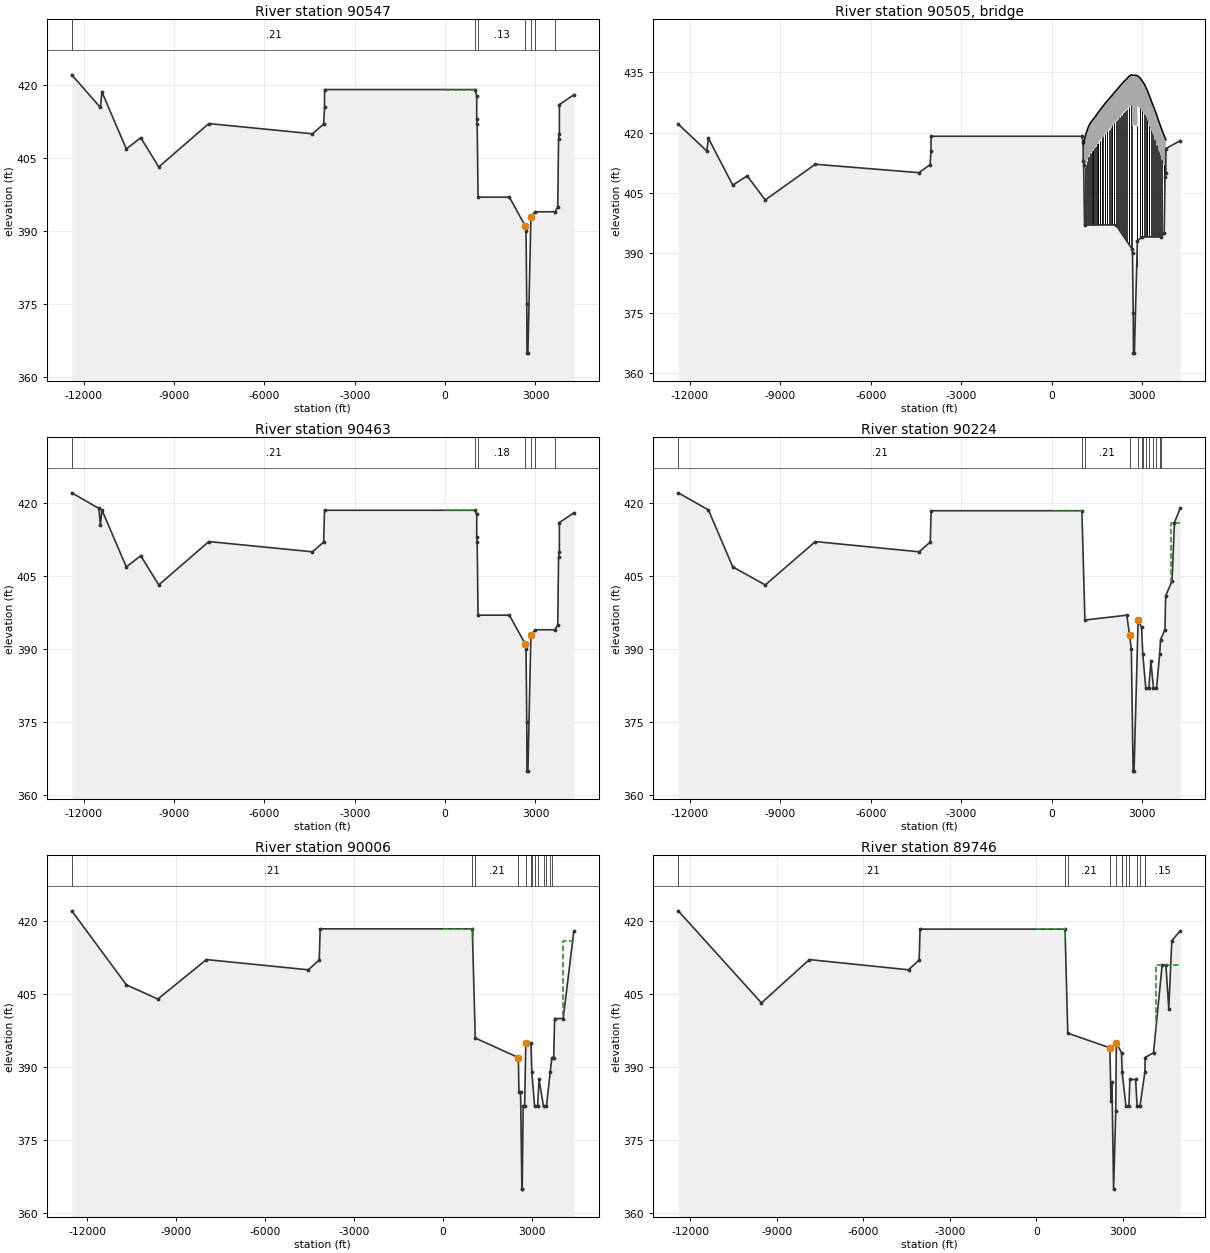
Type RM Length L Ch R = 1 ,90547   ,84,84,84
BEGIN DESCRIPTION:
This cross section corresponds to cross section 90538 of the non-georeferenced CDC model which was the source of this model.
END DESCRIPTION:
XS GIS Cut Line= 6
2504518.918487766967390.887152462504294.386128436959440.69734421
2504194.397811356956905.597099472504159.880163856956428.90612371
2504149.595407526956103.648572132504041.910255436950732.62355305
#Sta/Elev= 30
-12390.9   422.1-11440.7   415.4-11390.4   418.6  -10581   406.9-10101.3   409.2
 -9503.5   403.2 -7841.9   412.1 -4400.7     410 -4030.9     412 -4000.7   415.4
   -4000  419.08    1000  419.08    1051   417.7    1051     413    1066     412
    1096     397    2135     397    2670     391    2688     390    2712     375
    2720     365    2750     365    2850     393    3000     394    3650     394
    3740     395    3768     409    3795     410    3795     416    4275     418
#Mann= 7 ,-1,0
-12390.9     .21       0    1000    .035       0    1096     .13       0
    2670     .06       0    2850     .18       0    3000    .045       0
    3650     .12       0
#XS Ineff= 2 , 0
       0    1010  419.08               0
Permanent Ineff=
       F       F
Bank Sta=2670,2850
XS Rating Curve= 0 ,0
Exp/Cntr=0.5,0.3

Type RM Length L Ch R = 3 ,90505   ,,,
BEGIN DESCRIPTION:
90498  SH 310/Central Expressway
END DESCRIPTION:
Node Name=SH 310
Bridge Culvert--1,0,-1,-1, 0
Deck Dist Width WeirC Skew NumUp NumDn MinLoCord MaxHiCord MaxSubmerge Is_Ogee
1,82,2.6,0, 36, 36, , , 0.95, 0, ,,,
    1051  1135.3  1220.6  1288.7  1370.7  1452.7  1527.3  1606.9  1690.6  1770.2
  1849.8  1929.3  2008.9  2088.4  2167.9  2247.5    2327  2406.6  2486.1  2565.7
  2649.4  2649.4  2850.5  2850.5  2930.1  3009.6  3089.2  3168.7  3248.3  3327.8
  3407.4  3486.9  3566.5    3646  3725.6  3796.1
     417   419.5   421.4   422.4   423.2     424   424.8   425.6   426.4   427.2
   427.9   428.6   429.3     430   430.7   431.4   432.1   432.8   433.3     434
   434.4   434.4   434.2   434.2   433.7   432.9     432   430.7   429.2   427.6
   426.1   424.5   422.7   421.1   419.5   418.2
   409.4   411.9   413.8   414.8   415.6   416.4   417.2     418   418.8   419.6
   420.3     421   421.7   422.4   423.1   423.8   424.5   425.2   425.7   426.4
   426.8   421.9   421.7   426.6   426.1   425.3   424.4   423.1   421.6     420
   418.5   416.9   415.1   413.5   411.9   410.6
    1051  1135.3  1220.6  1288.7  1370.7  1452.7  1527.3  1606.9  1690.6  1770.2
  1849.8  1929.3  2008.9  2088.4  2167.9  2247.5    2327  2406.6  2486.1  2565.7
  2649.4  2649.4  2850.5  2850.5  2930.1  3009.6  3089.2  3168.7  3248.3  3327.8
  3407.4  3486.9  3566.5    3646  3725.6  3796.1
     417   419.5   421.4   422.4   423.2     424   424.8   425.6   426.4   427.2
   427.9   428.6   429.3     430   430.7   431.4   432.1   432.8   433.3     434
   434.4   434.4   434.2   434.2   433.7   432.9     432   430.7   429.2   427.6
   426.1   424.5   422.7   421.1   419.5   418.2
   409.4   411.9   413.8   414.8   415.6   416.4   417.2     418   418.8   419.6
   420.3     421   421.7   422.4   423.1   423.8   424.5   425.2   425.7   426.4
   426.8   421.9   421.7   426.6   426.1   425.3   424.4   423.1   421.6     420
   418.5   416.9   415.1   413.5   411.9   410.6
Pier Skew, UpSta & Num, DnSta & Num=  ,1121, 2 ,1121, 2 , 0 , 0 , 0 ,,
       3       2
   384.3   414.3
       3       2
   384.3   414.3
Pier Skew, UpSta & Num, DnSta & Num=  ,1135.3, 2 ,1135.3, 2 , 0 , 0 , 0 ,,
     2.5     2.5
       0     419
     2.5     2.5
       0     419
Pier Skew, UpSta & Num, DnSta & Num=  ,1181, 2 ,1181, 2 , 0 , 0 , 0 ,,
       3       2
   384.8   414.8
       3       2
   384.8   414.8
Pier Skew, UpSta & Num, DnSta & Num=  ,1220.6, 2 ,1220.6, 2 , 0 , 0 , 0 ,,
     2.5     2.5
       0     419
     2.5     2.5
       0     419
Pier Skew, UpSta & Num, DnSta & Num=  ,1241, 2 ,1241, 2 , 0 , 0 , 0 ,,
       3       2
   385.4   415.4
       3       2
   385.4   415.4
Pier Skew, UpSta & Num, DnSta & Num=  ,1288.7, 2 ,1288.7, 2 , 0 , 0 , 0 ,,
     2.5     2.5
       0     419
     2.5     2.5
       0     419
Pier Skew, UpSta & Num, DnSta & Num=  ,1301, 2 ,1301, 2 , 0 , 0 , 0 ,,
       3       2
   385.9   415.9
       3       2
   385.9   415.9
Pier Skew, UpSta & Num, DnSta & Num=  ,1361, 2 ,1361, 2 , 0 , 0 , 0 ,,
       3       2
     386     416
       3       2
     386     416
Pier Skew, UpSta & Num, DnSta & Num=  ,1370.7, 2 ,1370.7, 2 , 0 , 0 , 0 ,,
     2.5     2.5
       0     419
     2.5     2.5
       0     419
Pier Skew, UpSta & Num, DnSta & Num=  ,1421, 2 ,1421, 2 , 0 , 0 , 0 ,,
       3       2
   386.9   416.9
       3       2
   386.9   416.9
Pier Skew, UpSta & Num, DnSta & Num=  ,1452.7, 2 ,1452.7, 2 , 0 , 0 , 0 ,,
     2.5     2.5
       0     419
     2.5     2.5
       0     419
Pier Skew, UpSta & Num, DnSta & Num=  ,1481, 2 ,1481, 2 , 0 , 0 , 0 ,,
       3       2
   387.5   417.5
       3       2
   387.5   417.5
Pier Skew, UpSta & Num, DnSta & Num=  ,1527.3, 2 ,1527.3, 2 , 0 , 0 , 0 ,,
     2.5     2.5
       0     419
     2.5     2.5
       0     419
Pier Skew, UpSta & Num, DnSta & Num=  ,1541, 2 ,1541, 2 , 0 , 0 , 0 ,,
       3       2
     388     418
       3       2
     388     418
Pier Skew, UpSta & Num, DnSta & Num=  ,1601, 2 ,1601, 2 , 0 , 0 , 0 ,,
       3       2
   388.5   418.5
       3       2
   388.5   418.5
Pier Skew, UpSta & Num, DnSta & Num=  ,1606.9, 2 ,1606.9, 2 , 0 , 0 , 0 ,,
     2.5     2.5
       0     419
     2.5     2.5
       0     419
Pier Skew, UpSta & Num, DnSta & Num=  ,1661, 2 ,1661, 2 , 0 , 0 , 0 ,,
       3       2
   388.6   418.6
       3       2
   388.6   418.6
Pier Skew, UpSta & Num, DnSta & Num=  ,1690.6, 2 ,1690.6, 2 , 0 , 0 , 0 ,,
     2.5     2.5
       0     426
     2.5     2.5
       0     426
Pier Skew, UpSta & Num, DnSta & Num=  ,1721, 2 ,1721, 2 , 0 , 0 , 0 ,,
       3       2
   389.5   419.5
       3       2
   389.5   419.5
Pier Skew, UpSta & Num, DnSta & Num=  ,1770.2, 2 ,1770.2, 2 , 0 , 0 , 0 ,,
     2.5     2.5
       0     426
     2.5     2.5
       0     426
Pier Skew, UpSta & Num, DnSta & Num=  ,1781, 2 ,1781, 2 , 0 , 0 , 0 ,,
       3       2
   390.1   420.1
       3       2
   390.1   420.1
Pier Skew, UpSta & Num, DnSta & Num=  ,1841, 2 ,1841, 2 , 0 , 0 , 0 ,,
       3       2
   390.6   420.6
       3       2
   390.6   420.6
Pier Skew, UpSta & Num, DnSta & Num=  ,1849.8, 2 ,1849.8, 2 , 0 , 0 , 0 ,,
     2.5     2.5
       0     426
     2.5     2.5
       0     426
Pier Skew, UpSta & Num, DnSta & Num=  ,1901, 2 ,1901, 2 , 0 , 0 , 0 ,,
       3       2
   391.1   421.1
       3       2
   391.1   421.1
Pier Skew, UpSta & Num, DnSta & Num=  ,1929.3, 2 ,1929.3, 2 , 0 , 0 , 0 ,,
     2.5     2.5
       0     426
     2.5     2.5
       0     426
Pier Skew, UpSta & Num, DnSta & Num=  ,1961, 2 ,1961, 2 , 0 , 0 , 0 ,,
       3       2
   391.2   421.4
       3       2
   391.2   421.4
Pier Skew, UpSta & Num, DnSta & Num=  ,2008.9, 2 ,2008.9, 2 , 0 , 0 , 0 ,,
     2.5     2.5
       0     426
     2.5     2.5
       0     426
Pier Skew, UpSta & Num, DnSta & Num=  ,2021, 2 ,2021, 2 , 0 , 0 , 0 ,,
       3       2
     392   422.1
       3       2
     392   422.1
Pier Skew, UpSta & Num, DnSta & Num=  ,2081, 2 ,2081, 2 , 0 , 0 , 0 ,,
       3       2
     392   422.7
       3       2
     392   422.7
Pier Skew, UpSta & Num, DnSta & Num=  ,2088.4, 2 ,2088.4, 2 , 0 , 0 , 0 ,,
     2.5     2.5
       0     426
     2.5     2.5
       0     426
Pier Skew, UpSta & Num, DnSta & Num=  ,2141, 2 ,2141, 2 , 0 , 0 , 0 ,,
       3       2
     392   423.2
       3       2
     392   423.2
Pier Skew, UpSta & Num, DnSta & Num=  ,2167.9, 2 ,2167.9, 2 , 0 , 0 , 0 ,,
     2.5     2.5
       0     426
     2.5     2.5
       0     426
Pier Skew, UpSta & Num, DnSta & Num=  ,2201, 2 ,2201, 2 , 0 , 0 , 0 ,,
       3       2
     392   423.7
       3       2
     392   423.7
Pier Skew, UpSta & Num, DnSta & Num=  ,2247.5, 2 ,2247.5, 2 , 0 , 0 , 0 ,,
     2.5     2.5
       0     426
     2.5     2.5
       0     426
Pier Skew, UpSta & Num, DnSta & Num=  ,2261, 2 ,2261, 2 , 0 , 0 , 0 ,,
       3       2
     392     424
       3       2
     392     424
Pier Skew, UpSta & Num, DnSta & Num=  ,2321, 2 ,2321, 2 , 0 , 0 , 0 ,,
       3       2
     392   424.7
       3       2
     392   424.7
Pier Skew, UpSta & Num, DnSta & Num=  ,2327, 2 ,2327, 2 , 0 , 0 , 0 ,,
     2.5     2.5
       0     426
     2.5     2.5
       0     426
Pier Skew, UpSta & Num, DnSta & Num=  ,2381, 2 ,2381, 2 , 0 , 0 , 0 ,,
       3       2
     392   425.3
       3       2
     392   425.3
Pier Skew, UpSta & Num, DnSta & Num=  ,2406.6, 2 ,2406.6, 2 , 0 , 0 , 0 ,,
     2.5     2.5
       0     426
     2.5     2.5
       0     426
Pier Skew, UpSta & Num, DnSta & Num=  ,2441, 2 ,2441, 2 , 0 , 0 , 0 ,,
       3       2
     392   425.8
       3       2
     392   425.8
Pier Skew, UpSta & Num, DnSta & Num=  ,2486.1, 2 ,2486.1, 2 , 0 , 0 , 0 ,,
     2.5     2.5
       0     426
     2.5     2.5
       0     426
Pier Skew, UpSta & Num, DnSta & Num=  ,2501, 2 ,2501, 2 , 0 , 0 , 0 ,,
       3       2
     392   426.3
       3       2
     392   426.3
Pier Skew, UpSta & Num, DnSta & Num=  ,2561, 2 ,2561, 2 , 0 , 0 , 0 ,,
       3       2
     392   426.5
       3       2
     392   426.5
Pier Skew, UpSta & Num, DnSta & Num=  ,2565.7, 2 ,2565.7, 2 , 0 , 0 , 0 ,,
     2.5     2.5
       0     434
     2.5     2.5
       0     434
Pier Skew, UpSta & Num, DnSta & Num=  ,2649.4, 2 ,2649.4, 2 , 0 , 0 , 0 ,,
       3       3
       0     434
       3       3
       0     434
Pier Skew, UpSta & Num, DnSta & Num=  ,2675, 2 ,2675, 2 , 0 , 0 , 0 ,,
       5     2.5
     368     422
       5     2.5
     368     422
Pier Skew, UpSta & Num, DnSta & Num=  ,2827, 2 ,2827, 2 , 0 , 0 , 0 ,,
       5     2.5
     368     422
       5     2.5
     368     422
Pier Skew, UpSta & Num, DnSta & Num=  ,2850.5, 2 ,2850.5, 2 , 0 , 0 , 0 ,,
       3       3
       0     434
       3       3
       0     434
Pier Skew, UpSta & Num, DnSta & Num=  ,2930.1, 2 ,2930.1, 2 , 0 , 0 , 0 ,,
     2.5     2.5
       0     427
     2.5     2.5
       0     427
Pier Skew, UpSta & Num, DnSta & Num=  ,2941, 2 ,2941, 2 , 0 , 0 , 0 ,,
       3       2
     392   426.3
       3       2
     392   426.3
Pier Skew, UpSta & Num, DnSta & Num=  ,3001, 2 ,3001, 2 , 0 , 0 , 0 ,,
       3       2
     392   426.2
       3       2
     392   426.2
Pier Skew, UpSta & Num, DnSta & Num=  ,3009.6, 2 ,3009.6, 2 , 0 , 0 , 0 ,,
     2.5     2.5
       0     427
     2.5     2.5
       0     427
Pier Skew, UpSta & Num, DnSta & Num=  ,3061, 2 ,3061, 2 , 0 , 0 , 0 ,,
       3       2
     392   425.5
       3       2
     392   425.5
Pier Skew, UpSta & Num, DnSta & Num=  ,3089.2, 2 ,3089.2, 2 , 0 , 0 , 0 ,,
     2.5     2.5
       0     427
     2.5     2.5
       0     427
Pier Skew, UpSta & Num, DnSta & Num=  ,3121, 2 ,3121, 2 , 0 , 0 , 0 ,,
       3       2
     392   424.5
       3       2
     392   424.5
Pier Skew, UpSta & Num, DnSta & Num=  ,3168.7, 2 ,3168.7, 2 , 0 , 0 , 0 ,,
     2.5     2.5
       0     427
     2.5     2.5
       0     427
Pier Skew, UpSta & Num, DnSta & Num=  ,3181, 2 ,3181, 2 , 0 , 0 , 0 ,,
       3       2
     392   423.4
       3       2
     392   423.4
Pier Skew, UpSta & Num, DnSta & Num=  ,3241, 2 ,3241, 2 , 0 , 0 , 0 ,,
       3       2
     392   421.8
       3       2
     392   421.8
Pier Skew, UpSta & Num, DnSta & Num=  ,3248.3, 2 ,3248.3, 2 , 0 , 0 , 0 ,,
     2.5     2.5
       0     427
     2.5     2.5
       0     427
Pier Skew, UpSta & Num, DnSta & Num=  ,3301, 2 ,3301, 2 , 0 , 0 , 0 ,,
       3       2
     391     421
       3       2
     391     421
Pier Skew, UpSta & Num, DnSta & Num=  ,3327.8, 2 ,3327.8, 2 , 0 , 0 , 0 ,,
     2.5     2.5
       0     420
     2.5     2.5
       0     420
Pier Skew, UpSta & Num, DnSta & Num=  ,3361, 2 ,3361, 2 , 0 , 0 , 0 ,,
       3       2
   389.8   419.8
       3       2
   389.8   419.8
Pier Skew, UpSta & Num, DnSta & Num=  ,3407.4, 2 ,3407.4, 2 , 0 , 0 , 0 ,,
     2.5     2.5
       0     420
     2.5     2.5
       0     420
Pier Skew, UpSta & Num, DnSta & Num=  ,3421, 2 ,3421, 2 , 0 , 0 , 0 ,,
       3       2
   388.6   418.6
       3       2
   388.6   418.6
Pier Skew, UpSta & Num, DnSta & Num=  ,3481, 2 ,3481, 2 , 0 , 0 , 0 ,,
       3       2
   387.4   417.4
       3       2
   387.4   417.4
Pier Skew, UpSta & Num, DnSta & Num=  ,3486.9, 2 ,3486.9, 2 , 0 , 0 , 0 ,,
     2.5     2.5
       0     420
     2.5     2.5
       0     420
Pier Skew, UpSta & Num, DnSta & Num=  ,3541, 2 ,3541, 2 , 0 , 0 , 0 ,,
       3       2
   385.8   415.8
       3       2
   385.8   415.8
Pier Skew, UpSta & Num, DnSta & Num=  ,3566.5, 2 ,3566.5, 2 , 0 , 0 , 0 ,,
     2.5     2.5
       0     420
     2.5     2.5
       0     420
Pier Skew, UpSta & Num, DnSta & Num=  ,3601, 2 ,3601, 2 , 0 , 0 , 0 ,,
       3       2
     385     415
       3       2
     385     415
Pier Skew, UpSta & Num, DnSta & Num=  ,3646, 2 ,3646, 2 , 0 , 0 , 0 ,,
     2.5     2.5
       0     420
     2.5     2.5
       0     420
Pier Skew, UpSta & Num, DnSta & Num=  ,3661, 2 ,3661, 2 , 0 , 0 , 0 ,,
       3       2
   383.8   413.8
       3       2
   383.8   413.8
Pier Skew, UpSta & Num, DnSta & Num=  ,3721, 2 ,3721, 2 , 0 , 0 , 0 ,,
       3       2
   382.6   412.6
       3       2
   382.6   412.6
Pier Skew, UpSta & Num, DnSta & Num=  ,3725.6, 2 ,3725.6, 2 , 0 , 0 , 0 ,,
     2.5     2.5
       0     412
     2.5     2.5
       0     412
BR Coef= 1 , 0 , 0 ,1.05, 0 ,,,0.8,-1,0.5,1,
WSPro=,,,, 1 ,,,, 0 ,,,, 0 ,,,,-1 ,-1 ,-1 , 0 , 0 , 0 , 0 , 0
BC Design=,, 0 ,, 0 ,,,,,,
BC HTab HWMax=422
BC Use User HTab Curves=0
BC User HTab FreeFlow(D)= 0

Type RM Length L Ch R = 1 ,90463   ,200,239,263
BEGIN DESCRIPTION:
This cross section corresponds to cross section 90458 of the non-georeferenced CDC model which was the source of this model.
END DESCRIPTION:
XS GIS Cut Line= 6
2504712.349859426967385.800876542504509.150462666959627.94368888
2504229.035209276956920.250285392504229.908895166956833.46797863
2504185.970990936953966.099041462504123.483583096950737.95917229
#Sta/Elev= 30
-12390.9   422.1  -11490   418.9-11440.7   415.4-11390.4   418.6  -10581   406.9
-10101.3   409.2 -9503.5   403.2 -7841.9   412.1 -4400.7     410 -4030.9     412
   -4000  418.52    1000  418.52    1051   417.7    1051     413    1066     412
    1096     397    2135     397    2670     391    2688     390    2712     375
    2720     365    2750     365    2850     393    3000     394    3650     394
    3740     395    3768     409    3795     410    3795     416    4275     418
#Mann= 7 ,-1,0
-12390.9     .21       0    1000    .035       0    1096     .18       0
    2670     .07       0    2850     .18       0    3000    .045       0
    3650     .12       0
#XS Ineff= 2 , 0
       0    1010  418.52               0
Permanent Ineff=
       F       F
Bank Sta=2670,2850
XS Rating Curve= 0 ,0
Exp/Cntr=0.5,0.3

Type RM Length L Ch R = 1 ,90224   ,177,218,242
BEGIN DESCRIPTION:
This cross section corresponds to cross section 90230 of the non-georeferenced CDC model which was the source of this model.
END DESCRIPTION:
XS GIS Cut Line= 6
2504733.230723176967376.199845882504553.379376836959669.41014138
2504255.313043836956771.077027312504276.976386346955937.01242247
2504341.42212358 6953931.26971482504425.88291267 6950740.1186168
#Sta/Elev= 30
-12390.9   422.1-11390.4   418.6  -10581   406.9 -9503.5   403.2 -7841.9   412.1
 -4400.7     410 -4030.9     412   -4000  418.43    1000  418.43    1100     396
    2490     397    2580     393    2640     390    2700     365    2730     365
    2865     396    2980   394.5    3020     389    3120     382    3220     382
    3290   387.5    3375     382    3475     382    3580     389    3610     392
    3755     394    3780     401    3990     404    4070     416    4265     419
#Mann= 13 ,-1,0
-12390.9     .21       0    1000    .035       0    1100     .21       0
    2580     .07       0    2865     .21       0    2980    .035       0
    3020    .045       0    3120    .025       0    3220    .045       0
    3375    .025       0    3475    .045       0    3580    .035       0
    3610     .15       0
#XS Ineff= 2 , 0
       0    1010  418.43    3955       0     416
Permanent Ineff=
       F       F
Bank Sta=2580,2865
XS Rating Curve= 0 ,0
Exp/Cntr=0.3,0.1

Type RM Length L Ch R = 1 ,90006   ,224,260,313
BEGIN DESCRIPTION:
This cross section corresponds to cross section 89996 of the non-georeferenced CDC model which was the source of this model.
END DESCRIPTION:
XS GIS Cut Line= 6
2504767.667662176967471.27478696 2504593.01217166959626.34395455
2504274.791023256956694.380002222504316.995335166956089.37465055
 2504469.70730016953988.73744763 2504734.26385766950546.70332122
#Sta/Elev= 30
-12530.9   422.1-10683.2   406.9 -9623.6     404 -7981.9   412.1 -4540.7     410
 -4170.9     412   -4140   418.4    1000   418.4    1100     396    2555     392
    2575     385    2630     385    2675     365    2685     365    2718     382
    2768     382    2807     395    2980     395    3010     389    3105     382
    3205     382    3255   387.5    3405     382    3505     382    3630     389
    3690     392    3750     392    3780     400    4070     400    4430     418
#Mann= 13 ,-1,0
-12530.9     .21       0    1000    .035       0    1100     .21       0
    2555     .07       0    2807     .21       0    2980    .035       0
    3010    .045       0    3105    .025       0    3205    .045       0
    3405    .025       0    3505    .045       0    3630    .035       0
    3690     .15       0
#XS Ineff= 2 , 0
       0    1010   418.4    4080       0     416
Permanent Ineff=
       F       F
Bank Sta=2555,2807
XS Rating Curve= 0 ,0
Exp/Cntr=0.5,0.3

Type RM Length L Ch R = 1 ,89746   ,166,207,218
BEGIN DESCRIPTION:
This cross section corresponds to cross section 89764 of the non-georeferenced CDC model which was the source of this model.
END DESCRIPTION:
XS GIS Cut Line= 6
2504889.330476586967427.398234292504693.322010346959908.78794347
2504639.523233416959115.706852472504410.825528096956778.16133071
2504390.712707436956208.803545552505139.599661086950068.86175722
#Sta/Elev= 30
-12420.9   422.1 -9533.5   403.2 -7871.9   412.1 -4430.7     410 -4060.9     412
   -4030  418.35    1000  418.35    1095     397    2555     394    2595     383
    2627     387    2685     365    2760     381    2780     395    2960     393
    2980     389    3115     382    3215     382    3250   387.5    3450   387.5
    3500     382    3600     382    3770     389    3780     392    4070     393
    4370     411    4500     411    4600     402    4705     416    5000     418
#Mann= 13 ,-1,0
-12420.9     .21       0    1000    .035       0    1095     .21       0
    2555     .07       0    2780     .21       0    2960    .035       0
    2980    .045       0    3115    .025       0    3215    .045       0
    3500    .025       0    3600    .045       0    3770    .035       0
    3780     .15       0
#XS Ineff= 2 , 0
       0    1010  418.35    4150       0     411
Permanent Ineff=
       F       F
Bank Sta=2555,2780
XS Rating Curve= 0 ,0
Exp/Cntr=0.3,0.1

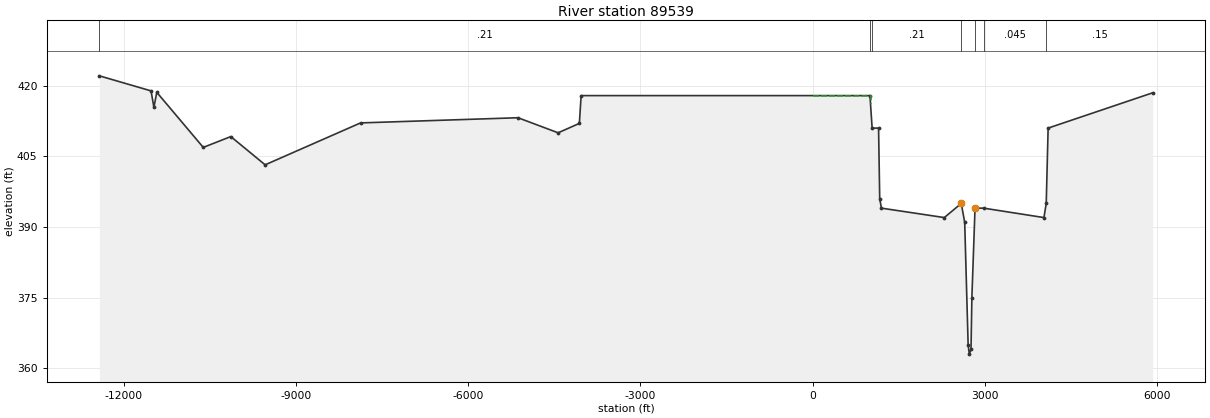
Type RM Length L Ch R = 1 ,89539   ,29,29,29
BEGIN DESCRIPTION:
This cross section corresponds to cross section 89547 of the non-georeferenced CDC model which was the source of this model.
END DESCRIPTION:
XS GIS Cut Line= 6
2504974.830633676967465.533000542504786.084291996959588.55728471
2504516.475251176956562.830068472504453.863499766956162.13565989
2504769.67192325 6954081.32846982505598.48686668 6949234.8991863
#Sta/Elev= 30
-12420.9   422.1  -11520   418.9-11470.7   415.4-11420.4   418.6  -10611   406.9
-10131.3   409.2 -9533.5   403.2 -7871.9   412.1   -5129   413.2 -4430.7     410
 -4060.9     412   -4030   417.9    1000   417.9    1038     411    1150     411
    1170     396    1200     394    2295     392    2590     395    2650     391
    2710     365    2730     363    2760     364    2775     375    2830     394
    2980     394    4030     392    4070     395    4103     411    5925   418.5
#Mann= 7 ,-1,0
-12420.9     .21       0    1000    .035       0    1038     .21       0
    2590     .07       0    2830     .21       0    2980    .045       0
    4070     .15       0
#XS Ineff= 2 , 0
       0    1010   417.9               0
Permanent Ineff=
       F       F
Bank Sta=2590,2830
XS Rating Curve= 0 ,0
Exp/Cntr=0.5,0.3