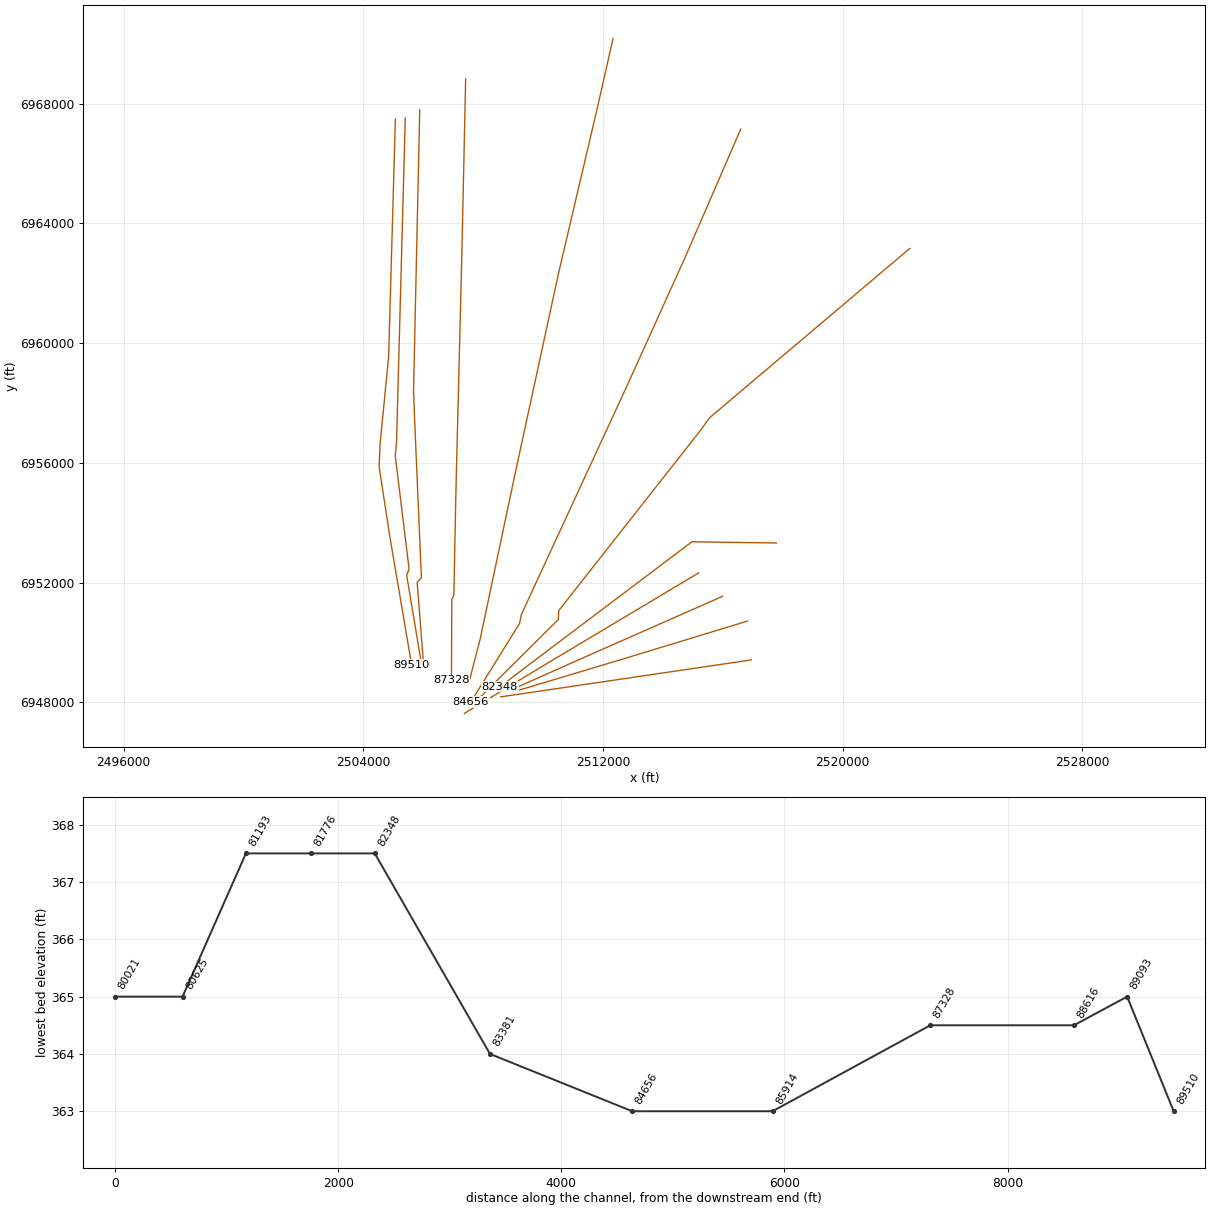
HEC-RAS study CDC_Consolidated_Model.prj: Upper Trinity CDC Consolidated Model

--- CDC_Consolidated_Model.g01 (geometry) --- (continued)

Type RM Length L Ch R = 3 ,89529   ,,,
BEGIN DESCRIPTION:
89537  Union Pacific Railroad Bridge
Includes modification for CDC DAL091008-1. The UPRR replaced single piers at each end of the river channel truss span with two piers at each end.
END DESCRIPTION:
Node Name=UP RR
Bridge Culvert--1,0,-1,-1, 0
Deck Dist Width WeirC Skew NumUp NumDn MinLoCord MaxHiCord MaxSubmerge Is_Ogee
1,18,2.6,0, 38, 38, , , 0.95, 0, ,,,
    1150    2643    2643    2662    2662    2663    2663    2682    2682    2683
    2683    2684    2684    2704    2704    2705    2705    2725    2725    2726
    2726    2746    2746    2747    2747    2767    2767    2768    2768    2769
    2769    2788    2788    2789    2789    2809    2809    4103
     411     411     411     411     420     420     411     411     411     411
     420     420     411     411     420     420     411     411     420     420
     411     411     420     420     411     411     420     420     411     411
     411     411     420     420     411     411     411     411
   408.4   408.4   405.4   405.4   405.4   405.4   405.4   405.4   408.4   408.4
   408.4   408.4   408.4   408.4   408.4   408.4   408.4   408.4   408.4   408.4
   408.4   408.4   408.4   408.4   408.4   408.4   408.4   408.4   408.4   408.4
   405.4   405.4   405.4   405.4   405.4   405.4   408.4   408.4
    1150    2643    2643    2662    2662    2663    2663    2682    2682    2683
    2683    2684    2684    2704    2704    2705    2705    2725    2725    2726
    2726    2746    2746    2747    2747    2767    2767    2768    2768    2769
    2769    2788    2788    2789    2789    2809    2809    4103
     411     411     411     411     420     420     411     411     411     411
     420     420     411     411     420     420     411     411     420     420
     411     411     420     420     411     411     420     420     411     411
     411     411     420     420     411     411     411     411
   408.4   408.4   405.4   405.4   405.4   405.4   405.4   405.4   408.4   408.4
   408.4   408.4   408.4   408.4   408.4   408.4   408.4   408.4   408.4   408.4
   408.4   408.4   408.4   408.4   408.4   408.4   408.4   408.4   408.4   408.4
   405.4   405.4   405.4   405.4   405.4   405.4   408.4   408.4
Pier Skew, UpSta & Num, DnSta & Num=  ,1167, 2 ,1167, 2 , 0 , 0 , 0 ,,
       5       5
       0     410
       5       5
       0     410
Pier Skew, UpSta & Num, DnSta & Num=  ,1188, 2 ,1188, 2 , 0 , 0 , 0 ,,
     6.2     6.2
       0     410
     6.2     6.2
       0     410
Pier Skew, UpSta & Num, DnSta & Num=  ,1221, 2 ,1221, 2 , 0 , 0 , 0 ,,
     2.4     2.4
       0     410
     2.4     2.4
       0     410
Pier Skew, UpSta & Num, DnSta & Num=  ,1251, 2 ,1251, 2 , 0 , 0 , 0 ,,
     2.4     2.4
       0     410
     2.4     2.4
       0     410
Pier Skew, UpSta & Num, DnSta & Num=  ,1281, 2 ,1281, 2 , 0 , 0 , 0 ,,
     2.4     2.4
       0     410
     2.4     2.4
       0     410
Pier Skew, UpSta & Num, DnSta & Num=  ,1311, 2 ,1311, 2 , 0 , 0 , 0 ,,
     2.4     2.4
       0     410
     2.4     2.4
       0     410
Pier Skew, UpSta & Num, DnSta & Num=  ,1341, 2 ,1341, 2 , 0 , 0 , 0 ,,
     2.4     2.4
       0     410
     2.4     2.4
       0     410
Pier Skew, UpSta & Num, DnSta & Num=  ,1371, 2 ,1371, 2 , 0 , 0 , 0 ,,
     2.4     2.4
       0     410
     2.4     2.4
       0     410
Pier Skew, UpSta & Num, DnSta & Num=  ,1401, 2 ,1401, 2 , 0 , 0 , 0 ,,
     2.4     2.4
       0     410
     2.4     2.4
       0     410
Pier Skew, UpSta & Num, DnSta & Num=  ,1431, 2 ,1431, 2 , 0 , 0 , 0 ,,
     2.4     2.4
       0     410
     2.4     2.4
       0     410
Pier Skew, UpSta & Num, DnSta & Num=  ,1461, 2 ,1461, 2 , 0 , 0 , 0 ,,
     2.4     2.4
       0     410
     2.4     2.4
       0     410
Pier Skew, UpSta & Num, DnSta & Num=  ,1491, 2 ,1491, 2 , 0 , 0 , 0 ,,
     2.4     2.4
       0     410
     2.4     2.4
       0     410
Pier Skew, UpSta & Num, DnSta & Num=  ,1508, 2 ,1508, 2 , 0 , 0 , 0 ,,
       5       5
       0     410
       5       5
       0     410
Pier Skew, UpSta & Num, DnSta & Num=  ,1523, 2 ,1523, 2 , 0 , 0 , 0 ,,
     1.2     1.2
       0     410
     1.2     1.2
       0     410
Pier Skew, UpSta & Num, DnSta & Num=  ,1538, 2 ,1538, 2 , 0 , 0 , 0 ,,
     1.2     1.2
       0     410
     1.2     1.2
       0     410
Pier Skew, UpSta & Num, DnSta & Num=  ,1553, 2 ,1553, 2 , 0 , 0 , 0 ,,
     1.2     1.2
       0     410
     1.2     1.2
       0     410
Pier Skew, UpSta & Num, DnSta & Num=  ,1568, 2 ,1568, 2 , 0 , 0 , 0 ,,
     1.2     1.2
       0     410
     1.2     1.2
       0     410
Pier Skew, UpSta & Num, DnSta & Num=  ,1583, 2 ,1583, 2 , 0 , 0 , 0 ,,
     1.2     1.2
       0     410
     1.2     1.2
       0     410
Pier Skew, UpSta & Num, DnSta & Num=  ,1598, 2 ,1598, 2 , 0 , 0 , 0 ,,
     1.2     1.2
       0     410
     1.2     1.2
       0     410
Pier Skew, UpSta & Num, DnSta & Num=  ,1613, 2 ,1613, 2 , 0 , 0 , 0 ,,
     1.2     1.2
       0     410
     1.2     1.2
       0     410
Pier Skew, UpSta & Num, DnSta & Num=  ,1628, 2 ,1628, 2 , 0 , 0 , 0 ,,
     1.2     1.2
       0     410
     1.2     1.2
       0     410
Pier Skew, UpSta & Num, DnSta & Num=  ,1643, 2 ,1643, 2 , 0 , 0 , 0 ,,
     1.2     1.2
       0     410
     1.2     1.2
       0     410
Pier Skew, UpSta & Num, DnSta & Num=  ,1658, 2 ,1658, 2 , 0 , 0 , 0 ,,
     1.2     1.2
       0     410
     1.2     1.2
       0     410
Pier Skew, UpSta & Num, DnSta & Num=  ,1673, 2 ,1673, 2 , 0 , 0 , 0 ,,
     1.2     1.2
       0     410
     1.2     1.2
       0     410
Pier Skew, UpSta & Num, DnSta & Num=  ,1688, 2 ,1688, 2 , 0 , 0 , 0 ,,
     1.2     1.2
       0     410
     1.2     1.2
       0     410
Pier Skew, UpSta & Num, DnSta & Num=  ,1703, 2 ,1703, 2 , 0 , 0 , 0 ,,
     1.2     1.2
       0     410
     1.2     1.2
       0     410
Pier Skew, UpSta & Num, DnSta & Num=  ,1718, 2 ,1718, 2 , 0 , 0 , 0 ,,
     1.2     1.2
       0     410
     1.2     1.2
       0     410
Pier Skew, UpSta & Num, DnSta & Num=  ,1733, 2 ,1733, 2 , 0 , 0 , 0 ,,
     1.2     1.2
       0     410
     1.2     1.2
       0     410
Pier Skew, UpSta & Num, DnSta & Num=  ,1748, 2 ,1748, 2 , 0 , 0 , 0 ,,
     1.2     1.2
       0     410
     1.2     1.2
       0     410
Pier Skew, UpSta & Num, DnSta & Num=  ,1763, 2 ,1763, 2 , 0 , 0 , 0 ,,
     1.2     1.2
       0     410
     1.2     1.2
       0     410
Pier Skew, UpSta & Num, DnSta & Num=  ,1778, 2 ,1778, 2 , 0 , 0 , 0 ,,
     1.2     1.2
       0     410
     1.2     1.2
       0     410
Pier Skew, UpSta & Num, DnSta & Num=  ,1793, 2 ,1793, 2 , 0 , 0 , 0 ,,
     1.2     1.2
       0     410
     1.2     1.2
       0     410
Pier Skew, UpSta & Num, DnSta & Num=  ,1810, 2 ,1810, 2 , 0 , 0 , 0 ,,
     1.2     1.2
       0     410
     1.2     1.2
       0     410
Pier Skew, UpSta & Num, DnSta & Num=  ,1825, 2 ,1825, 2 , 0 , 0 , 0 ,,
     1.2     1.2
       0     410
     1.2     1.2
       0     410
Pier Skew, UpSta & Num, DnSta & Num=  ,1840, 2 ,1840, 2 , 0 , 0 , 0 ,,
     1.2     1.2
       0     410
     1.2     1.2
       0     410
Pier Skew, UpSta & Num, DnSta & Num=  ,1855, 2 ,1855, 2 , 0 , 0 , 0 ,,
     1.2     1.2
       0     410
     1.2     1.2
       0     410
Pier Skew, UpSta & Num, DnSta & Num=  ,1870, 2 ,1870, 2 , 0 , 0 , 0 ,,
     1.2     1.2
       0     410
     1.2     1.2
       0     410
Pier Skew, UpSta & Num, DnSta & Num=  ,1885, 2 ,1885, 2 , 0 , 0 , 0 ,,
     1.2     1.2
       0     410
     1.2     1.2
       0     410
Pier Skew, UpSta & Num, DnSta & Num=  ,1900, 2 ,1900, 2 , 0 , 0 , 0 ,,
     1.2     1.2
       0     410
     1.2     1.2
       0     410
Pier Skew, UpSta & Num, DnSta & Num=  ,1915, 2 ,1915, 2 , 0 , 0 , 0 ,,
     1.2     1.2
       0     410
     1.2     1.2
       0     410
Pier Skew, UpSta & Num, DnSta & Num=  ,1930, 2 ,1930, 2 , 0 , 0 , 0 ,,
     1.2     1.2
       0     410
     1.2     1.2
       0     410
Pier Skew, UpSta & Num, DnSta & Num=  ,1945, 2 ,1945, 2 , 0 , 0 , 0 ,,
     1.2     1.2
       0     410
     1.2     1.2
       0     410
Pier Skew, UpSta & Num, DnSta & Num=  ,1960, 2 ,1960, 2 , 0 , 0 , 0 ,,
     1.2     1.2
       0     410
     1.2     1.2
       0     410
Pier Skew, UpSta & Num, DnSta & Num=  ,1975, 2 ,1975, 2 , 0 , 0 , 0 ,,
     1.2     1.2
       0     410
     1.2     1.2
       0     410
Pier Skew, UpSta & Num, DnSta & Num=  ,1990, 2 ,1990, 2 , 0 , 0 , 0 ,,
     1.2     1.2
       0     410
     1.2     1.2
       0     410
Pier Skew, UpSta & Num, DnSta & Num=  ,2005, 2 ,2005, 2 , 0 , 0 , 0 ,,
     1.2     1.2
       0     410
     1.2     1.2
       0     410
Pier Skew, UpSta & Num, DnSta & Num=  ,2020, 2 ,2020, 2 , 0 , 0 , 0 ,,
     1.2     1.2
       0     410
     1.2     1.2
       0     410
Pier Skew, UpSta & Num, DnSta & Num=  ,2035, 2 ,2035, 2 , 0 , 0 , 0 ,,
     1.2     1.2
       0     410
     1.2     1.2
       0     410
Pier Skew, UpSta & Num, DnSta & Num=  ,2050, 2 ,2050, 2 , 0 , 0 , 0 ,,
     1.2     1.2
       0     410
     1.2     1.2
       0     410
Pier Skew, UpSta & Num, DnSta & Num=  ,2065, 2 ,2065, 2 , 0 , 0 , 0 ,,
     1.2     1.2
       0     410
     1.2     1.2
       0     410
Pier Skew, UpSta & Num, DnSta & Num=  ,2080, 2 ,2080, 2 , 0 , 0 , 0 ,,
     1.2     1.2
       0     410
     1.2     1.2
       0     410
Pier Skew, UpSta & Num, DnSta & Num=  ,2095, 2 ,2095, 2 , 0 , 0 , 0 ,,
     1.2     1.2
       0     410
     1.2     1.2
       0     410
Pier Skew, UpSta & Num, DnSta & Num=  ,2111, 2 ,2111, 2 , 0 , 0 , 0 ,,
     1.2     1.2
       0     410
     1.2     1.2
       0     410
Pier Skew, UpSta & Num, DnSta & Num=  ,2126, 2 ,2126, 2 , 0 , 0 , 0 ,,
     1.2     1.2
       0     410
     1.2     1.2
       0     410
Pier Skew, UpSta & Num, DnSta & Num=  ,2141, 2 ,2141, 2 , 0 , 0 , 0 ,,
     1.2     1.2
       0     410
     1.2     1.2
       0     410
Pier Skew, UpSta & Num, DnSta & Num=  ,2156, 2 ,2156, 2 , 0 , 0 , 0 ,,
     1.2     1.2
       0     410
     1.2     1.2
       0     410
Pier Skew, UpSta & Num, DnSta & Num=  ,2171, 2 ,2171, 2 , 0 , 0 , 0 ,,
     1.2     1.2
       0     410
     1.2     1.2
       0     410
Pier Skew, UpSta & Num, DnSta & Num=  ,2186, 2 ,2186, 2 , 0 , 0 , 0 ,,
     1.2     1.2
       0     410
     1.2     1.2
       0     410
Pier Skew, UpSta & Num, DnSta & Num=  ,2202, 2 ,2202, 2 , 0 , 0 , 0 ,,
     1.2     1.2
       0     410
     1.2     1.2
       0     410
Pier Skew, UpSta & Num, DnSta & Num=  ,2217, 2 ,2217, 2 , 0 , 0 , 0 ,,
     1.2     1.2
       0     410
     1.2     1.2
       0     410
Pier Skew, UpSta & Num, DnSta & Num=  ,2232, 2 ,2232, 2 , 0 , 0 , 0 ,,
     1.2     1.2
       0     410
     1.2     1.2
       0     410
Pier Skew, UpSta & Num, DnSta & Num=  ,2247, 2 ,2247, 2 , 0 , 0 , 0 ,,
     1.2     1.2
       0     410
     1.2     1.2
       0     410
Pier Skew, UpSta & Num, DnSta & Num=  ,2262, 2 ,2262, 2 , 0 , 0 , 0 ,,
     1.2     1.2
       0     410
     1.2     1.2
       0     410
Pier Skew, UpSta & Num, DnSta & Num=  ,2277, 2 ,2277, 2 , 0 , 0 , 0 ,,
     1.2     1.2
       0     410
     1.2     1.2
       0     410
Pier Skew, UpSta & Num, DnSta & Num=  ,2292, 2 ,2292, 2 , 0 , 0 , 0 ,,
     1.2     1.2
       0     410
     1.2     1.2
       0     410
Pier Skew, UpSta & Num, DnSta & Num=  ,2309, 2 ,2309, 2 , 0 , 0 , 0 ,,
     1.2     1.2
       0     410
     1.2     1.2
       0     410
Pier Skew, UpSta & Num, DnSta & Num=  ,2324, 2 ,2324, 2 , 0 , 0 , 0 ,,
     1.2     1.2
       0     410
     1.2     1.2
       0     410
Pier Skew, UpSta & Num, DnSta & Num=  ,2339, 2 ,2339, 2 , 0 , 0 , 0 ,,
     1.2     1.2
       0     410
     1.2     1.2
       0     410
Pier Skew, UpSta & Num, DnSta & Num=  ,2354, 2 ,2354, 2 , 0 , 0 , 0 ,,
     1.2     1.2
       0     410
     1.2     1.2
       0     410
Pier Skew, UpSta & Num, DnSta & Num=  ,2369, 2 ,2369, 2 , 0 , 0 , 0 ,,
     1.2     1.2
       0     410
     1.2     1.2
       0     410
Pier Skew, UpSta & Num, DnSta & Num=  ,2384, 2 ,2384, 2 , 0 , 0 , 0 ,,
     1.2     1.2
       0     410
     1.2     1.2
       0     410
Pier Skew, UpSta & Num, DnSta & Num=  ,2400, 2 ,2400, 2 , 0 , 0 , 0 ,,
     1.2     1.2
       0     410
     1.2     1.2
       0     410
Pier Skew, UpSta & Num, DnSta & Num=  ,2415, 2 ,2415, 2 , 0 , 0 , 0 ,,
     1.2     1.2
       0     410
     1.2     1.2
       0     410
Pier Skew, UpSta & Num, DnSta & Num=  ,2430, 2 ,2430, 2 , 0 , 0 , 0 ,,
     1.2     1.2
       0     410
     1.2     1.2
       0     410
Pier Skew, UpSta & Num, DnSta & Num=  ,2445, 2 ,2445, 2 , 0 , 0 , 0 ,,
     1.2     1.2
       0     410
     1.2     1.2
       0     410
Pier Skew, UpSta & Num, DnSta & Num=  ,2460, 2 ,2460, 2 , 0 , 0 , 0 ,,
     1.2     1.2
       0     410
     1.2     1.2
       0     410
Pier Skew, UpSta & Num, DnSta & Num=  ,2475, 2 ,2475, 2 , 0 , 0 , 0 ,,
     1.2     1.2
       0     410
     1.2     1.2
       0     410
Pier Skew, UpSta & Num, DnSta & Num=  ,2490, 2 ,2490, 2 , 0 , 0 , 0 ,,
     1.2     1.2
       0     410
     1.2     1.2
       0     410
Pier Skew, UpSta & Num, DnSta & Num=  ,2505, 2 ,2505, 2 , 0 , 0 , 0 ,,
     1.2     1.2
       0     410
     1.2     1.2
       0     410
Pier Skew, UpSta & Num, DnSta & Num=  ,2520, 2 ,2520, 2 , 0 , 0 , 0 ,,
     1.2     1.2
       0     410
     1.2     1.2
       0     410
Pier Skew, UpSta & Num, DnSta & Num=  ,2535, 2 ,2535, 2 , 0 , 0 , 0 ,,
     1.2     1.2
       0     410
     1.2     1.2
       0     410
Pier Skew, UpSta & Num, DnSta & Num=  ,2550, 2 ,2550, 2 , 0 , 0 , 0 ,,
     1.2     1.2
       0     410
     1.2     1.2
       0     410
Pier Skew, UpSta & Num, DnSta & Num=  ,2565, 2 ,2565, 2 , 0 , 0 , 0 ,,
     1.2     1.2
       0     410
     1.2     1.2
       0     410
Pier Skew, UpSta & Num, DnSta & Num=  ,2580, 2 ,2580, 2 , 0 , 0 , 0 ,,
     1.2     1.2
       0     410
     1.2     1.2
       0     410
Pier Skew, UpSta & Num, DnSta & Num=  ,2595, 2 ,2595, 2 , 0 , 0 , 0 ,,
     1.2     1.2
       0     410
     1.2     1.2
       0     410
Pier Skew, UpSta & Num, DnSta & Num=  ,2611, 2 ,2611, 2 , 0 , 0 , 0 ,,
     1.2     1.2
       0     410
     1.2     1.2
       0     410
Pier Skew, UpSta & Num, DnSta & Num=  ,2626, 2 ,2626, 2 , 0 , 0 , 0 ,,
     1.2     1.2
       0     410
     1.2     1.2
       0     410
Pier Skew, UpSta & Num, DnSta & Num=  ,2646, 2 ,2646, 2 , 0 , 0 , 0 ,,
       6       6
       0     410
       6       6
       0     410
Pier Skew, UpSta & Num, DnSta & Num=  ,2679, 2 ,2679, 2 , 0 , 0 , 0 ,,
       6       6
       0     410
       6       6
       0     410
Pier Skew, UpSta & Num, DnSta & Num=  ,2772, 2 ,2772, 2 , 0 , 0 , 0 ,,
       6       6
       0     410
       6       6
       0     410
Pier Skew, UpSta & Num, DnSta & Num=  ,2806, 2 ,2806, 2 , 0 , 0 , 0 ,,
       6       6
       0     410
       6       6
       0     410
Pier Skew, UpSta & Num, DnSta & Num=  ,2813, 2 ,2813, 2 , 0 , 0 , 0 ,,
     1.2     1.2
       0     410
     1.2     1.2
       0     410
Pier Skew, UpSta & Num, DnSta & Num=  ,2828, 2 ,2828, 2 , 0 , 0 , 0 ,,
     1.2     1.2
       0     410
     1.2     1.2
       0     410
Pier Skew, UpSta & Num, DnSta & Num=  ,2843, 2 ,2843, 2 , 0 , 0 , 0 ,,
     1.2     1.2
       0     410
     1.2     1.2
       0     410
Pier Skew, UpSta & Num, DnSta & Num=  ,2858, 2 ,2858, 2 , 0 , 0 , 0 ,,
     1.2     1.2
       0     410
     1.2     1.2
       0     410
Pier Skew, UpSta & Num, DnSta & Num=  ,2873, 2 ,2873, 2 , 0 , 0 , 0 ,,
       5       5
       0     410
       5       5
       0     410
Pier Skew, UpSta & Num, DnSta & Num=  ,2888, 2 ,2888, 2 , 0 , 0 , 0 ,,
     1.2     1.2
       0     410
     1.2     1.2
       0     410
Pier Skew, UpSta & Num, DnSta & Num=  ,2903, 2 ,2903, 2 , 0 , 0 , 0 ,,
     1.2     1.2
       0     410
     1.2     1.2
       0     410
Pier Skew, UpSta & Num, DnSta & Num=  ,2918, 2 ,2918, 2 , 0 , 0 , 0 ,,
     1.2     1.2
       0     410
     1.2     1.2
       0     410
Pier Skew, UpSta & Num, DnSta & Num=  ,2933, 2 ,2933, 2 , 0 , 0 , 0 ,,
     1.2     1.2
       0     410
     1.2     1.2
       0     410
Pier Skew, UpSta & Num, DnSta & Num=  ,2948, 2 ,2948, 2 , 0 , 0 , 0 ,,
     1.2     1.2
       0     410
     1.2     1.2
       0     410
Pier Skew, UpSta & Num, DnSta & Num=  ,2963, 2 ,2963, 2 , 0 , 0 , 0 ,,
     1.2     1.2
       0     410
     1.2     1.2
       0     410
Pier Skew, UpSta & Num, DnSta & Num=  ,2978, 2 ,2978, 2 , 0 , 0 , 0 ,,
     1.2     1.2
       0     410
     1.2     1.2
       0     410
Pier Skew, UpSta & Num, DnSta & Num=  ,2993, 2 ,2993, 2 , 0 , 0 , 0 ,,
     1.2     1.2
       0     410
     1.2     1.2
       0     410
Pier Skew, UpSta & Num, DnSta & Num=  ,3008, 2 ,3008, 2 , 0 , 0 , 0 ,,
     1.2     1.2
       0     410
     1.2     1.2
       0     410
Pier Skew, UpSta & Num, DnSta & Num=  ,3023, 2 ,3023, 2 , 0 , 0 , 0 ,,
     1.2     1.2
       0     410
     1.2     1.2
       0     410
Pier Skew, UpSta & Num, DnSta & Num=  ,3038, 2 ,3038, 2 , 0 , 0 , 0 ,,
     1.2     1.2
       0     410
     1.2     1.2
       0     410
Pier Skew, UpSta & Num, DnSta & Num=  ,3053, 2 ,3053, 2 , 0 , 0 , 0 ,,
     1.2     1.2
       0     410
     1.2     1.2
       0     410
Pier Skew, UpSta & Num, DnSta & Num=  ,3068, 2 ,3068, 2 , 0 , 0 , 0 ,,
     1.2     1.2
       0     410
     1.2     1.2
       0     410
Pier Skew, UpSta & Num, DnSta & Num=  ,3083, 2 ,3083, 2 , 0 , 0 , 0 ,,
     1.2     1.2
       0     410
     1.2     1.2
       0     410
Pier Skew, UpSta & Num, DnSta & Num=  ,3100, 2 ,3100, 2 , 0 , 0 , 0 ,,
     1.2     1.2
       0     410
     1.2     1.2
       0     410
Pier Skew, UpSta & Num, DnSta & Num=  ,3115, 2 ,3115, 2 , 0 , 0 , 0 ,,
     1.2     1.2
       0     410
     1.2     1.2
       0     410
Pier Skew, UpSta & Num, DnSta & Num=  ,3130, 2 ,3130, 2 , 0 , 0 , 0 ,,
     1.2     1.2
       0     410
     1.2     1.2
       0     410
Pier Skew, UpSta & Num, DnSta & Num=  ,3145, 2 ,3145, 2 , 0 , 0 , 0 ,,
     1.2     1.2
       0     410
     1.2     1.2
       0     410
Pier Skew, UpSta & Num, DnSta & Num=  ,3160, 2 ,3160, 2 , 0 , 0 , 0 ,,
     1.2     1.2
       0     410
     1.2     1.2
       0     410
Pier Skew, UpSta & Num, DnSta & Num=  ,3175, 2 ,3175, 2 , 0 , 0 , 0 ,,
     1.2     1.2
       0     410
     1.2     1.2
       0     410
Pier Skew, UpSta & Num, DnSta & Num=  ,3190, 2 ,3190, 2 , 0 , 0 , 0 ,,
     1.2     1.2
       0     410
     1.2     1.2
       0     410
Pier Skew, UpSta & Num, DnSta & Num=  ,3205, 2 ,3205, 2 , 0 , 0 , 0 ,,
     1.2     1.2
       0     410
     1.2     1.2
       0     410
Pier Skew, UpSta & Num, DnSta & Num=  ,3220, 2 ,3220, 2 , 0 , 0 , 0 ,,
     1.2     1.2
       0     410
     1.2     1.2
       0     410
Pier Skew, UpSta & Num, DnSta & Num=  ,3235, 2 ,3235, 2 , 0 , 0 , 0 ,,
     1.2     1.2
       0     410
     1.2     1.2
       0     410
Pier Skew, UpSta & Num, DnSta & Num=  ,3250, 2 ,3250, 2 , 0 , 0 , 0 ,,
     1.2     1.2
       0     410
     1.2     1.2
       0     410
Pier Skew, UpSta & Num, DnSta & Num=  ,3265, 2 ,3265, 2 , 0 , 0 , 0 ,,
       3       3
       0     410
       3       3
       0     410
Pier Skew, UpSta & Num, DnSta & Num=  ,3295, 2 ,3295, 2 , 0 , 0 , 0 ,,
       3       3
       0     410
       3       3
       0     410
Pier Skew, UpSta & Num, DnSta & Num=  ,3310, 2 ,3310, 2 , 0 , 0 , 0 ,,
     1.2     1.2
       0     410
     1.2     1.2
       0     410
Pier Skew, UpSta & Num, DnSta & Num=  ,3325, 2 ,3325, 2 , 0 , 0 , 0 ,,
     1.2     1.2
       0     410
     1.2     1.2
       0     410
Pier Skew, UpSta & Num, DnSta & Num=  ,3340, 2 ,3340, 2 , 0 , 0 , 0 ,,
     1.2     1.2
       0     410
     1.2     1.2
       0     410
Pier Skew, UpSta & Num, DnSta & Num=  ,3355, 2 ,3355, 2 , 0 , 0 , 0 ,,
     1.2     1.2
       0     410
     1.2     1.2
       0     410
Pier Skew, UpSta & Num, DnSta & Num=  ,3370, 2 ,3370, 2 , 0 , 0 , 0 ,,
     1.2     1.2
       0     410
     1.2     1.2
       0     410
Pier Skew, UpSta & Num, DnSta & Num=  ,3385, 2 ,3385, 2 , 0 , 0 , 0 ,,
     1.2     1.2
       0     410
     1.2     1.2
       0     410
Pier Skew, UpSta & Num, DnSta & Num=  ,3400, 2 ,3400, 2 , 0 , 0 , 0 ,,
     1.2     1.2
       0     410
     1.2     1.2
       0     410
Pier Skew, UpSta & Num, DnSta & Num=  ,3415, 2 ,3415, 2 , 0 , 0 , 0 ,,
     1.2     1.2
       0     410
     1.2     1.2
       0     410
Pier Skew, UpSta & Num, DnSta & Num=  ,3430, 2 ,3430, 2 , 0 , 0 , 0 ,,
     1.2     1.2
       0     410
     1.2     1.2
       0     410
Pier Skew, UpSta & Num, DnSta & Num=  ,3445, 2 ,3445, 2 , 0 , 0 , 0 ,,
     1.2     1.2
       0     410
     1.2     1.2
       0     410
Pier Skew, UpSta & Num, DnSta & Num=  ,3460, 2 ,3460, 2 , 0 , 0 , 0 ,,
     1.2     1.2
       0     410
     1.2     1.2
       0     410
Pier Skew, UpSta & Num, DnSta & Num=  ,3475, 2 ,3475, 2 , 0 , 0 , 0 ,,
     1.2     1.2
       0     410
     1.2     1.2
       0     410
Pier Skew, UpSta & Num, DnSta & Num=  ,3490, 2 ,3490, 2 , 0 , 0 , 0 ,,
     1.2     1.2
       0     410
     1.2     1.2
       0     410
Pier Skew, UpSta & Num, DnSta & Num=  ,3505, 2 ,3505, 2 , 0 , 0 , 0 ,,
     1.2     1.2
       0     410
     1.2     1.2
       0     410
Pier Skew, UpSta & Num, DnSta & Num=  ,3520, 2 ,3520, 2 , 0 , 0 , 0 ,,
     1.2     1.2
       0     410
     1.2     1.2
       0     410
Pier Skew, UpSta & Num, DnSta & Num=  ,3535, 2 ,3535, 2 , 0 , 0 , 0 ,,
     1.2     1.2
       0     410
     1.2     1.2
       0     410
Pier Skew, UpSta & Num, DnSta & Num=  ,3550, 2 ,3550, 2 , 0 , 0 , 0 ,,
     1.2     1.2
       0     410
     1.2     1.2
       0     410
Pier Skew, UpSta & Num, DnSta & Num=  ,3565, 2 ,3565, 2 , 0 , 0 , 0 ,,
     1.2     1.2
       0     410
     1.2     1.2
       0     410
Pier Skew, UpSta & Num, DnSta & Num=  ,3580, 2 ,3580, 2 , 0 , 0 , 0 ,,
     1.2     1.2
       0     410
     1.2     1.2
       0     410
Pier Skew, UpSta & Num, DnSta & Num=  ,3595, 2 ,3595, 2 , 0 , 0 , 0 ,,
     1.2     1.2
       0     410
     1.2     1.2
       0     410
Pier Skew, UpSta & Num, DnSta & Num=  ,3610, 2 ,3610, 2 , 0 , 0 , 0 ,,
     1.2     1.2
       0     410
     1.2     1.2
       0     410
Pier Skew, UpSta & Num, DnSta & Num=  ,3625, 2 ,3625, 2 , 0 , 0 , 0 ,,
     1.2     1.2
       0     410
     1.2     1.2
       0     410
Pier Skew, UpSta & Num, DnSta & Num=  ,3640, 2 ,3640, 2 , 0 , 0 , 0 ,,
     1.2     1.2
       0     410
     1.2     1.2
       0     410
Pier Skew, UpSta & Num, DnSta & Num=  ,3655, 2 ,3655, 2 , 0 , 0 , 0 ,,
     1.2     1.2
       0     410
     1.2     1.2
       0     410
Pier Skew, UpSta & Num, DnSta & Num=  ,3670, 2 ,3670, 2 , 0 , 0 , 0 ,,
     1.2     1.2
       0     410
     1.2     1.2
       0     410
Pier Skew, UpSta & Num, DnSta & Num=  ,3685, 2 ,3685, 2 , 0 , 0 , 0 ,,
       3       3
       0     410
       3       3
       0     410
Pier Skew, UpSta & Num, DnSta & Num=  ,3715, 2 ,3715, 2 , 0 , 0 , 0 ,,
       3       3
       0     410
       3       3
       0     410
Pier Skew, UpSta & Num, DnSta & Num=  ,3730, 2 ,3730, 2 , 0 , 0 , 0 ,,
     1.2     1.2
       0     410
     1.2     1.2
       0     410
Pier Skew, UpSta & Num, DnSta & Num=  ,3745, 2 ,3745, 2 , 0 , 0 , 0 ,,
     1.2     1.2
       0     410
     1.2     1.2
       0     410
Pier Skew, UpSta & Num, DnSta & Num=  ,3760, 2 ,3760, 2 , 0 , 0 , 0 ,,
     1.2     1.2
       0     410
     1.2     1.2
       0     410
Pier Skew, UpSta & Num, DnSta & Num=  ,3775, 2 ,3775, 2 , 0 , 0 , 0 ,,
     1.2     1.2
       0     410
     1.2     1.2
       0     410
Pier Skew, UpSta & Num, DnSta & Num=  ,3790, 2 ,3790, 2 , 0 , 0 , 0 ,,
     1.2     1.2
       0     410
     1.2     1.2
       0     410
Pier Skew, UpSta & Num, DnSta & Num=  ,3805, 2 ,3805, 2 , 0 , 0 , 0 ,,
     1.2     1.2
       0     410
     1.2     1.2
       0     410
Pier Skew, UpSta & Num, DnSta & Num=  ,3820, 2 ,3820, 2 , 0 , 0 , 0 ,,
     1.2     1.2
       0     410
     1.2     1.2
       0     410
Pier Skew, UpSta & Num, DnSta & Num=  ,3835, 2 ,3835, 2 , 0 , 0 , 0 ,,
     1.2     1.2
       0     410
     1.2     1.2
       0     410
Pier Skew, UpSta & Num, DnSta & Num=  ,3850, 2 ,3850, 2 , 0 , 0 , 0 ,,
     1.2     1.2
       0     410
     1.2     1.2
       0     410
Pier Skew, UpSta & Num, DnSta & Num=  ,3865, 2 ,3865, 2 , 0 , 0 , 0 ,,
     1.2     1.2
       0     410
     1.2     1.2
       0     410
Pier Skew, UpSta & Num, DnSta & Num=  ,3880, 2 ,3880, 2 , 0 , 0 , 0 ,,
     1.2     1.2
       0     410
     1.2     1.2
       0     410
Pier Skew, UpSta & Num, DnSta & Num=  ,3895, 2 ,3895, 2 , 0 , 0 , 0 ,,
     1.2     1.2
       0     410
     1.2     1.2
       0     410
Pier Skew, UpSta & Num, DnSta & Num=  ,3910, 2 ,3910, 2 , 0 , 0 , 0 ,,
       3       3
       0     410
       3       3
       0     410
Pier Skew, UpSta & Num, DnSta & Num=  ,3926, 2 ,3926, 2 , 0 , 0 , 0 ,,
     1.2     1.2
       0     410
     1.2     1.2
       0     410
Pier Skew, UpSta & Num, DnSta & Num=  ,3941, 2 ,3941, 2 , 0 , 0 , 0 ,,
     1.2     1.2
       0     410
     1.2     1.2
       0     410
Pier Skew, UpSta & Num, DnSta & Num=  ,3956, 2 ,3956, 2 , 0 , 0 , 0 ,,
     1.2     1.2
       0     410
     1.2     1.2
       0     410
Pier Skew, UpSta & Num, DnSta & Num=  ,3971, 2 ,3971, 2 , 0 , 0 , 0 ,,
     1.2     1.2
       0     410
     1.2     1.2
       0     410
Pier Skew, UpSta & Num, DnSta & Num=  ,3986, 2 ,3986, 2 , 0 , 0 , 0 ,,
     1.2     1.2
       0     410
     1.2     1.2
       0     410
Pier Skew, UpSta & Num, DnSta & Num=  ,4001, 2 ,4001, 2 , 0 , 0 , 0 ,,
     1.2     1.2
       0     410
     1.2     1.2
       0     410
Pier Skew, UpSta & Num, DnSta & Num=  ,4016, 2 ,4016, 2 , 0 , 0 , 0 ,,
     1.2     1.2
       0     410
     1.2     1.2
       0     410
Pier Skew, UpSta & Num, DnSta & Num=  ,4031, 2 ,4031, 2 , 0 , 0 , 0 ,,
     1.2     1.2
       0     410
     1.2     1.2
       0     410
Pier Skew, UpSta & Num, DnSta & Num=  ,4046, 2 ,4046, 2 , 0 , 0 , 0 ,,
     1.2     1.2
       0     410
     1.2     1.2
       0     410
Pier Skew, UpSta & Num, DnSta & Num=  ,4061, 2 ,4061, 2 , 0 , 0 , 0 ,,
     1.2     1.2
       0     410
     1.2     1.2
       0     410
Pier Skew, UpSta & Num, DnSta & Num=  ,4076, 2 ,4076, 2 , 0 , 0 , 0 ,,
     1.2     1.2
       0     410
     1.2     1.2
       0     410
Pier Skew, UpSta & Num, DnSta & Num=  ,4091, 2 ,4091, 2 , 0 , 0 , 0 ,,
     1.2     1.2
       0     410
     1.2     1.2
       0     410
BR Coef= 1 , 0 , 0 ,1.05, 0 ,,,0.8,-1,0.5,1,
WSPro=,,,, 1 ,,,, 0 ,,,, 0 ,,,,-1 ,-1 ,-1 , 0 , 0 , 0 , 0 , 0
BC Design=,, 0 ,, 0 ,,,,,,
BC HTab HWMax=419
BC Use User HTab Curves=0
BC User HTab FreeFlow(D)= 0

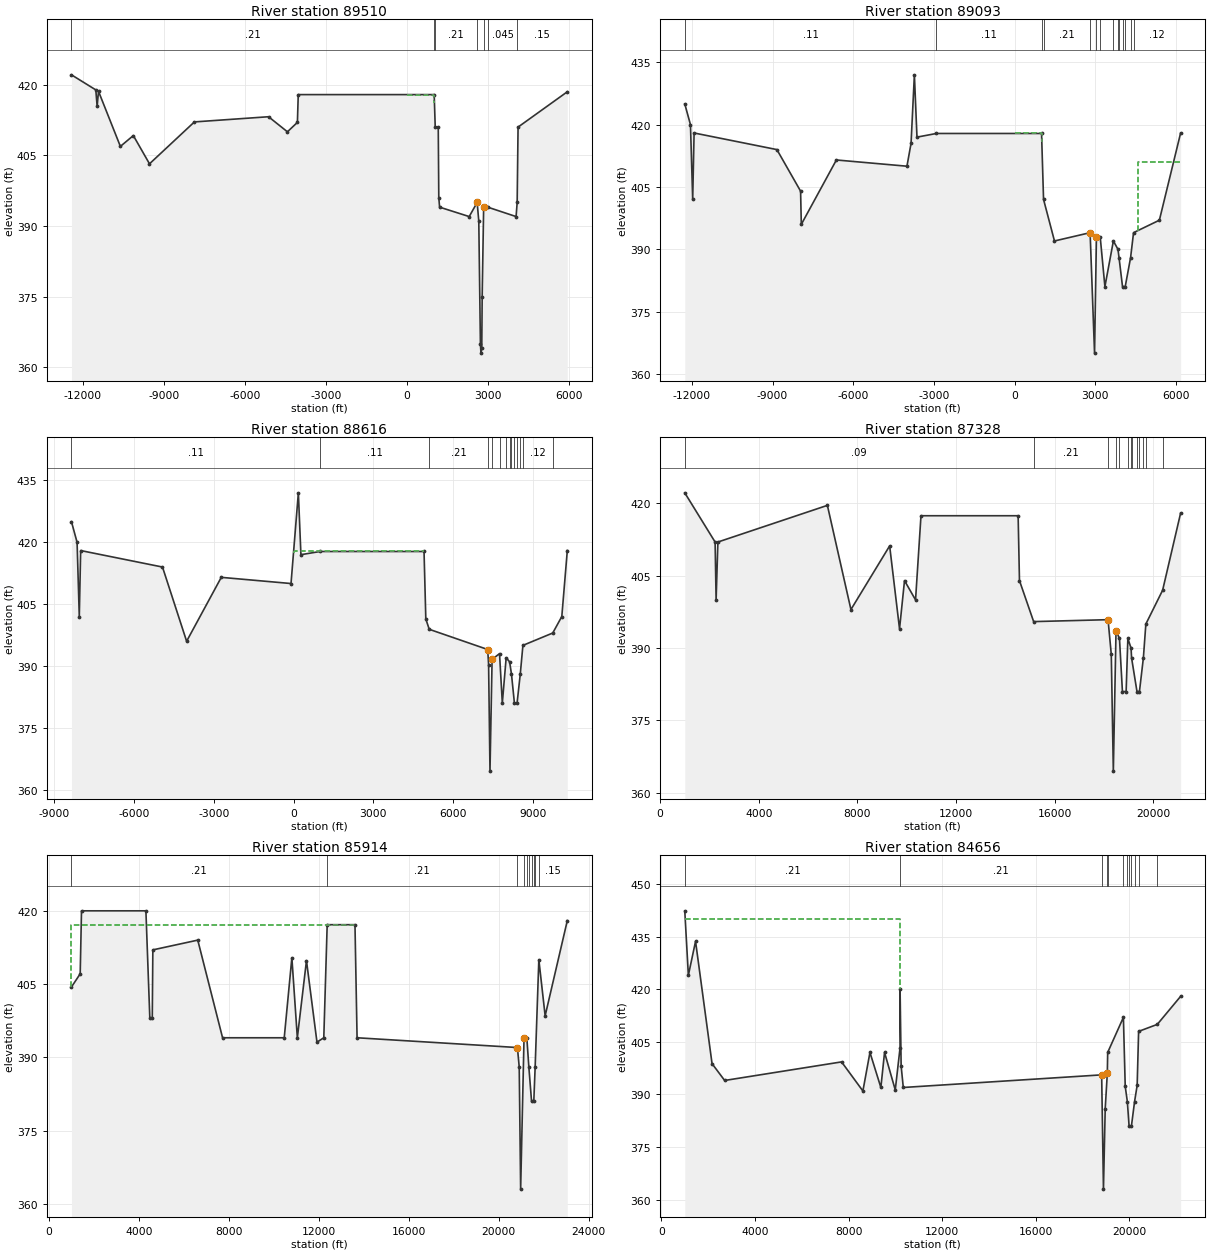
Type RM Length L Ch R = 1 ,89510   ,478,417,339
BEGIN DESCRIPTION:
This cross section corresponds to cross section 89527 of the non-georeferenced CDC model which was the source of this model.
END DESCRIPTION:
XS GIS Cut Line= 6
2505072.772038856967485.777382632504847.424392436959548.29719463
2504560.284546766956615.987442462504529.697665666955873.67691922
 2504897.26320356953474.729945472505616.634796266949247.79975104
#Sta/Elev= 30
-12420.9   422.1  -11520   418.9-11470.7   415.4-11420.4   418.6  -10611   406.9
-10131.3   409.2 -9533.5   403.2 -7871.9   412.1   -5129   413.2 -4430.7     410
 -4060.9     412   -4030   417.9    1000   417.9    1038     411    1150     411
    1170     396    1200     394    2295     392    2590     395    2650     391
    2710     365    2730     363    2760     364    2775     375    2830     394
    2980     394    4030     392    4070     395    4103     411    5925   418.5
#Mann= 7 ,-1,0
-12420.9     .21       0    1000    .035       0    1038     .21       0
    2590     .07       0    2830     .21       0    2980    .045       0
    4070     .15       0
#XS Ineff= 2 , 0
       0    1010   417.9               0
Permanent Ineff=
       F       F
Bank Sta=2590,2830
XS Rating Curve= 0 ,0
Exp/Cntr=0.5,0.3

Type RM Length L Ch R = 1 ,89093   ,456,477,327
BEGIN DESCRIPTION:
This cross section corresponds to cross section 89108 of the non-georeferenced CDC model which was the source of this model.
END DESCRIPTION:
XS GIS Cut Line= 6
 2505402.50267866967523.582097052505112.19879726 6956745.9924318
2505068.927886436956232.005270792505530.209444176952459.97606947
2505449.998646596952244.493888882505960.305040666949180.38781238
#Sta/Elev= 30
-12264.4     425-12052.8     420-11969.9     402  -11918     418 -8839.7     414
 -7958.9     404 -7931.9     396 -6628.1   411.5 -4004.4     410 -3851.9   415.5
 -3728.2     432 -3631.7     417   -2910  417.88    1000  417.88    1074     402
    1480     392    2805     394    2970     365    3040     393    3180     393
    3355     381    3670     392    3840     390    3880     388    4010     381
    4110     381    4310     388    4420     394    5380     397    6170     418
#Mann= 14 ,-1,0
-12264.4     .11       0   -2910     .11       0    1000    .035       0
    1074     .21       0    2805     .07       0    3040     .21       0
    3180     .07       0    3670     .15       0    3840    .035       0
    3880    .045       0    4010    .025       0    4110    .045       0
    4310    .035       0    4420     .12       0
#XS Ineff= 2 , 0
       0    1010  417.88    4580       0     411
Permanent Ineff=
       F       F
Bank Sta=2805,3040
XS Rating Curve= 0 ,0
Exp/Cntr=0.3,0.1

Type RM Length L Ch R = 1 ,88616   ,1175,1288,1145
BEGIN DESCRIPTION:
This cross section corresponds to cross section 88626 of the non-georeferenced CDC model which was the source of this model.
END DESCRIPTION:
XS GIS Cut Line= 6
2505886.171658756967798.805627972505678.745564436958428.03204672
2505721.02861634 6957305.60745432505941.999959176952156.99996938
2505799.99991509 6952008.99993732506018.152037836949217.87297364
#Sta/Elev= 30
 -8354.4     425 -8142.8     420 -8059.9     402   -8008     418 -4929.7     414
 -4021.9     396 -2718.1   411.5   -94.4     410   181.8     432   278.3     417
    1000  417.77    4910  417.77    4977   401.4  5105.5   398.9  7305.3     394
  7338.9   390.3    7391   364.5  7470.5   391.6    7750     393    7855     381
    8000     392    8130     391    8200     388    8310     381    8410     381
    8530     388    8630     395  9752.5     398 10093.1     402   10300     418
#Mann= 14 ,-1,0
 -8354.4     .11       0    1000     .11       0  5105.5     .21       0
  7305.3     .07       0  7470.5     .21       0    7750     .07       0
    8000     .15       0    8130    .035       0    8200    .045       0
    8310    .025       0    8410    .045       0    8530    .035       0
    8630     .12       0  9752.5     .16       0
#XS Ineff= 2 , 0
       0    4910  417.77               0
Permanent Ineff=
       F       F
Bank Sta=7305.3,7470.5
XS Rating Curve= 0 ,0
Exp/Cntr=0.5,0.3

Type RM Length L Ch R = 1 ,87328   ,1526,1414,998
BEGIN DESCRIPTION:
This cross section corresponds to cross section 87333 of the non-georeferenced CDC model which was the source of this model.
END DESCRIPTION:
XS GIS Cut Line= 6
2507418.728961086968830.000744042507291.642273016962971.53378646
2507090.097072426954882.923651382507025.000089766951583.00013313
2506955.999899696951433.000105052506945.390340836948739.73679081
#Sta/Elev= 30
    1000   422.2    2230     412  2270.9     400  2343.5     412  6783.8   419.6
  7738.9     398  9309.1   411.2  9709.8     394  9911.9     404 10359.4     400
   10580  417.45   14520  417.45   14574     404 15149.1   395.5 18166.4   395.9
 18297.9   388.7   18381   364.5 18490.3   393.6   18630     392   18750     381
   18900     381   18970     392   19100     390   19120     388   19340     381
   19440     381   19600     388   19700     395   20380     402   21110     418
#Mann= 13 ,-1,0
    1000     .09       0 15149.1     .21       0 18166.4    .065       0
 18490.3     .21       0   18630     .07       0   18970     .15       0
   19100    .035       0   19120    .045       0   19340    .025       0
   19440    .045       0   19600    .035       0   19700    .095       0
   20380     .16       0
#XS Ineff= 2 , 0
       0   14520  417.45               0
Permanent Ineff=
       F       F
Bank Sta=18166.4,18490.3
XS Rating Curve= 0 ,0
Exp/Cntr=0.3,0.1

Type RM Length L Ch R = 1 ,85914   ,1670,1258,1000
BEGIN DESCRIPTION:
This cross section corresponds to cross section 85916 of the non-georeferenced CDC model which was the source of this model.
END DESCRIPTION:
XS GIS Cut Line= 6
2512340.097071086970185.006892292511845.153507176967991.07000722
2510522.318226346962346.479590392509074.472040686955664.17340122
2507901.999976166950111.000124382507528.35603842 6948668.4121303
#Sta/Elev= 30
    1000   404.4  1388.9   407.1  1446.6     420  4310.6     420  4485.2     398
  4593.9     398  4619.1     412  6616.4     414  7719.8     394 10461.9     394
 10801.5   410.4 11044.9     394 11450.8   409.8 11917.9   393.1 12221.1     394
   12372  417.16   13608  417.16   13701     394 20831.6     392 20911.6     388
   20975     363 21125.7     394   21250     394   21340     388   21460     381
   21560     381   21620     388   21784     410 22064.5   398.5   23050     418
#Mann= 10 ,-1,0
    1000     .21       0   12372     .21       0 20831.6    .065       0
 21125.7     .15       0   21250    .035       0   21340    .045       0
   21460    .025       0   21560    .045       0   21620    .035       0
   21784     .15       0
#XS Ineff= 2 , 0
       0   13608  417.16               0
Permanent Ineff=
       F       F
Bank Sta=20831.6,21125.7
XS Rating Curve= 0 ,0
Exp/Cntr=0.3,0.1

Type RM Length L Ch R = 1 ,84656   ,1498,1275,799
BEGIN DESCRIPTION:
This cross section corresponds to cross section 84658 of the non-georeferenced CDC model which was the source of this model.
END DESCRIPTION:
XS GIS Cut Line= 6
2516603.637428496967153.40468781 2514754.10175756962886.64878564
2512856.483833586958684.984288722509280.99984285 6950942.0001028
2509218.999966836950639.00005263 2507591.31293356948014.49381872
#Sta/Elev= 30
    1000   442.4  1153.3     424  1460.3   433.7  2165.6   398.8  2704.1     394
  7699.7   399.3  8611.1     391  8912.3     402  9378.5     392  9536.2     402
  9993.9   391.3 10198.5   403.3   10200     420 10245.2   398.1 10337.1     392
 18812.8   395.6   18890     363   18965     386 19054.3     396 19070.9     402
   19742     412   19820   392.3   19910     388   19985     381   20085     381
   20220     388   20330   392.6   20392     408   21190     410   22187     418
#Mann= 12 ,-1,0
    1000     .21       0   10200     .21       0 18812.8     .06       0
 19054.3     .17       0 19070.9      .1       0   19742    .035       0
   19910    .045       0   19985    .025       0   20085    .045       0
   20220    .035       0   20392     .08       0   21190     .13       0
#XS Ineff= 2 , 0
       0   10200     440               0
Permanent Ineff=
       F       F
Bank Sta=18812.8,19054.3
XS Rating Curve= 0 ,0
Exp/Cntr=0.3,0.1

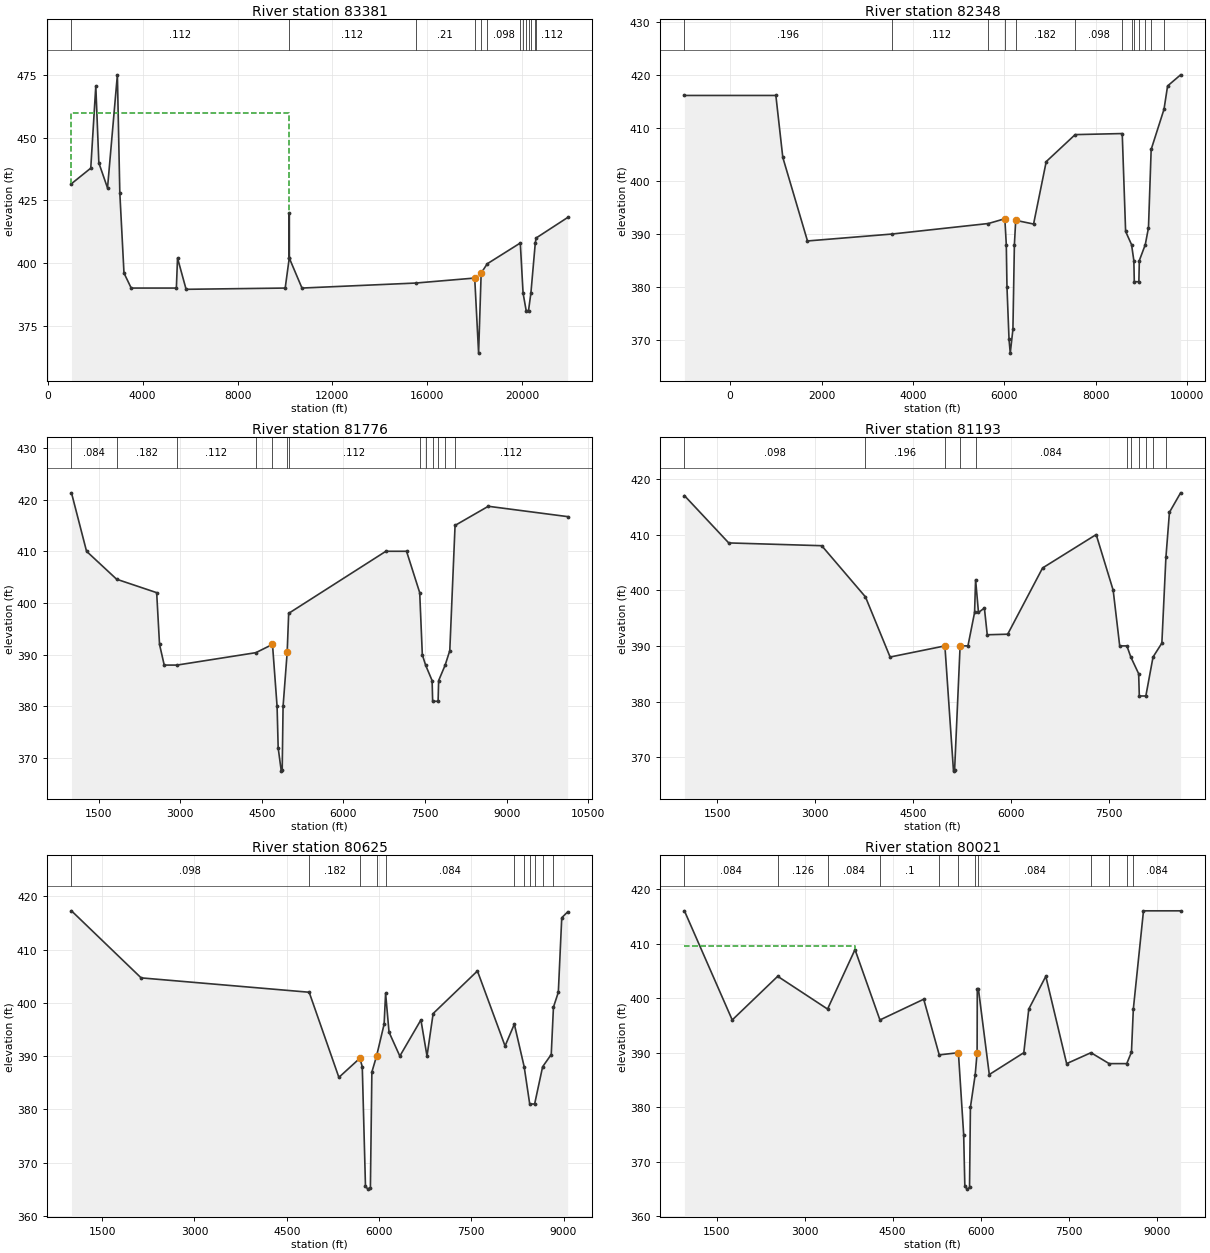
Type RM Length L Ch R = 1 ,83381   ,1367,1033,577
BEGIN DESCRIPTION:
This cross section corresponds to cross section 83381 of the non-georeferenced CDC model which was the source of this model.
END DESCRIPTION:
XS GIS Cut Line= 6
2522243.842355436963163.442851472515563.888851856957511.37344697
2515263.054151686957093.211553632510527.999973516951068.00017889
2510512.000005516950768.000122712507894.286408936948165.88426396
#Sta/Elev= 30
    1000   431.7  1813.1   437.9  2025.7   470.7  2154.1     440  2519.6     430
  2935.5   475.2  3038.2     428  3213.9     396  3518.5     390  5422.6     390
  5471.3     402  5832.9   389.5 10010.9     390 10181.9     402   10182     420
 10182.9     402 10718.5     390   15510     392 18001.2     394   18165     364
   18273     396   18530   399.7   19923     408   20040     388   20170     381
   20270     381   20370     388   20555     408   20590     410   21920   418.2
#Mann= 13 ,-1,0
    1000    .112       0   10182    .112       0   15510     .21       0
 18001.2     .06       0   18273    .182       0   18530    .098       0
   19923    .035       0   20040    .045       0   20170    .025       0
   20270    .045       0   20370    .035       0   20555    .098       0
   20590    .112       0
#XS Ineff= 2 , 0
       0   10182     460               0
Permanent Ineff=
       F       F
Bank Sta=18001.2,18273
XS Rating Curve= 0 ,0
Exp/Cntr=0.3,0.1

Type RM Length L Ch R = 1 ,82348   ,701,572,381
BEGIN DESCRIPTION:
82361  White Rock Creek
END DESCRIPTION:
XS GIS Cut Line= 5
2517791.478261546953326.148350372515791.668251936953353.71509564
2514972.999941776953365.000178052509759.999869086949431.00017205
2508562.88513735 6948521.8238408
#Sta/Elev= 30
   -1000   416.2    1000   416.2  1151.7   404.5  1691.6   388.7    3530     390
  5649.7     392  6008.3   392.9  6040.2     388    6055     380    6100   370.1
    6127   367.5    6185     372  6217.3     388  6246.3   392.6  6636.9   391.9
  6913.6   403.7  7546.4   408.8    8576     409    8650   390.5    8780     388
    8830     385    8840     381    8940     381    8950     385    9080     388
    9150   391.2    9209     406    9490   413.6  9568.3     418  9852.8   420.1
#Mann= 13 ,-1,0
   -1000    .196       0    3530    .112       0  5649.7    .182       0
  6008.3     .06       0  6246.3    .182       0  7546.4    .098       0
    8576    .035       0    8780    .045       0    8840    .025       0
    8940    .045       0    9080    .035       0    9209    .098       0
    9490     .14       0
Bank Sta=6008.3,6246.3
XS Rating Curve= 0 ,0
Exp/Cntr=0.3,0.1

Type RM Length L Ch R = 1 ,81776   ,753,583,401
BEGIN DESCRIPTION:
This cross section corresponds to cross section 81790 of the non-georeferenced CDC model which was the source of this model.
END DESCRIPTION:
XS GIS Cut Line= 3
2515199.83741459 6952326.90284482510356.999987426949433.00016806
 2507378.16211316947633.09792797
#Sta/Elev= 30
    1000   421.3    1277     410    1830   404.6  2566.3     402  2618.7     392
    2705     388    2940     388    4390   390.4  4695.6     392    4780     380
    4800     372    4857   367.5    4874   367.7    4890     380  4965.7   390.5
    4993     398    6780     410    7160     410    7402     402    7450     390
    7510     388    7630     385    7640     381    7740     381    7750     385
    7870     388    7955   390.8    8052     415    8663   418.7   10122   416.7
#Mann= 13 ,-1,0
    1000    .084       0    1830    .182       0    2940    .112       0
    4390    .182       0  4695.6     .06       0  4965.7    .196       0
    4993    .112       0    7402    .035       0    7510    .045       0
    7640    .025       0    7740    .045       0    7870    .035       0
    8052    .112       0
Bank Sta=4695.6,4965.7
XS Rating Curve= 0 ,0
Exp/Cntr=0.3,0.1

Type RM Length L Ch R = 1 ,81193   ,650,568,350
BEGIN DESCRIPTION:
This cross section corresponds to cross section 81209 of the non-georeferenced CDC model which was the source of this model.
END DESCRIPTION:
XS GIS Cut Line= 3
2515997.262000836951544.647191462511215.999909856949434.00016604
2509056.391696246948469.01817213
#Sta/Elev= 30
    1000     417  1677.9   408.5  3100.8     408    3770   398.8    4147     388
  4985.3     390    5117   367.5    5134   367.7  5218.1     390  5338.1     390
  5439.5     396    5455   401.9  5499.2     396  5589.7   396.8  5633.3     392
  5946.2   392.1    6480     404    7300     410    7560     400    7660     390
    7770     390    7830     388    7950     385    7960     381    8060     381
    8170     388    8305   390.5    8367   405.9  8421.1     414  8591.8   417.5
#Mann= 11 ,-1,0
    1000    .098       0    3770    .196       0  4985.3     .06       0
  5218.1    .182       0    5455    .084       0    7770    .035       0
    7830    .045       0    7960    .025       0    8060    .045       0
    8170    .035       0    8367    .084       0
#XS Ineff= 2 , 0
          4985.3     390  5218.1             390
Permanent Ineff=
       F       F
Bank Sta=4985.3,5218.1
XS Rating Curve= 0 ,0
Exp/Cntr=0.3,0.1

Type RM Length L Ch R = 1 ,80625   ,799,604,400
BEGIN DESCRIPTION:
This cross section corresponds to cross section 80641 of the non-georeferenced CDC model which was the source of this model.
END DESCRIPTION:
XS GIS Cut Line= 3
2516826.689147746950716.07699822 2512684.99992466949454.00012605
2509105.140614516948380.72963481
#Sta/Elev= 30
    1000   417.3  2132.5   404.7  4864.4     402  5347.6     386  5688.9   389.6
  5727.7     388    5780   365.5    5820     365    5860   365.3  5883.8     387
    5960     390  6082.9     396    6107   401.8  6162.9   394.5  6338.4     390
  6681.2   396.8  6780.2     390    6880     398    7600     406  8049.3   391.9
    8200     396    8360     388    8450     381    8530     381    8660     388
    8800   390.3    8836   399.2  8915.3     402  8970.8     416    9067   417.1
#Mann= 11 ,-1,0
    1000    .098       0  4864.4    .182       0  5688.9     .06       0
    5960    .182       0    6107    .084       0    8200    .035       0
    8360    .045       0    8450    .025       0    8530    .045       0
    8660    .035       0    8836    .084       0
#XS Ineff= 2 , 0
          5688.9   389.6    5960             390
Permanent Ineff=
       F       F
Bank Sta=5688.9,5960
XS Rating Curve= 0 ,0
Exp/Cntr=0.3,0.1

Type RM Length L Ch R = 1 ,80021   ,623,688,603
BEGIN DESCRIPTION:
This cross section corresponds to cross section 80036 of the non-georeferenced CDC model which was the source of this model.
END DESCRIPTION:
XS GIS Cut Line= 2
2516952.853593596949419.146521212508585.724002426948184.02595997
#Sta/Elev= 30
     950     416    1765     396    2540     404    3390     398  3857.8   408.9
  4282.5     396  5028.8   399.8  5293.4   389.6  5620.3     390    5710     375
    5730   365.5    5770     365    5810   365.3    5825     380  5906.9     386
    5939     390    5942   401.7    5961   401.7  6146.8     386    6735     390
    6820     398    7110     404  7465.2     388    7880     390    8190     388
    8490     388    8570   390.1    8602     398    8775     416  9407.8     416
#Mann= 12 ,-1,0
     950    .084       0    2540    .126       0    3390    .084       0
  4282.5      .1       0  5293.4    .196       0  5620.3     .06       0
  5906.9    .182       0    5961    .084       0    7880    .035       0
    8190    .045       0    8490    .035       0    8602    .084       0
#XS Ineff= 2 , 0
       0    3850   409.5    5939       0     390
Permanent Ineff=
       F       F
Bank Sta=5620.3,5939
XS Rating Curve= 0 ,0
Exp/Cntr=0.3,0.1