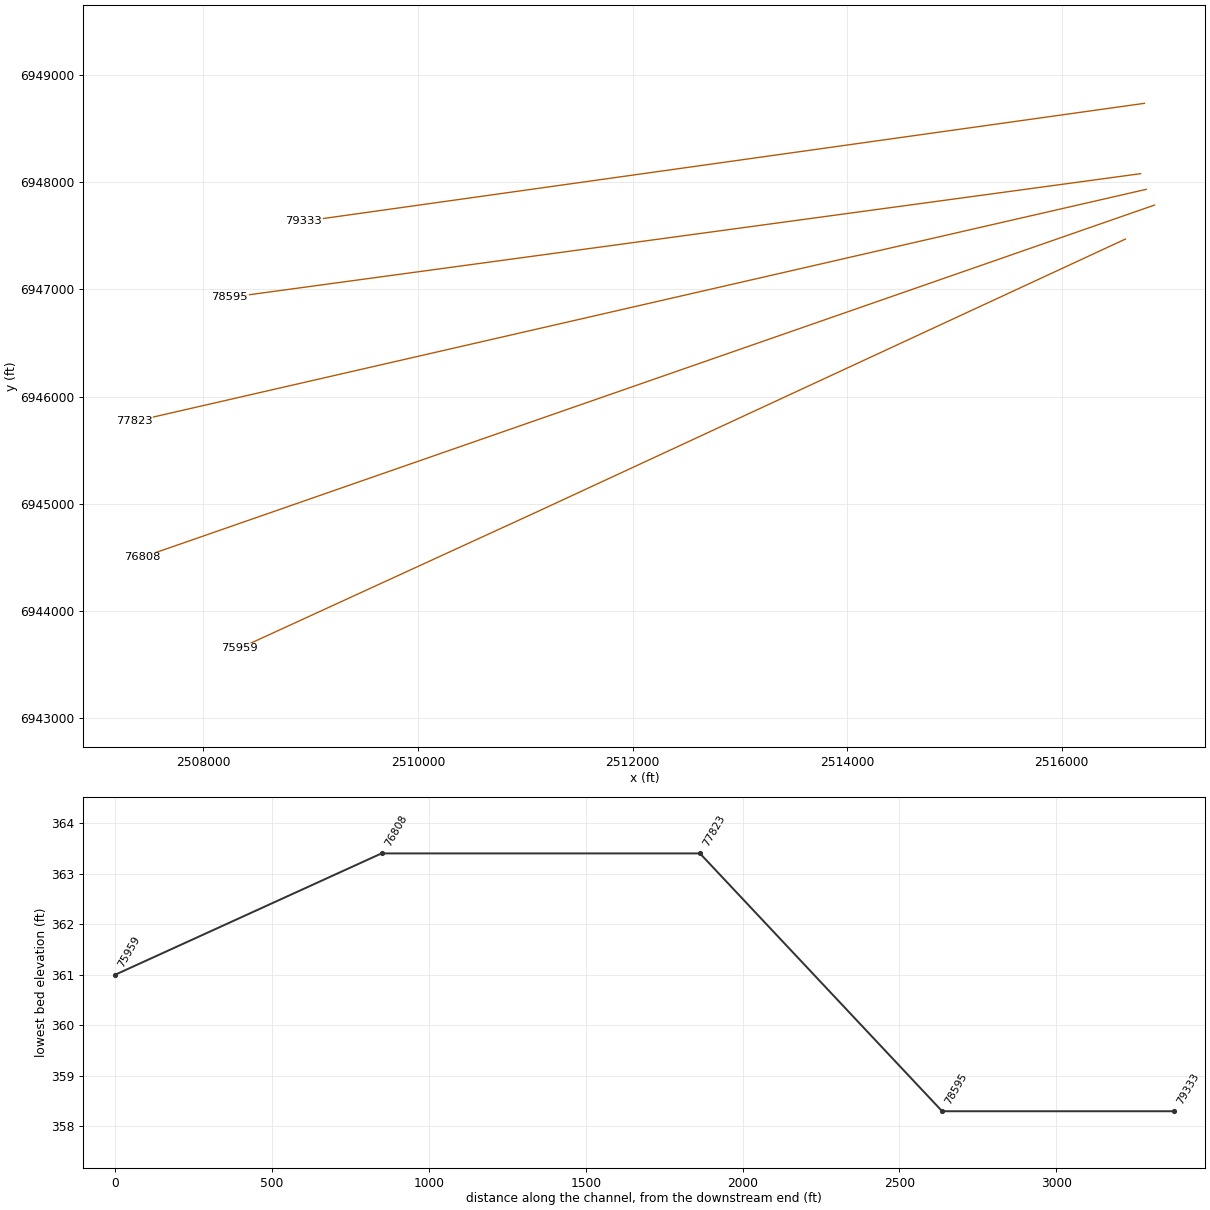
HEC-RAS study CDC_Consolidated_Model.prj: Upper Trinity CDC Consolidated Model

--- CDC_Consolidated_Model.g01 (geometry) --- (continued)

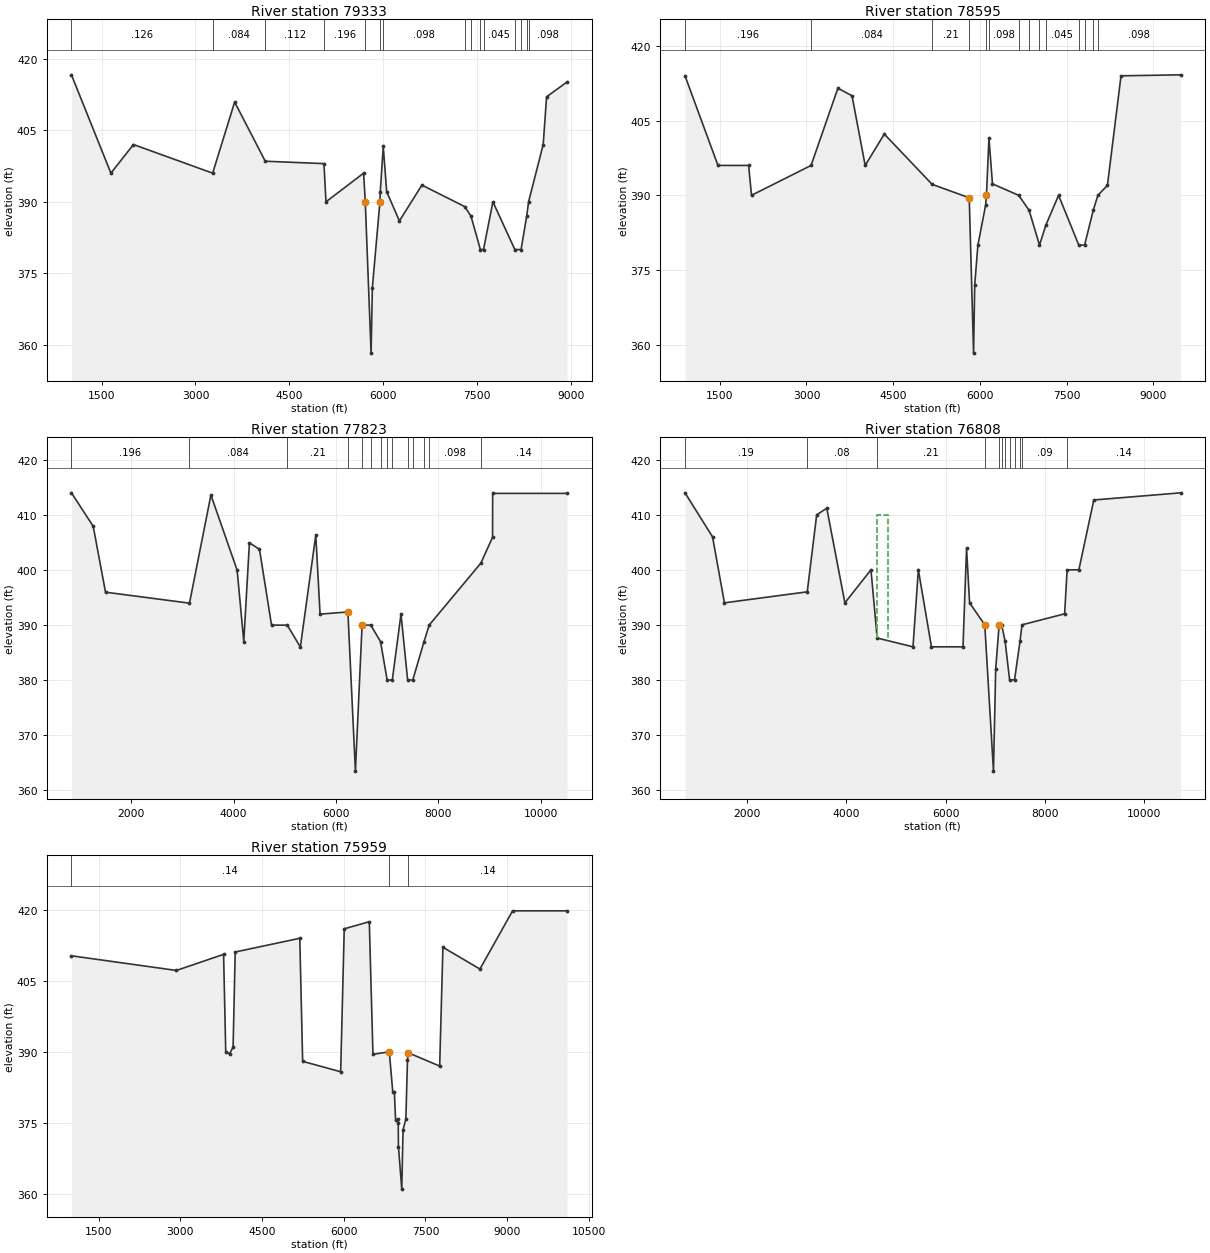
Type RM Length L Ch R = 1 ,79333   ,630,738,620
BEGIN DESCRIPTION:
This cross section corresponds to cross section 79352 of the non-georeferenced CDC model which was the source of this model.
END DESCRIPTION:
XS GIS Cut Line= 2
2516772.977969086948736.487781552508935.312870176947636.34234405
#Sta/Elev= 30
    1020   416.6    1650     396    2010     402    3275     396  3626.1   410.9
    4115   398.5    5052     398  5084.9     390  5685.5     396  5712.1     390
    5805   358.3    5825     372    5946     390  5951.4     392    5999   401.6
  6054.2   392.1  6257.1     386  6616.7   393.5    7300     389    7400     387
    7550     380    7600     380    7750     390    8100     380    8200     380
    8290     387    8320     390  8553.3     402  8607.4     412  8934.5   415.1
#Mann= 15 ,-1,0
    1020    .126       0    3275    .084       0    4115    .112       0
    5052    .196       0  5712.1     .06       0  5951.4    .182       0
    5999    .098       0    7300    .035       0    7400    .045       0
    7550    .025       0    7600    .045       0    8100    .025       0
    8200    .045       0    8290    .035       0    8320    .098       0
#XS Ineff= 2 , 0
       0    3600   409.2    5946       0     390
Permanent Ineff=
       F       F
Bank Sta=5712.1,5946
XS Rating Curve= 0 ,0
Exp/Cntr=0.3,0.1

Type RM Length L Ch R = 1 ,78595   ,501,772,751
BEGIN DESCRIPTION:
This cross section corresponds to cross section 78614 of the non-georeferenced CDC model which was the source of this model.
END DESCRIPTION:
XS GIS Cut Line= 3
2516736.886505846948080.255170142509234.95498744 6947060.6732198
2508244.064642646946926.00204774
#Sta/Elev= 30
     900     414    1470     396    2000     396    2050     390    3080     396
  3543.7   411.5  3787.9     410  4015.8     396    4346   402.3  5173.7   392.2
  5815.3   389.5    5890   358.3    5910     372    5965     380  6098.3     388
    6113     390    6156   401.5    6217   392.3    6670     390    6850     387
    7030     380    7140     384    7360     390    7710     380    7810     380
    7960     387    8040     390    8205     392  8439.9     414  9470.9   414.2
#Mann= 14 ,-1,0
     900    .196       0    3080    .084       0  5173.7     .21       0
  5815.3     .06       0  6098.3    .182       0    6156    .098       0
    6670    .035       0    6850    .045       0    7030    .025       0
    7140    .045       0    7710    .025       0    7810    .045       0
    7960    .035       0    8040    .098       0
#XS Ineff= 2 , 0
       0    3500     409    6113       0     390
Permanent Ineff=
       F       F
Bank Sta=5815.3,6113
XS Rating Curve= 0 ,0
Exp/Cntr=0.3,0.1

Type RM Length L Ch R = 1 ,77823   ,647,1015,877
BEGIN DESCRIPTION:
This cross section corresponds to cross section 77843 of the non-georeferenced CDC model which was the source of this model.
END DESCRIPTION:
XS GIS Cut Line= 3
2516789.376558336947934.081249882508331.202529856945993.21111588
2507356.533944346945769.55703383
#Sta/Elev= 30
     835   414.1    1260     408    1500     396    3140     394  3558.3   413.7
  4070.7     400    4200     387  4310.3     405  4506.9   403.8    4742     390
    5050     390  5304.6     386  5606.2   406.4  5689.9     392  6233.1   392.4
    6380   363.4  6510.4     390    6680     390    6870     387    7000     380
    7100     380    7270     392    7400     380    7500     380    7720     387
    7820     390    8830   401.3    9058     406    9060     414   10513     414
#Mann= 14 ,-1,0
     835    .196       0    3140    .084       0    5050     .21       0
  6233.1     .06       0  6510.4     .08       0    6680    .035       0
    6870    .045       0    7000    .025       0    7100    .045       0
    7400    .025       0    7500    .045       0    7720    .035       0
    7820    .098       0    8830     .14       0
#XS Ineff= 2 , 0
       0    3500   408.5  6510.4       0     390
Permanent Ineff=
       F       F
Bank Sta=6233.1,6510.4
XS Rating Curve= 0 ,0
Exp/Cntr=0.3,0.1

Type RM Length L Ch R = 1 ,76808   ,696,849,855
BEGIN DESCRIPTION:
This cross section corresponds to cross section 76824 of the non-georeferenced CDC model which was the source of this model.
---------------------------------------------------------------------
CDC DAL070601-1 Dallas Floodway Extension
From Loop 12 to ATSF Railroad
Cross-section 76824 - 108276
---------------------------------------------------------------------
END DESCRIPTION:
XS GIS Cut Line= 3
2516865.623453086947786.952935222508371.72213385 6944829.6442173
2507427.325714096944500.83515061
#Sta/Elev= 30
     745     414    1300     406    1540     394    3210     396    3400     410
  3603.8   411.2  3968.9     394  4494.6     400  4620.1   387.6  5342.3     386
    5450     400  5714.2     386  6350.4     386    6422   403.9  6483.4     394
  6789.6     390    6965   363.4    7010     382    7079     390    7130     390
    7200     387    7290     380    7390     380    7500     387    7540     390
    8400     392    8450     400    8687     400  8988.2   412.7   10739     414
#Mann= 12 ,-1,0
     745     .19       0    3210     .08       0  4620.1     .21       0
  6789.6    .055       0    7079     .08       0    7130    .035       0
    7200    .045       0    7290    .025       0    7390    .045       0
    7500    .035       0    7540     .09       0    8450     .14       0
#XS Ineff= 2 ,-1
    1000    3500     408    4620    4830     410
Permanent Ineff=
       F       F
Bank Sta=6789.6,7079
XS Rating Curve= 0 ,0
Exp/Cntr=0.3,0.1

Type RM Length L Ch R = 1 ,75959   ,82,82,82
BEGIN DESCRIPTION:
This cross section corresponds to cross section 75970 of the non-georeferenced CDC model which was the source of this model.
END DESCRIPTION:
XS GIS Cut Line= 4
2516595.093810416947469.943398642511100.582161676944921.17126521
2509243.767961926944068.794032962508334.95123467 6943651.5984478
#Sta/Elev= 30
    1000   410.3    2927   407.2  3793.4   410.6    3833     390    3903   389.6
    3968     391  4006.6   411.1  5192.4     414    5245     388    5943   385.8
  6008.6     416  6468.4   417.5    6536   389.5    6836     390    6900   381.5
    6929   381.5    6952   375.5    6994   375.8    7000     375    7004     370
    7065     361    7088   373.5    7140   375.8    7170   388.3    7186   389.8
    7761     387  7820.6   412.1    8500   407.5    9100   419.8   10100   419.8
#Mann= 3 ,0,0
    1000     .14       0    6836    .055       0    7186     .14       0
Bank Sta=6836,7186
XS Rating Curve= 0 ,0
Exp/Cntr=0.3,0.1