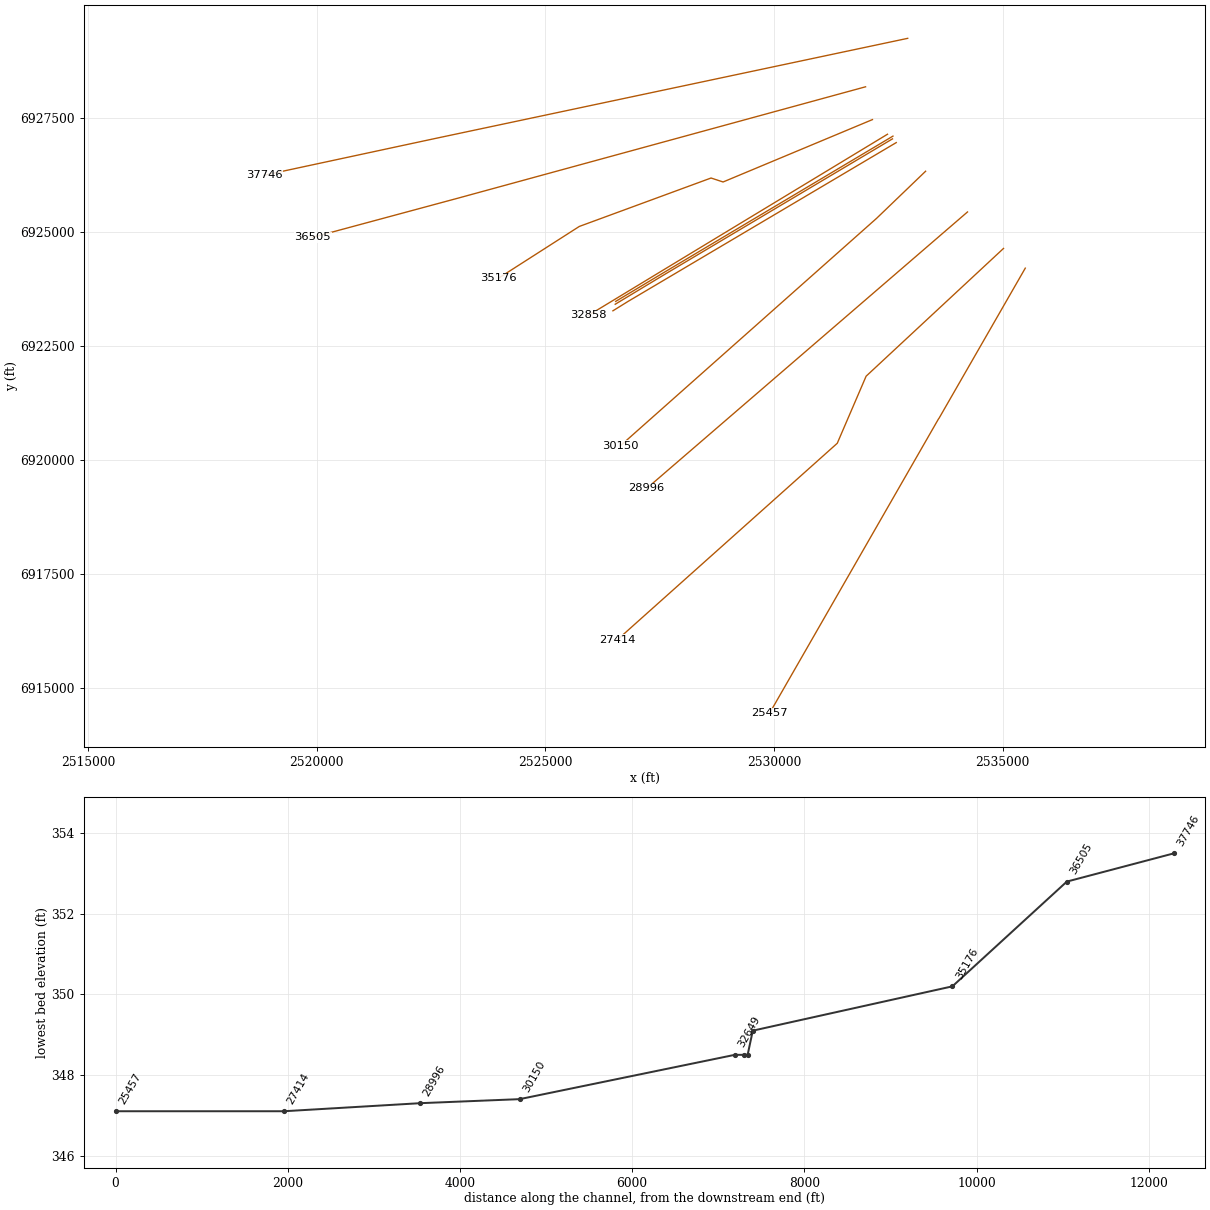
HEC-RAS study CDC_Consolidated_Model.prj: Upper Trinity CDC Consolidated Model

--- CDC_Consolidated_Model.g01 (geometry) --- (continued)

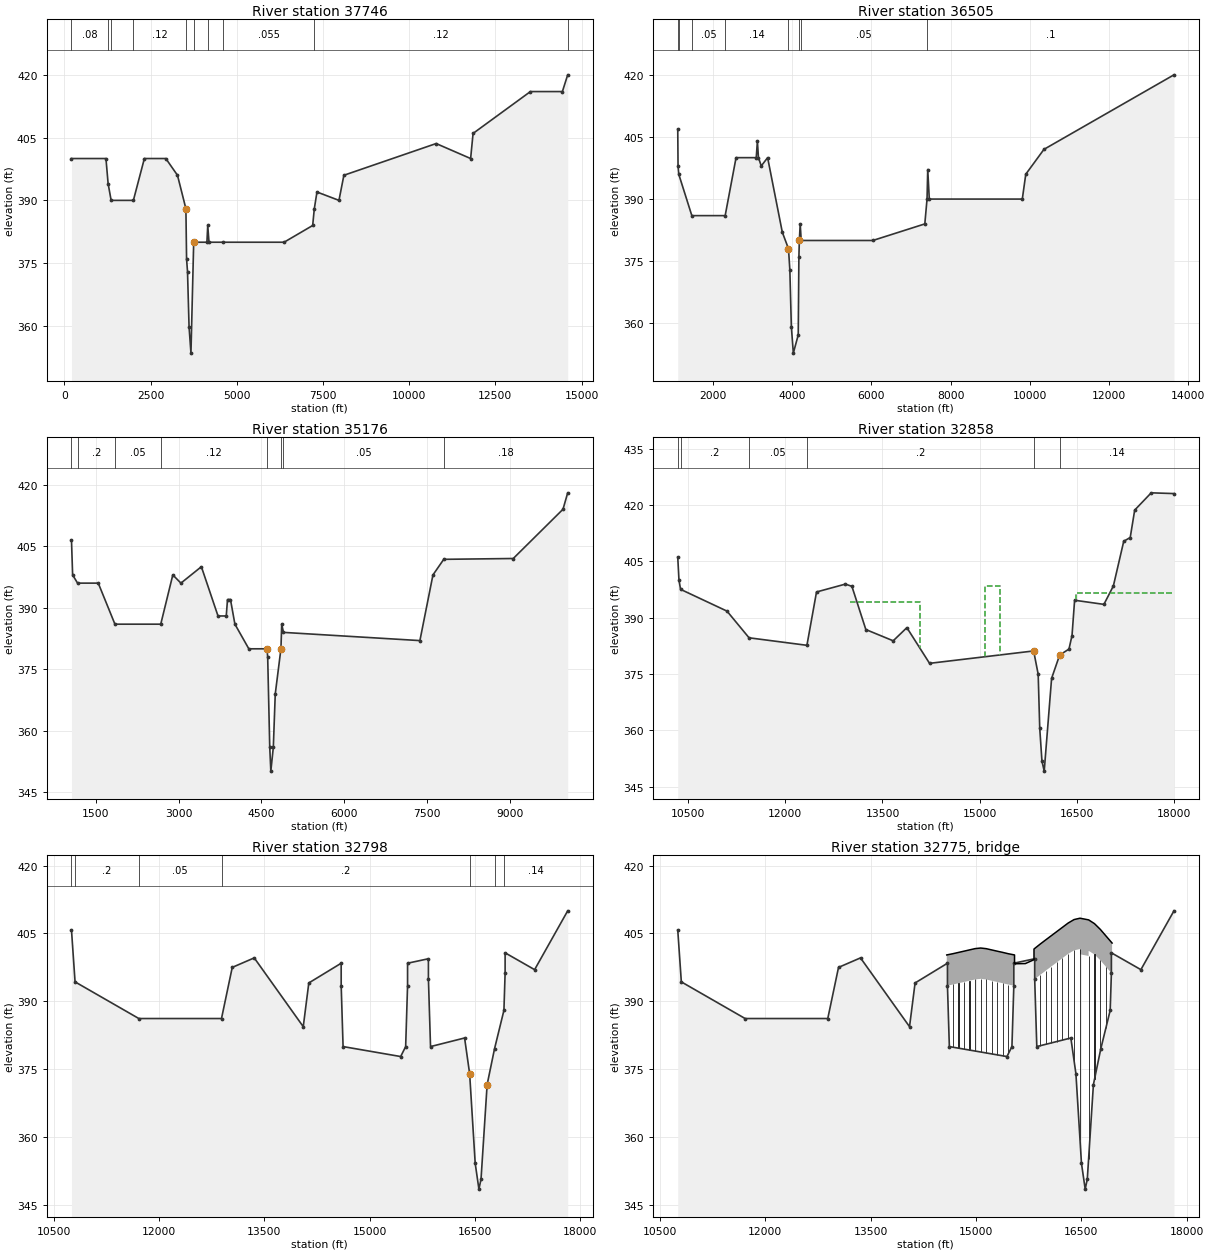
Type RM Length L Ch R = 1 ,37746   ,960,1241,1260
BEGIN DESCRIPTION:
This cross section corresponds to cross section 37760 of the non-georeferenced CDC model which was the source of this model.
END DESCRIPTION:
XS GIS Cut Line= 4
2532926.589845656929248.149480832531948.441056436929040.24338147
2522565.999847596927045.999994642518848.287794836926245.29293463
#Sta/Elev= 30
     204     400    1204     400  1266.9     394  1354.7     390  1999.9     390
  2318.6     400  2940.7     400    3279     396  3523.6     388  3542.8     376
    3570     373    3615   359.8    3670   353.5  3749.5     380  4133.3     380
  4156.8     384  4193.4     380  4599.5     380  6371.5     380    7201     384
  7248.3     388  7325.8     392  7963.8     390  8106.1     396   10783  403.58
   11783     400   11854     406   13518     416   14445     416   14599     420
#Mann= 10 ,-1,0
     204     .08       0  1266.9     .08       0  1354.7     .05       0
  1999.9     .12       0  3523.6    .055       0  3749.5      .2       0
  4156.8     .05       0  4599.5    .055       0  7248.3     .12       0
   14599       2       0
#XS Ineff= 2 , 0
          3523.6     388  3749.5             380
Permanent Ineff=
       F       F
Bank Sta=3523.6,3749.5
XS Rating Curve= 0 ,0
Exp/Cntr=0.3,0.1

Type RM Length L Ch R = 1 ,36505   ,951,1329,1302
BEGIN DESCRIPTION:
This cross section corresponds to cross section 36519 of the non-georeferenced CDC model which was the source of this model.
END DESCRIPTION:
XS GIS Cut Line= 3
 2532005.15419766928185.576127542523073.000145916925737.99998596
 2519915.63113266924884.57649596
#Sta/Elev= 30
  1108.9   406.9  1116.4     398  1134.2     396  1464.7     386  2306.4     386
  2581.6     400  3091.6     400  3120.2     404  3147.1     400    3218     398
  3378.7     400  3749.4     382  3905.9     378    3940   372.9    3978   359.2
    4028   352.8    4152   357.2  4168.3     376  4179.8     380  4201.7     384
  4226.5     380  6035.5     380  7348.6     384  7404.8     390  7422.4  397.13
  7461.8     390  9810.8     390  9898.4     396   10357     402   13641     420
#Mann= 8 ,-1,0
  1108.9     .03       0  1134.2      .1       0  1464.7     .05       0
  2306.4     .14       0  3905.9    .055       0  4179.8      .2       0
  4226.5     .05       0  7404.8      .1       0
#XS Ineff= 2 , 0
          3905.9     378  4179.8             380
Permanent Ineff=
       F       F
Bank Sta=3905.9,4179.8
XS Rating Curve= 0 ,0
Exp/Cntr=0.3,0.1

Type RM Length L Ch R = 1 ,35176   ,849,2318,1797
BEGIN DESCRIPTION:
This cross section corresponds to cross section 35192 of the non-georeferenced CDC model which was the source of this model.
END DESCRIPTION:
XS GIS Cut Line= 5
2532155.647334936927466.298694712528888.999996846926097.99992213
2528625.999866666926185.000076222525745.000051266925123.00023171
2523980.464538346923989.68852197
#Sta/Elev= 30
  1059.7   406.5  1080.5     398  1170.1     396  1544.8     396  1846.7     386
  2676.3     386  2894.7     398  3041.7     396    3412     400  3713.4     388
  3862.6     388  3885.2     392  3939.2     392  4019.4     386  4271.3     380
  4599.5     380    4613     378    4650   356.1    4670   350.2    4715     356
    4750     369    4853     380    4867     386  4898.5     384  7369.4     382
  7605.9     398  7801.3   401.8  9060.1     402    9961     414   10046     418
#Mann= 8 ,-1,0
  1059.7     .03       0  1170.1      .2       0  1846.7     .05       0
  2676.3     .12       0  4599.5    .055       0    4853      .2       0
  4898.5     .05       0  7801.3     .18       0
#XS Ineff= 2 , 0
          4599.5     380    4853             380
Permanent Ineff=
       F       F
Bank Sta=4599.5,4853
XS Rating Curve= 0 ,0
Exp/Cntr=0.3,0.1

Type RM Length L Ch R = 1 ,32858   ,60,60,60
BEGIN DESCRIPTION:
This cross section corresponds to cross section 32870 of the non-georeferenced CDC model which was the source of this model.
END DESCRIPTION:
XS GIS Cut Line= 2
 2532484.41898716927145.076568132525940.685355426923170.92441146
#Sta/Elev= 30
   10341   406.1   10360   399.9   10385   397.5   11101   391.7   11441   384.6
   12334   382.6   12482   396.8   12928   398.9   13028   398.3   13243   386.8
   13665   383.8   13876   387.3   14226   377.8   15832   381.1   15902   374.9
   15926   360.5   15960   351.8   15995   349.1   16109   373.8   16233     380
   16377   381.6   16424   385.2   16464   394.6   16916   393.5   17062   398.4
   17222   410.3   17322   411.3   17391   418.6   17646   423.2   17997     423
#Mann= 6 ,-1,0
   10341     .03       0   10385      .2       0   11441     .05       0
   12334      .2       0   15832    .055       0   16233     .14       0
#XS Ineff= 3 ,-1
   13000   14085     394   15085   15320   398.3   16480   17997   396.6
Permanent Ineff=
       F       F       F
Bank Sta=15832,16233
XS Rating Curve= 0 ,0
Exp/Cntr=0.3,0.1

Type RM Length L Ch R = 1 ,32798   ,47,47,47
BEGIN DESCRIPTION:
This cross section corresponds to cross section 32796 of the non-georeferenced CDC model which was the source of this model.
END DESCRIPTION:
XS GIS Cut Line= 3
2532603.880034276927103.952306552527617.459232846924126.36967905
2526539.912503426923478.69938646
#Sta/Elev= 30
   10755   405.8   10806   394.3   11714   386.2   12891   386.2   13044   397.5
   13357   399.6   14055   384.4   14134  394.06   14595  398.42   14595  393.44
   14622     380   15442   377.8   15513     380   15540  393.44   15540  398.42
   15837  399.41   15837  394.95   15867     380   16352   381.9   16424     374
   16503   354.2   16556   348.5   16586   350.7   16673   371.6   16778   379.5
   16912     388   16929  396.27   16929  400.72   17349     397   17820     410
#Mann= 7 ,-1,0
   10755     .03       0   10806      .2       0   11714     .05       0
   12891      .2       0   16424    .055       0   16778      .2       0
   16912     .14       0
#XS Ineff= 1 ,-1
   13500   14134     394
Permanent Ineff=
       F
Bank Sta=16424,16673
XS Rating Curve= 0 ,0
Exp/Cntr=0.3,0.1

Type RM Length L Ch R = 3 ,32775   ,,,
BEGIN DESCRIPTION:
32772  Dowdy-Ferry Road
Bridge data revised May 2002 from bridge plans dated 12-98 supplied by TXDOT.  Bridge plans supplied in metric, therefore stationing and elevations were converted to english prior to input.  Main bridge length is 1092.2 ft. (333.0 m) and relief bridge length is 944.6 ft (288.0m).
END DESCRIPTION:
Node Name=Dowdy-Ferry Road
Bridge Culvert--1,0,-1,-1, 0
Deck Dist Width WeirC Skew NumUp NumDn MinLoCord MaxHiCord MaxSubmerge Is_Ogee
1.5,44,2.6,0, 33, 33, , , 0.95, 0, ,,,
   14585   14674   14753   14832   14910   14989   15068   15146   15225   15304
   15383   15461   15550   15550   15571   15703   15827   15827   15916   15994
   16073   16152   16231   16314   16398   16482   16482   16605   16605   16688
   16772   16851   16939
  400.25  400.53  400.81  401.09  401.37  401.65  401.78  401.64  401.36  401.08
  400.81  400.52  400.25  398.42  398.31  398.34   399.2  401.56  402.66  403.58
   404.5  405.42  406.34  407.31  408.07  408.37  408.37     408     408  407.17
  405.89  404.46  402.88
  393.44  393.72     394  394.28  394.56  394.84  394.97  394.83  394.55  394.27
     394  393.71  393.44  398.42  398.31  398.34   399.2  394.75  395.85  396.77
  397.69  398.61  399.53   400.5  401.26  401.56   400.4  400.02  401.17  400.36
  399.08  397.65  396.07
   14585   14674   14753   14832   14910   14989   15068   15146   15225   15304
   15383   15461   15550   15550   15571   15703   15827   15827   15916   15994
   16073   16152   16231   16314   16398   16482   16482   16605   16605   16688
   16772   16851   16939
  400.25  400.53  400.81  401.09  401.37  401.65  401.78  401.64  401.36  401.08
  400.81  400.52  400.25  398.42  398.31  398.34   399.2  401.56  402.66  403.58
   404.5  405.42  406.34  407.31  408.07  408.37  408.37     408     408  407.17
  405.89  404.46  402.88
  393.44  393.72     394  394.28  394.56  394.84  394.97  394.83  394.55  394.27
     394  393.71  393.44  398.42  398.31  398.34   399.2  394.75  395.85  396.77
  397.69  398.61  399.53   400.5  401.26  401.56   400.4  400.02  401.17  400.36
  399.08  397.65  396.07
Pier Skew, UpSta & Num, DnSta & Num=  ,14674, 2 ,14674, 2 , 0 , 0 , 0 ,,
     2.5     2.5
       0     396
     2.5     2.5
       0     396
Pier Skew, UpSta & Num, DnSta & Num=  ,14753, 2 ,14753, 2 , 0 , 0 , 0 ,,
     2.5     2.5
       0     396
     2.5     2.5
       0     396
Pier Skew, UpSta & Num, DnSta & Num=  ,14832, 2 ,14832, 2 , 0 , 0 , 0 ,,
     2.5     2.5
       0     396
     2.5     2.5
       0     396
Pier Skew, UpSta & Num, DnSta & Num=  ,14910, 2 ,14910, 2 , 0 , 0 , 0 ,,
     2.5     2.5
       0     396
     2.5     2.5
       0     396
Pier Skew, UpSta & Num, DnSta & Num=  ,14989, 2 ,14989, 2 , 0 , 0 , 0 ,,
     2.5     2.5
       0     396
     2.5     2.5
       0     396
Pier Skew, UpSta & Num, DnSta & Num=  ,15068, 2 ,15068, 2 , 0 , 0 , 0 ,,
     2.5     2.5
       0     396
     2.5     2.5
       0     396
Pier Skew, UpSta & Num, DnSta & Num=  ,15146, 2 ,15146, 2 , 0 , 0 , 0 ,,
     2.5     2.5
       0     396
     2.5     2.5
       0     396
Pier Skew, UpSta & Num, DnSta & Num=  ,15225, 2 ,15225, 2 , 0 , 0 , 0 ,,
     2.5     2.5
       0     396
     2.5     2.5
       0     396
Pier Skew, UpSta & Num, DnSta & Num=  ,15304, 2 ,15304, 2 , 0 , 0 , 0 ,,
     2.5     2.5
       0     396
     2.5     2.5
       0     396
Pier Skew, UpSta & Num, DnSta & Num=  ,15383, 2 ,15383, 2 , 0 , 0 , 0 ,,
     2.5     2.5
       0     396
     2.5     2.5
       0     396
Pier Skew, UpSta & Num, DnSta & Num=  ,15461, 2 ,15461, 2 , 0 , 0 , 0 ,,
     2.5     2.5
       0     396
     2.5     2.5
       0     396
Pier Skew, UpSta & Num, DnSta & Num=  ,15916, 2 ,15916, 2 , 0 , 0 , 0 ,,
     2.5     2.5
       0     400
     2.5     2.5
       0     400
Pier Skew, UpSta & Num, DnSta & Num=  ,15994, 2 ,15994, 2 , 0 , 0 , 0 ,,
     2.5     2.5
       0     400
     2.5     2.5
       0     400
Pier Skew, UpSta & Num, DnSta & Num=  ,16073, 2 ,16073, 2 , 0 , 0 , 0 ,,
     2.5     2.5
       0     400
     2.5     2.5
       0     400
Pier Skew, UpSta & Num, DnSta & Num=  ,16152, 2 ,16152, 2 , 0 , 0 , 0 ,,
     2.5     2.5
       0     401
     2.5     2.5
       0     401
Pier Skew, UpSta & Num, DnSta & Num=  ,16231, 2 ,16231, 2 , 0 , 0 , 0 ,,
     2.5     2.5
       0     401
     2.5     2.5
       0     401
Pier Skew, UpSta & Num, DnSta & Num=  ,16314, 2 ,16314, 2 , 0 , 0 , 0 ,,
     2.5     2.5
       0     402
     2.5     2.5
       0     402
Pier Skew, UpSta & Num, DnSta & Num=  ,16398, 2 ,16398, 2 , 0 , 0 , 0 ,,
     2.5     2.5
       0     403
     2.5     2.5
       0     403
Pier Skew, UpSta & Num, DnSta & Num=  ,16482, 2 ,16482, 2 , 0 , 0 , 0 ,,
     3.5     3.5
       0     403
     3.5     3.5
       0     403
Pier Skew, UpSta & Num, DnSta & Num=  ,16605, 2 ,16605, 2 , 0 , 0 , 0 ,,
     3.5     3.5
       0     403
     3.5     3.5
       0     403
Pier Skew, UpSta & Num, DnSta & Num=  ,16688, 2 ,16688, 2 , 0 , 0 , 0 ,,
     2.5     2.5
       0     403
     2.5     2.5
       0     403
Pier Skew, UpSta & Num, DnSta & Num=  ,16772, 2 ,16772, 2 , 0 , 0 , 0 ,,
     2.5     2.5
       0     403
     2.5     2.5
       0     403
Pier Skew, UpSta & Num, DnSta & Num=  ,16851, 2 ,16851, 2 , 0 , 0 , 0 ,,
     2.5     2.5
       0     403
     2.5     2.5
       0     403
BR Coef= 1 , 0 , 0 ,1.05, 0 ,,,0.8,-1,0.5,1,
WSPro=,,,, 1 ,,,, 0 ,,,, 0 ,,,,-1 ,-1 ,-1 , 0 , 0 , 0 , 0 , 0
BC Design=,, 0 ,, 0 ,,,,,,
BC HTab HWMax=410
BC Use User HTab Curves=0
BC User HTab FreeFlow(D)= 0

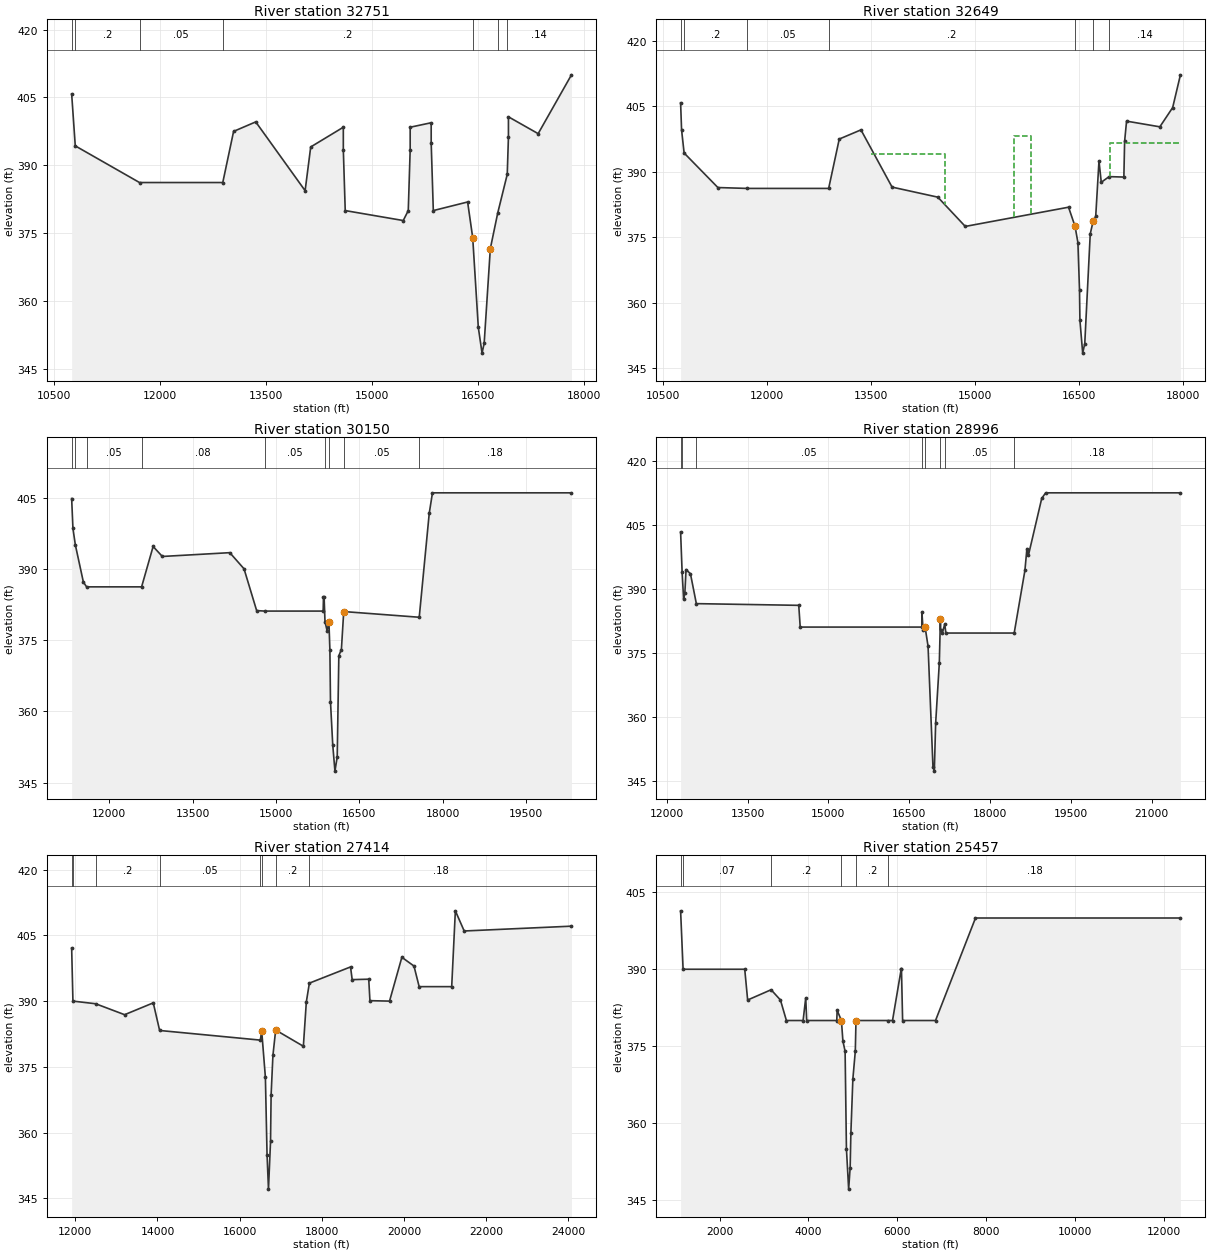
Type RM Length L Ch R = 1 ,32751   ,102,102,102
BEGIN DESCRIPTION:
This cross section corresponds to cross section 32748 of the non-georeferenced CDC model which was the source of this model.
END DESCRIPTION:
XS GIS Cut Line= 3
  2532593.520803 6927043.47112832527625.427064666924079.38912997
2526530.35117084 6923416.9134208
#Sta/Elev= 30
   10755   405.8   10806   394.3   11714   386.2   12891   386.2   13044   397.5
   13357   399.6   14055   384.4   14134  394.06   14595  398.42   14595  393.44
   14622     380   15442   377.8   15513     380   15540  393.44   15540  398.42
   15837  399.41   15837  394.95   15867     380   16352   381.9   16424     374
   16503   354.2   16556   348.5   16586   350.7   16673   371.6   16778   379.5
   16912     388   16929  396.27   16929  400.72   17349     397   17820     410
#Mann= 7 ,-1,0
   10755     .03       0   10806      .2       0   11714     .05       0
   12891      .2       0   16424    .055       0   16778      .2       0
   16912     .14       0
#XS Ineff= 1 ,-1
   13500   14134     394
Permanent Ineff=
       F
Bank Sta=16424,16673
XS Rating Curve= 0 ,0
Exp/Cntr=0.3,0.1

Type RM Length L Ch R = 1 ,32649   ,1449,2499,2298
BEGIN DESCRIPTION:
This cross section corresponds to cross section 32658 of the non-georeferenced CDC model which was the source of this model.
END DESCRIPTION:
XS GIS Cut Line= 3
2532676.001937276926961.907643142526802.99990377 6923473.9999208
2526480.132767356923272.92781638
#Sta/Elev= 30
   10755   405.8   10769   399.6   10806   394.3   11293   386.4   11714   386.2
   12891   386.2   13044   397.5   13357   399.6   13806   386.5   14466   384.2
   14862   377.5   16352   381.9   16446   377.5   16487   373.8   16510     363
   16516     356   16556   348.5   16586   350.7   16665   375.8   16707   378.7
   16744   379.8   16791   392.5   16824   387.6   16937   388.9   17150   388.8
   17161     397   17189   401.6   17669   400.3   17854   404.7   17966   412.2
#Mann= 7 ,-1,0
   10755     .03       0   10806      .2       0   11714     .05       0
   12891      .2       0   16446    .055       0   16707      .2       0
   16937     .14       0
#XS Ineff= 3 ,-1
   13500   14575     394   15560   15817   398.3   16950   17966   396.5
Permanent Ineff=
       F       F       F
Bank Sta=16446,16707
XS Rating Curve= 0 ,0
Exp/Cntr=0.3,0.1

Type RM Length L Ch R = 1 ,30150   ,1200,1154,1130
BEGIN DESCRIPTION:
This cross section corresponds to cross section 30157 of the non-georeferenced CDC model which was the source of this model.
END DESCRIPTION:
XS GIS Cut Line= 4
2533318.201440246926333.938426632532243.99984851 6925299.0002078
2528511.396421346921976.166630392526644.106699696920313.87029838
#Sta/Elev= 30
   11325   404.8   11348   398.5   11392     395   11536   387.2   11594   386.2
   12583   386.2   12790   394.7   12956   392.6   14169   393.4   14425     390
   14652   381.2   14798   381.1   15848   381.1   15854   384.1   15865   384.1
   15881   378.9   15918     377   15952   378.7   15969     373   15980     362
   16020     353   16060   347.4   16101   350.4   16130   371.7   16176     373
   16218     381   17576   379.8   17756   401.7   17814     406   20314     406
#Mann= 9 ,-1,0
   11325     .03       0   11392      .2       0   11594     .05       0
   12583     .08       0   14798     .05       0   15881      .2       0
   15952    .055       0   16218     .05       0   17576     .18       0
#XS Ineff= 2 , 0
           15952   378.7   16218             381
Permanent Ineff=
       F       F
Bank Sta=15952,16218
XS Rating Curve= 0 ,0
Exp/Cntr=0.3,0.1

Type RM Length L Ch R = 1 ,28996   ,1245,1582,1992
BEGIN DESCRIPTION:
This cross section corresponds to cross section 29003 of the non-georeferenced CDC model which was the source of this model.
END DESCRIPTION:
XS GIS Cut Line= 3
 2534234.07690516925440.849333552529110.048767336921011.64362505
2527218.705116846919376.76772892
#Sta/Elev= 30
   12258   403.4   12286     394   12314   387.7   12337   389.1   12359   394.6
   12441   393.6   12550   386.6   14450   386.2   14477   381.1   16733   381.1
   16735   384.6   16756   380.5   16794   381.1   16849   376.6   16940   348.3
   16965   347.3   16990   358.6   17058   372.7   17078     383   17082   380.5
   17115   379.8   17159   381.8   17179   379.7   18447   379.7   18646   394.4
   18683   399.5   18712     398   18958   411.3   19031   412.6   21531   412.6
#Mann= 8 ,-1,0
   12258     .03       0   12286     .16       0   12550     .05       0
   16733      .2       0   16794    .055       0   17078      .2       0
   17159     .05       0   18447     .18       0
#XS Ineff= 2 , 0
           16794   381.1   17078             383
Permanent Ineff=
       F       F
Bank Sta=16794,17078
XS Rating Curve= 0 ,0
Exp/Cntr=0.3,0.1

Type RM Length L Ch R = 1 ,27414   ,1300,1957,1999
BEGIN DESCRIPTION:
This cross section corresponds to cross section 27415 of the non-georeferenced CDC model which was the source of this model.
END DESCRIPTION:
XS GIS Cut Line= 5
2535021.79120892 6924641.00742932532016.999974436921839.00023805
2531385.99992409 6920368.00022732528440.778124246917728.59376071
2526578.997260126916060.12979226
#Sta/Elev= 30
   11911   402.1   11942     390   12494   389.4   13200   386.9   13897   389.6
   14052   383.3   16503   381.1   16536   383.2   16626   372.6   16666     355
   16701   347.1   16751     358   16765   368.6   16809   377.6   16876   383.4
   17550   379.7   17622   389.8   17696   394.1   18698   397.8   18738   394.9
   19141     395   19170   390.1   19647     390   19947     400   20242     398
   20368   393.3   21160   393.3   21249   410.6   21464     406   24075   407.1
#Mann= 8 ,-1,0
   11911     .03       0   11942     .08       0   12494      .2       0
   14052     .05       0   16503      .2       0   16536    .055       0
   16876      .2       0   17696     .18       0
#XS Ineff= 2 , 0
           16536   383.2   16876           383.4
Permanent Ineff=
       F       F
Bank Sta=16536,16876
XS Rating Curve= 0 ,0
Exp/Cntr=0.3,0.1

Type RM Length L Ch R = 1 ,25457   ,0,0,0
BEGIN DESCRIPTION:
This cross section corresponds to cross section 25457 of the non-georeferenced CDC model which was the source of this model.
END DESCRIPTION:
XS GIS Cut Line= 5
2535497.477593516924208.306194962533614.000061246920921.00010554
2533600.635914746920903.282293222531145.627045246916614.24133064
2529903.705690966914444.53366605
#Sta/Elev= 30
  1121.7   401.4  1177.8     390  2565.6     390  2631.2     384  3159.1     386
  3369.4     384  3503.5     380  3879.8     380  3938.8  384.42  3960.6     380
  4637.8     380  4645.8     382  4742.3     380  4775.5     376  4825.3     374
    4855     355    4905   347.1    4939  351.31    4955     358    5000   368.6
  5054.8     374  5070.4     380    5800     380  5892.7     380  6087.4     390
  6094.1     390  6120.1     380    6861     380  7760.7     400 12374.5     400
#Mann= 6 ,-1,0
  1121.7     .03       0  1177.8     .07       0  3159.1      .2       0
  4742.3    .055       0  5070.4      .2       0    5800     .18       0
#XS Ineff= 2 , 0
          4742.3     380  5070.4             380
Permanent Ineff=
       F       F
Bank Sta=4742.3,5070.4
XS Rating Curve= 0 ,0
Exp/Cntr=0.3,0.1
Stream Node=Elm Fork        ,ef6             , 0 , 0 ,Upstream end
Stream Node=Elm Fork        ,ef6             , 0 , 1 ,Downstream end
Stream Node=Elm Fork        ,ef5             , 0 , 0 ,Upstream end
Stream Node=Elm Fork        ,ef5             , 0 , 1 ,Downstream end
Stream Node=Elm Fork        ,ef4             , 0 , 0 ,Upstream end
Stream Node=Elm Fork        ,ef4             , 0 , 1 ,Downstream end
Stream Node=Elm Fork        ,ef3             , 0 , 0 ,Upstream end
Stream Node=Elm Fork        ,ef3             , 0 , 1 ,Downstream end
Stream Node=Elm Fork        ,ef2             , 0 , 0 ,Upstream end
Stream Node=Elm Fork        ,ef2             , 0 , 1 ,Downstream end
Stream Node=Elm Fork        ,ef1             , 0 , 0 ,Upstream end
Stream Node=Elm Fork        ,ef1             , 0 , 1 ,Downstream end
Stream Node=Elm Fork L-Spill,efl             , 0 , 0 ,Upstream end
Stream Node=Elm Fork L-Spill,efl             , 0 , 1 ,Downstream end
Stream Node=Elm Fork Split1 ,efs1            , 0 , 0 ,Upstream end
Stream Node=Elm Fork Split1 ,efs1            , 0 , 1 ,Downstream end
Stream Node=Elm Fork Split2 ,efs2            , 0 , 0 ,Upstream end
Stream Node=Elm Fork Split2 ,efs2            , 0 , 1 ,Downstream end
Stream Node=Main Stem       ,ms              , 0 , 0 ,Upstream end
Stream Node=Main Stem       ,ms              , 0 , 1 ,Downstream end
Stream Node=West Fork       ,wf3             , 0 , 0 ,Upstream end
Stream Node=West Fork       ,wf3             , 0 , 1 ,Downstream end
Stream Node=West Fork       ,wf3f            , 0 , 0 ,Upstream end
Stream Node=West Fork       ,wf3f            , 0 , 1 ,Downstream end
Stream Node=West Fork       ,wf3e            , 0 , 0 ,Upstream end
Stream Node=West Fork       ,wf3e            , 0 , 1 ,Downstream end
Stream Node=West Fork       ,wf3d            , 0 , 0 ,Upstream end
Stream Node=West Fork       ,wf3d            , 0 , 1 ,Downstream end
Stream Node=West Fork       ,wf3b            , 0 , 0 ,Upstream end
Stream Node=West Fork       ,wf3b            , 0 , 1 ,Downstream end
Stream Node=West Fork       ,wf3c            , 0 , 0 ,Upstream end
Stream Node=West Fork       ,wf3c            , 0 , 1 ,Downstream end
Stream Node=West Fork       ,wf3a            , 0 , 0 ,Upstream end
Stream Node=West Fork       ,wf3a            , 0 , 1 ,Downstream end
Stream Node=West Fork       ,wf2             , 0 , 0 ,Upstream end
Stream Node=West Fork       ,wf2             , 0 , 1 ,Downstream end
Stream Node=West Fork       ,wf1             , 0 , 0 ,Upstream end
Stream Node=West Fork       ,wf1             , 0 , 1 ,Downstream end
Stream Node=West Fork Split ,wfs             , 0 , 0 ,Upstream end
Stream Node=West Fork Split ,wfs             , 0 , 1 ,Downstream end
LCMann Table=0

Chan Stop Cuts=-1
Use User Specified Reach Order=0
User Specified Reach Order=Main Stem       ,ms
User Specified Reach Order=West Fork Split ,wfs
User Specified Reach Order=Elm Fork Split1 ,efs1
User Specified Reach Order=West Fork       ,wf1
User Specified Reach Order=West Fork       ,wf2
User Specified Reach Order=West Fork       ,wf3
User Specified Reach Order=West Fork       ,wf4
User Specified Reach Order=Clear Fork      ,cf
User Specified Reach Order=Elm Fork Split2 ,efs2
User Specified Reach Order=Elm Fork        ,ef1
User Specified Reach Order=Elm Fork        ,ef2
User Specified Reach Order=Elm Fork        ,ef3
User Specified Reach Order=Elm Fork        ,ef4
User Specified Reach Order=Elm Fork        ,ef5
User Specified Reach Order=Elm Fork        ,ef6
User Specified Reach Order=Elm Fork L-Spill,efl
Composite Channel Slope=5

--- CDC_Consolidated_Model.g02 (geometry) ---

Geom Title=Exist: 0.2% AEP [WF/EF/TRMS]
Program Version=6.60
BEGIN GEOM DESCRIPTION:
Existing: Geometry file for use with 0.2% AEP peak flows for the WF/EF/TRMS
END GEOM DESCRIPTION:

Junct Name=ef-wf
Junct Desc=, 0 , 0 , 0 ,0
Up River,Reach=Elm Fork        ,ef3 ds
Up River,Reach=West Fork       ,wf
Dn River,Reach=Main Stem       ,ms
Junc L&A=3030,20
Junc L&A=1494,0

Junct Name=ef5-ef4-efs2
Junct Desc=, 0 , 0 , 0 ,0
Up River,Reach=Elm Fork        ,ef5
Dn River,Reach=Elm Fork        ,ef4
Dn River,Reach=Elm Fork Split2 ,efs2
Junc L&A=2415,
Junc L&A=1129,

Junct Name=ef4-efs2-ef3
Junct Desc=, 0 , 0 , 0 ,0
Up River,Reach=Elm Fork        ,ef4
Up River,Reach=Elm Fork Split2 ,efs2
Dn River,Reach=Elm Fork        ,ef3
Junc L&A=513,
Junc L&A=1010,

Junct Name=ef6-efl-ef5
Junct Desc=, 0 , 0 , 0 ,0
Up River,Reach=Elm Fork        ,ef6
Up River,Reach=Elm Fork L-Spill,efl
Dn River,Reach=Elm Fork        ,ef5
Junc L&A=612,0
Junc L&A=2000,80

Junct Name=J2
Junct Desc=, 0 , 0 ,-1 ,0
Up River,Reach=Elm Fork        ,ef3
Dn River,Reach=Elm Fork        ,PGBT split west
Dn River,Reach=Elm Fork        ,PGBT split east
Junc L&A=741,0
Junc L&A=370,0

Junct Name=J1
Junct Desc=, 0 , 0 ,-1 ,0
Up River,Reach=Elm Fork        ,PGBT split west
Up River,Reach=Elm Fork        ,PGBT split east
Dn River,Reach=Elm Fork        ,ef3 ds
Junc L&A=1067,0
Junc L&A=1067,0

River Reach=Elm Fork L-Spill,efl
Reach XY= 30
      2451737.34      7074615.52      2451160.73      7070671.78
      2450672.18      7070144.08      2449903.65      7069914.65
      2449400.97      7069330.44      2448360.65      7069030.65
      2447453.37       7069372.2      2446791.42      7069358.45
      2446224.26      7069727.31      2445576.06      7069838.23
      2443448.88      7069483.23      2442684.97      7069013.34
       2442525.1      7069212.15      2441972.49      7069020.23
      2441526.94      7069208.05       2441203.1      7069005.14
      2440850.56      7069029.73      2440955.29      7068759.25
       2440630.7      7068827.13      2440501.92      7068571.07
      2441216.66      7068357.13      2441211.29       7068119.7
       2440934.6      7068021.32      2441088.32      7067781.51
      2440856.71      7067752.82       2440958.6       7067428.5
      2440655.07      7067329.59      2440432.53       7067546.2
      2439901.58      7067254.76      2439760.19      7066982.89

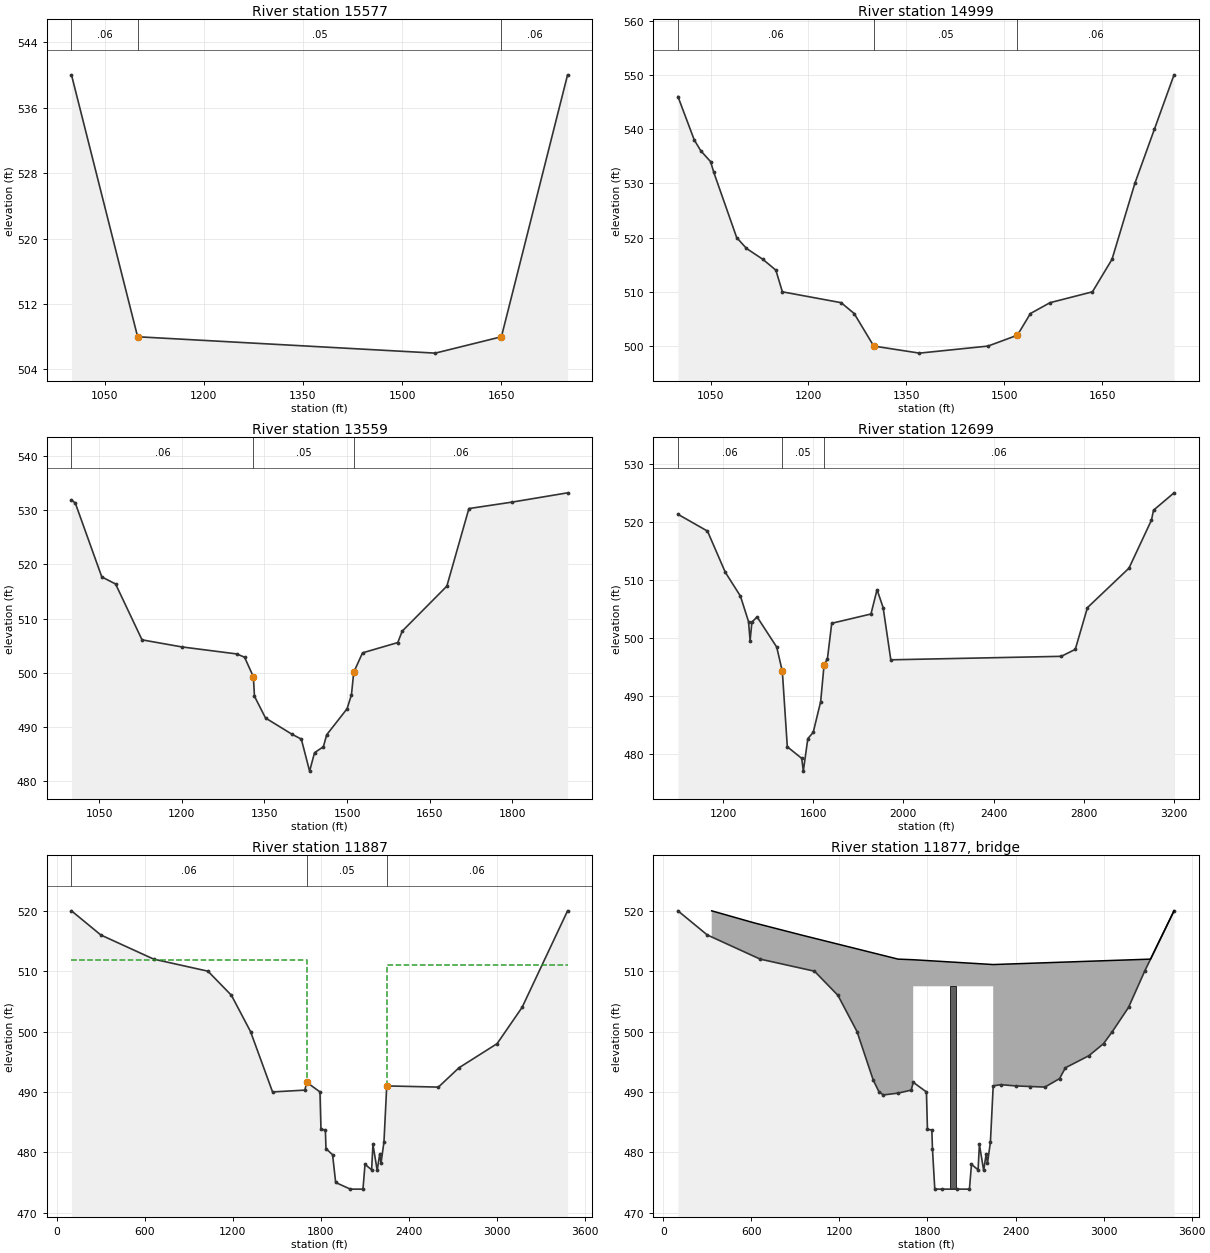
Type RM Length L Ch R = 1 ,15577   ,578,578,578
BEGIN DESCRIPTION:
This cross section corresponds to cross section 15590 of the non-georeferenced CDC model which was the source of this model.
END DESCRIPTION:
XS GIS Cut Line= 4
 2452088.23102657074382.826383382452048.285240267074384.91299339
2451350.368657087074421.371581882451339.251881427074421.95228939
#Sta/Elev= 5
    1000     540    1100     508    1550     506    1650     508    1750     540
#Mann= 3 ,0,0
    1000     .06       0    1100     .05       0    1650     .06       0
Bank Sta=1100,1650
XS Rating Curve= 0 ,0
Exp/Cntr=0.3,0.1

Type RM Length L Ch R = 1 ,14999   ,1440,1440,1440
BEGIN DESCRIPTION:
This cross section corresponds to cross section 15010 of the non-georeferenced CDC model which was the source of this model.
END DESCRIPTION:
XS GIS Cut Line= 2
2452061.263888847073781.360066642451306.078063257073866.76770422
#Sta/Elev= 23
    1000     546    1025     538    1035     536    1050     534    1055     532
    1090     520    1105     518    1130     516    1150     514    1160     510
    1250     508    1270     506    1300     500    1370   498.7    1475     500
    1520     502    1540     506    1570     508    1635     510    1665     516
    1700     530    1730     540    1760     550
#Mann= 3 ,0,0
    1000     .06       0    1300     .05       0    1520     .06       0
Bank Sta=1300,1520
XS Rating Curve= 0 ,0
Exp/Cntr=0.3,0.1

Type RM Length L Ch R = 1 ,13559   ,850,860,870
BEGIN DESCRIPTION:
This cross section corresponds to cross section 13580 of the non-georeferenced CDC model which was the source of this model.
END DESCRIPTION:
XS GIS Cut Line= 3
2451912.20742843 7072291.41685232451863.757722177072303.77148639
2451040.115996757072513.80453089
#Sta/Elev= 27
    1000   531.9    1007   531.3    1055   517.7    1080   516.4    1128   506.1
    1200   504.8    1300   503.5    1314   502.9    1330   499.3    1332   495.7
    1352   491.7    1400   488.7    1417   487.8    1432   481.9    1441   485.3
    1457   486.4    1463   488.6    1500   493.4    1508     496    1512   500.1
    1528   503.7    1592   505.6    1600   507.7    1681     516    1721   530.3
    1800   531.5    1900   533.2
#Mann= 3 ,0,0
    1000     .06       0    1330     .05       0    1512     .06       0
Bank Sta=1330,1512
XS Rating Curve= 0 ,0
Exp/Cntr=0.3,0.1

Type RM Length L Ch R = 1 ,12699   ,802,812,822
BEGIN DESCRIPTION:
This cross section corresponds to cross section 12720 of the non-georeferenced CDC model which was the source of this model.
END DESCRIPTION:
XS GIS Cut Line= 3
2451879.478491257071432.729593312451820.891666177071445.67510547
2449731.297092087071907.40482505
#Sta/Elev= 30
    1000   521.3    1131   518.4    1210   511.3    1277   507.2    1313   502.8
    1320   499.5    1328   502.7    1351   503.6    1438   498.4    1463   494.2
    1485   481.2    1549   479.2    1556     477    1576   482.6    1600   483.7
    1633     489    1648   495.3    1663   496.4    1682   502.5    1856   504.1
    1883   508.3    1910   505.2    1944   496.2    2700   496.8    2762     498
    2816   505.2    3000     512    3100   520.3    3109     522    3200     525
#Mann= 3 ,0,0
    1000     .06       0    1463     .05       0    1648     .06       0
Bank Sta=1463,1648
XS Rating Curve= 0 ,0
Exp/Cntr=0.5,0.3

Type RM Length L Ch R = 1 ,11887   ,20,20,20
BEGIN DESCRIPTION:
This cross section corresponds to cross section 11890 of the non-georeferenced CDC model which was the source of this model.
END DESCRIPTION:
XS GIS Cut Line= 3
   2453141.91263   7070417.87497   2452811.88359   7070475.37132
   2449812.06735   7070997.98738
#Sta/Elev= 30
     100     520     300     516     660     512    1030     510    1190     506
    1320     500    1470     490    1690   490.3    1703   491.6    1793     490
    1800   483.8    1830   483.7    1834   480.6    1879   479.6    1900     475
    2000   473.9    2086   473.9    2100     478    2145   477.1    2154   481.3
    2183     477    2200   479.7    2209   478.2    2229   481.7    2248     491
    2600   490.8    2740     494    3000     498    3170     504    3480     520
#Mann= 3 ,0,0
     100     .06       0    1703     .05       0    2248     .06       0
#XS Ineff= 2 , 0
            1703   511.9    2248           511.1
Permanent Ineff=
       F       F
Bank Sta=1703,2248
XS Rating Curve= 0 ,0
Exp/Cntr=0.5,0.3

Type RM Length L Ch R = 3 ,11877   ,,,
BEGIN DESCRIPTION:
Atchinson, Topeka, and Sante Fe Railroad
END DESCRIPTION:
Node Name=ATSF Railroad
Bridge Culvert--1,0,-1,-1, 0
Deck Dist Width WeirC Skew NumUp NumDn MinLoCord MaxHiCord MaxSubmerge Is_Ogee
1,18,2.7,0, 10, 10, 511.1, , 0.95, 0, 0,0,,
     330     620     940    1600    1703    1703    2248    2248    3320    3480
     520     518     516     512   511.9   511.9   511.1   511.1     512     520
   473.9   473.9   473.9   473.9   473.9   507.5   507.5   473.9   473.9   473.9
     330     620     940    1600    1703    1703    2248    2248    3320    3480
     520     518     516     512   511.9   511.9   511.1   511.1     512     520
   473.9   473.9   473.9   473.9   473.9   507.5   507.5   473.9   473.9   473.9
Pier Skew, UpSta & Num, DnSta & Num=  ,1975.5, 2 ,1975.5, 2 , 0 , 0 , 0 ,,
      38      38
   473.9   507.5
      38      38
   473.9   507.5
Abutment Skew #Up #Dn= , 2 , 2
    1703    1898
   507.5   473.9
    1703    1898
   507.5   473.9
Abutment Skew #Up #Dn= , 2 , 2
    2053    2248
   473.9   507.5
    2053    2248
   473.9   507.5
BR Coef= 0 , 0 ,-1 ,1.05, 0 ,,,0.7905694,0,2,2,507.5
WSPro=,,,, 1 ,,,, 0 ,,,, 0 ,,,,-1 ,-1 ,-1 , 0 , 0 , 0 , 0 , 0
BR U #Sta/Elev= 40
     100     520     300     516     660     512    1030     510    1190     506
    1320     500    1430     492    1470     490    1500   489.5    1600   489.8
    1690   490.3    1703   491.6    1793     490    1800   483.8    1830   483.7
    1834   480.6    1850   473.9    1900   473.9    2000   473.9    2086   473.9
    2100     478    2145   477.1    2154   481.3    2183     477    2200   479.7
    2209   478.2    2229   481.7    2248     491    2300   491.2    2400     491
    2500   490.9    2600   490.8    2700   492.2    2740     494    2900     496
    3000     498    3060     500    3170     504    3280     510    3480     520
BR U #Mann= 3
     100     .06    1703     .05    2248     .06
BR D #Sta/Elev= 40
     100     520     300     516     660     512    1030     510    1190     506
    1320     500    1430     492    1470     490    1500   489.5    1600   489.8
    1690   490.3    1703   491.6    1793     490    1800   483.8    1830   483.7
    1834   480.6    1850   473.9    1900   473.9    2000   473.9    2086   473.9
    2100     478    2145   477.1    2154   481.3    2183     477    2200   479.7
    2209   478.2    2229   481.7    2248     491    2300   491.2    2400     491
    2500   490.9    2600   490.8    2700   492.2    2740     494    2900     496
    3000     498    3060     500    3170     504    3280     510    3480     520
BR D #Mann= 3
     100     .06    1703     .05    2248     .06
BC Design=,, 0 ,, 0 ,,,,,,
BC HTab HWMax=520
BC Use User HTab Curves=0
BC User HTab FreeFlow(D)= 0

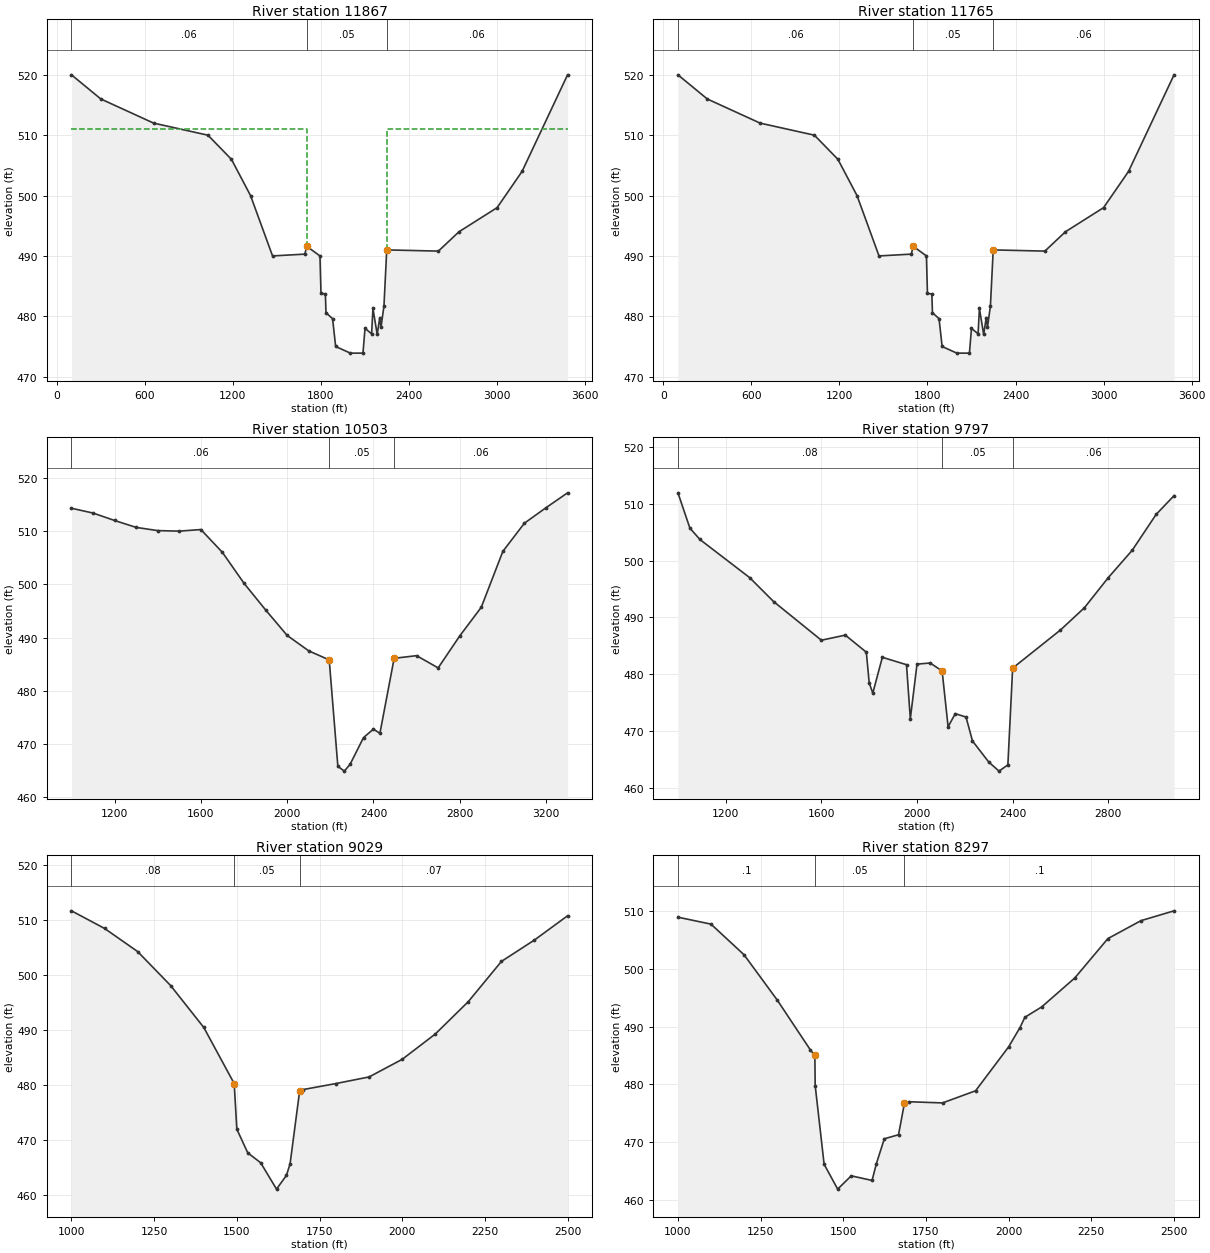
Type RM Length L Ch R = 1 ,11867   ,102,102,102
BEGIN DESCRIPTION:
This cross section corresponds to cross section 11870 of the non-georeferenced CDC model which was the source of this model.
END DESCRIPTION:
XS GIS Cut Line= 3
   2453138.95232   7070398.39365   2452808.92327      7070455.89
   2449809.10704   7070978.50607
#Sta/Elev= 30
     100     520     300     516     660     512    1030     510    1190     506
    1320     500    1470     490    1690   490.3    1703   491.6    1793     490
    1800   483.8    1830   483.7    1834   480.6    1879   479.6    1900     475
    2000   473.9    2086   473.9    2100     478    2145   477.1    2154   481.3
    2183     477    2200   479.7    2209   478.2    2229   481.7    2248     491
    2600   490.8    2740     494    3000     498    3170     504    3480     520
#Mann= 3 ,0,0
     100     .06       0    1703     .05       0    2248     .06       0
#XS Ineff= 2 , 0
       0    1703     511    2248       0     511
Permanent Ineff=
       F       F
Bank Sta=1703,2248
XS Rating Curve= 0 ,0
Exp/Cntr=0.5,0.3

Type RM Length L Ch R = 1 ,11765   ,1302,1262,1202
BEGIN DESCRIPTION:
This cross section corresponds to cross section 11770 of the non-georeferenced CDC model which was the source of this model.
END DESCRIPTION:
XS GIS Cut Line= 4
2452694.99457675 7069512.09563932452648.642635357069550.19464447
2451363.500848687070606.511757552449733.389607587070900.72704838
#Sta/Elev= 30
     100     520     300     516     660     512    1030     510    1190     506
    1320     500    1470     490    1690   490.3    1703   491.6    1793     490
    1800   483.8    1830   483.7    1834   480.6    1879   479.6    1900     475
    2000   473.9    2086   473.9    2100     478    2145   477.1    2154   481.3
    2183     477    2200   479.7    2209   478.2    2229   481.7    2248     491
    2600   490.8    2740     494    3000     498    3170     504    3480     520
#Mann= 3 ,0,0
     100     .06       0    1703     .05       0    2248     .06       0
Bank Sta=1703,2248
XS Rating Curve= 0 ,0
Exp/Cntr=0.5,0.3

Type RM Length L Ch R = 1 ,10503   ,857,706,726
BEGIN DESCRIPTION:
This cross section corresponds to cross section 10510 of the non-georeferenced CDC model which was the source of this model.
END DESCRIPTION:
XS GIS Cut Line= 5
 2451223.2524415 7069472.47367132450667.106572187069544.81768672
2450226.302663747069927.493758632449504.546889427070753.39532205
2449465.985942937070797.52056189
#Sta/Elev= 28
    1000   514.3    1100   513.4    1200     512    1300   510.7    1400   510.1
    1500     510    1600   510.3    1700     506    1800   500.2    1900   495.2
    2000   490.4    2100   487.5    2195   485.8    2235   465.8    2265   464.9
    2292   466.2    2354   471.2    2400   472.8    2430     472    2496   486.1
    2600   486.6    2700   484.3    2800   490.3    2900   495.7    3000   506.2
    3100   511.5    3200   514.4    3300   517.2
#Mann= 3 ,0,0
    1000     .06       0    2195     .05       0    2496     .06       0
Bank Sta=2195,2496
XS Rating Curve= 0 ,0
Exp/Cntr=0.3,0.1

Type RM Length L Ch R = 1 ,9797    ,887,768,493
BEGIN DESCRIPTION:
This cross section corresponds to cross section 9810 of the non-georeferenced CDC model which was the source of this model.
END DESCRIPTION:
XS GIS Cut Line= 6
2450189.009431247068487.324722962450182.706622337068500.93624429
2449727.370918847069484.267939052449490.014766257069665.91783822
2449071.009042597070186.647439792449065.304329577070193.73732063
#Sta/Elev= 30
    1000   511.9    1050   505.7    1092   503.7    1300     497    1400   492.8
    1600     486    1700   486.9    1788   483.9    1800   478.5    1815   476.7
    1855     483    1956   481.7    1972   472.2    2000   481.8    2055     482
    2105   480.6    2130   470.8    2160   473.1    2205   472.5    2232   468.3
    2300   464.6    2343     463    2380   464.1    2400   481.1    2600   487.8
    2700   491.7    2800     497    2900   501.8    3000   508.1    3075   511.4
#Mann= 3 ,0,0
    1000     .08       0    2105     .05       0    2400     .06       0
Bank Sta=2105,2400
XS Rating Curve= 0 ,0
Exp/Cntr=0.3,0.1

Type RM Length L Ch R = 1 ,9029    ,802,732,552
BEGIN DESCRIPTION:
This cross section corresponds to cross section 9030 of the non-georeferenced CDC model which was the source of this model.
END DESCRIPTION:
XS GIS Cut Line= 3
2449167.433390417068631.139067892449162.114831517068650.41921306
 2448768.54081557070077.12502106
#Sta/Elev= 22
    1000   511.6    1100   508.4    1200   504.2    1300     498    1400   490.4
    1492   480.2    1500   471.9    1533   467.6    1572   465.8    1620     461
    1650   463.5    1661   465.6    1690   478.9    1700   479.1    1800   480.2
    1900   481.4    2000   484.6    2100   489.2    2200   495.1    2300   502.4
    2400   506.3    2500   510.7
#Mann= 3 ,0,0
    1000     .08       0    1492     .05       0    1690     .07       0
Bank Sta=1492,1690
XS Rating Curve= 0 ,0
Exp/Cntr=0.3,0.1

Type RM Length L Ch R = 1 ,8297    ,940,951,1013
BEGIN DESCRIPTION:
This cross section corresponds to cross section 8300 of the non-georeferenced CDC model which was the source of this model.
END DESCRIPTION:
XS GIS Cut Line= 3
2448282.807206937068503.407039882448402.276456187069997.66389388
2448402.353883837069998.63075547
#Sta/Elev= 26
    1000   508.9    1100   507.7    1200   502.4    1300   494.6    1400     486
    1414     485    1415   479.8    1442   466.2    1483   461.9    1524   464.2
    1587   463.4    1600   466.3    1624   470.6    1667   471.3    1685   476.8
    1700     477    1800   476.8    1900   478.9    2000   486.5    2034   489.8
    2049   491.6    2100   493.4    2200   498.4    2300   505.2    2400   508.3
    2500     510
#Mann= 3 ,0,0
    1000      .1       0    1414     .05       0    1685      .1       0
Bank Sta=1414,1685
XS Rating Curve= 0 ,0
Exp/Cntr=0.3,0.1