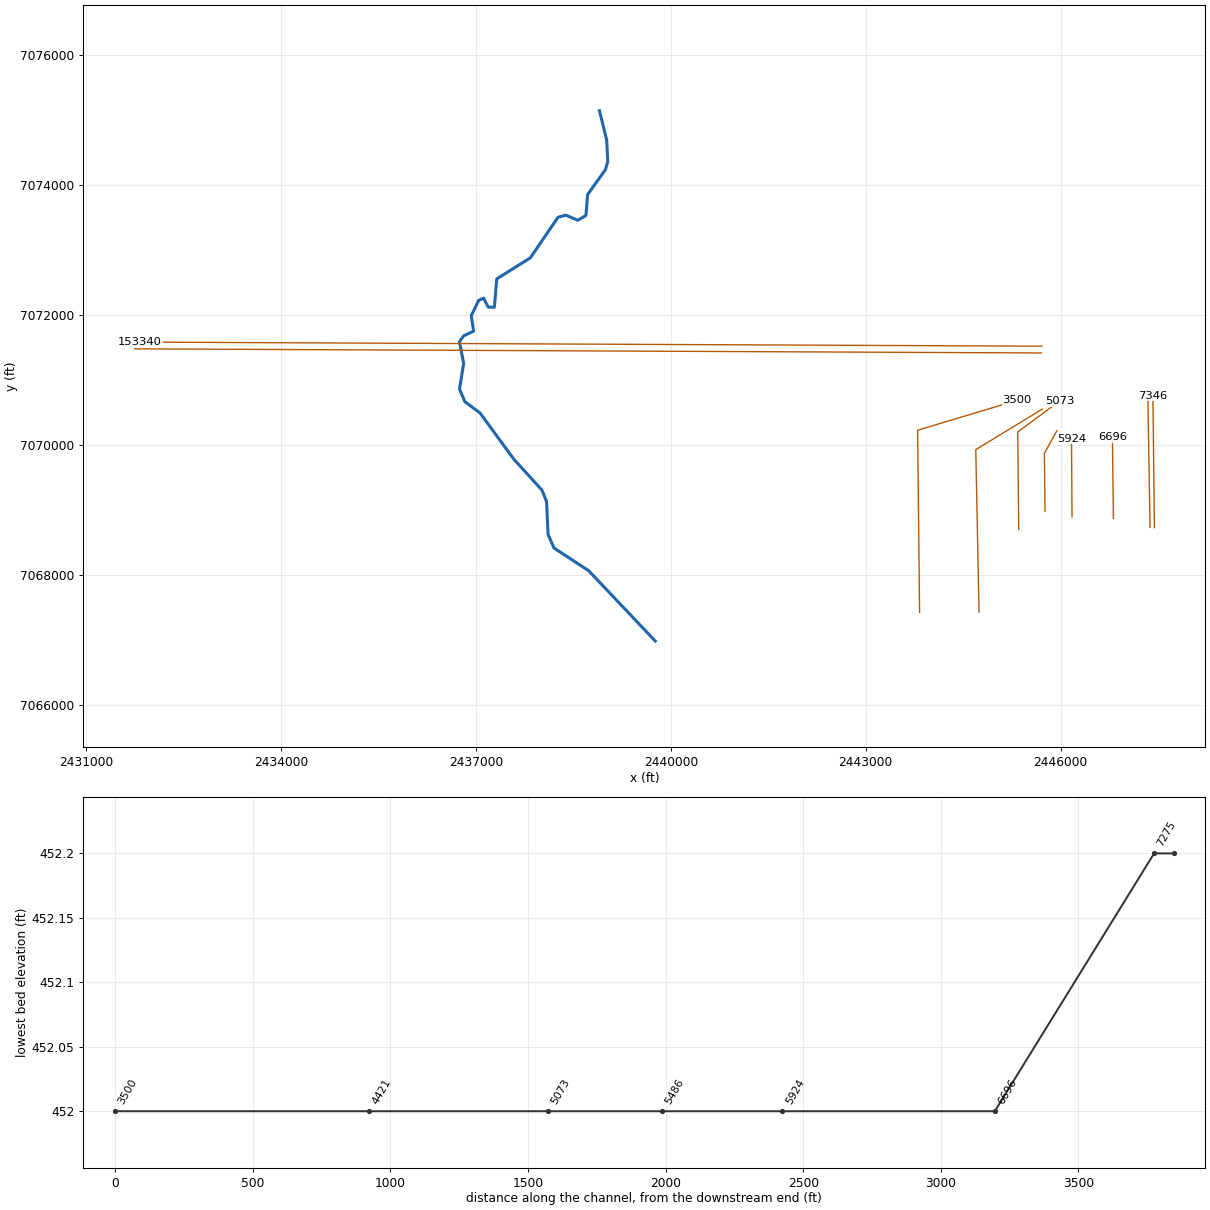
HEC-RAS study CDC_Consolidated_Model.prj: Upper Trinity CDC Consolidated Model

--- CDC_Consolidated_Model.g02 (geometry) --- (continued)

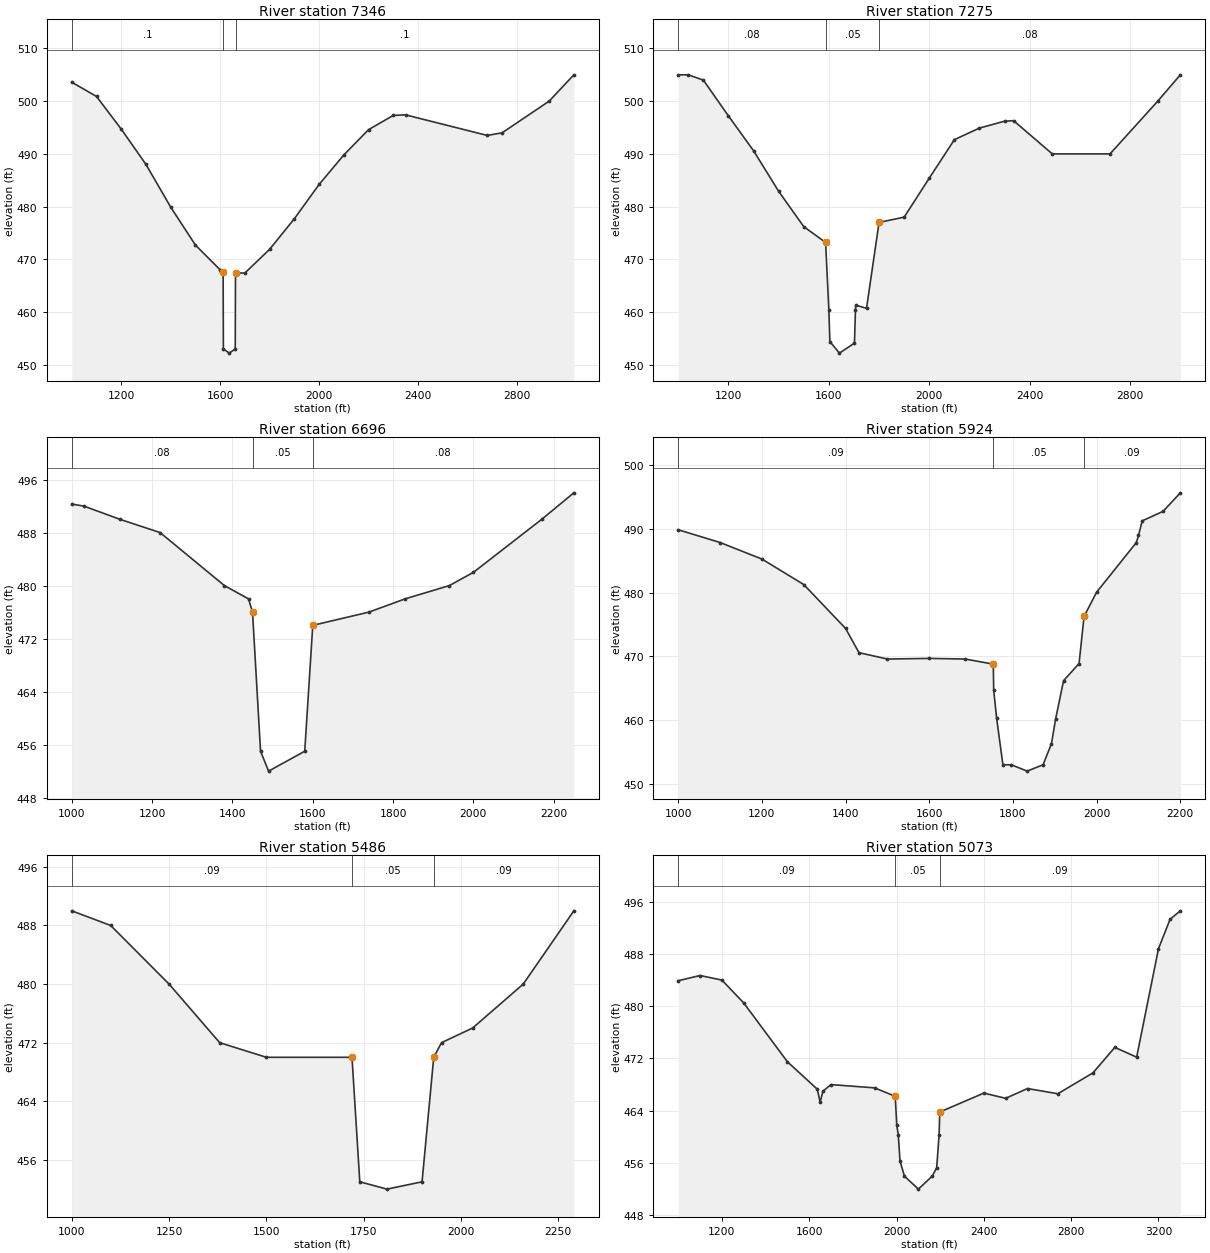
Type RM Length L Ch R = 1 ,7346    ,71,71,71
BEGIN DESCRIPTION:
This cross section corresponds to cross section 7380 of the non-georeferenced CDC model which was the source of this model.
END DESCRIPTION:
XS GIS Cut Line= 3
2447444.033950097068729.586377552447420.596332917070755.62792914
2447420.552041687070759.44780338
#Sta/Elev= 24
    1000   503.6    1100   500.9    1200   494.7    1300     488    1400   479.9
    1500   472.7    1600     468    1612   467.5    1613     453    1637   452.2
    1661     453    1662   467.4    1700   467.4    1800   471.9    1900   477.7
    2000   484.2    2100   489.8    2200   494.6    2300   497.3    2350   497.4
    2680   493.5    2740     494    2930     500    3030     505
#Mann= 3 ,0,0
    1000      .1       0    1612     .05       0    1662      .1       0
Bank Sta=1612,1662
XS Rating Curve= 0 ,0
Exp/Cntr=0.3,0.1

Type RM Length L Ch R = 1 ,7275    ,579,579,579
BEGIN DESCRIPTION:
This cross section corresponds to cross section 7310 of the non-georeferenced CDC model which was the source of this model.
END DESCRIPTION:
XS GIS Cut Line= 3
2447376.834609427068730.840640132447376.325424087068760.83631505
2447342.897013257070730.55153571
#Sta/Elev= 26
    1000     505    1040     505    1100     504    1200   497.2    1300   490.6
    1400   482.9    1500   476.2    1587   473.2    1600   460.4    1604   454.4
    1642   452.2    1702   454.1    1706   460.4    1707   461.3    1750   460.7
    1800     477    1900     478    2000   485.4    2100   492.7    2200   494.9
    2300   496.2    2336   496.3    2490     490    2720     490    2910     500
    3000     505
#Mann= 3 ,0,0
    1000     .08       0    1587     .05       0    1800     .08       0
Bank Sta=1587,1800
XS Rating Curve= 0 ,0
Exp/Cntr=0.3,0.1

Type RM Length L Ch R = 1 ,6696    ,635,772,654
BEGIN DESCRIPTION:
This cross section corresponds to cross section 6730 of the non-georeferenced CDC model which was the source of this model.
END DESCRIPTION:
XS GIS Cut Line= 3
2446812.794070847068868.818054472446797.875793587070072.74379621
2446797.305912857070118.72008222
#Sta/Elev= 17
    1000   492.3    1030     492    1120     490    1220     488    1380     480
    1440     478    1450     476    1470     455    1490     452    1580     455
    1600     474    1740     476    1830     478    1940     480    2000     482
    2170     490    2250     494
#Mann= 3 ,0,0
    1000     .08       0    1450     .05       0    1600     .08       0
Bank Sta=1450,1600
XS Rating Curve= 0 ,0
Exp/Cntr=0.3,0.1

Type RM Length L Ch R = 1 ,5924    ,418,438,358
BEGIN DESCRIPTION:
This cross section corresponds to cross section 5940 of the non-georeferenced CDC model which was the source of this model.
END DESCRIPTION:
XS GIS Cut Line= 3
2446175.645082687068894.611966132446168.066357677070089.04100771
2446168.030924687070094.59086539
#Sta/Elev= 27
    1000   489.9    1100   487.9    1200   485.3    1300   481.3    1400   474.4
    1432   470.6    1500   469.6    1600   469.7    1686   469.6    1753   468.8
    1754   464.7    1761   460.3    1776     453    1796     453    1834     452
    1872     453    1892   456.3    1902   460.2    1921   466.2    1958   468.9
    1970   476.3    2000   480.1    2095   487.9    2100     489    2109   491.3
    2159   492.8    2200   495.7
#Mann= 3 ,0,0
    1000     .09       0    1753     .05       0    1970     .09       0
Bank Sta=1753,1970
XS Rating Curve= 0 ,0
Exp/Cntr=0.3,0.1

Type RM Length L Ch R = 1 ,5486    ,413,413,491
BEGIN DESCRIPTION:
This cross section corresponds to cross section 5500 of the non-georeferenced CDC model which was the source of this model.
END DESCRIPTION:
XS GIS Cut Line= 5
2445760.451359247068978.989093962445759.62524542 7069048.9843608
2445749.912338357069871.806862132445924.744665837070188.17040263
2445941.992990917070219.38162629
#Sta/Elev= 14
    1000     490    1100     488    1250     480    1380     472    1500     470
    1720     470    1740     453    1810     452    1900     453    1930     470
    1950     472    2030     474    2160     480    2290     490
#Mann= 3 ,0,0
    1000     .09       0    1720     .05       0    1930     .09       0
Bank Sta=1720,1930
XS Rating Curve= 0 ,0
Exp/Cntr=0.3,0.1

Type RM Length L Ch R = 1 ,5073    ,643,652,198
BEGIN DESCRIPTION:
This cross section corresponds to cross section 5080 of the non-georeferenced CDC model which was the source of this model.
END DESCRIPTION:
XS GIS Cut Line= 4
2445355.492195437068700.940437472445339.867226667070200.94039021
  2445931.0130267070638.440499472445982.850520767070676.80492406
#Sta/Elev= 30
    1000   483.9    1100   484.7    1200     484    1300   480.5    1500   471.5
    1637   467.3    1650   465.3    1663     467    1700     468    1900   467.5
    1994   466.2    2001   461.8    2008   460.3    2016   456.3    2036     454
    2100     452    2164     454    2184   455.3    2195   460.3    2198   463.8
    2400   466.7    2500   465.9    2600   467.4    2739   466.6    2900   469.8
    3000   473.7    3100   472.2    3200   488.8    3253   493.3    3300   494.6
#Mann= 3 ,0,0
    1000     .09       0    1994     .05       0    2198     .09       0
Bank Sta=1994,2198
XS Rating Curve= 0 ,0
Exp/Cntr=0.3,0.1

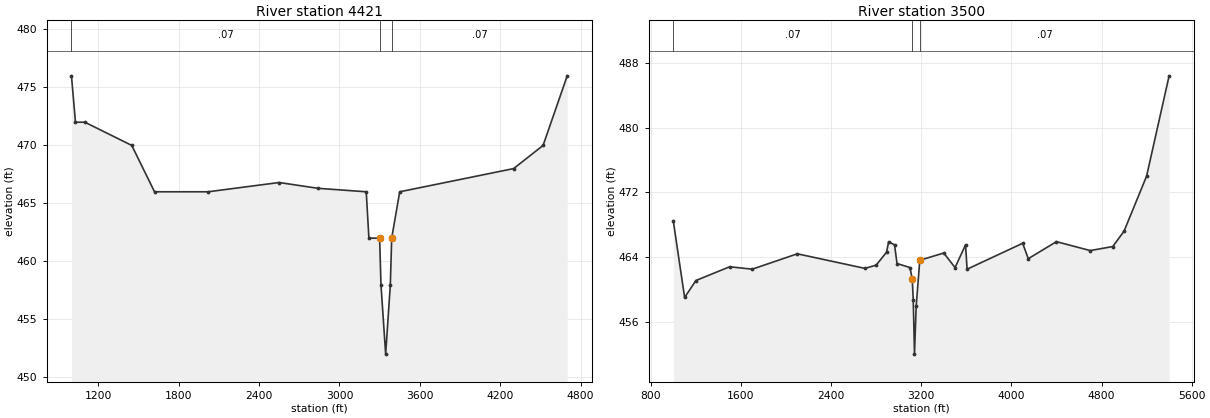
Type RM Length L Ch R = 1 ,4421    ,921,921,500
BEGIN DESCRIPTION:
This cross section corresponds to cross section 4420 of the non-georeferenced CDC model which was the source of this model.
END DESCRIPTION:
XS GIS Cut Line= 4
2444744.335937417067427.858337972444743.030821927067492.84508464
2444694.105066757069928.996052222445717.367783997070552.69067097
#Sta/Elev= 19
    1000     476    1030     472    1100     472    1450     470    1620     466
    2020     466    2550   466.8    2840   466.3    3200     466    3220     462
    3300     462    3310     458    3345     452    3380     458    3390     462
    3450     466    4300     468    4520     470    4700     476
#Mann= 3 ,0,0
    1000     .07       0    3300     .05       0    3390     .07       0
Bank Sta=3300,3390
XS Rating Curve= 0 ,0
Exp/Cntr=0.3,0.1

Type RM Length L Ch R = 1 ,3500    ,1000,2000,3000
BEGIN DESCRIPTION:
This cross section corresponds to cross section 3500 of the non-georeferenced CDC model which was the source of this model.
END DESCRIPTION:
XS GIS Cut Line= 5
 2443829.15338467067423.683805632443829.021823177067435.68312547
2443828.91224334 7067445.68244932443798.415913257070227.65063864
2445326.70878842 7070687.1110058
#Sta/Elev= 30
    1000   468.4    1100     459    1200   461.1    1500   462.8    1700   462.5
    2100   464.4    2700   462.6    2800     463    2892   464.6    2911   465.9
    2963   465.5    2985   463.2    3100   462.7    3120   461.3    3129   458.7
    3140     452    3155   457.9    3187   463.6    3400   464.5    3500   462.7
    3593   465.5    3607   462.5    4100   465.7    4150   463.8    4400   465.9
    4700   464.8    4900   465.3    5000   467.2    5200     474    5400   486.4
#Mann= 3 ,0,0
    1000     .07       0    3120     .05       0    3187     .07       0
Bank Sta=3120,3187
XS Rating Curve= 0 ,0
Exp/Cntr=0.3,0.1

River Reach=Elm Fork        ,ef6
Reach XY= 30
      2438900.87      7075147.22      2439012.72      7074695.68
      2439028.98      7074361.69      2438990.53      7074235.22
      2438718.77       7073855.4      2438693.57      7073534.74
      2438568.22      7073459.89       2438383.1       7073538.6
      2438263.42       7073506.2      2437837.47       7072881.9
      2437320.02      7072557.43      2437283.59      7072120.52
      2437188.54      7072123.44      2437118.44      7072261.15
      2437042.75      7072228.18      2436927.72      7071991.37
      2436964.65      7071752.62      2436813.18       7071682.7
      2436745.65      7071591.11      2436810.76      7071256.41
      2436746.66      7070860.99      2436830.46      7070666.22
      2437062.03      7070494.61      2437584.49      7069780.49
      2438016.21       7069306.3      2438087.58       7069129.3
      2438109.78      7068625.16      2438202.12      7068414.42
      2438735.14      7068065.71      2439760.19      7066982.89

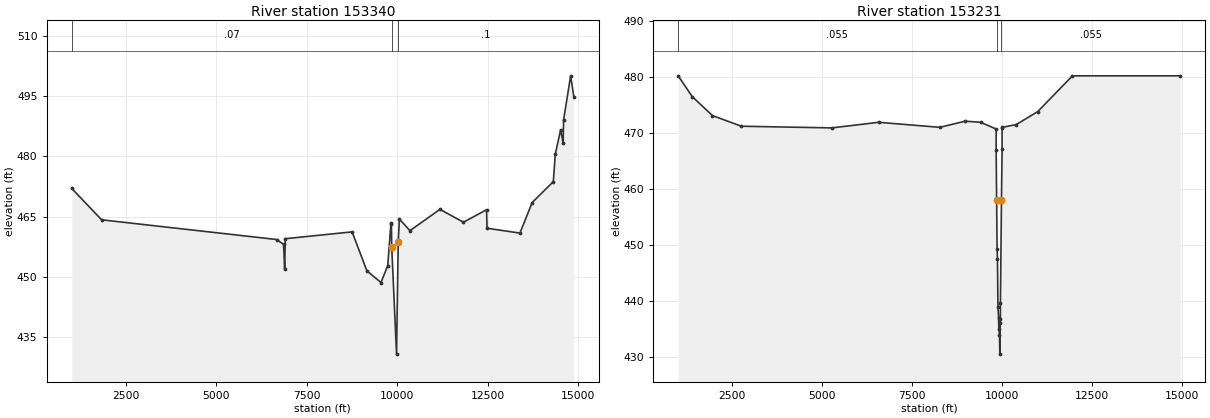
Type RM Length L Ch R = 1 ,153340  ,109,109,109
BEGIN DESCRIPTION:
This cross section corresponds to cross section 153328 of the non-georeferenced CDC model which was the source of this model.
END DESCRIPTION:
XS GIS Cut Line= 2
2445712.881900587071521.728102972431829.024825847071584.68959121
#Sta/Elev= 30
    1000     472    1825   464.2    6664   459.3    6857   458.1    6887     452
    6905   459.5    8752   461.2    9162   451.5    9550   448.6    9737   452.8
    9827   463.4    9839   463.1    9848   457.4    9981   430.8   10028   458.8
   10060   464.4   10352   461.5   11181   466.8   11831   463.6   12470   466.7
   12484   462.1   13393   460.9   13733   468.5   14317   473.7   14370   480.5
   14520   486.6   14588   483.2   14601   489.1   14796     500   14884   494.8
#Mann= 3 ,0,0
    1000     .07       0    9848     .05       0   10028      .1       0
Bank Sta=9848,10028
XS Rating Curve= 0 ,0
Exp/Cntr=0.3,0.1

Type RM Length L Ch R = 1 ,153231  ,29,29,29
BEGIN DESCRIPTION:
This cross section corresponds to cross section 153221 of the non-georeferenced CDC model which was the source of this model.
END DESCRIPTION:
XS GIS Cut Line= 4
2445706.509866097071417.480936142434742.620048497071467.20065297
2434742.620048497071467.200652972431742.650895467071480.80509622
#Sta/Elev= 30
    1000   480.2    1388   476.5    1952   473.1    2756   471.2    5267   470.9
    6575   471.9    8275     471    8980   472.1    9410   471.9  9842.4   470.7
  9842.4   466.9    9855     458  9868.5  449.31    9879   447.4    9892     439
    9910     437    9916     435    9934     434    9944   430.5    9956     436
    9960   436.8    9961  439.63    9990     458 10006.8   467.1 10006.8   470.9
   10014     471   10402   471.5   10996   473.8   11964   480.2   14964   480.2
#Mann= 3 ,0,0
    1000    .055       0    9855     .05       0    9990    .055       0
Bank Sta=9855,9990
XS Rating Curve= 0 ,0
Exp/Cntr=0.5,0.3