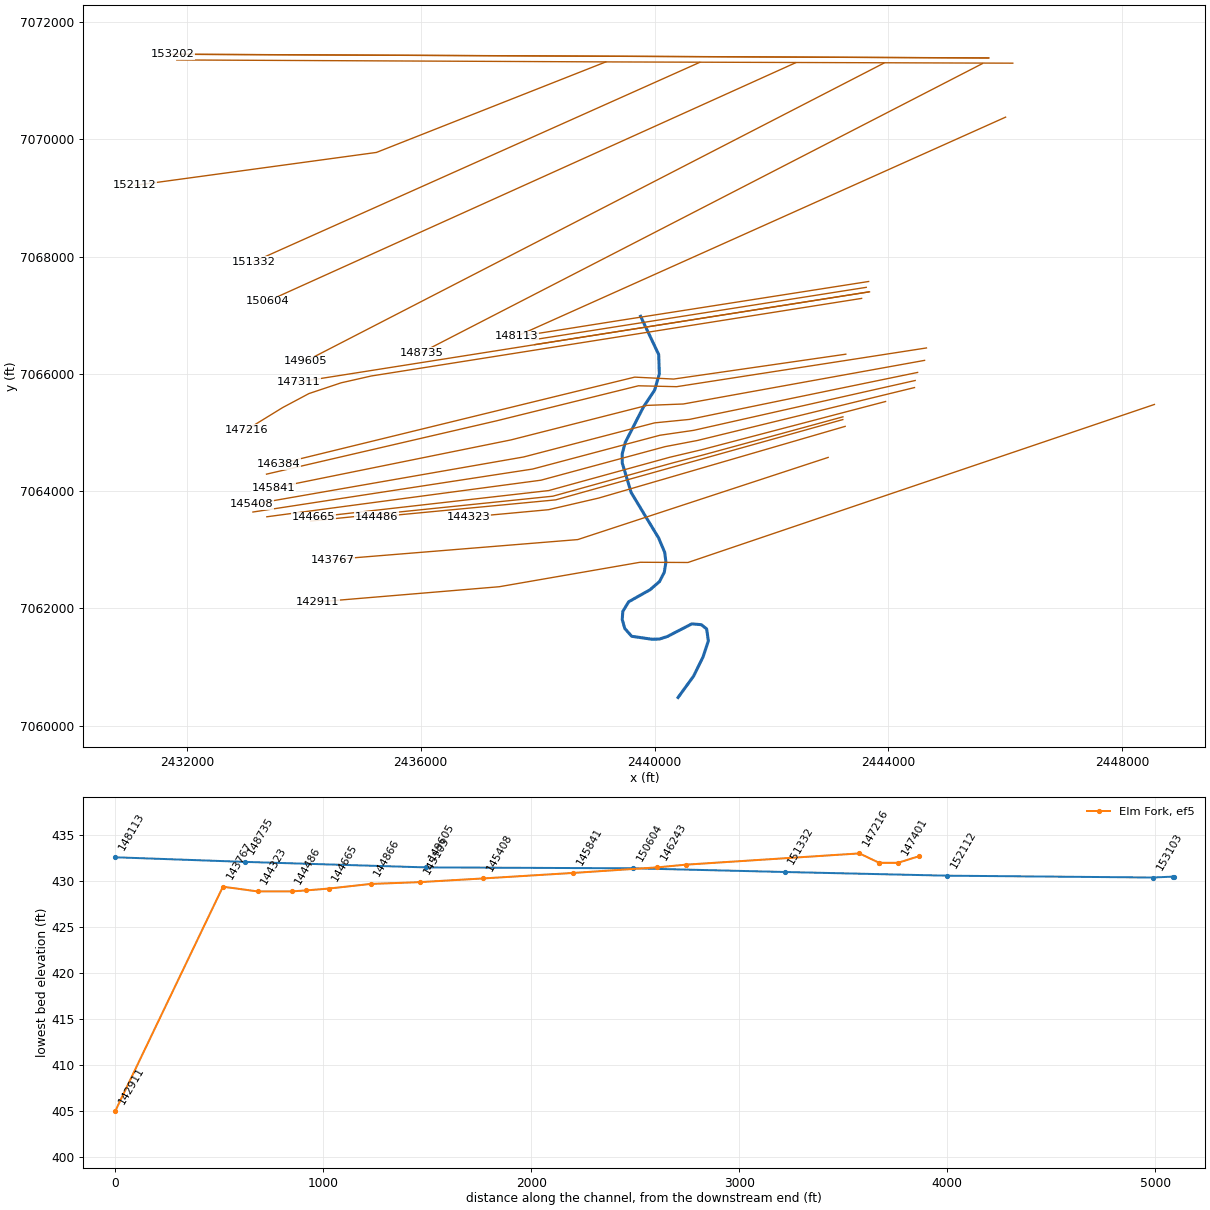
HEC-RAS study CDC_Consolidated_Model.prj: Upper Trinity CDC Consolidated Model

--- CDC_Consolidated_Model.g02 (geometry) --- (continued)

Type RM Length L Ch R = 3 ,153216  ,,,
BEGIN DESCRIPTION:
Atchinson, Topeka, and Sante Fe Railroad
Data from bridge plans.  Minimum low chord elev. 466.0.
END DESCRIPTION:
Node Name=ATSF Railroad
Bridge Culvert--1,0,-1,-1, 0
Deck Dist Width WeirC Skew NumUp NumDn MinLoCord MaxHiCord MaxSubmerge Is_Ogee
2,26,2.6,0, 18, 18, , , 0.95, 0, ,,,
  9842.4  9856.5  9857.5  9870.5  9871.5    9886    9886    9886    9890    9961
    9965    9966    9966  9980.5  9981.5  9994.5  9995.5 10006.8
   470.7  470.74  470.74  470.77  470.77   470.8     474     474     474     474
     474     474   470.8  470.86  470.86  470.92  470.92   470.9
  466.92  466.94  466.94  466.97  466.97     467     466     466     466     466
     466     466     467  467.03  467.03  467.06  467.06   467.1
  9842.4  9856.5  9857.5  9870.5  9871.5    9886    9886    9886    9890    9961
    9965    9966    9966  9980.5  9981.5  9994.5  9995.5 10006.8
   470.7  470.74  470.74  470.77  470.77   470.8     474     474     474     474
     474     474   470.8  470.86  470.86  470.92  470.92   470.9
  466.92  466.94  466.94  466.97  466.97     467     466     466     466     466
     466     466     467  467.03  467.03  467.06  467.06   467.1
Pier Skew, UpSta & Num, DnSta & Num=  ,9857, 2 ,9857, 2 , 0 , 0 , 0 ,,
       1       1
     435     469
       1       1
     435     469
Pier Skew, UpSta & Num, DnSta & Num=  ,9871, 2 ,9871, 2 , 0 , 0 , 0 ,,
       1       1
     435     469
       1       1
     435     469
Pier Skew, UpSta & Num, DnSta & Num=  ,9888, 2 ,9888, 2 , 0 , 0 , 0 ,,
       4       4
     435     469
       4       4
     435     469
Pier Skew, UpSta & Num, DnSta & Num=  ,9963, 2 ,9963, 2 , 0 , 0 , 0 ,,
       4       4
     435     469
       4       4
     435     469
Pier Skew, UpSta & Num, DnSta & Num=  ,9981, 2 ,9981, 2 , 0 , 0 , 0 ,,
       1       1
     435     469
       1       1
     435     469
Pier Skew, UpSta & Num, DnSta & Num=  ,9995, 2 ,9995, 2 , 0 , 0 , 0 ,,
       1       1
     435     469
       1       1
     435     469
BR Coef= 1 , 0 , 0 ,1.05, 0 ,,,0.8,-1,0.5,1,
WSPro=,,,, 1 ,,,, 0 ,,,, 0 ,,,,-1 ,-1 ,-1 , 0 , 0 , 0 , 0 , 0
BC Design=,, 0 ,, 0 ,,,,,,
BC HTab HWMax=480.2
BC Use User HTab Curves=0
BC User HTab FreeFlow(D)= 0

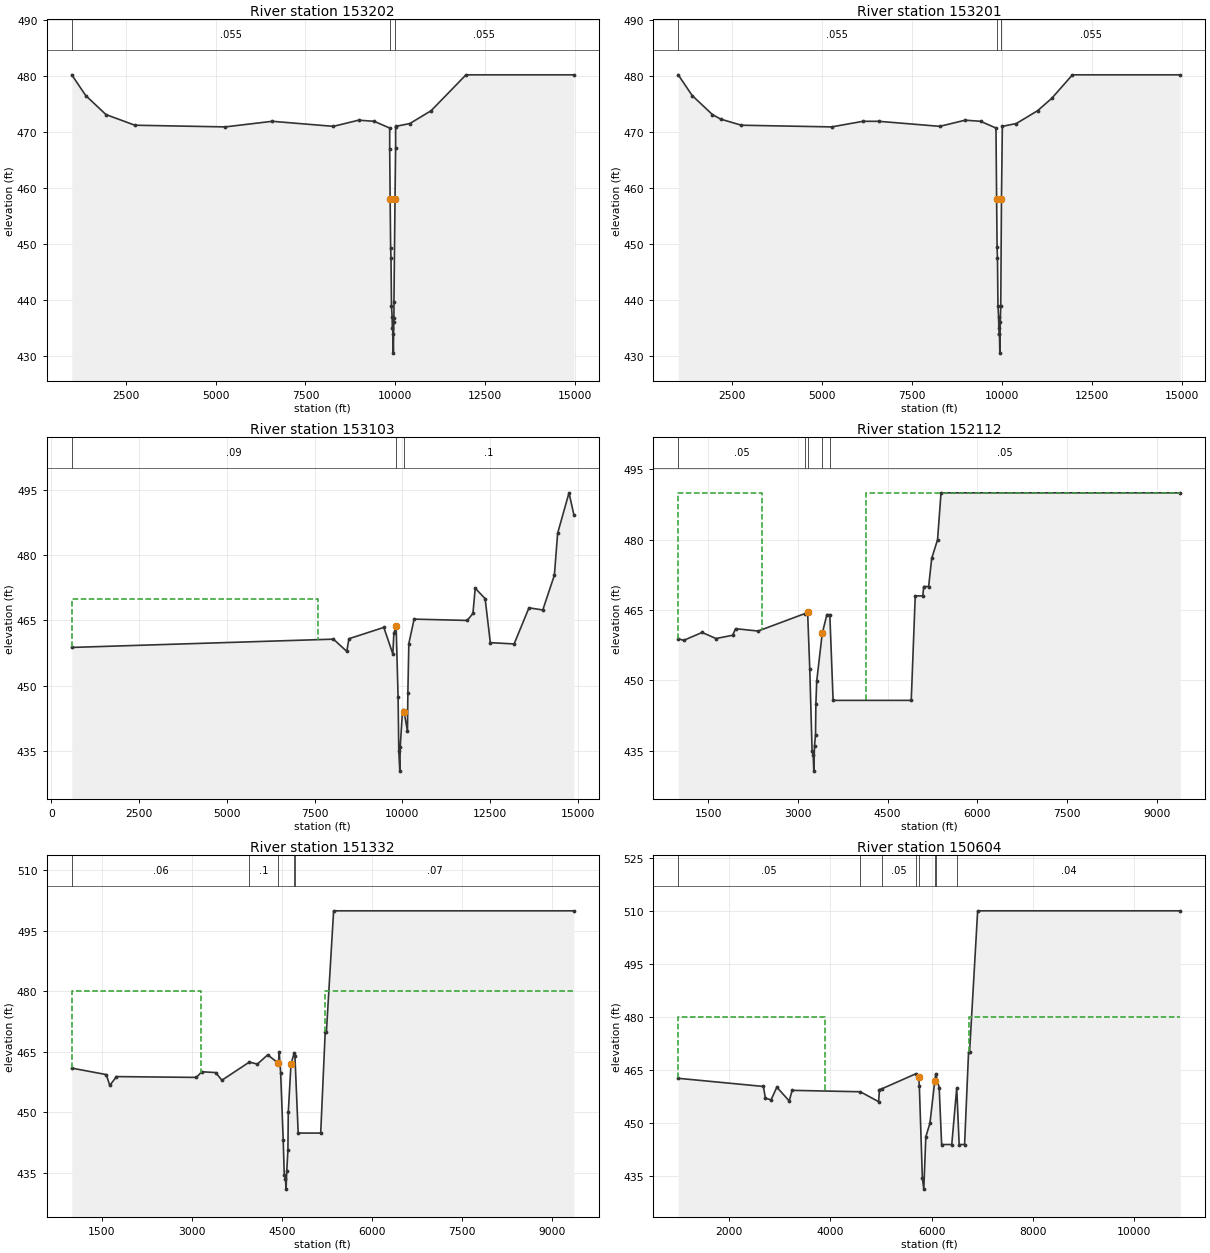
Type RM Length L Ch R = 1 ,153202  ,1,1,1
BEGIN DESCRIPTION:
This cross section corresponds to cross section 153192 of the non-georeferenced CDC model which was the source of this model.
END DESCRIPTION:
XS GIS Cut Line= 4
2445717.119424917071389.170953382434753.231903917071438.89067021
2434753.231903917071438.890670212431753.262750897071452.49511631
#Sta/Elev= 30
    1000   480.2    1388   476.5    1952   473.1    2756   471.2    5267   470.9
    6575   471.9    8275     471    8980   472.1    9410   471.9  9842.4   470.7
  9842.4   466.9    9855     458  9868.5  449.31    9879   447.4    9892     439
    9910     437    9916     435    9934     434    9944   430.5    9956     436
    9960   436.8    9961  439.63    9990     458 10006.8   467.1 10006.8   470.9
   10014     471   10402   471.5   10996   473.8   11964   480.2   14964   480.2
#Mann= 3 ,0,0
    1000    .055       0    9855     .05       0    9990    .055       0
Bank Sta=9855,9990
XS Rating Curve= 0 ,0
Exp/Cntr=0.5,0.3

Type RM Length L Ch R = 1 ,153201  ,98,98,98
BEGIN DESCRIPTION:
This cross section corresponds to cross section 153191 of the non-georeferenced CDC model which was the source of this model.
END DESCRIPTION:
XS GIS Cut Line= 4
2445709.209663847071388.232635052434745.31754968 7071437.9520238
2434745.31754968 7071437.95202382431745.348396237071451.55637443
#Sta/Elev= 30
    1000   480.2    1388   476.5    1952   473.1    2176   472.3    2756   471.2
    5267   470.9    6136   471.9    6575   471.9    8275     471    8980   472.1
    9410   471.9    9837   470.7    9855     458    9868   449.4    9879   447.4
    9892     439    9910     437    9916     435    9926     434    9934     434
    9944   430.5    9956     436    9970     439    9990     458   10014     471
   10402   471.5   10996   473.8   11388     476   11964   480.2   14964   480.2
#Mann= 3 ,0,0
    1000    .055       0    9855     .05       0    9990    .055       0
Bank Sta=9855,9990
XS Rating Curve= 0 ,0
Exp/Cntr=0.3,0.1

Type RM Length L Ch R = 1 ,153103  ,849,991,1049
BEGIN DESCRIPTION:
This cross section corresponds to cross section 153092 of the non-georeferenced CDC model which was the source of this model.
END DESCRIPTION:
XS GIS Cut Line= 3
 2446125.8345826 7071299.8535518 2439125.9065575 7071321.5969416
 2431827.9818489 7071354.6916916
#Sta/Elev= 30
     586   458.8    8038   460.7    8417   457.9    8479   460.8    9473   463.4
    9729   457.3    9759   462.1    9823   463.7    9879   447.4    9899     435
    9928   430.4    9940     436   10006   444.5   10052   443.9   10146   439.6
   10157   448.3   10185   459.7   10335   465.3   11848     465   12010   466.6
   12075   472.4   12358     470   12505   459.9   13183   459.6   13606   467.9
   13999   467.4   14330   475.4   14422     485   14746   494.3   14884   489.3
#Mann= 3 ,0,0
     586     .09       0    9823     .05       0   10052      .1       0
#XS Ineff= 2 , 0
       0    7586     470               0
Permanent Ineff=
       F       F
Bank Sta=9823,10052
XS Rating Curve= 0 ,0
Exp/Cntr=0.3,0.1

Type RM Length L Ch R = 1 ,152112  ,850,780,1050
BEGIN DESCRIPTION:
This cross section corresponds to cross section 152100 of the non-georeferenced CDC model which was the source of this model.
END DESCRIPTION:
XS GIS Cut Line= 5
2439165.977999667071321.415183382435243.193850527069777.64103997
2435067.435999937069753.726717712435067.435999937069753.72671771
2431103.95652817 7069214.4397098
#Sta/Elev= 30
    1000   458.9    1089   458.5    1399   460.2    1632   458.9    1909   459.6
    1959     461    2335   460.5    3111   464.2    3163   464.5    3199   452.3
    3238   434.8    3256     434    3266   430.6    3278     436    3295   438.4
    3301     445    3315   449.8    3407     460    3485     464    3534     464
    3589   445.7    4895   445.7    4962     468    5088     468    5104     470
    5186     470    5237     476    5335     480    5393     490    9393     490
#Mann= 5 ,-1,0
    1000     .05       0    3111     .09       0    3163     .05       0
    3407     .09       0    3534     .05       0
#XS Ineff= 2 , 0
       0    2400     490    4140       0     490
Permanent Ineff=
       F       F
Bank Sta=3163,3407
XS Rating Curve= 0 ,0
Exp/Cntr=0.3,0.1

Type RM Length L Ch R = 1 ,151332  ,700,728,700
BEGIN DESCRIPTION:
This cross section corresponds to cross section 151320 of the non-georeferenced CDC model which was the source of this model.
END DESCRIPTION:
XS GIS Cut Line= 4
 2440772.67885457071314.129108712436790.555257087069538.65989064
2436790.555257087069538.65989064 2433137.23078757067909.78901793
#Sta/Elev= 30
    1000     461    1575   459.4    1633   456.7    1744   458.9    3075   458.7
    3164   460.1    3395   459.9    3500     458    3957   462.5    4090     462
    4263   464.3    4440   462.2    4455   464.9    4478   459.8    4521   443.1
    4538   434.6    4558   433.6    4568     431    4580   435.5    4599   440.7
    4605     450    4650     462    4704   464.8    4716     464    4770   444.9
    5145   444.9    5220     470    5240     470    5360     500    9360     500
#Mann= 5 ,-1,0
    1000     .06       0    3957      .1       0    4440     .05       0
    4704     .09       0    4716     .07       0
#XS Ineff= 2 , 0
       0    3150     480    5220       0     480
Permanent Ineff=
       F       F
Bank Sta=4440,4650
XS Rating Curve= 0 ,0
Exp/Cntr=0.3,0.1

Type RM Length L Ch R = 1 ,150604  ,901,999,991
BEGIN DESCRIPTION:
This cross section corresponds to cross section 150592 of the non-georeferenced CDC model which was the source of this model.
END DESCRIPTION:
XS GIS Cut Line= 4
2442410.498085417071306.700973972437021.811684347068879.73601164
2437021.811684347068879.736011642433374.646610477067237.12013324
#Sta/Elev= 30
    1000   462.7    2680   460.4    2721   457.1    2832   456.6    2946   460.2
    3191   456.3    3248   459.3    4594   458.9    4955   456.1    4972   459.5
    5029   459.8    5693     464    5747     463    5759   460.5    5819   434.5
    5847   431.4    5887   446.2    5968     450    6064     462    6083     464
    6151     460    6199     444    6399     444    6497     460    6545     444
    6652     444    6730     470    6750     470    6910     510   10910     510
#Mann= 8 ,-1,0
    1000     .05       0    4594     .07       0    5029     .05       0
    5693     .09       0    5747     .05       0    6064     .08       0
    6083     .04       0    6497     .04       0
#XS Ineff= 2 , 0
       0    3900     480    6730       0     480
Permanent Ineff=
       F       F
Bank Sta=5747,6064
XS Rating Curve= 0 ,0
Exp/Cntr=0.3,0.1

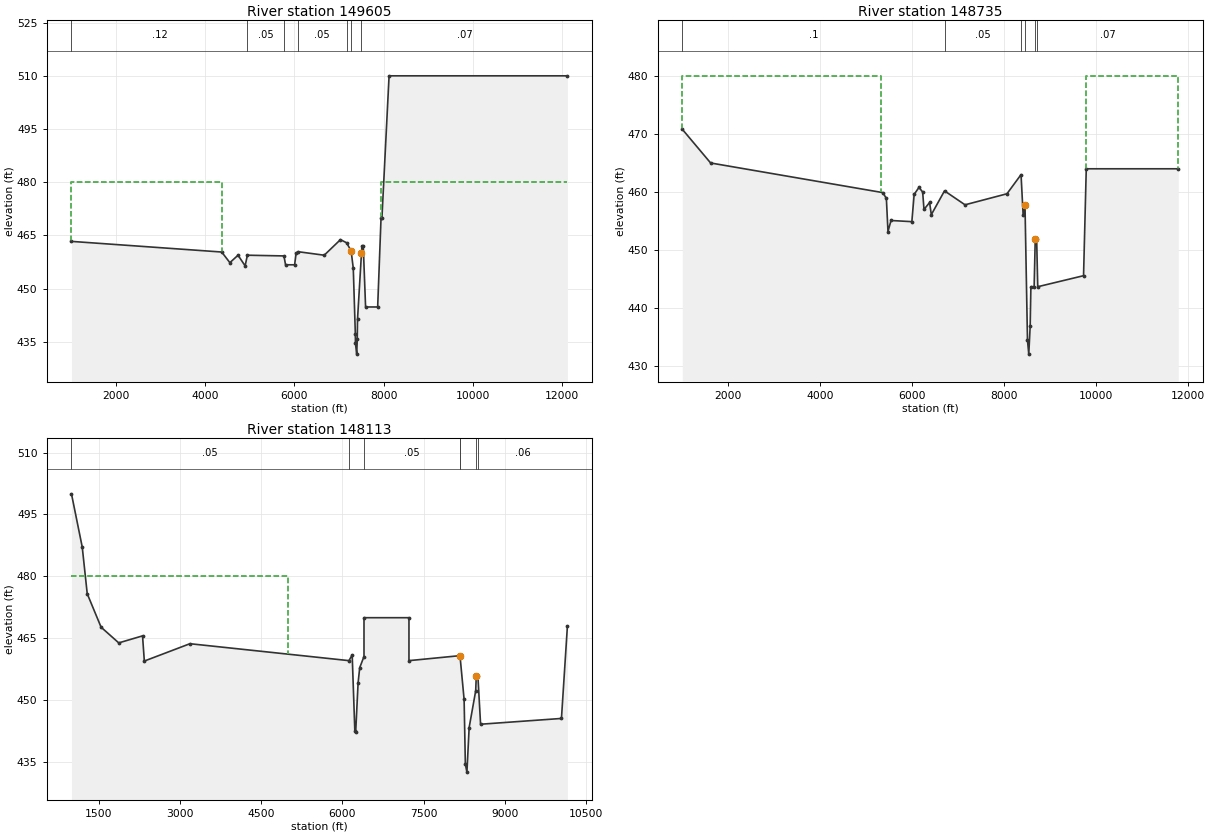
Type RM Length L Ch R = 1 ,149605  ,779,870,779
BEGIN DESCRIPTION:
This cross section corresponds to cross section 149594 of the non-georeferenced CDC model which was the source of this model.
END DESCRIPTION:
XS GIS Cut Line= 3
2443919.972100597071299.856171382437583.829917257068043.37416729
2434026.198034917066214.91706093
#Sta/Elev= 30
    1000   463.3    4370   460.3    4553   457.3    4736   459.4    4895   456.4
    4946   459.4    5766   459.2    5802   456.7    6005   456.7    6039   459.9
    6077   460.4    6669   459.4    7034   463.8    7172   462.9    7273   460.6
    7321   455.7    7367   437.3    7370   434.5    7398   431.5    7410   435.7
    7416   441.3    7505     460    7515     462    7545     462    7597   444.8
    7868   444.8    7944     470    7964     470    8124     510   12124     510
#Mann= 7 ,-1,0
    1000     .12       0    4946     .05       0    5766     .08       0
    6077     .05       0    7172     .09       0    7273     .05       0
    7505     .07       0
#XS Ineff= 2 , 0
       0    4370     480    7944       0     480
Permanent Ineff=
       F       F
Bank Sta=7273,7505
XS Rating Curve= 0 ,0
Exp/Cntr=0.3,0.1

Type RM Length L Ch R = 1 ,148735  ,750,622,570
BEGIN DESCRIPTION:
This cross section corresponds to cross section 148723 of the non-georeferenced CDC model which was the source of this model.
END DESCRIPTION:
XS GIS Cut Line= 3
2445605.16886142 7071292.21412632437792.88658574 7067278.5705788
2436013.93126713 7066364.6132634
#Sta/Elev= 30
    1000   470.8    1616     465    5359   459.9    5437   458.9    5472   453.2
    5538   455.1    5991   454.9    6041   459.6    6146   460.8    6226     460
    6255     457    6377   458.2    6414   456.1    6701   460.2    7147   457.8
    8059   459.7    8365     463    8411     456    8451   457.7    8505   434.5
    8533   432.1    8564     437    8579   443.7    8650   443.7    8674     452
    8704     452    8728   443.7    9724   445.6    9783     464   11783     464
#Mann= 6 ,-1,0
    1000      .1       0    6701     .05       0    8365     .09       0
    8451     .05       0    8674     .09       0    8704     .07       0
#XS Ineff= 2 , 0
       0    5320     480    9783       0     480
Permanent Ineff=
       F       F
Bank Sta=8451,8674
XS Rating Curve= 0 ,0
Exp/Cntr=0.3,0.1

Type RM Length L Ch R = 1 ,148113  ,0,0,0
BEGIN DESCRIPTION:
This cross section corresponds to cross section 148101 of the non-georeferenced CDC model which was the source of this model.
---------------------------------------------------------------------
CDC LEW012804-01 Lewisville Landfill
Cross-section 148101 - 152100
Located in LOB.
---------------------------------------------------------------------
END DESCRIPTION:
XS GIS Cut Line= 2
2446002.700874757070379.352106882437644.630648677066643.48753138
#Sta/Elev= 30
    1000     500    1199   487.1    1291   475.8    1547   467.7    1873   463.9
    2312   465.6    2345   459.5    3187   463.7    6123   459.6    6182     461
    6231   442.5    6247   442.4    6291   454.2    6321   457.9    6400   460.6
    6400     470    7230     470    7230   459.6    8165   460.8    8172   460.8
    8248   450.2    8271   434.5    8300   432.6    8341   443.4    8462   452.3
    8473     456    8502     456    8552   444.2   10045   445.6   10155     468
#Mann= 7 ,-1,0
    1000     .05       0    6123     .12       0    6400     .05       0
    8165     .09       0    8172     .04       0    8473     .08       0
    8502     .06       0
#XS Ineff= 2 , 0
       0    5000     480               0
Permanent Ineff=
       F       F
Bank Sta=8172,8473
XS Rating Curve= 0 ,0
Exp/Cntr=0.3,0.1

River Reach=Elm Fork        ,ef5
Reach XY= 30
      2439760.19      7066982.89       2440070.1      7066331.29
      2440081.26       7065998.9       2439999.6      7065722.59
      2439807.97      7065433.87      2439498.65      7064832.26
      2439446.53      7064639.71      2439447.03      7064479.92
      2439599.85      7063975.96      2440069.73      7063200.98
      2440172.81      7062957.74      2440193.97      7062791.14
       2440165.5      7062617.14      2440083.72      7062458.84
      2439922.97        7062320.      2439557.08      7062114.87
      2439456.28      7061950.22       2439446.5      7061811.99
      2439489.79      7061659.83      2439608.05      7061525.81
      2439951.53      7061475.85      2440082.51      7061478.57
      2440219.71      7061522.72      2440636.29      7061737.72
      2440798.38        7061724.      2440890.21      7061651.06
      2440919.48      7061448.08       2440828.3      7061172.42
      2440666.25      7060845.77      2440400.92      7060482.14

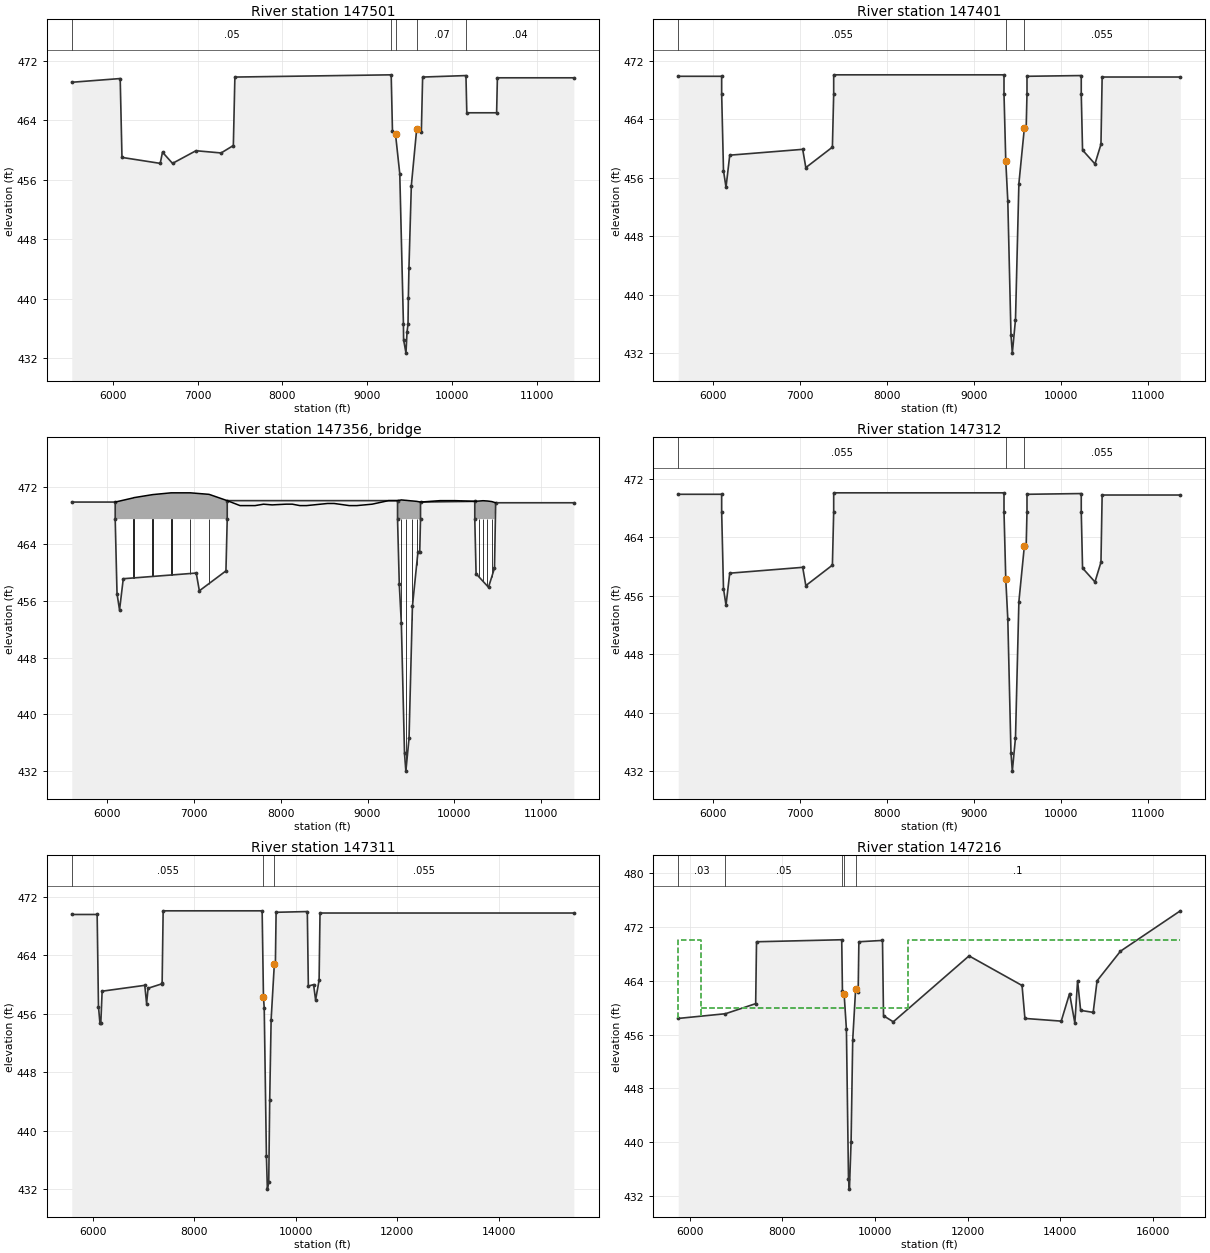
Type RM Length L Ch R = 1 ,147501  ,100,100,100
BEGIN DESCRIPTION:
This cross section corresponds to cross section 147489 of the non-georeferenced CDC model which was the source of this model.
END DESCRIPTION:
XS GIS Cut Line= 5
2443660.585755317067576.688206852443166.565470937067499.59113413
2439376.452972417066908.104128142438710.714802597066802.82415497
2437821.761775897066662.24493773
#Sta/Elev= 30
    5520   469.1    6090   469.6    6111     459    6561   458.2    6588   459.7
    6706   458.2    6982   459.9    7278   459.6    7422   460.6    7440   469.8
    9280   470.1    9295   462.5    9331   462.1    9381   456.8    9424   436.6
    9426   434.5    9454   432.7    9466   435.5    9478   436.6    9482   440.1
    9489   444.2    9517   455.2    9580   462.8    9635   462.4    9650   469.8
   10160     470   10170     465   10521     465   10530   469.7   11430   469.7
#Mann= 5 ,-1,0
    5520     .05       0    9280     .09       0    9331     .05       0
    9580     .07       0   10160     .04       0
Bank Sta=9331,9580
XS Rating Curve= 0 ,0
Exp/Cntr=0.3,0.1

Type RM Length L Ch R = 1 ,147401  ,89,89,89
BEGIN DESCRIPTION:
This cross section corresponds to cross section 147390 of the non-georeferenced CDC model which was the source of this model.
END DESCRIPTION:
XS GIS Cut Line= 4
2443619.449423847067476.809938342443125.501576667067399.25012746
2438797.923617667066719.732785722437908.817492737066580.12512613
#Sta/Elev= 30
    5595   469.9    6095   469.9    6095  467.49    6116     457    6145   454.7
    6188   459.1    7028   459.9    7064   457.4    7370   460.2  7384.8   467.5
  7384.8   470.1  9345.7   470.1  9345.7   467.5    9366   458.3  9389.5  452.81
    9426   434.5  9441.5     432    9478   436.6    9517   455.2    9580   462.8
    9601   462.8  9610.3   467.5  9610.3   469.9 10235.1     470 10235.1  467.49
   10250   459.8   10393   457.9   10462   460.6 10475.6   469.8 11375.6   469.8
#Mann= 3 ,0,0
    5595    .055       0    9366     .05       0    9580    .055       0
Bank Sta=9366,9580
XS Rating Curve= 0 ,0
Exp/Cntr=0.5,0.3

Type RM Length L Ch R = 3 ,147356  ,,,
BEGIN DESCRIPTION:
SH 121
END DESCRIPTION:
Node Name=SH 121
Bridge Culvert--1,0,-1,-1, 0
Deck Dist Width WeirC Skew NumUp NumDn MinLoCord MaxHiCord MaxSubmerge Is_Ogee
2,86,2.6,0, 54, 54, , , 0.95, 0, ,,,
    6095    6095  6304.5  6309.5  6521.5  6526.5  6738.5  6743.5  6955.5  6960.5
  7172.5  7177.5  7384.8  7384.8    7532    7705    7803    7901    8061    8135
    8221    8298    8540    8616    8790    8876    9053    9242  9345.7  9345.7
  9389.5  9390.5  9441.5  9444.5    9478  9511.5  9514.5  9564.5  9565.5  9610.3
  9610.3    9835   10010 10235.1 10279.5 10280.5 10329.5 10330.5 10379.5 10380.5
 10429.5 10430.5 10475.6 10475.6
   469.9   469.9  470.49  470.52  470.94  470.95   471.2   471.2   471.2   471.2
  470.99  470.98   470.1   470.1   469.4   469.4   469.6   469.5   469.6   469.6
   469.4   469.4   469.7   469.7   469.4   469.4   469.6   470.1   470.1   470.1
   470.2   470.2  470.14  470.14   470.1  470.06  470.06     470     470   469.9
   469.9   470.1   470.1     470  470.04  470.04  470.09  470.09  470.05  470.05
  469.97  469.97   469.8   469.8
   469.9  467.49   467.5   467.5   467.5   467.5   467.5   467.5   467.5   467.5
   467.5   467.5   467.5   470.1   469.4   469.4   469.6   469.5   469.6   469.6
   469.4   469.4   469.7   469.7   469.4   469.4   469.6   470.1   470.1   467.5
   467.5   467.5   467.5   467.5   467.5   467.5   467.5   467.5   467.5   467.5
   469.9   470.1   470.1  467.49   467.5   467.5   467.5   467.5   467.5   467.5
   467.5   467.5   467.5   469.8
    6095    6095  6304.5  6309.5  6521.5  6526.5  6738.5  6743.5  6955.5  6960.5
  7172.5  7177.5  7384.8  7384.8    7532    7705    7803    7901    8061    8135
    8221    8298    8540    8616    8790    8876    9053    9242  9345.7  9345.7
  9389.5  9390.5  9441.5  9444.5    9478  9511.5  9514.5  9564.5  9565.5  9610.3
  9610.3    9835   10010 10235.1 10279.5 10280.5 10329.5 10330.5 10379.5 10380.5
 10429.5 10430.5 10475.6 10475.6
   469.9   469.9  470.49  470.52  470.94  470.95   471.2   471.2   471.2   471.2
  470.99  470.98   470.1   470.1   469.4   469.4   469.6   469.5   469.6   469.6
   469.4   469.4   469.7   469.7   469.4   469.4   469.6   470.1   470.1   470.1
   470.2   470.2  470.14  470.14   470.1  470.06  470.06     470     470   469.9
   469.9   470.1   470.1     470  470.04  470.04  470.09  470.09  470.05  470.05
  469.97  469.97   469.8   469.8
   469.9  467.49   467.5   467.5   467.5   467.5   467.5   467.5   467.5   467.5
   467.5   467.5   467.5   470.1   469.4   469.4   469.6   469.5   469.6   469.6
   469.4   469.4   469.7   469.7   469.4   469.4   469.6   470.1   470.1   467.5
   467.5   467.5   467.5   467.5   467.5   467.5   467.5   467.5   467.5   467.5
   469.9   470.1   470.1  467.49   467.5   467.5   467.5   467.5   467.5   467.5
   467.5   467.5   467.5   469.8
Pier Skew, UpSta & Num, DnSta & Num=  ,6307, 2 ,6307, 2 , 0 , 0 , 0 ,,
       5       5
     455     468
       5       5
     455     468
Pier Skew, UpSta & Num, DnSta & Num=  ,6524, 2 ,6524, 2 , 0 , 0 , 0 ,,
       5       5
     455     468
       5       5
     455     468
Pier Skew, UpSta & Num, DnSta & Num=  ,6741, 2 ,6741, 2 , 0 , 0 , 0 ,,
       5       5
     455     468
       5       5
     455     468
Pier Skew, UpSta & Num, DnSta & Num=  ,6958, 2 ,6958, 2 , 0 , 0 , 0 ,,
       5       5
     455     468
       5       5
     455     468
Pier Skew, UpSta & Num, DnSta & Num=  ,7175, 2 ,7175, 2 , 0 , 0 , 0 ,,
       5       5
     455     468
       5       5
     455     468
Pier Skew, UpSta & Num, DnSta & Num=  ,9390, 2 ,9390, 2 , 0 , 0 , 0 ,,
       1       1
     430     469
       1       1
     430     469
Pier Skew, UpSta & Num, DnSta & Num=  ,9440, 2 ,9440, 2 , 0 , 0 , 0 ,,
       3       3
     430     469
       3       3
     430     469
Pier Skew, UpSta & Num, DnSta & Num=  ,9513, 2 ,9513, 2 , 0 , 0 , 0 ,,
       3       3
     430     469
       3       3
     430     469
Pier Skew, UpSta & Num, DnSta & Num=  ,9565, 2 ,9565, 2 , 0 , 0 , 0 ,,
       1       1
     430     469
       1       1
     430     469
Pier Skew, UpSta & Num, DnSta & Num=  ,10280, 2 ,10280, 2 , 0 , 0 , 0 ,,
       1       1
     430     469
       1       1
     430     469
Pier Skew, UpSta & Num, DnSta & Num=  ,10330, 2 ,10330, 2 , 0 , 0 , 0 ,,
       1       1
     430     469
       1       1
     430     469
Pier Skew, UpSta & Num, DnSta & Num=  ,10380, 2 ,10380, 2 , 0 , 0 , 0 ,,
       1       1
     430     469
       1       1
     430     469
Pier Skew, UpSta & Num, DnSta & Num=  ,10430, 2 ,10430, 2 , 0 , 0 , 0 ,,
       1       1
     430     469
       1       1
     430     469
BR Coef= 1 , 0 , 0 ,1.05, 0 ,,,0.8,-1,0.5,1,
WSPro=,,,, 1 ,,,, 0 ,,,, 0 ,,,,-1 ,-1 ,-1 , 0 , 0 , 0 , 0 , 0
BC Design=,, 0 ,, 0 ,,,,,,
BC HTab HWMax=470.1
BC Use User HTab Curves=0
BC User HTab FreeFlow(D)= 0

Type RM Length L Ch R = 1 ,147312  ,1,1,1
BEGIN DESCRIPTION:
This cross section corresponds to cross section 147301 of the non-georeferenced CDC model which was the source of this model.
END DESCRIPTION:
XS GIS Cut Line= 4
2443660.98029071 7067399.15611012443167.06776652 7067321.3716743
2438839.800174337066639.88648872 2437950.75763087066499.87450428
#Sta/Elev= 30
    5595   469.9    6095   469.9    6095  467.49    6116     457    6145   454.7
    6188   459.1    7028   459.9    7064   457.4    7370   460.2  7384.8   467.5
  7384.8   470.1  9345.7   470.1  9345.7   467.5    9366   458.3  9389.5  452.81
    9426   434.5  9441.5     432    9478   436.6    9517   455.2    9580   462.8
    9601   462.8  9610.3   467.5  9610.3   469.9 10235.1     470 10235.1  467.49
   10250   459.8   10393   457.9   10462   460.6 10475.6   469.8 11375.6   469.8
#Mann= 3 ,0,0
    5595    .055       0    9366     .05       0    9580    .055       0
Bank Sta=9366,9580
XS Rating Curve= 0 ,0
Exp/Cntr=0.5,0.3

Type RM Length L Ch R = 1 ,147311  ,95,95,95
BEGIN DESCRIPTION:
This cross section corresponds to cross section 147300 of the non-georeferenced CDC model which was the source of this model.
END DESCRIPTION:
XS GIS Cut Line= 4
2443675.931390817067400.564594352443182.019180187067322.77816755
2438845.474047517066639.813982292433906.351941257065861.94971431
#Sta/Elev= 30
    5590   469.6    6090   469.6    6116     457    6145   454.7    6162   454.7
    6188   459.1    7028   459.9    7064   457.4    7093   459.5    7362   460.1
    7370   460.2    7390   470.1    9340   470.1    9366   458.3    9381   456.8
    9424   436.6    9443     432    9470     433    9489   444.2    9517   455.2
    9580   462.8    9601   462.8    9615   469.9   10230     470   10250   459.8
   10353     460   10393   457.9   10462   460.6   10480   469.8   15480   469.8
#Mann= 3 ,0,0
    5590    .055       0    9366     .05       0    9580    .055       0
Bank Sta=9366,9580
XS Rating Curve= 0 ,0
Exp/Cntr=0.5,0.3

Type RM Length L Ch R = 1 ,147216  ,901,832,801
BEGIN DESCRIPTION:
This cross section corresponds to cross section 147204 of the non-georeferenced CDC model which was the source of this model.
END DESCRIPTION:
XS GIS Cut Line= 6
2443540.606116427067288.328175862435154.239960167065964.90293054
2434638.254115497065848.390040222434088.977983097065665.29821479
2433639.570089257065426.723232632433014.50375408 7065043.7089068
#Sta/Elev= 30
    5750   458.4    6769   459.1    7422   460.6    7440   469.8    9280   470.1
    9295   462.5    9331   462.1    9381   456.8    9426   434.5    9446  433.02
    9482   440.1    9517   455.2    9580   462.8    9635   462.4    9650   469.8
   10160     470   10182   458.8   10393   457.9   12029   467.7   13173   463.3
   13235   458.4   14019     458   14199   462.1   14313   457.7   14372     464
   14438   459.6   14709   459.3   14793     464   15298   468.4   16590   474.4
#Mann= 5 ,-1,0
    5750     .03       0    6769     .05       0    9280     .08       0
    9331     .05       0    9580      .1       0
#XS Ineff= 4 ,-1
    6250    9331     460    9580   10700     460   10700   16590     470
    5750    6250     470
Permanent Ineff=
       F       F       F       F
Bank Sta=9331,9580
XS Rating Curve= 0 ,0
Exp/Cntr=0.3,0.1

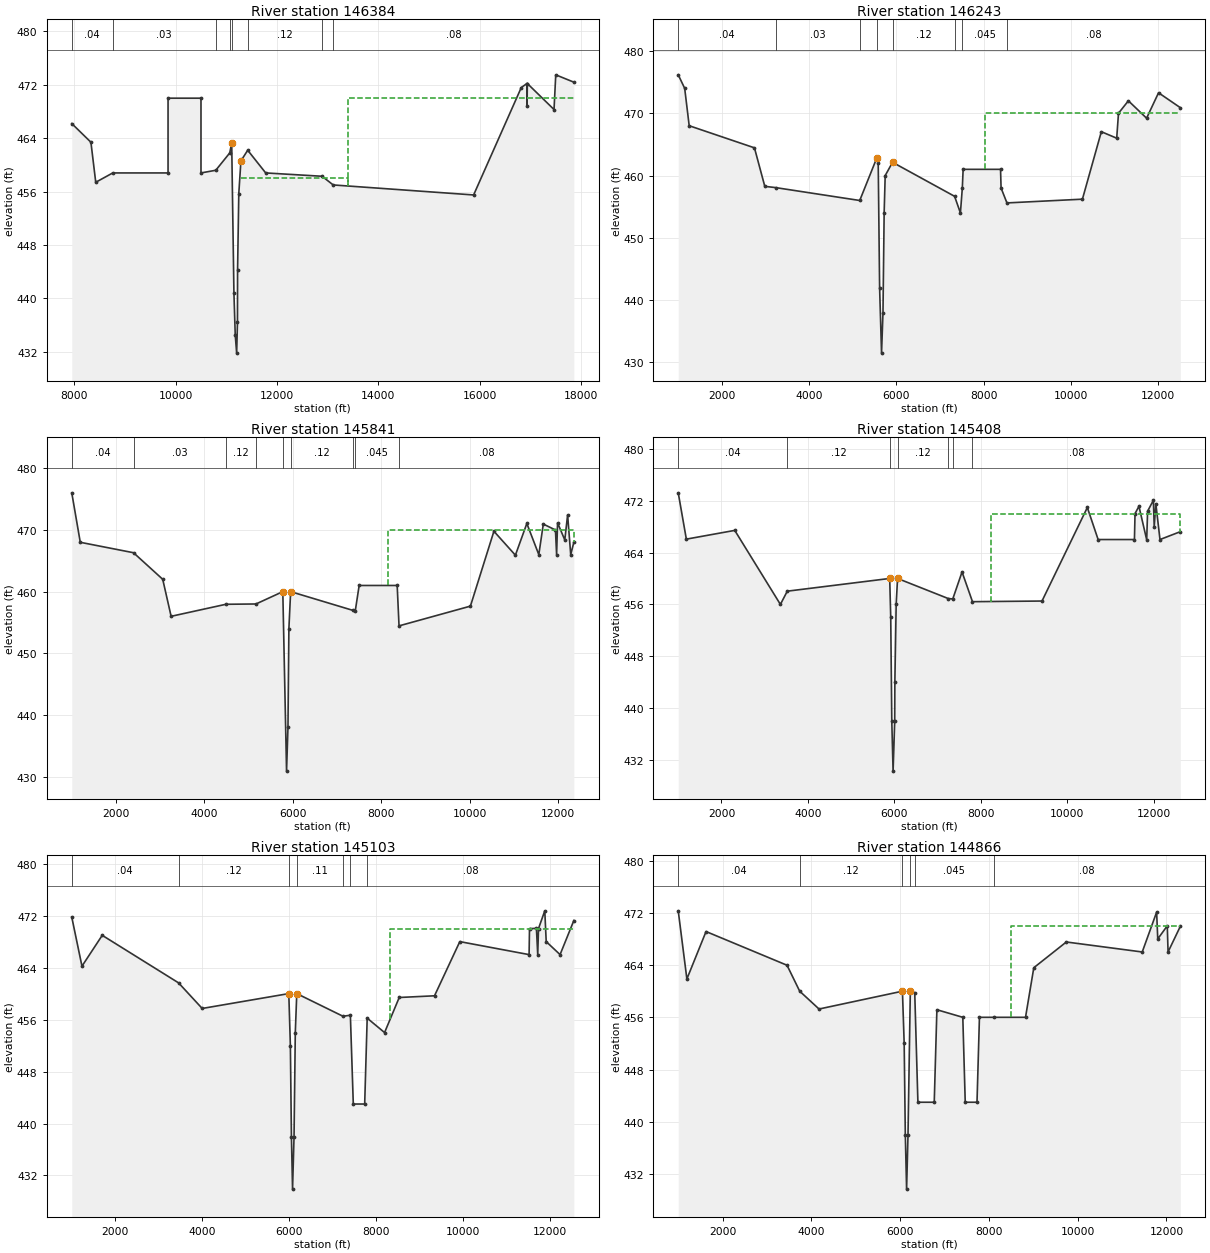
Type RM Length L Ch R = 1 ,146384  ,141,141,177
BEGIN DESCRIPTION:
This cross section corresponds to cross section 146373 of the non-georeferenced CDC model which was the source of this model.
 Cross Section Truncated due to Ineffective Flow Areas
- End Lewisville CLOMR.
Proposed Park Improvements - 13863.99-14110 (not shown)
END DESCRIPTION:
XS GIS Cut Line= 4
2443270.27720577 7066336.75159632440325.592150247065912.75014772
  2439659.4350187065945.512221312433571.254609087064463.41577604
#Sta/Elev= 30
    7950   466.2    8328   463.4    8423   457.4    8759   458.8    9850   458.8
    9850     470   10500     470   10500   458.8   10792   459.2   11068   461.8
   11106   463.3   11150   440.8   11176   434.5   11204   431.8   11220   436.5
   11222   444.2   11246   455.7   11288   460.6   11422   462.2   11777   458.8
   12890   458.3   13109     457   15880   455.5   16821   471.6   16933   472.2
   16935   468.8   16940   472.2   17467   468.3   17501   473.5   17858   472.4
#Mann= 8 ,-1,0
    7950     .04       0    8759     .03       0   10792     .04       0
   11068     .09       0   11106     .05       0   11422     .12       0
   12890     .05       0   13109     .08       0
#XS Ineff= 3 ,-1
    7950   11106     458   11288   13400     458   13400   17858     470
Permanent Ineff=
       F       F       F
Bank Sta=11106,11288
XS Rating Curve= 0 ,0
Exp/Cntr=0.3,0.1

Type RM Length L Ch R = 1 ,146243  ,237,402,298
BEGIN DESCRIPTION:
This cross section corresponds to cross section 146190 of the non-georeferenced CDC model which was the source of this model.
Added XS for Lewisville Atheltic Complex CLOMR.
Geopak data, interpolated flowline.
Proposed Park Improvements - 7514.39-8537.5
END DESCRIPTION:
XS GIS Cut Line= 5
2444648.866312097066443.213981792440376.618951087065782.63787514
2439723.594010417065798.005298472437299.62543318 7065201.0393008
2433363.086718357064290.98534663
#Sta/Elev= 30
    1000  476.17 1147.93     474 1251.16     468 2747.63  464.45  2984.9  458.27
 3232.16  458.07  5161.9     456 5556.94   462.9 5585.76     462 5617.74     442
    5662   431.5 5695.12  438.01 5721.77     454 5745.64     460 5914.86  462.13
 7337.32  456.67 7470.52     454 7514.39     458 7532.93     461  8390.6     461
 8402.96     458  8537.5  455.6110268.12  456.2110702.09  467.0411054.48     466
11095.36     47011322.03     472 11739.9  469.2112013.82  473.2912512.98   470.9
#Mann= 8 ,-1,0
    1000     .04       0 3232.16     .03       0  5161.9     .04       0
 5556.94     .05       0 5914.86     .12       0 7337.32     .05       0
 7514.39    .045       0  8537.5     .08       0
#XS Ineff= 2 , 0
       0    5590     458    8030       0     470
Permanent Ineff=
       F       F
Bank Sta=5556.94,5914.86
XS Rating Curve= 0 ,0
Exp/Cntr=0.3,0.1

Type RM Length L Ch R = 1 ,145841  ,314,433,239
BEGIN DESCRIPTION:
This cross section corresponds to cross section 145774 of the non-georeferenced CDC model which was the source of this model.
Added XS for Lewisville Atheltic Complex CLOMR.
Geopak data, interpolated flowline.
Proposed Park Improvements - 7415.65-8405.03
END DESCRIPTION:
XS GIS Cut Line= 5
2444617.051415097066231.377135132440492.26471716 7065487.5544758
2439869.413600687065463.58437939 2437543.50650717064874.87886389
2433478.885043177064053.98713297
#Sta/Elev= 30
    1000  476.02 1192.47     468    2397 466.309 3058.11     462 3247.94     456
  4487.9  457.95 5168.07     458  5775.2     460    5860   430.9 5892.08     438
 5912.78     454 5952.43     460 7357.92  456.97 7415.65  456.92 7502.95     461
 8363.24     461 8405.03  454.4510020.19  457.6510551.82  469.79   11038  465.91
11296.87  471.0511567.86     466 11669.6  470.9511944.33     47011970.66     466
11992.25  471.16 12155.6  468.3812219.71  472.44 12289.8     46612360.57     468
#Mann= 9 ,-1,0
    1000     .04       0    2397     .03       0  4487.9     .12       0
 5168.07     .04       0  5775.2     .05       0 5952.43     .12       0
 7357.92     .05       0 7415.65    .045       0 8405.03     .08       0
#XS Ineff= 2 , 0
       0    5774     457    8160       0     470
Permanent Ineff=
       F       F
Bank Sta=5775.2,5952.43
XS Rating Curve= 0 ,0
Exp/Cntr=0.3,0.1

Type RM Length L Ch R = 1 ,145408  ,222,305,244
BEGIN DESCRIPTION:
This cross section corresponds to cross section 145400 of the non-georeferenced CDC model which was the source of this model.
Added XS for Lewisville Atheltic Complex CLOMR
END DESCRIPTION:
XS GIS Cut Line= 5
2444497.827572177066025.763701222440595.212017837065224.42376846
2440000.141029517065165.626641962437760.809878267064584.05956364
2433112.307036167063774.77279638
#Sta/Elev= 30
    1000   473.2 1187.62  466.06 2307.28  467.41  3363.1     456 3522.78  458.04
 5891.45     460 5915.47     454  5939.9     438    5970   430.3 6007.61     438
 6010.92     444 6041.31     456 6073.27     460    7247 456.901 7350.71  456.84
 7564.92     461 7806.49  456.42 9414.81  456.5210463.22  470.9410712.89     466
11552.91     46611566.71     47011657.19  471.1311836.79  465.9511857.19  470.36
11991.42  472.0612010.32     46812048.15  471.5112143.83     46612614.05  467.21
#Mann= 7 ,-1,0
    1000     .04       0 3522.78     .12       0 5891.45     .05       0
 6073.27     .12       0    7247     .05       0 7350.71    .045       0
 7806.49     .08       0
#XS Ineff= 2 , 0
       0    5887     457    8240       0     470
Permanent Ineff=
       F       F
Bank Sta=5891.45,6073.27
XS Rating Curve= 0 ,0
Exp/Cntr=0.3,0.1

Type RM Length L Ch R = 1 ,145103  ,237,237,237
BEGIN DESCRIPTION:
This cross section corresponds to cross section 145140 of the non-georeferenced CDC model which was the source of this model.
Added XS for Lewisville Atheltic Complex CLOMR.
END DESCRIPTION:
XS GIS Cut Line= 5
2444456.547142927065888.113057882440667.99763343 7065038.0671858
2440093.219255427064954.782575472437914.820068937064378.15544789
2433130.851290437063645.08243896
#Sta/Elev= 30
    1000  471.77 1234.62  464.22 1701.25  468.97 3458.56  461.65 4002.06  457.71
 5995.61     460 6031.76     452 6055.88     438    6082   429.9 6116.27     438
 6145.24     454 6179.15     460    7243  456.51 7412.84  456.67  7480.2     443
 7742.35     443    7800  456.22 8200.17     454 8537.47   459.4 9349.61  459.66
 9932.04     46811526.57     46611536.24     47011695.48  470.0411725.67     466
11743.38  470.0111887.82  472.7411920.65     46812239.67     46612556.76  471.25
#Mann= 7 ,-1,0
    1000     .04       0 3458.56     .12       0 5995.61     .05       0
 6179.15     .11       0    7243     .05       0 7412.84    .045       0
    7800     .08       0
#XS Ineff= 2 , 0
       0    5992     458    8330       0     470
Permanent Ineff=
       F       F
Bank Sta=5995.61,6179.15
XS Rating Curve= 0 ,0
Exp/Cntr=0.3,0.1

Type RM Length L Ch R = 1 ,144866  ,89,201,293
BEGIN DESCRIPTION:
This cross section corresponds to cross section 145000 of the non-georeferenced CDC model which was the source of this model.
Added XS for Lewisville Atheltic Complex CLOMR.
END DESCRIPTION:
XS GIS Cut Line= 5
2444444.939226517065767.548994562440735.146777337064865.91431488
2440179.557009257064760.134998892438057.010401347064187.95372856
2433368.266826097063564.04487139
#Sta/Elev= 30
    1000   472.3 1194.76  461.87 1626.44  469.13 3451.02  463.97 3736.34     460
 4172.12  457.27 6051.28     460 6090.49     452 6116.02     438    6145   429.7
 6176.63     438 6228.97     460 6328.36  459.78 6399.85     443 6767.83     443
 6827.46  457.16 7411.33     456 7466.17     443 7731.18     443 7786.18     456
 8108.31     456 8824.15     456 9010.82  463.59 9743.44  467.53 11453.9     466
11778.31   472.111803.53     46812018.14     47012035.55     46612311.75  469.92
#Mann= 6 ,-1,0
    1000     .04       0 3736.34     .12       0 6051.28     .05       0
 6228.97     .05       0 6328.36    .045       0 8108.31     .08       0
#XS Ineff= 2 , 0
       0    6029     458    8495       0     470
Permanent Ineff=
       F       F
Bank Sta=6051.28,6228.97
XS Rating Curve= 0 ,0
Exp/Cntr=0.3,0.1

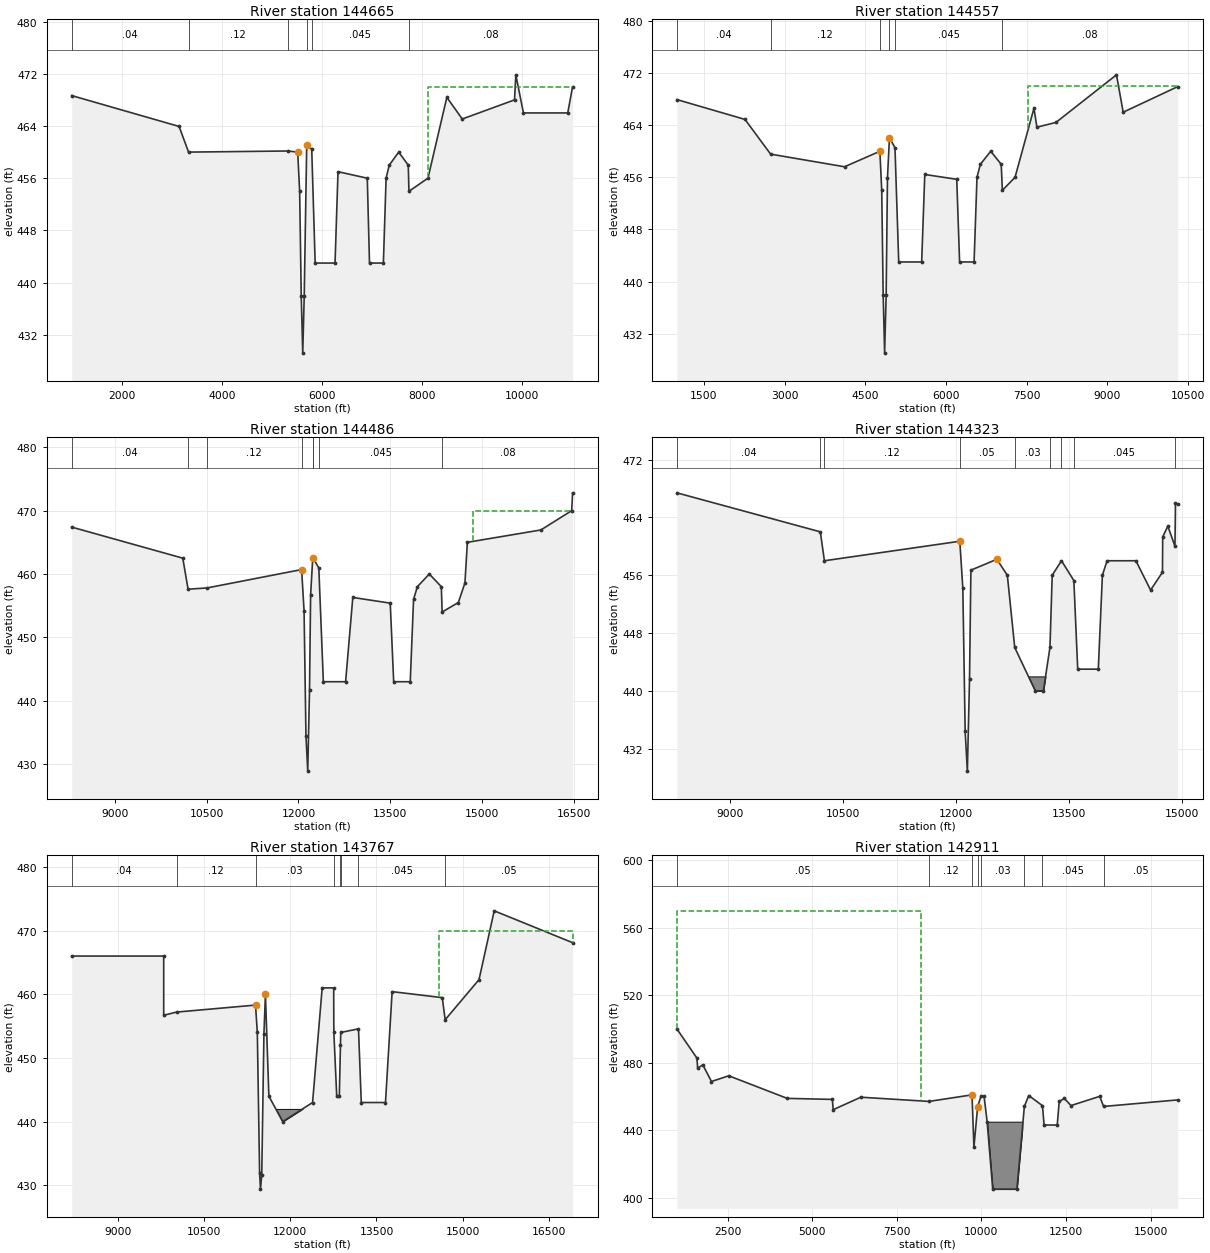
Type RM Length L Ch R = 1 ,144665  ,108,108,162
BEGIN DESCRIPTION:
This cross section corresponds to cross section 144646 of the non-georeferenced CDC model which was the source of this model.
Added XS for Lewisville Atheltic Complex CLOMR.
END DESCRIPTION:
XS GIS Cut Line= 5
2443949.803405767065529.901503972440797.504592277064705.83392638
2440260.166756187064579.254783212438189.185661917064011.10434471
2434167.64514858 7063554.7335383
#Sta/Elev= 30
    1000  468.66 3144.94  463.93 3333.97     460 5314.63  460.17 5514.24     460
 5552.99     454 5584.77     438    5615   429.2 5644.71     438 5694.29  461.08
 5794.43  460.45 5863.14     443  6260.1     443 6319.53     457 6904.17     456
 6948.46     443 7225.61     443 7280.07     456 7343.04     458 7531.96     460
 7722.58     458 7736.29     454 8115.92     456 8493.25  468.39 8801.11  465.07
 9845.37     468 9871.13  471.8410023.42     46610908.52     46611005.13  470.02
#Mann= 6 ,-1,0
    1000     .04       0 3333.97     .12       0 5314.63     .05       0
 5694.29     .05       0 5794.43    .045       0 7736.29     .08       0
#XS Ineff= 2 , 0
       0 5514.24     458    8110       0     470
Permanent Ineff=
       F       F
Bank Sta=5514.24,5694.29
XS Rating Curve= 0 ,0
Exp/Cntr=0.3,0.1

Type RM Length L Ch R = 1 ,144557  ,71,71,71
BEGIN DESCRIPTION:
This cross section corresponds to cross section 144554 of the non-georeferenced CDC model which was the source of this model.
Added XS for Lewisville Atheltic Complex CLOMR.
END DESCRIPTION:
XS GIS Cut Line= 5
2443220.874417427065268.569677552440831.276506337064619.02373254
 2440304.05807267064481.228732562438260.802316587063915.20099321
2434118.101284417063490.54173756
#Sta/Elev= 30
    1000  467.94 2266.35  464.89 2742.04  459.56  4115.2  457.62 4771.73     460
 4806.33     454  4833.1     438    4860     429 4888.67     438 4912.92  455.94
 4949.96  462.08  5052.5  460.55 5121.92     443 5548.33     443 5606.34  456.44
 6200.02  455.69 6252.98     443 6522.04     443 6576.31     456 6638.77     458
 6831.33     460 7026.35     458 7047.53     454 7283.14     456 7634.76  466.61
  7689.1   463.7 8043.26  464.43 9167.73  471.74 9292.68     46610305.85  469.93
#Mann= 6 ,-1,0
    1000     .04       0 2742.04     .12       0 4771.73     .05       0
 4949.96     .05       0  5052.5    .045       0 7047.53     .08       0
#XS Ineff= 2 , 0
       0    4781     458    7530       0     470
Permanent Ineff=
       F       F
Bank Sta=4771.73,4949.96
XS Rating Curve= 0 ,0
Exp/Cntr=0.3,0.1

Type RM Length L Ch R = 1 ,144486  ,155,163,155
BEGIN DESCRIPTION:
This cross section corresponds to cross section 144474 of the non-georeferenced CDC model which was the source of this model.
END DESCRIPTION:
XS GIS Cut Line= 3
2443218.701849587065221.590768892438307.751041597063852.31004289
2435247.728946427063561.08523163
#Sta/Elev= 30
    8300   467.4   10112   462.5   10199   457.6   10508   457.8   12051   460.7
   12091   454.2   12122   434.4   12151  428.89   12180   441.7   12198   456.7
   12233   462.6   12240   462.5 12331.7  460.9412405.75     44312768.79     443
12886.31   456.313497.03   455.413553.14     443 13823.4     44313877.68     456
13939.99     45814134.51     46014330.39     45814343.79     454   14608   455.5
   14716   458.6   14755     46515955.06  466.9516457.94     47016472.12  472.81
#Mann= 8 ,-1,0
    8300     .04       0   10199     .09       0   10508     .12       0
   12051     .05       0   12233      .1       0   12240     .05       0
 12331.7    .045       014343.79     .08       0
#XS Ineff= 2 , 0
       0   12051     458   14850       0     470
Permanent Ineff=
       F       F
Bank Sta=12051,12233
XS Rating Curve= 0 ,0
Exp/Cntr=0.3,0.1

Type RM Length L Ch R = 1 ,144323  ,111,167,261
BEGIN DESCRIPTION:
This cross section corresponds to cross section 144314 of the non-georeferenced CDC model which was the source of this model.
Added cross-section
END DESCRIPTION:
XS GIS Cut Line= 4
2443258.935036847065105.671053222439044.389332097063883.30243497
2438185.70568201 7063684.66438082436821.044041257063559.26732188
#Sta/Elev= 30
    8300   467.4   10202     462   10256     458   12051   460.7   12091   454.2
   12122   434.4   12151  428.89   12180   441.7   12198   456.7   12542   458.2
   12681     456   12779     446   13051     440   13159     440   13246     446
   13276     456   13399     45813562.81  455.2613614.04     44313886.99     443
13941.31     45614003.39     45814385.64     45814580.24  453.9414737.65  456.41
 14740.7  461.29 14808.5  462.7914903.27     460   14910     466   14940   465.8
#Mann= 9 ,-1,0
    8300     .04       0   10202     .09       0   10256     .12       0
   12051     .05       0   12779     .03       0   13246     .05       0
   13399     .08       013562.81    .045       014903.27     .08       0
#Block Obstruct= 1 ,-1
   12961   13201     442
Bank Sta=12051,12542
XS Rating Curve= 0 ,0
Exp/Cntr=0.3,0.1

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
Type RM Length L Ch R = 1 ,143767  ,622,518,306
BEGIN DESCRIPTION:
This cross section corresponds to cross section 143756 of the non-georeferenced CDC model which was the source of this model.
Proposed Park Improvements - 13187.64-14694.95
END DESCRIPTION:
XS GIS Cut Line= 3
2442968.259765187064576.398817792438685.958946597063175.14899564
2434494.472250857062834.95020096
#Sta/Elev= 30
    8200     466    9800     466    9800   456.7   10024   457.2   11397   458.3
   11428     454   11468   431.9   11483   429.4   11505   431.6   11543   453.8
   11569     460   11629     444   11869     440   12389     443   12556     461
   12756     461   12759     454   12809     444   12854     444   12874     452
   12879     45413187.64  454.5713236.01     44313656.82     44313772.62  460.41
14644.48  459.4714694.95     456   15284   462.3   15548   473.1   16911   468.1
#Mann= 8 ,-1,0
    8200     .04       0   10024     .12       0   11397     .03       0
   12756     .04       0   12874     .12       0   12879     .05       0
13187.64    .045       014694.95     .05       0
#XS Ineff= 2 , 0
       0   11358     458   14580       0     470
Permanent Ineff=
       F       F
#Block Obstruct= 1 ,-1
   11669   12269     442
Bank Sta=11397,11569
XS Rating Curve= 0 ,0
Exp/Cntr=0.3,0.1

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
Type RM Length L Ch R = 1 ,142911  ,185,252,195
BEGIN DESCRIPTION:
This cross section corresponds to cross section 142900 of the non-georeferenced CDC model which was the source of this model.
Proposed Park Improvements
END DESCRIPTION:
XS GIS Cut Line= 6
2448547.842109927065479.617155722440570.55885193 7062784.4890158
2439751.839032687062788.279034472437343.548901777062371.20014422
2435732.283423517062236.658090472434237.485531177062111.84118035
#Sta/Elev= 30
    1000     500    1593   482.7    1614   476.7    1767   478.7    2022   468.8
    2534   472.2    4261   458.8    5594   458.2    5620   452.1    6436   459.5
    8450     457    9721   460.9    9778  429.91    9887   453.8    9983     460
   10078     460   10168     445   10333     405   11048     405   11268     454
   11398   460.511802.65  454.4711851.17     44312239.32     44312298.18     457
12451.44  458.7512646.12  454.5513494.93     46013608.97  454.01   15800   457.9
#Mann= 8 ,-1,0
    1000     .05       0    8450     .12       0    9721     .05       0
    9887      .1       0    9983     .03       0   11268     .03       0
11802.65    .045       013608.97     .05       0
#XS Ineff= 2 , 0
       0    8200     570               0
Permanent Ineff=
       F       F
#Block Obstruct= 1 ,-1
   10168   11208     445
Bank Sta=9721,9887
XS Rating Curve= 0 ,0
Exp/Cntr=0.3,0.1

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