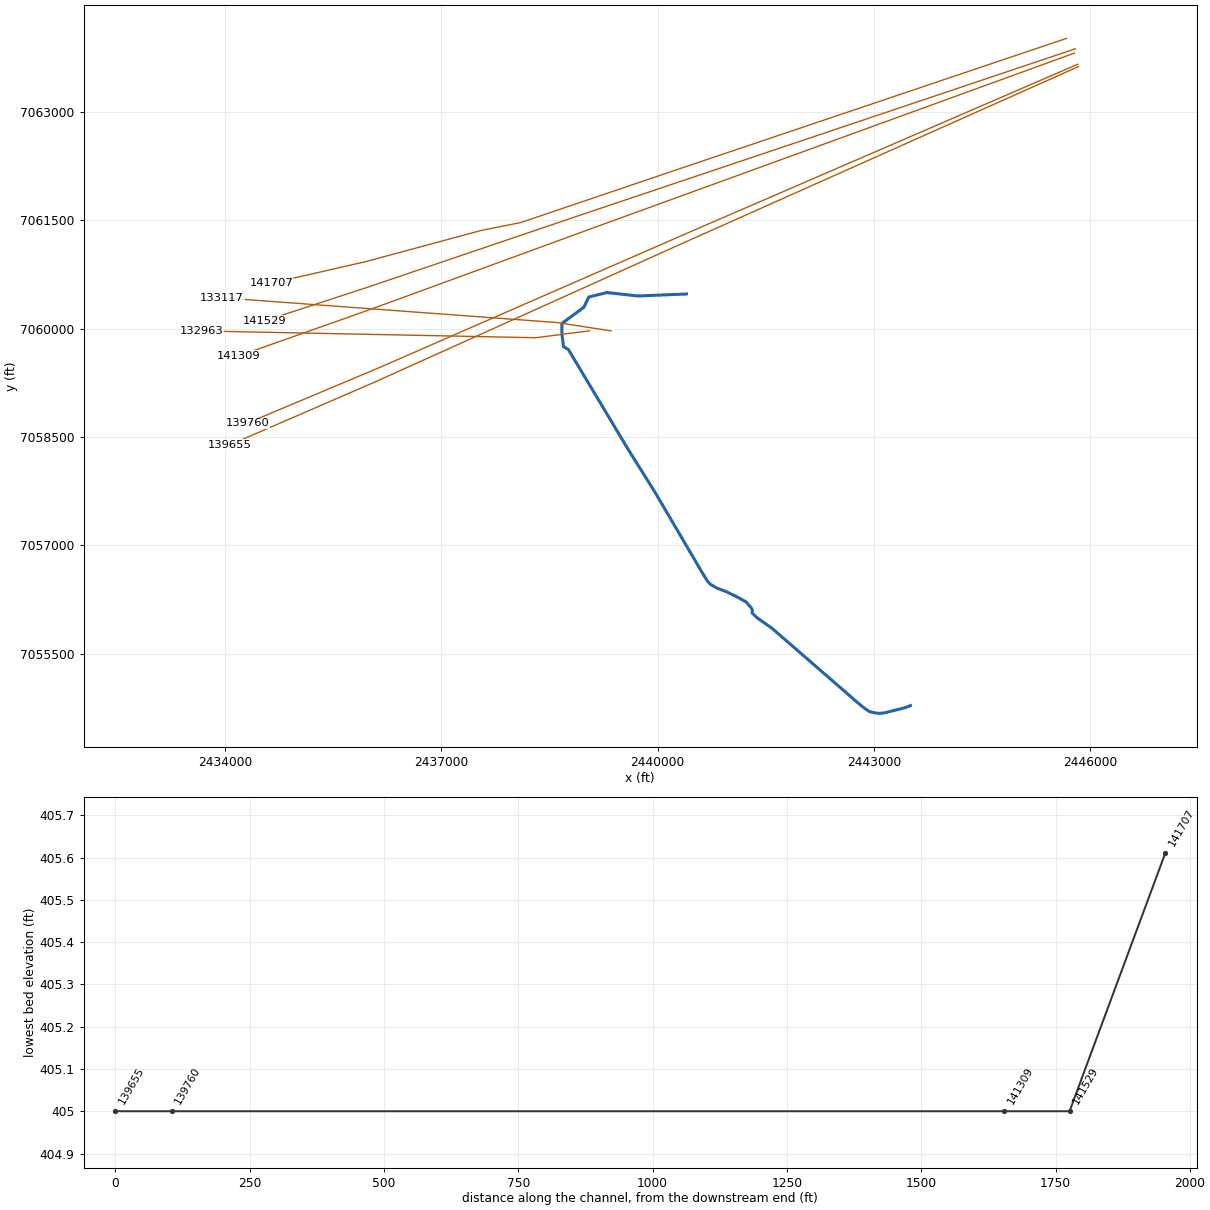
HEC-RAS study CDC_Consolidated_Model.prj: Upper Trinity CDC Consolidated Model

--- CDC_Consolidated_Model.g02 (geometry) --- (continued)

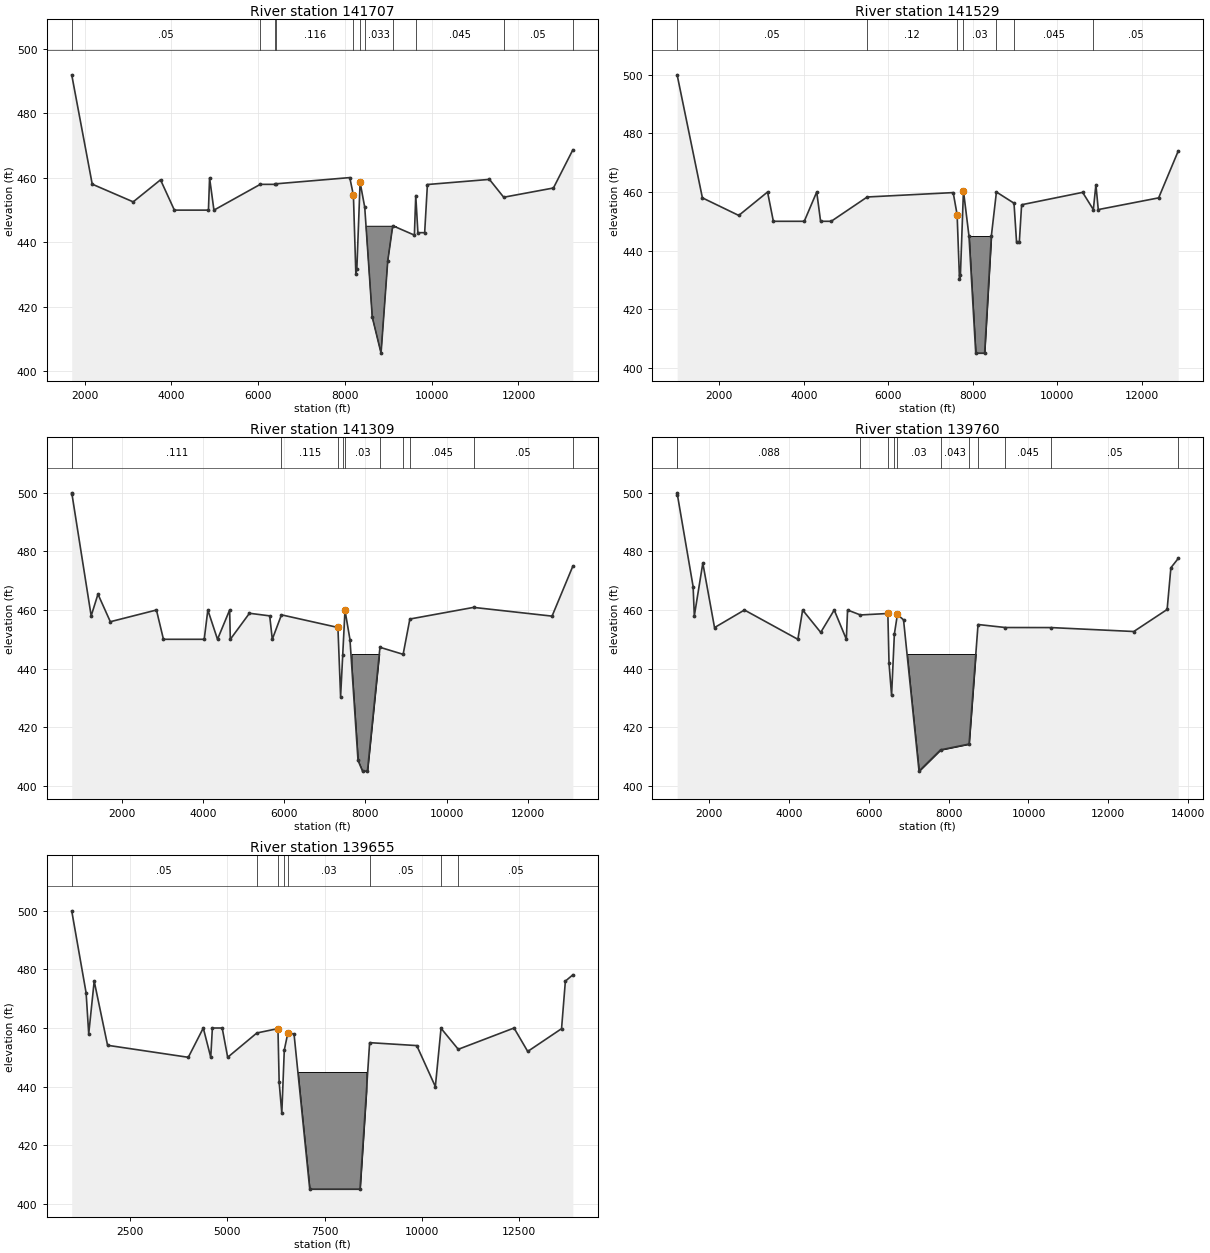
Type RM Length L Ch R = 1 ,141707  ,64,178,224
BEGIN DESCRIPTION:
This cross section corresponds to cross section 141891 of the non-georeferenced CDC model which was the source of this model.
Added XS for Lewisville Atheltic Complex CLOMR.
END DESCRIPTION:
XS GIS Cut Line= 6
   2445675.46499   7064022.81028 2440331.6065739 7062225.5521416
 2438102.0516498 7061471.7281899 2437558.2827243 7061363.5584587
 2435940.1183097 7060928.2164816 2434640.6839007 7060631.7269171
#Sta/Elev= 30
    1700     4922172.853458.05993117.467452.56643747.429459.40784067.159     450
4852.577     4504878.554     4604979.249     4506047.372     4586394.861     458
 6405.51  458.16 8111.09   460.1 8195.09  454.62 8251.36  430.19 8274.31  431.78
 8349.41  458.62 8456.11   450.9    8630  416.76 8832.49  405.61 8986.77   434.2
 9102.48  445.16 9601.18  442.24 9632.55  454.53  9681.8     443 9838.17     443
 9901.32  457.9511331.01  459.5411660.27     45412807.09  456.87 13254.5  468.71
#Mann= 11 ,-1,0
    1700     .05       06047.372     .05       06394.861    .113       0
 6405.51    .116       0 8195.09     .05       0 8349.41    .049       0
 8456.11    .033       0 9102.48    .052       0 9632.55    .045       0
11660.27     .05       0 13254.5    .045       0
#Block Obstruct= 1 ,-1
    8480 9188.54     445
Bank Sta=8195.09,8349.41
XS Rating Curve= 0 ,0
Exp/Cntr=0.3,0.1

Type RM Length L Ch R = 1 ,141529  ,71,122,150
BEGIN DESCRIPTION:
This cross section corresponds to cross section 141518 of the non-georeferenced CDC model which was the source of this model.
Proposed Park Improvements
END DESCRIPTION:
XS GIS Cut Line= 5
    2445796.5051   7063878.11306  2441757.547291 7062523.7054166
 2439044.7587539 7061614.0100576 2435962.6251544 7060571.4169984
 2434543.2283869 7060108.2647095
#Sta/Elev= 30
    1000     5001598.488     4582459.837     4523141.728     4603279.137     450
4010.772     4504306.086     4604397.665     4504648.871     450    5502   458.3
    7538   459.8    7631   452.3    7687   430.3    7709   431.6    7781   460.4
    7912     445    8072     405    8282     405    8442     445    8562     460
 8978.41  456.18 9038.35     443 9104.72     443 9158.59  455.6510603.44  459.88
10857.37     454   10918   462.5   10974     454   12404     458   12868     474
#Mann= 7 ,-1,0
    1000     .05       0    5502     .12       0    7631     .05       0
    7781     .03       0    8562     .06       0 8978.41    .045       0
10857.37     .05       0
#Block Obstruct= 1 ,-1
    7912    8442     445
Bank Sta=7631,7781
XS Rating Curve= 0 ,0
Exp/Cntr=0.3,0.1

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
Type RM Length L Ch R = 1 ,141309  ,422,1549,279
BEGIN DESCRIPTION:
This cross section corresponds to cross section 141084 of the non-georeferenced CDC model which was the source of this model.
Added XS for Lewisville Atheltic Complex CLOMR.
Swale normal pool elevation 453.5
END DESCRIPTION:
XS GIS Cut Line= 6
   2445785.53104    7063818.9137  2441511.608807 7062269.2869622
 2438997.3858172 7061357.6870794 2436348.4878998 7060390.0741852
 2435872.7778932 7060218.2661299 2434190.9876216 7059626.2236788
#Sta/Elev= 30
     774     500778.8699 499.6711252.676     4581419.875465.40811723.919     456
 2858.42     4603030.919     4504033.788     4504122.915     4604360.842     450
4659.301     4604676.231     4505146.837458.88725645.255     458 5708.92     450
 5934.26  458.35 7323.61  454.04 7389.57  430.44 7441.21  444.54 7497.45  459.89
 7619.84  449.93 7818.14  408.64 7928.86     405 8049.56     405 8358.13  447.27
 8928.09  444.87 9093.79  456.9210660.47  460.8912592.07  457.91 13103.4  474.96
#Mann= 11 ,-1,0
     774     .05       0778.8699    .111       0 5934.26    .115       0
 7323.61    .048       0 7441.21    .052       0 7497.45     .03       0
 8358.13    .055       0 8928.09    .049       0 9093.79    .045       0
10660.47     .05       0 13103.4     .05       0
#Block Obstruct= 1 ,-1
7659.0078473.479     445
Bank Sta=7323.61,7497.45
XS Rating Curve= 0 ,0
Exp/Cntr=0.3,0.1

Type RM Length L Ch R = 1 ,139760  ,103,105,103
BEGIN DESCRIPTION:
This cross section corresponds to cross section 139890 of the non-georeferenced CDC model which was the source of this model.
Added XS for Lewisville Atheltic Complex CLOMR.
Swale normal pool elevation 453.5
END DESCRIPTION:
XS GIS Cut Line= 5
   2445830.53784   7063664.34774  2441895.766503 7061965.7518081
 2440327.8103217 7061288.8830831 2436120.7544313 7059455.0340606
  2434305.973284  7058693.486043
#Sta/Elev= 30
    1200     5001207.549499.29291600.411     468 1630.78     4581843.391     476
2136.795     4542885.903     4604224.158     4504343.372     4604796.403452.3515
5134.408     4605438.438     450 5468.72     460 5789.87  458.31 6477.94  458.81
 6507.17  441.81 6571.28  430.82 6641.22   451.8 6717.37  458.49 6870.93  456.62
 7258.65     405 7797.24  412.25 8512.36  414.24 8736.59  455.05    9421  454.02
   10571     45412637.77  452.6613472.71  460.1813566.76  474.4213751.03   477.6
#Mann= 12 ,-1,0
    1200     .05       01207.549    .088       0 5789.87    .144       0
 6477.94    .041       0 6641.22    .092       0 6717.37     .03       0
 7797.24    .043       0 8512.36    .048       0 8736.59     .05       0
    9421    .045       0   10571     .05       013751.03     .05       0
#Block Obstruct= 1 ,-1
6962.984    9000     445
Bank Sta=6477.94,6717.37
XS Rating Curve= 0 ,0
Exp/Cntr=0.3,0.1

Type RM Length L Ch R = 1 ,139655  ,0,0,0
BEGIN DESCRIPTION:
This cross section corresponds to cross section 139643 of the non-georeferenced CDC model which was the source of this model.
---------------------------------------------------------------------
CDC LEW110305-1 Lewisville Athletic Complex
Cross-section 139643 - 146373
Project located in ROB.
---------------------------------------------------------------------
END DESCRIPTION:
XS GIS Cut Line= 5
   2445840.16414   7063631.77366  2441711.337082 7061792.4299763
 2440311.3900789 7061168.7701344 2436073.6820189 7059261.6181088
 2434067.9042063 7058394.1267336
#Sta/Elev= 30
    1000     5001369.871     4721437.134     4581577.627     4761922.011454.0978
3998.008     4504382.987     4604575.025     4504616.718     4604869.331     460
5010.003     450    5760   458.3    6303   459.8    6334   441.4    6402   430.9
    6466   452.5    6556   458.2    6716     458    7120     405    8413     405
    8660     455    9872     454   10350     440   10496   459.9   10939  452.73
   12373     460   12725     452   13595  459.77   13693     476   13885  478.15
#Mann= 8 ,-1,0
    1000     .05       0    5760     .15       0    6303     .04       0
    6466      .1       0    6556     .03       0    8660     .05       0
   10496     .03       0   10939     .05       0
#Block Obstruct= 1 ,-1
    6819    8578     445
Bank Sta=6303,6556
XS Rating Curve= 0 ,0
Exp/Cntr=0.3,0.1

River Reach=Elm Fork Split2 ,efs2
Reach XY= 30
      2440400.92      7060482.14       2439724.1      7060454.22
      2439297.21      7060501.84      2439044.88      7060439.71
      2438975.07      7060297.12      2438672.06      7060074.32
      2438672.06      7059921.33      2438694.34      7059753.48
      2438761.18      7059713.38      2439574.71      7058356.55
      2439972.31      7057721.91      2440604.42      7056646.97
      2440688.53      7056509.34      2440730.74      7056461.97
      2440822.83       7056408.5      2440939.57      7056364.69
      2441092.49      7056292.05       2441226.1      7056217.92
      2441302.25       7056131.3      2441314.62      7056100.84
      2441310.81      7056063.72       2441382.2      7055996.14
      2441589.26      7055850.01      2442820.61      7054783.54
      2442930.53      7054701.84      2443016.68      7054679.56
      2443082.03      7054673.62      2443154.81      7054682.53
      2443443.72      7054755.15      2443507.86      7054781.77

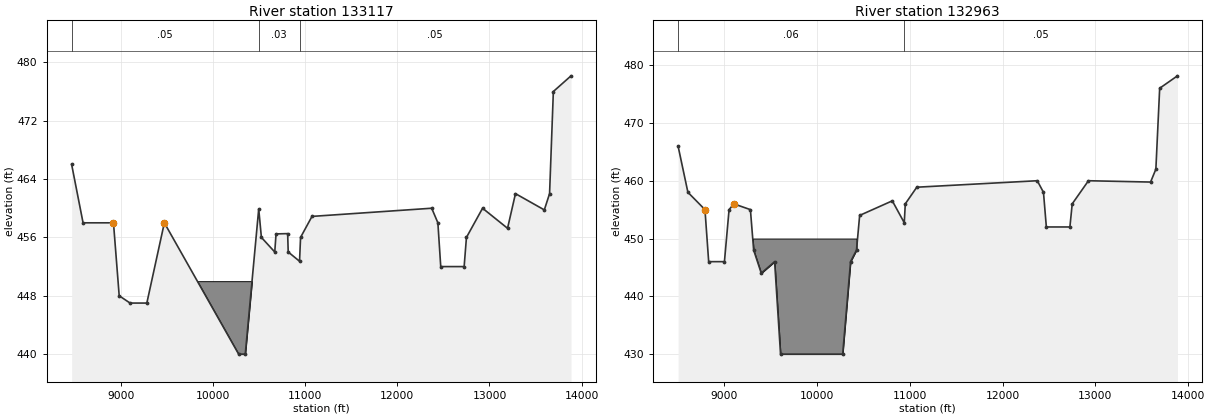
Type RM Length L Ch R = 1 ,133117  ,91,154,154
BEGIN DESCRIPTION:
This cross section corresponds to cross section 132950 of the non-georeferenced CDC model which was the source of this model.
This section is lined with rock rap rip in the graded portion.
END DESCRIPTION:
XS GIS Cut Line= 5
 2439354.44186167059971.015312052438603.42499092 7060086.8211828
2434066.766085277060421.018677132434019.738292167060424.48290905
2433956.908365347060429.11150871
#Sta/Elev= 30
    8466     466    8590     458    8920     458    8982     448    9100     447
    9282     447    9472     458   10278     440   10350     440   10496   459.9
   10525     456   10670     454   10684  456.48   10810  456.52   10816     454
   10939  452.73   10950     456   11074  458.88   12373     460   12440     458
   12471     452   12725     452   12750     456   12925     460   13196  457.25
   13282     462   13595  459.77   13652     462   13693     476   13885  478.15
#Mann= 3 ,-1,0
    8466     .05       0   10496     .03       0   10939     .05       0
#Block Obstruct= 1 ,-1
    9646   10439     450
Bank Sta=8920,9472
XS Rating Curve= 0 ,0
Exp/Cntr=0.5,0.3

Type RM Length L Ch R = 1 ,132963  ,174,247,306
BEGIN DESCRIPTION:
This cross section corresponds to cross section 132780 of the non-georeferenced CDC model which was the source of this model.
NOTE: topo east of railroad tracks updated Feb 2002 by Freese & Nichols, Inc.
END DESCRIPTION:
XS GIS Cut Line= 3
2439053.510048757059971.894575392438310.216915947059876.37409714
2433675.567392597059969.96478921
#Sta/Elev= 30
    8500     466    8606     458    8790     455    8830     446    9000     446
    9050     455    9101     456    9280     455    9315     448    9397     444
    9541     446    9605     430   10275     430   10360     446   10424     448
   10458     454   10810  456.52   10939  452.73   10950     456   11074  458.88
   12373     460   12440     458   12471     452   12725     452   12750     456
   12925     460   13595  459.77   13652     462   13693     476   13885  478.15
#Mann= 2 ,-1,0
    8500     .06       0   10939     .05       0
#Block Obstruct= 1 ,-1
    9307   10425     450
Bank Sta=8790,9101
XS Rating Curve= 0 ,0
Exp/Cntr=0.5,0.3