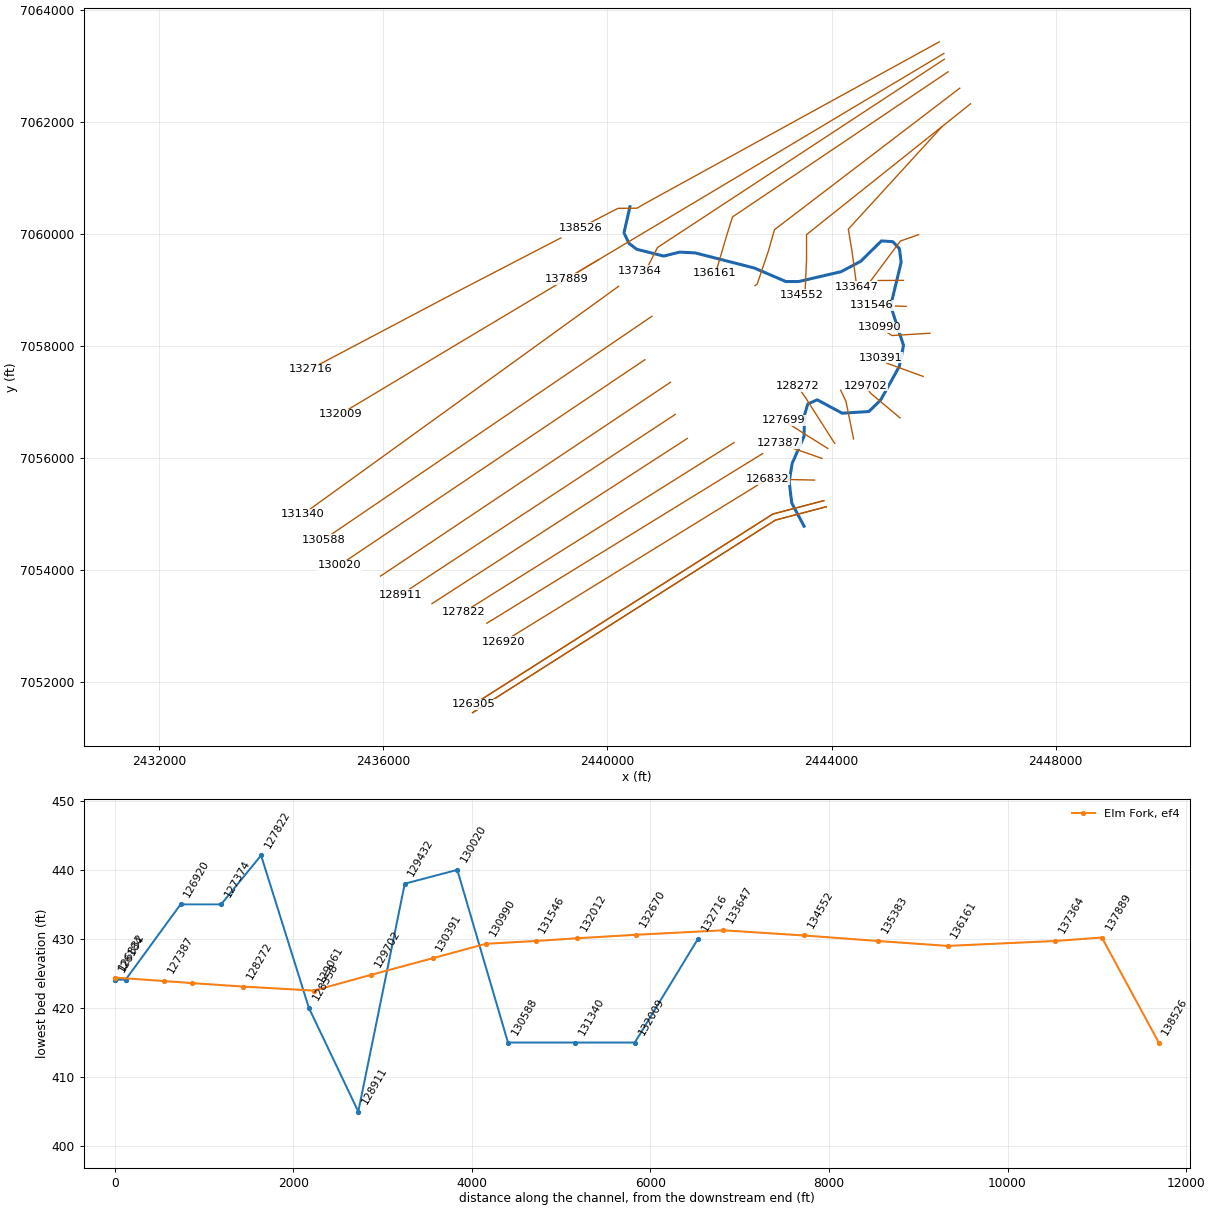
HEC-RAS study CDC_Consolidated_Model.prj: Upper Trinity CDC Consolidated Model

--- CDC_Consolidated_Model.g02 (geometry) --- (continued)

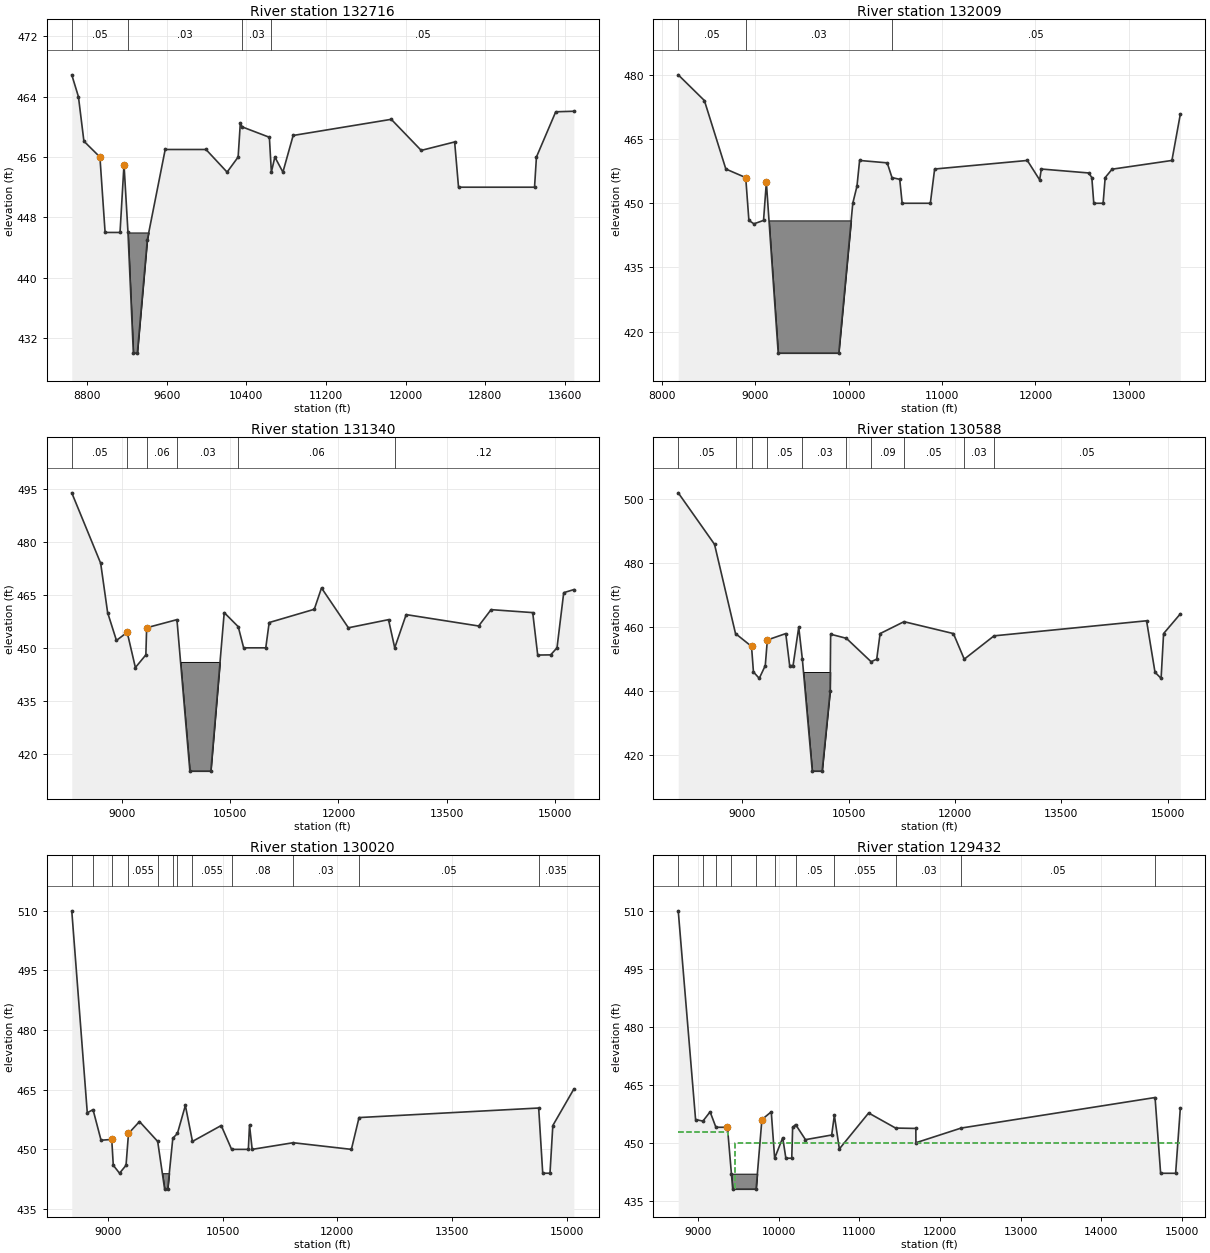
Type RM Length L Ch R = 1 ,132716  ,697,707,737
BEGIN DESCRIPTION:
This cross section corresponds to cross section 132538 of the non-georeferenced CDC model which was the source of this model.
NOTE: topo east of railroad tracks updated Feb 2002 by Freese & Nichols, Inc.
END DESCRIPTION:
XS GIS Cut Line= 3
2439167.494400837059925.544274392437240.019909357058926.38715197
2434697.548288267057584.31568913
#Sta/Elev= 30
    8645   466.9    8712     464    8767   458.1    8928     456    8980     446
    9130     446    9170     455    9210     446    9264     430    9304     430
    9404     445    9584     457    9994     457   10206     454   10317     456
   10339   460.5   10357     460   10631  458.62   10651     454   10686     456
   10767     454   10870  458.86   11856     461   12157  456.88   12493     458
   12532     452   13296     452   13315     456   13509     462   13691  462.07
#Mann= 4 ,-1,0
    8645     .05       0    9210     .03       0   10357     .03       0
   10651     .05       0
#Block Obstruct= 1 ,-1
    9184    9444     446
Bank Sta=8928,9170
XS Rating Curve= 0 ,0
Exp/Cntr=0.3,0.1

Type RM Length L Ch R = 1 ,132009  ,649,669,709
BEGIN DESCRIPTION:
This cross section corresponds to cross section 131838 of the non-georeferenced CDC model which was the source of this model.
NOTE: topo east of railroad tracks updated Feb 2002 by Freese & Nichols, Inc.
END DESCRIPTION:
XS GIS Cut Line= 3
2439844.869030337059539.183498552437484.033857027058129.90711764
2435228.776556497056777.78810272
#Sta/Elev= 30
    8173     480    8453     474    8683     458    8896     456    8930     446
    8984   445.2    9087     446    9117   454.9    9244     415    9893     415
   10043     450   10088     454   10116     460   10412  459.44   10463     456
   10546  455.59   10572     450   10874     450   10920     458   11913     460
   12045  455.46   12063     458   12570  457.08   12604     456   12625     450
   12725     450   12747     456   12821  457.96   13462     460   13552  470.79
#Mann= 3 ,-1,0
    8173     .05       0    8896     .03       0   10463     .05       0
#Block Obstruct= 1 ,-1
 9145.3310025.86     446
Bank Sta=8896,9117
XS Rating Curve= 0 ,0
Exp/Cntr=0.3,0.1

Type RM Length L Ch R = 1 ,131340  ,762,752,742
BEGIN DESCRIPTION:
This cross section corresponds to cross section 131168 of the non-georeferenced CDC model which was the source of this model.
NOTE: topo east of railroad tracks updated Feb 2002 by Freese & Nichols, Inc.
END DESCRIPTION:
XS GIS Cut Line= 2
  2440198.7528377059062.434123962434567.425845097054996.10006505
#Sta/Elev= 30
    8311     494    8711     474    8807     460    8929   452.1    9078   454.4
    9191   444.4    9336     448    9347   455.7    9766     458    9945     415
   10235     415   10420     460   10614     456   10689     450   10995     450
   11042  457.18   11666  460.94   11766     467   12138  455.69   12693     458
   12779     450   12937  459.43   13940   456.2   14112  460.84   14688     460
   14757  447.95   14936     448   15024     450   15117  465.66   15257  466.53
#Mann= 6 ,-1,0
    8311     .05       0    9078     .03       0    9347     .06       0
    9766     .03       0   10614     .06       0   12779     .12       0
#Block Obstruct= 1 ,-1
 9820.11   10359     446
Bank Sta=9078,9347
XS Rating Curve= 0 ,0
Exp/Cntr=0.3,0.1

Type RM Length L Ch R = 1 ,130588  ,568,568,558
BEGIN DESCRIPTION:
This cross section corresponds to cross section 130418 of the non-georeferenced CDC model which was the source of this model.
NOTE: topo east of railroad tracks updated Feb 2002 by Freese & Nichols, Inc.
END DESCRIPTION:
XS GIS Cut Line= 2
2440793.191936857058527.591361632434936.904764927054543.52419855
#Sta/Elev= 30
    8094     502    8606   485.9    8902     458    9128     454    9155     446
    9237     444    9322     448    9351     456    9611     458    9666     448
    9714     448    9794     460    9845     450    9985     415   10124     415
   10237     440   10244   457.8   10466  456.52   10815   449.2   10894     450
   10942     458   11279  461.72   11976     458   12129     450   12549  457.29
   14701     462   14820  445.91   14906     444   14941     458   15177  464.15
#Mann= 10 ,-1,0
    8094     .05       0    8902     .06       0    9128     .03       0
    9351     .05       0    9845     .03       0   10466     .05       0
   10815     .09       0   11279     .05       0   12129     .03       0
   12549     .05       0
#Block Obstruct= 1 ,-1
    9861 10263.2     446
Bank Sta=9128,9351
XS Rating Curve= 0 ,0
Exp/Cntr=0.3,0.1

Type RM Length L Ch R = 1 ,130020  ,588,588,588
BEGIN DESCRIPTION:
This cross section corresponds to cross section 129848 of the non-georeferenced CDC model which was the source of this model.
NOTE: topo east of railroad tracks updated Feb 2002 by Freese & Nichols, Inc.
END DESCRIPTION:
XS GIS Cut Line= 2
2440667.80143958 7057752.43608782435217.883861757054086.78167371
#Sta/Elev= 30
    8528     510    8731   459.2    8806     460    8911   452.3    9051   452.5
    9071     446    9153     444    9238     446    9270     454    9414     457
 9651.96     452    9743     440    9783     440 9849.89   452.8    9910     454
   10014  461.05   10107     452   10483     456   10619     450   10838     450
   10853  456.12   10888     450   11424  451.67   12186     450   12286     458
   14636   460.4   14689     444   14784     444   14821     456   15096  465.17
#Mann= 12 ,-1,0
    8528     .05       0    8806     .06       0    9051     .03       0
    9270    .055       0 9651.96     .03       0 9849.89    .055       0
    9910     .03       0   10107    .055       0   10619     .08       0
   11424     .03       0   12286     .05       0   14636    .035       0
#Block Obstruct= 1 ,-1
  9714.2  9803.8     444
Bank Sta=9051,9270
XS Rating Curve= 0 ,0
Exp/Cntr=0.3,0.1

Type RM Length L Ch R = 1 ,129432  ,531,521,511
BEGIN DESCRIPTION:
This cross section corresponds to cross section 129258 of the non-georeferenced CDC model which was the source of this model.
NOTE: topo east of railroad tracks updated Feb 2002 by Freese & Nichols, Inc.
END DESCRIPTION:
XS GIS Cut Line= 2
2441124.293308767057349.988729972435950.697684827053891.71775939
#Sta/Elev= 30
    8755     510    8970     456    9061   455.6    9150     458    9222     454
    9365     454    9414     442    9430     438    9720     438    9792     456
    9908     458    9950     446   10050   451.3   10089     446   10162     446
   10173     454   10210   454.7   10332   450.8   10657     452   10690   457.1
   10752   448.4   11115   457.7   11449   453.8   11700   453.7   11701     450
   12262   453.8   14665   461.7   14734   442.1   14920   442.1   14978   458.9
#Mann= 11 ,-1,0
    8755     .05       0    9061     .06       0    9222     .03       0
    9414     .02       0    9720     .03       0    9950     .06       0
   10210     .05       0   10690    .055       0   11449     .03       0
   12262     .05       0   14665    .035       0
#XS Ineff= 2 , 0
            9374   452.9    9462             450
Permanent Ineff=
       F       F
#Block Obstruct= 1 ,-1
    9414    9735     442
Bank Sta=9365,9792
XS Rating Curve= 0 ,0
Exp/Cntr=0.3,0.1

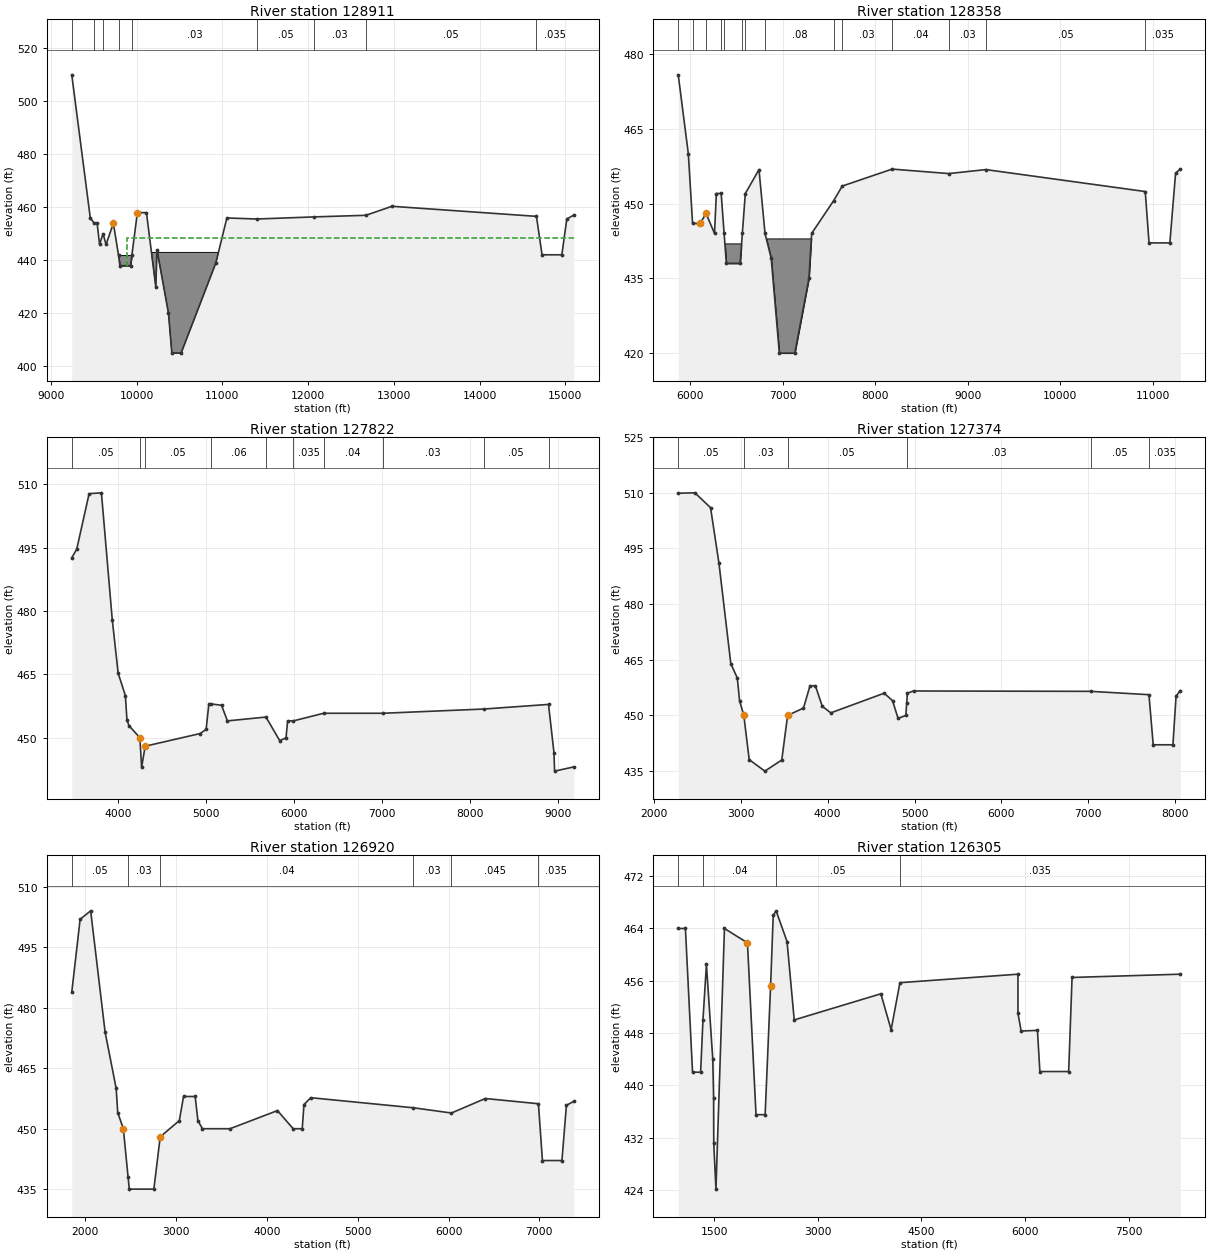
Type RM Length L Ch R = 1 ,128911  ,482,553,472
BEGIN DESCRIPTION:
This cross section corresponds to cross section 128738 of the non-georeferenced CDC model which was the source of this model.
NOTE: topo east of railroad tracks updated Feb 2002 by Freese & Nichols, Inc.
END DESCRIPTION:
XS GIS Cut Line= 2
2441208.818074087056775.937712712436315.32884535 7053561.1610058
#Sta/Elev= 30
    9245     510    9461     456    9508     454    9541     454    9569   446.1
    9610     450    9645     446    9730     454    9790     442    9806     438
    9930     438    9946     442   10010     458   10116     458   10225     430
   10239     444   10373     420   10412     405   10520     405   10925     439
   11054     456   11404   455.6   12073   456.4   12674     457   12979   460.4
   14664   456.6   14729   442.1   14960   442.1   15018   455.6   15100   457.1
#Mann= 9 ,-1,0
    9245     .05       0    9508     .03       0    9610     .03       0
    9790     .02       0    9946     .03       0   11404     .05       0
   12073     .03       0   12674     .05       0   14664    .035       0
#XS Ineff= 2 , 0
       0                    9886       0   448.6
Permanent Ineff=
       F       F
#Block Obstruct= 2 ,-1
    9788    9946     442   10178   10966     443
Bank Sta=9730,10010
XS Rating Curve= 0 ,0
Exp/Cntr=0.3,0.1

Type RM Length L Ch R = 1 ,128358  ,536,536,515
BEGIN DESCRIPTION:
This cross section corresponds to cross section 128188 of the non-georeferenced CDC model which was the source of this model.
NOTE: topo east of railroad tracks updated Feb 2002 by Freese & Nichols, Inc.
END DESCRIPTION:
XS GIS Cut Line= 2
2441425.431486017056347.495656222436868.573473757053400.06027813
#Sta/Elev= 30
    5871   475.8    5980     460    6026     446    6107     446    6172     448
    6263     444    6283     452 6335.19  452.01    6367     444    6391     438
    6540     438    6564     444    6596     452    6744   456.8    6809     444
    6876     439    6964     420    7131     420    7284     435    7313     444
    7552   450.6    7644   453.5    8183   456.9    8796     456    9196   456.8
   10919   452.4   10960   442.1   11185   442.1   11247   456.1   11298   456.9
#Mann= 14 ,-1,0
    5871     .05       0    6026     .07       0    6172     .03       0
 6335.19     .03       0    6367     .02       0    6564     .03       0
    6596     .03       0    6809     .08       0    7552     .05       0
    7644     .03       0    8183     .04       0    8796     .03       0
    9196     .05       0   10919    .035       0
#XS Ineff= 2 , 0
       0    6074   445.9    6161       0   447.1
Permanent Ineff=
       F       F
#Block Obstruct= 2 ,-1
    6809    7373     443    6373    6552     442
Bank Sta=6107,6172
XS Rating Curve= 0 ,0
Exp/Cntr=0.3,0.1

Type RM Length L Ch R = 1 ,127822  ,448,448,437
BEGIN DESCRIPTION:
This cross section corresponds to cross section 127678 of the non-georeferenced CDC model which was the source of this model.
NOTE: topo east of railroad tracks updated Feb 2002 by Freese & Nichols, Inc.
END DESCRIPTION:
XS GIS Cut Line= 2
2442260.192939857056274.711024882437426.586137277053242.43756188
#Sta/Elev= 30
    3473   492.6    3530   494.7    3670   507.8    3810     508    3933     478
    4000   465.3    4082     460    4100   454.3    4122   452.9    4247     450
    4267     443    4307     448    4932     451    5000     452    5031     458
    5060     458    5175   457.7    5242     454    5680   454.9    5837   449.3
    5908     450    5926     454    5992     454    6335   455.8    7006   455.8
    8154   456.8    8891   457.9    8953   446.5    8960   442.1    9179   443.1
#Mann= 10 ,-1,0
    3473     .05       0    4247     .03       0    4307     .05       0
    5060     .06       0    5680     .05       0    5992    .035       0
    6335     .04       0    7006     .03       0    8154     .05       0
    8891    .035       0
Bank Sta=4247,4307
XS Rating Curve= 0 ,0
Exp/Cntr=0.3,0.1

Type RM Length L Ch R = 1 ,127374  ,454,454,454
BEGIN DESCRIPTION:
This cross section corresponds to cross section 127248 of the non-georeferenced CDC model which was the source of this model.
NOTE: topo east of railroad tracks updated Feb 2002 by Freese & Nichols, Inc.
END DESCRIPTION:
XS GIS Cut Line= 2
2442769.560359427056077.474214632437846.038710427053049.71386597
#Sta/Elev= 30
    2280   509.9    2472     510    2652     506    2749     491    2885     464
    2960   460.1    2986     454    3035     450    3097   438.1    3277     435
    3472     438    3539     450    3722     452    3797     458    3859     458
    3938   452.5    4036   450.7    4651     456    4747     454    4811   449.2
    4900     450    4910   453.3    4918     456    4989   456.6    7029   456.5
    7699   455.6    7748   442.1    7975   442.1    8011   455.2    8060   456.7
#Mann= 6 ,-1,0
    2280     .05       0    3035     .03       0    3539     .05       0
    4910     .03       0    7029     .05       0    7699    .035       0
Bank Sta=3035,3539
XS Rating Curve= 0 ,0
Exp/Cntr=0.3,0.1

Type RM Length L Ch R = 1 ,126920  ,615,615,615
BEGIN DESCRIPTION:
This cross section corresponds to cross section 126818 of the non-georeferenced CDC model which was the source of this model.
NOTE: topo east of railroad tracks updated Feb 2002 by Freese & Nichols, Inc.
END DESCRIPTION:
XS GIS Cut Line= 2
2442852.222923767055621.470205382438144.89506808 7052721.3142603
#Sta/Elev= 30
    1851   483.9    1943     502    2059   504.1    2218     474    2340     460
    2357     454    2419     450    2471     438    2485     435    2755     435
    2825     448    3035     452    3082     458    3210     458    3240     452
    3290     450    3594     450    4116   454.5    4289     450    4389     450
    4408     456    4483   457.7    5613   455.2    6032   453.9    6405   457.5
    6990   456.2    7034   442.1    7249   442.1    7298   455.8    7380   456.8
#Mann= 6 ,-1,0
    1851     .05       0    2471     .03       0    2825     .04       0
    5613     .03       0    6032    .045       0    6990    .035       0
Bank Sta=2419,2825
XS Rating Curve= 0 ,0
Exp/Cntr=0.3,0.1

Type RM Length L Ch R = 1 ,126305  ,1,1,1
BEGIN DESCRIPTION:
This cross section corresponds to cross section 126293 of the non-georeferenced CDC model which was the source of this model.
NOTE: topo east of railroad tracks updated Feb 2002 by Freese & Nichols, Inc.
END DESCRIPTION:
XS GIS Cut Line= 4
   2443859.93255   7055237.76534   2442953.04198   7054999.89246
   2438876.95569   7052407.867692437611.203553217051602.96301973
#Sta/Elev= 30
     982     464    1086     464    1189     442    1306     442    1340     450
    1390   458.5    1482     444    1494   438.1    1496   431.1    1528   424.1
    1651     464    1984   461.8    2108   435.5    2240   435.5    2319   455.2
    2357     466    2399   466.7    2557     462    2661     450    3915     454
    4064   448.5    4191   455.7    5900     457    5900     451    5946   448.3
    6182   448.4    6217   442.1    6634   442.1    6683   456.5    8250     457
#Mann= 4 ,-1,0
     982     .03       0    1340     .04       0    2399     .05       0
    4191    .035       0
#Block Obstruct= 2 , 0
       0    1675                       0
Bank Sta=1984,2319
XS Rating Curve= 0 ,0
Exp/Cntr=0.5,0.3

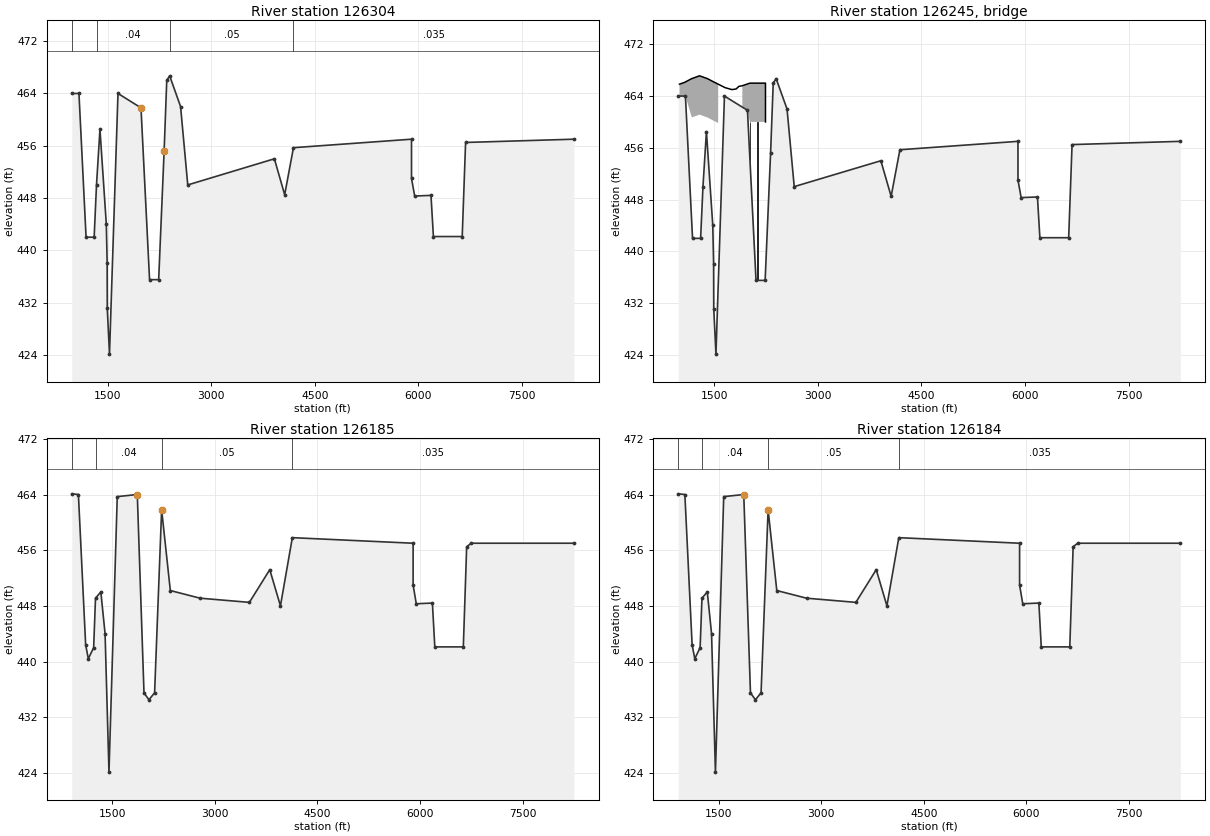
Type RM Length L Ch R = 1 ,126304  ,119,119,119
BEGIN DESCRIPTION:
This cross section corresponds to cross section 126292 of the non-georeferenced CDC model which was the source of this model.
NOTE: topo east of railroad tracks updated Feb 2002 by Freese & Nichols, Inc.
END DESCRIPTION:
XS GIS Cut Line= 4
    2443860.6805   7055237.11435   2442953.78993   7054999.24146
   2438877.70364   7052407.216692437611.951503217051602.31201973
#Sta/Elev= 30
     982     464    1086     464    1189     442    1306     442    1340     450
    1390   458.5    1482     444    1494   438.1    1496   431.1    1528   424.1
    1651     464    1984   461.8    2108   435.5    2240   435.5    2319   455.2
    2357     466    2399   466.7    2557     462    2661     450    3915     454
    4064   448.5    4191   455.7    5900     457    5900     451    5946   448.3
    6182   448.4    6217   442.1    6634   442.1    6683   456.5    8250     457
#Mann= 4 ,-1,0
     982     .03       0    1340     .04       0    2399     .05       0
    4191    .035       0
#Block Obstruct= 2 , 0
       0    1675                       0
Bank Sta=1984,2319
XS Rating Curve= 0 ,0
Exp/Cntr=0.5,0.3

Type RM Length L Ch R = 3 ,126245  ,,,
BEGIN DESCRIPTION:
Hebron Parkway
END DESCRIPTION:
Node Name=Hebron Parkway
Bridge Culvert--1,0,-1,-1, 0
Deck Dist Width WeirC Skew NumUp NumDn MinLoCord MaxHiCord MaxSubmerge Is_Ogee
1,117,2.6,0, 25, 25, , , 0.95, 0, 0,0,,
    1000    1069  1071.5    1179  1181.5    1289  1291.5    1400  1402.5    1510
  1512.5    1560    1560    1660    1760    1820    1860    1910    1910    2019
  2021.5    2129  2131.5    2245    2245
  465.84   466.1   466.1  466.71  466.71  467.13  467.13  466.71  466.71   466.1
   466.1  465.84  465.84   465.3     465   465.1   465.5   465.6   465.6     466
     466     466     466     466     460
  459.84   460.1   460.1  460.71  460.71  461.13  461.13  460.71  460.71   460.1
   460.1  459.84  465.84   465.3     465   465.1   465.5   465.6     460     460
     460     460     460     460     460
    1000    1069  1071.5    1179  1181.5    1289  1291.5    1400  1402.5    1510
  1512.5    1560    1560    1660    1760    1820    1860    1910    1910    2019
  2021.5    2129  2131.5    2245    2245
  465.84   466.1   466.1  466.71  466.71  467.13  467.13  466.71  466.71   466.1
   466.1  465.84  465.84   465.3     465   465.1   465.5   465.6   465.6     466
     466     466     466     466     460
  459.84   460.1   460.1  460.71  460.71  461.13  461.13  460.71  460.71   460.1
   460.1  459.84  465.84   465.3     465   465.1   465.5   465.6     460     460
     460     460     460     460     460
Pier Skew, UpSta & Num, DnSta & Num=  ,2020.25, 2 ,2020.25, 2 , 0 , 0 , 0 ,,
     2.5     2.5
       0     461
     2.5     2.5
       0     461
Pier Skew, UpSta & Num, DnSta & Num=  ,2130.25, 2 ,2130.25, 2 , 0 , 0 , 0 ,,
     2.5     2.5
       0     461
     2.5     2.5
       0     461
BR Coef=-1 , 0 , 0 ,, 0 ,,,0.8,-1,,1,
WSPro=,,,, 1 ,,,, 0 ,,,, 0 ,,,,-1 ,-1 ,-1 , 0 , 0 , 0 , 0 , 0
BC Design=,, 0 ,, 0 ,,,,,,
BC HTab HWMax=465.84
BC Use User HTab Curves=0
BC User HTab FreeFlow(D)= 0

Type RM Length L Ch R = 1 ,126185  ,1,1,1
BEGIN DESCRIPTION:
This cross section corresponds to cross section 126172 of the non-georeferenced CDC model which was the source of this model.
NOTE: topo east of railroad tracks updated Feb 2002 by Freese & Nichols, Inc.
END DESCRIPTION:
XS GIS Cut Line= 5
     2443902.554     7055128.606     2442995.663     7054890.733
     2438885.824     7052277.244     2438857.977     7052259.536
2437592.220936077051454.63750539
#Sta/Elev= 30
     909   464.1    1006     464    1112   442.4    1151   440.4    1229     442
    1256   449.1    1334     450    1396     444    1453   424.1    1574   463.7
    1867     464    1965   435.5    2037   434.5    2120   435.5    2223   461.8
    2350   450.2    2785   449.1    3506   448.5    3804   453.2    3960     448
    4134   457.8    5900     457    5900     451    5946   448.3    6182   448.4
    6217   442.1    6634   442.1    6683   456.5    6750     457    8250     457
#Mann= 4 ,-1,0
     909     .03       0    1256     .04       0    2223     .05       0
    4134    .035       0
#Block Obstruct= 2 , 0
       0    1676                       0
Bank Sta=1867,2223
XS Rating Curve= 0 ,0
Exp/Cntr=0.5,0.3

Type RM Length L Ch R = 1 ,126184  ,0,0,0
BEGIN DESCRIPTION:
This cross section corresponds to cross section 126171 of the non-georeferenced CDC model which was the source of this model.
NOTE: topo east of railroad tracks updated Feb 2002 by Freese & Nichols, Inc.
END DESCRIPTION:
XS GIS Cut Line= 4
2443903.383551097055127.946914212442996.492976437054890.07403038
2438858.807026097052258.876864972437593.054964697051453.97207615
#Sta/Elev= 30
     909   464.1    1006     464    1112   442.4    1151   440.4    1229     442
    1256   449.1    1334     450    1396     444    1453   424.1    1574   463.7
    1867     464    1965   435.5    2037   434.5    2120   435.5    2223   461.8
    2350   450.2    2785   449.1    3506   448.5    3804   453.2    3960     448
    4134   457.8    5900     457    5900     451    5946   448.3    6182   448.4
    6217   442.1    6634   442.1    6683   456.5    6750     457    8250     457
#Mann= 4 ,-1,0
     909     .03       0    1256     .04       0    2223     .05       0
    4134    .035       0
#Block Obstruct= 2 , 0
       0    1676                       0
Bank Sta=1867,2223
XS Rating Curve= 0 ,0
Exp/Cntr=0.5,0.3

River Reach=Elm Fork        ,ef4
Reach XY= 30
      2440400.92      7060482.14      2440294.34      7060015.81
      2440383.31      7059829.47      2440522.78      7059722.76
       2441002.8      7059601.84      2441288.86      7059672.27
      2441563.46      7059658.68      2442618.16      7059389.23
      2443182.24      7059147.58      2443412.14      7059147.38
      2444167.74      7059322.94       2444519.5      7059508.74
      2444888.28      7059871.88      2445091.58       7059858.5
      2445209.51      7059732.61      2445240.46      7059490.37
      2445053.22      7058713.77      2445282.96      7058007.48
      2445208.63      7057633.68      2444876.01      7057035.28
      2444665.63      7056828.23      2444188.86      7056797.96
      2443742.29      7057037.22        2443575.       7056962.7
      2443517.68      7056772.63      2443507.66      7056384.86
      2443297.03      7055905.67      2443242.05      7055579.44
      2443287.84      7055196.61      2443507.86      7054781.77

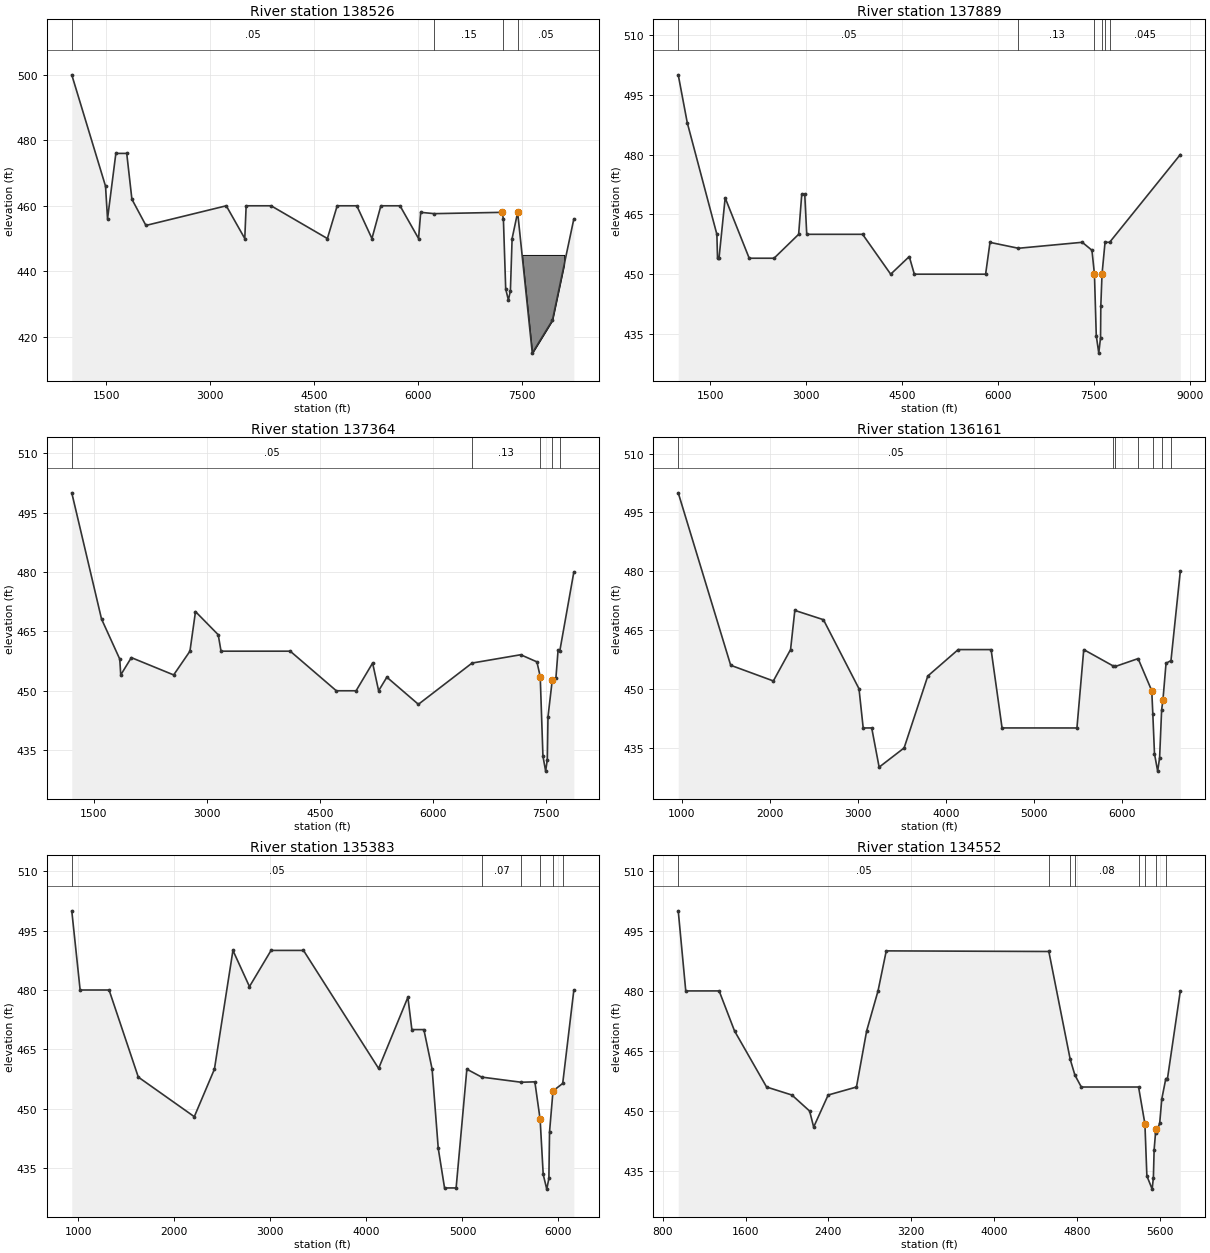
Type RM Length L Ch R = 1 ,138526  ,421,637,701
BEGIN DESCRIPTION:
This cross section corresponds to cross section 138514 of the non-georeferenced CDC model which was the source of this model.
ROCK RIP RAP PORTION OF POND
END DESCRIPTION:
XS GIS Cut Line= 6
   2445920.99665   7063424.07033  2441687.507077 7061098.8896967
 2440710.5710391 7060562.3222003 2440526.5969976 7060455.9730036
 2440186.7151314  7060453.884097 2439518.1777546 7060107.3303281
#Sta/Elev= 30
    1000     5001487.401     4661516.302     4561636.653     4761793.639     476
1868.329     4622070.719     4543231.114     4603498.249     4503518.073     460
3878.572     4604691.068     4504832.649     460 5115.82     4605334.396     450
5463.418     4605739.785     4606007.649     4506038.542     458    6235   457.6
  7212.6     458  7232.7     456    7266   434.6    7305  431.19    7334   434.1
  7358.5     450  7438.6     458    7650     415    7940     425    8250     456
#Mann= 4 ,-1,0
    1000     .05       0    6235     .15       0  7232.7     .04       0
  7438.6     .05       0
#Block Obstruct= 1 ,-1
    7505    8110     445
Bank Sta=7212.6,7438.6
XS Rating Curve= 0 ,0
Exp/Cntr=0.3,0.1

Type RM Length L Ch R = 1 ,137889  ,319,525,669
BEGIN DESCRIPTION:
This cross section corresponds to cross section 137878 of the non-georeferenced CDC model which was the source of this model.
END DESCRIPTION:
XS GIS Cut Line= 3
     2446002.735   7063217.85355  2441817.580308 7060717.8327161
 2439263.5631063 7059192.1792713
#Sta/Elev= 30
    1000     5001140.983     4881604.058     4601614.375     4541637.325     454
1733.895469.13912109.635     4542497.949     4542882.506     4602931.008     470
2978.196     4703009.224     4603882.662     4604321.727     4504612.306454.4227
4691.324     4505805.794     450 5874.59 457.977    6319   456.5  7316.8     458
  7468.5     456  7507.5     450    7536   434.6    7575   430.2    7603   434.1
    7607     442  7625.8     450  7673.2     458    7745     458    8850     480
#Mann= 6 ,-1,0
    1000     .05       0    6319     .13       0  7507.5     .04       0
  7625.8      .1       0  7673.2     .07       0    7745    .045       0
Bank Sta=7507.5,7625.8
XS Rating Curve= 0 ,0
Exp/Cntr=0.3,0.1

Type RM Length L Ch R = 1 ,137364  ,1233,1203,1183
BEGIN DESCRIPTION:
This cross section corresponds to cross section 137352 of the non-georeferenced CDC model which was the source of this model.
END DESCRIPTION:
XS GIS Cut Line= 5
   2446010.16478   7063113.17693  2441821.632137  7060364.305536
 2440892.0168704 7059754.2129241 2440723.4860395 7059421.9852421
 2440581.9295641 7059336.1704531
#Sta/Elev= 30
    1210     5001604.655468.13281846.536     4581859.607     4542000.286458.3746
2561.672     4542777.542     460 2851.19     4703152.595464.15243189.918     460
4108.099     4604719.196     4504981.615     450 5200.63457.0022 5280.35     450
5389.495453.43115807.923446.5769    6520     457    7165   459.1    7380   457.3
    7424   453.6    7460   433.5    7496   429.7    7518   432.6    7527   443.4
    7583   452.6    7632   453.2    7661   460.3    7684   460.1    7870     480
#Mann= 5 ,-1,0
    1210     .05       0    6520     .13       0    7424     .05       0
    7583      .1       0    7684    .045       0
Bank Sta=7424,7583
XS Rating Curve= 0 ,0
Exp/Cntr=0.3,0.1

Type RM Length L Ch R = 1 ,136161  ,789,778,759
BEGIN DESCRIPTION:
This cross section corresponds to cross section 136149 of the non-georeferenced CDC model which was the source of this model.
END DESCRIPTION:
XS GIS Cut Line= 5
   2446077.87363   7062889.65277  2442230.476463 7060299.5599306
 2442123.0035817 7059955.0340448 2441930.7880868 7059301.5041839
 2441915.9967778 7059291.4418681
#Sta/Elev= 30
     962     5001557.286     4562041.457     4522236.795     4602285.182     470
2609.802467.62933013.416 450.0123061.105     440 3157.84 440.0123241.932     430
  3525.5 434.9083794.254453.26014139.198     4604512.671     4604637.029440.0103
5486.837     4405563.988     460    5900   455.8    5923   455.7    6181   457.7
    6336   449.5    6348   443.6    6367   433.4    6403  428.99    6425   432.4
    6448   444.6    6463   447.2    6498   456.5    6554   457.2    6660     480
#Mann= 7 ,-1,0
     962     .05       0    5900      .1       0    5923     .07       0
    6181      .1       0    6348     .05       0    6448      .1       0
    6554    .045       0
Bank Sta=6336,6463
XS Rating Curve= 0 ,0
Exp/Cntr=0.3,0.1

Type RM Length L Ch R = 1 ,135383  ,729,831,849
BEGIN DESCRIPTION:
This cross section corresponds to cross section 135370 of the non-georeferenced CDC model which was the source of this model.
END DESCRIPTION:
XS GIS Cut Line= 6
   2446286.48378   7062597.42238  2443061.265156 7060134.6337512
 2442980.1465524 7060072.6912898 2442872.0201283 7059693.3967728
 2442670.8151501  7059099.678144 2442632.0845845 7059073.6201252
#Sta/Elev= 30
     932     5001019.138     4801320.523     480 1624.75     4582207.872     448
2417.369     4602610.204     4902782.302480.86223007.138     4903344.886     490
4127.077460.18314431.959478.16654473.341     4704598.328     4704684.343     460
4748.019     4404813.729     4304934.143     4305045.907     460    5200     458
    5611   456.7    5754   456.8    5809   447.3    5841   433.4    5878   429.7
    5900   432.4    5907   444.2    5943   454.5    6044   456.4    6160     480
#Mann= 6 ,-1,0
     932     .05       0    5200     .07       0    5611      .1       0
    5809     .05       0    5943     .08       0    6044    .045       0
Bank Sta=5809,5943
XS Rating Curve= 0 ,0
Exp/Cntr=0.3,0.1

Type RM Length L Ch R = 1 ,134552  ,821,905,921
BEGIN DESCRIPTION:
This cross section corresponds to cross section 134538 of the non-georeferenced CDC model which was the source of this model.
END DESCRIPTION:
XS GIS Cut Line= 6
2446478.774475797062318.488174322443679.896793347060086.29559331
2443552.315027517059984.545140642443552.315027517059537.52208455
2443526.172035167058955.517014972443461.993029687058912.61683831
#Sta/Elev= 30
     950     5001022.603     4801345.108     4801493.955     4701803.493     456
2048.101     4542219.146     4502258.179     4462398.165     4542671.638     456
2769.915     470 2879.97     4802959.483     490    4530489.8436 4736.19462.9355
4781.939458.95964843.612     4565396.818     456    5458   446.8    5477   433.8
    5528   430.5    5540   433.4    5547   440.3    5564   445.6    5568   444.5
    5601     447    5621     453    5660   458.1    5676   458.1    5800     480
#Mann= 8 ,-1,0
     950     .05       0    4530     .05       0 4736.19     .03       0
4781.939     .08       05396.818      .1       0    5458     .05       0
    5568     .09       0    5660    .045       0
Bank Sta=5458,5564
XS Rating Curve= 0 ,0
Exp/Cntr=0.3,0.1

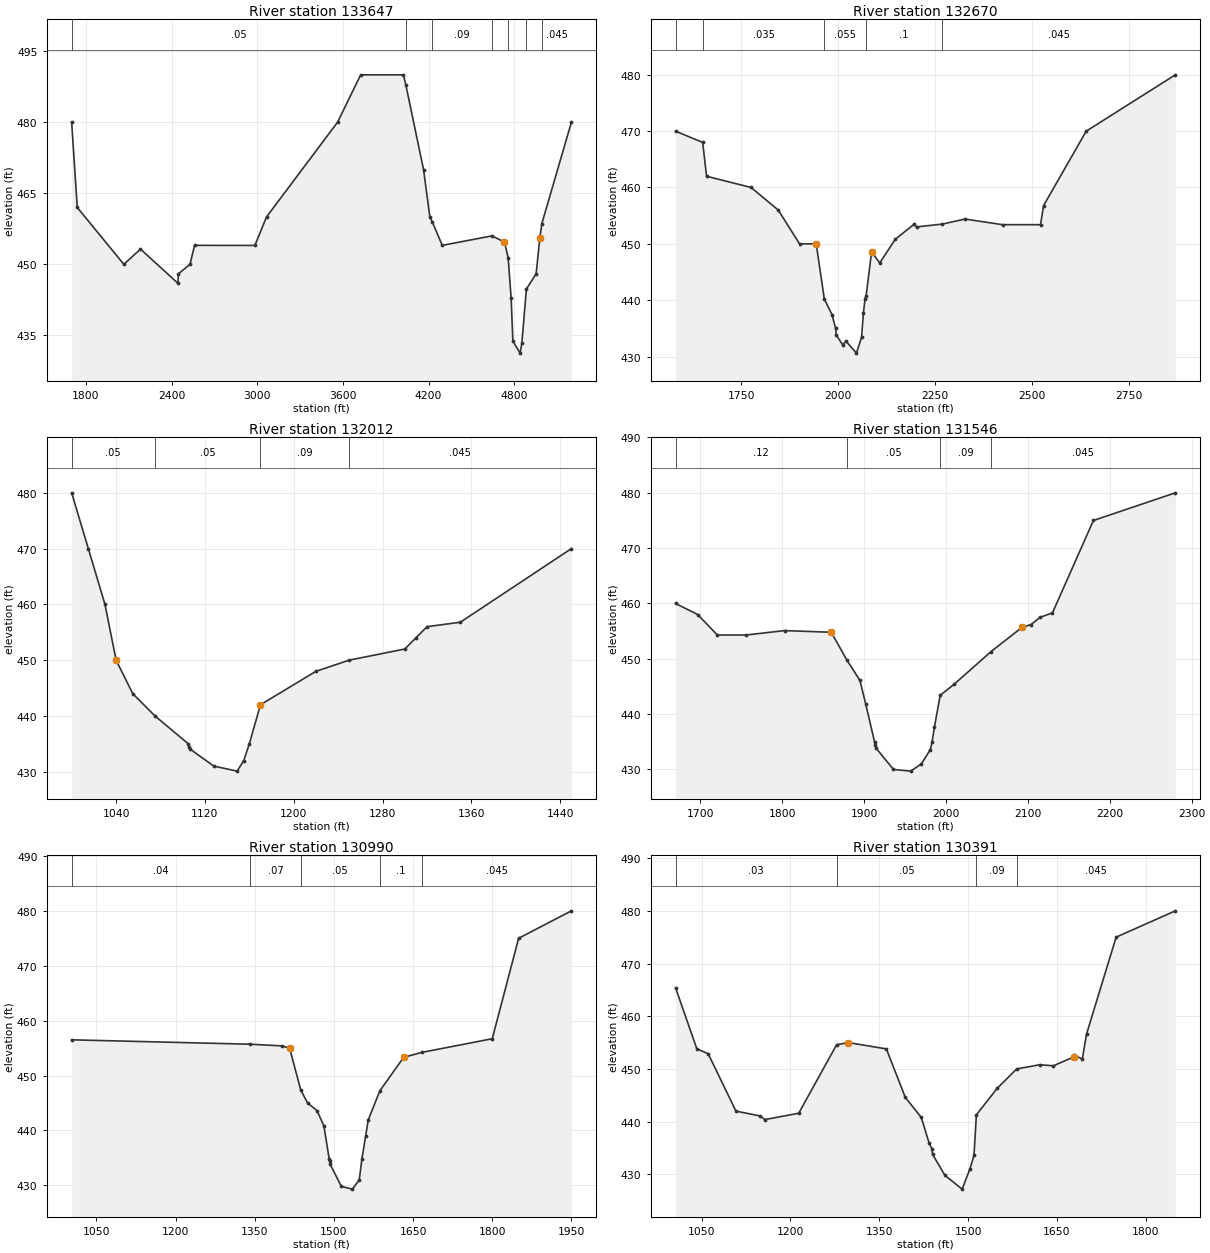
Type RM Length L Ch R = 1 ,133647  ,999,977,649
BEGIN DESCRIPTION:
This cross section corresponds to cross section 133634 of the non-georeferenced CDC model which was the source of this model.
---------------------------------------------------------------------
CDC LEW063011-1 Camelot Landfill
Cross-section 133634 - 134538
Located in LOB.
---------------------------------------------------------------------
END DESCRIPTION:
XS GIS Cut Line= 5
2445960.838502867061901.407539022444382.196241777060174.12973522
2444297.873903847060081.868108722444362.306845847059695.54407822
2444448.880491587059058.04600938
#Sta/Elev= 30
    1700     4801739.155     462 2065.52     4502182.107453.21262444.073     446
2447.858     4482529.027     4502560.779     4542983.234453.98473064.632     460
3562.264     4803724.297     490 4023.01     490    4040487.9333 4164.99469.9083
4208.559     4604226.869458.8767 4295.42     4544643.583     456    4731   454.7
    4757   451.4    4778   442.8    4790   433.8    4841  431.25    4853   433.4
    4885   444.8    4953     448    4979   455.6    4993   458.6    5200     480
#Mann= 7 ,-1,0
    1700     .05       0    4040     .05       04226.869     .09       0
4643.583     .11       0    4757     .04       0    4885     .12       0
    4993    .045       0
Bank Sta=4731,4979
XS Rating Curve= 0 ,0
Exp/Cntr=0.3,0.1

Type RM Length L Ch R = 1 ,132670  ,730,658,430
BEGIN DESCRIPTION:
This cross section corresponds to cross section 132656 of the non-georeferenced CDC model which was the source of this model.
---------------------------------------------------------------------
CDC CAR110497-1 Coyote Ridge Golf Club
Cross-section 132656
Project located in LOB.
---------------------------------------------------------------------
END DESCRIPTION:
XS GIS Cut Line= 3
2445552.465554747059984.042845062445224.724740427059868.39478238
 2444662.00178457059112.37824979
#Sta/Elev= 30
    1580     470    1650     468    1660     462    1775     460    1845     456
    1900     450    1943     450    1964   440.2    1984   437.4    1993     435
    1995   433.8    2011   432.1    2020   432.7    2047   430.6    2060   433.4
    2065   437.8    2069   440.2    2072   440.8    2086   448.6    2107   446.6
    2147   450.8    2196   453.5    2202     453    2268   453.5    2327   454.4
    2424   453.4    2522   453.4    2530   456.8    2640     470    2870     480
#Mann= 5 ,-1,0
    1580     .05       0    1650    .035       0    1964    .055       0
    2072      .1       0    2268    .045       0
Bank Sta=1943,2086
XS Rating Curve= 0 ,0
Exp/Cntr=0.3,0.1

Type RM Length L Ch R = 1 ,132012  ,460,466,450
BEGIN DESCRIPTION:
This cross section corresponds to cross section 131998 of the non-georeferenced CDC model which was the source of this model.
END DESCRIPTION:
XS GIS Cut Line= 2
2445280.482174847059168.430959212444830.489636517059165.79874663
#Sta/Elev= 21
    1000     480    1015     470    1030     460    1040     450    1055     444
    1075     440    1105     435    1106   434.4    1107     434    1128     431
    1149   430.1    1155     432    1160     435    1170     442    1220     448
    1250     450    1300     452    1310     454    1320     456    1350   456.8
    1450     470
#Mann= 4 ,-1,0
    1000     .05       0    1075     .05       0    1170     .09       0
    1250    .045       0
Bank Sta=1040,1170
XS Rating Curve= 0 ,0
Exp/Cntr=0.3,0.1

Type RM Length L Ch R = 1 ,131546  ,541,556,451
BEGIN DESCRIPTION:
This cross section corresponds to cross section 131532 of the non-georeferenced CDC model which was the source of this model.
END DESCRIPTION:
XS GIS Cut Line= 2
2445331.159238857058704.210430962444721.515773097058725.04995622
#Sta/Elev= 27
    1670     460    1697     458    1721   454.3    1756   454.3    1803   455.1
    1860   454.8    1879   449.8    1895   446.1    1902   441.9    1913   434.9
    1914   434.4    1915   433.8    1936     430    1957   429.7    1970     431
    1981   433.6    1983   434.9    1986   437.7    1993   443.4    2010   445.4
    2055   451.3    2093   455.7    2104   456.2    2115   457.5    2130   458.3
    2180     475    2280     480
#Mann= 4 ,-1,0
    1670     .12       0    1879     .05       0    1993     .09       0
    2055    .045       0
Bank Sta=1860,2093
XS Rating Curve= 0 ,0
Exp/Cntr=0.3,0.1

Type RM Length L Ch R = 1 ,130990  ,729,599,449
BEGIN DESCRIPTION:
This cross section corresponds to cross section 130977 of the non-georeferenced CDC model which was the source of this model.
END DESCRIPTION:
XS GIS Cut Line= 3
2445752.870665767058224.918082462445075.839867597058183.76823038
2444852.991231927058333.93065971
#Sta/Elev= 23
    1003   456.5    1341   455.7    1401   455.4    1416     455    1437   447.4
    1450     445    1468   443.6    1481   440.8    1491   434.8    1492   434.4
    1493   433.8    1514   429.8    1535   429.3    1548     431    1553   434.8
    1560   438.9    1565   441.9    1587   447.2    1632   453.3    1666   454.2
    1800   456.7    1850     475    1950     480
#Mann= 5 ,-1,0
    1003     .04       0    1341     .07       0    1437     .05       0
    1587      .1       0    1666    .045       0
Bank Sta=1416,1632
XS Rating Curve= 0 ,0
Exp/Cntr=0.3,0.1

Type RM Length L Ch R = 1 ,130391  ,821,689,501
BEGIN DESCRIPTION:
This cross section corresponds to cross section 130377 of the non-georeferenced CDC model which was the source of this model.
END DESCRIPTION:
XS GIS Cut Line= 3
2445633.120905257057454.420279642444989.106117167057689.21803838
2444867.026636937057790.33496213
#Sta/Elev= 30
    1006   465.4    1042   453.8    1061   452.9    1108     442    1148   441.1
    1157   440.4    1214   441.6    1278   454.6    1298     455    1362   453.8
    1394   444.6    1421   440.8    1434     436    1439   434.8    1440   433.8
    1461   429.8    1490   427.2    1503     431    1510   433.6    1514   441.3
    1549   446.3    1582     450    1621   450.8    1644   450.6    1679   452.3
    1679   452.6    1693   451.9    1700   456.6    1750     475    1850     480
#Mann= 4 ,-1,0
    1006     .03       0    1278     .05       0    1514     .09       0
    1582    .045       0
Bank Sta=1298,1679
XS Rating Curve= 0 ,0
Exp/Cntr=0.3,0.1

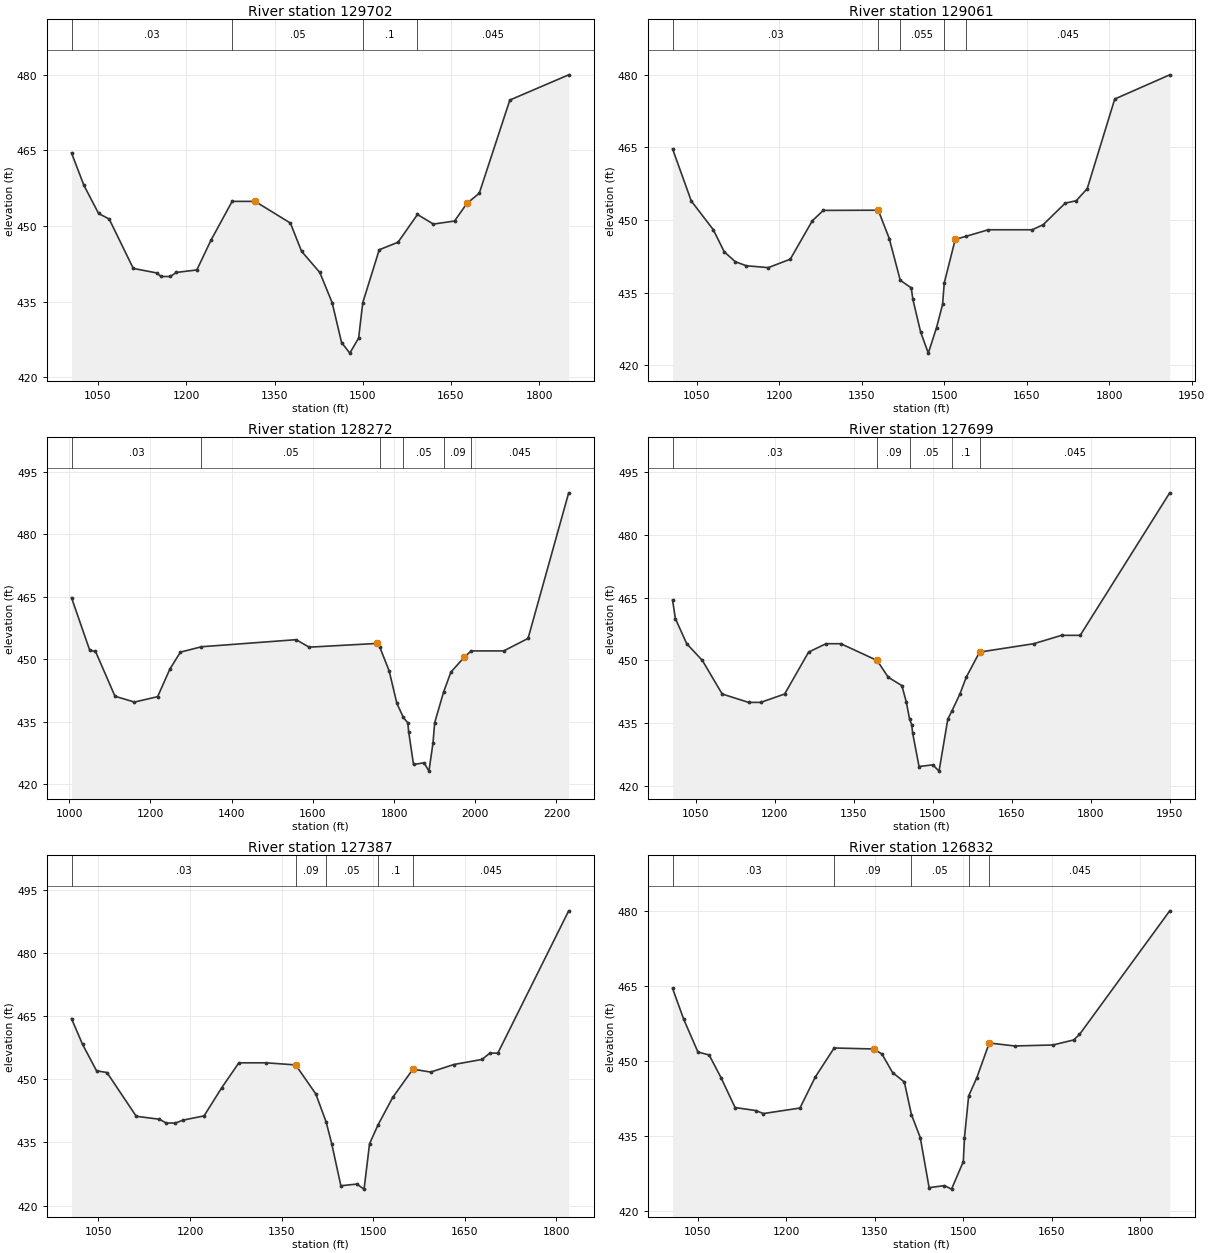
Type RM Length L Ch R = 1 ,129702  ,840,641,450
BEGIN DESCRIPTION:
This cross section corresponds to cross section 129689 of the non-georeferenced CDC model which was the source of this model.
END DESCRIPTION:
XS GIS Cut Line= 3
2445219.482624927056715.184881462444689.060129347057160.73910847
2444611.97891867 7057292.0649613
#Sta/Elev= 30
    1005   464.5    1026   458.1    1051   452.5    1069   451.4    1110   441.6
    1150   440.7    1157     440    1173     440    1183   440.8    1218   441.3
    1242   447.2    1278   454.9    1317   454.9    1377   450.6    1396     445
    1427   440.8    1448   434.8    1464   426.9    1478   424.8    1493   427.8
    1500   434.8    1528   445.3    1560   446.8    1593   452.3    1620   450.4
    1656     451    1677   454.5    1698   456.5    1750     475    1850     480
#Mann= 4 ,-1,0
    1005     .03       0    1278     .05       0    1500      .1       0
    1593    .045       0
Bank Sta=1317,1677
XS Rating Curve= 0 ,0
Exp/Cntr=0.3,0.1

Type RM Length L Ch R = 1 ,129061  ,400,789,800
BEGIN DESCRIPTION:
This cross section corresponds to cross section 129048 of the non-georeferenced CDC model which was the source of this model.
END DESCRIPTION:
XS GIS Cut Line= 3
2444391.83697051 7056338.82474182444256.431073347057007.48022863
2444161.65501618 7057207.9804838
#Sta/Elev= 30
    1006   464.7    1040  453.95    1080  448.02    1100  443.44    1120  441.41
    1140  440.57    1180  440.18    1220  441.92    1260  449.84    1280     452
    1380  452.04    1400  446.19    1420  437.57    1440     436    1443   433.6
    1457   426.9    1471  422.52    1486   427.8    1497   432.6    1500     437
    1520  446.02    1540  446.66    1580     448    1660     448    1680  449.06
    1720   453.5    1740     454    1760   456.5    1810     475    1910     480
#Mann= 5 ,-1,0
    1006     .03       0    1380      .1       0    1420    .055       0
    1500      .1       0    1540    .045       0
Bank Sta=1380,1520
XS Rating Curve= 0 ,0
Exp/Cntr=0.3,0.1

Type RM Length L Ch R = 1 ,128272  ,220,573,750
BEGIN DESCRIPTION:
This cross section corresponds to cross section 128259 of the non-georeferenced CDC model which was the source of this model.
END DESCRIPTION:
XS GIS Cut Line= 3
2444054.734626357056258.631988792443537.38789201 7057070.5280028
2443385.42690983 7057283.0767903
#Sta/Elev= 30
    1006   464.8    1051   452.1    1065   451.9    1113   441.1    1161   439.7
    1218     441    1248   447.6    1274   451.7    1326     453    1559   454.7
    1591   452.9    1759   453.8    1765   452.9    1788   447.2    1807   439.4
    1823     436    1834   434.7    1836   432.6    1848   424.7    1874   425.1
    1886   423.1    1896   429.9    1900   434.7    1922   442.1    1940   446.9
    1973   450.5    1990     452    2070     452    2130     455    2230     490
#Mann= 6 ,-1,0
    1006     .03       0    1326     .05       0    1765     .09       0
    1823     .05       0    1922     .09       0    1990    .045       0
Bank Sta=1759,1973
XS Rating Curve= 0 ,0
Exp/Cntr=0.3,0.1

Type RM Length L Ch R = 1 ,127699  ,250,312,350
BEGIN DESCRIPTION:
This cross section corresponds to cross section 127686 of the non-georeferenced CDC model which was the source of this model.
END DESCRIPTION:
XS GIS Cut Line= 3
2443932.347403917056168.207957042443528.493880937056421.38592838
2443135.312252587056674.01764096
#Sta/Elev= 30
    1006   464.4  1011.3     460  1032.9     454  1062.6     450  1100.2     442
  1150.4     440  1173.4     440  1218.8     442  1264.3     452  1297.3     454
  1325.5     454  1394.4     450  1415.5     446  1441.4     444    1450     440
    1456     436    1460   434.7    1462   432.6    1474   424.7    1500   425.1
    1512   423.6  1528.6     436  1536.6     438  1551.6     442  1563.6     446
  1588.9     452  1691.8     454  1744.5     456    1780     456    1950     490
#Mann= 5 ,-1,0
    1006     .03       0  1394.4     .09       0    1456     .05       0
  1536.6      .1       0  1588.9    .045       0
Bank Sta=1394.4,1588.9
XS Rating Curve= 0 ,0
Exp/Cntr=0.3,0.1

Type RM Length L Ch R = 1 ,127387  ,450,555,590
BEGIN DESCRIPTION:
This cross section corresponds to cross section 127374 of the non-georeferenced CDC model which was the source of this model.
END DESCRIPTION:
XS GIS Cut Line= 2
 2443829.11401467055991.458310542443060.813385847056260.36361264
#Sta/Elev= 30
    1006   464.4    1024   458.3    1047     452    1064   451.6    1112   441.2
    1150   440.5    1161   439.6    1176   439.6    1189   440.3    1223   441.3
    1252     448    1280   453.9    1325   453.9    1373   453.4    1406   446.5
    1423   439.8    1432   434.7    1447   424.7    1473   425.1    1485   423.9
    1494   434.7    1508   439.2    1532   445.7    1565   452.4    1594   451.7
    1632   453.5    1678   454.7    1691   456.2    1704   456.2    1820     490
#Mann= 5 ,-1,0
    1006     .03       0    1373     .09       0    1423     .05       0
    1508      .1       0    1565    .045       0
Bank Sta=1373,1565
XS Rating Curve= 0 ,0
Exp/Cntr=0.3,0.1

Type RM Length L Ch R = 1 ,126832  ,1,1,1
BEGIN DESCRIPTION:
This cross section corresponds to cross section 126819 of the non-georeferenced CDC model which was the source of this model.
END DESCRIPTION:
XS GIS Cut Line= 2
     2443695.892     7055604.893     2442853.075     7055622.452
#Sta/Elev= 30
    1007   464.5    1026   458.3    1050   451.8    1069   451.2    1089   446.7
    1113   440.7    1148   440.1    1161   439.5    1223   440.6    1249   446.8
    1281   452.6    1348   452.4    1362   451.4    1380   447.7    1400   445.8
    1412   439.3    1427   434.7    1442   424.7    1468   425.1    1480   424.4
    1500   429.9    1502   434.7    1509     443    1523   446.7    1544   453.6
    1587     453    1652   453.2    1687   454.2    1697   455.3    1850     480
#Mann= 5 ,-1,0
    1007     .03       0    1281     .09       0    1412     .05       0
    1509     .08       0    1544    .045       0
Bank Sta=1348,1544
XS Rating Curve= 0 ,0
Exp/Cntr=0.3,0.1