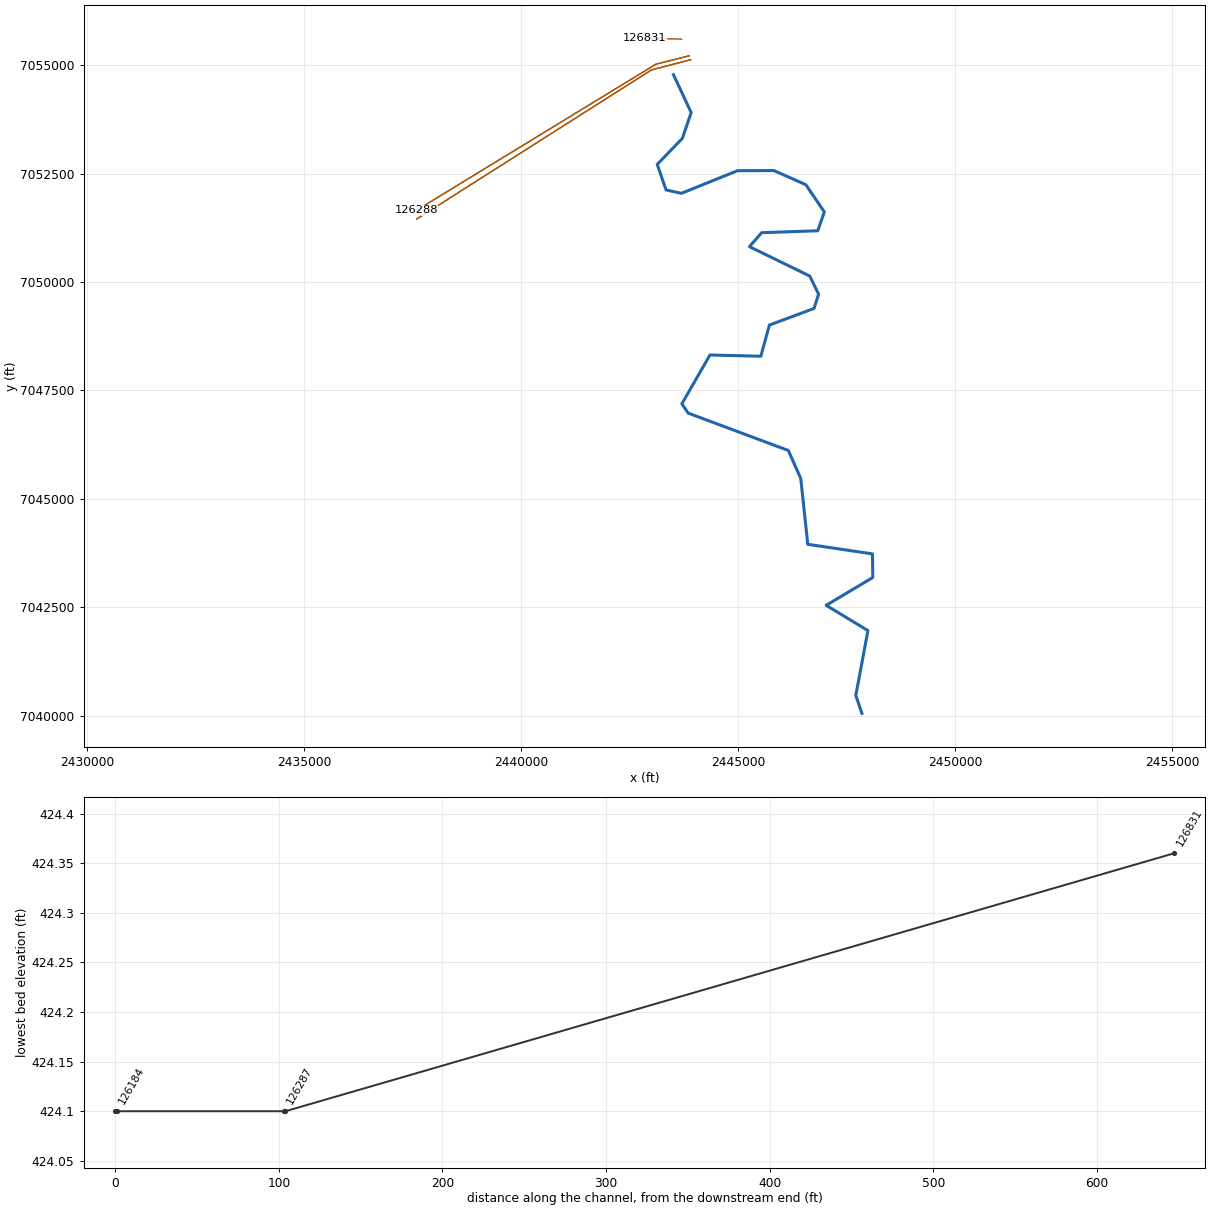
HEC-RAS study CDC_Consolidated_Model.prj: Upper Trinity CDC Consolidated Model

--- CDC_Consolidated_Model.g02 (geometry) --- (continued)

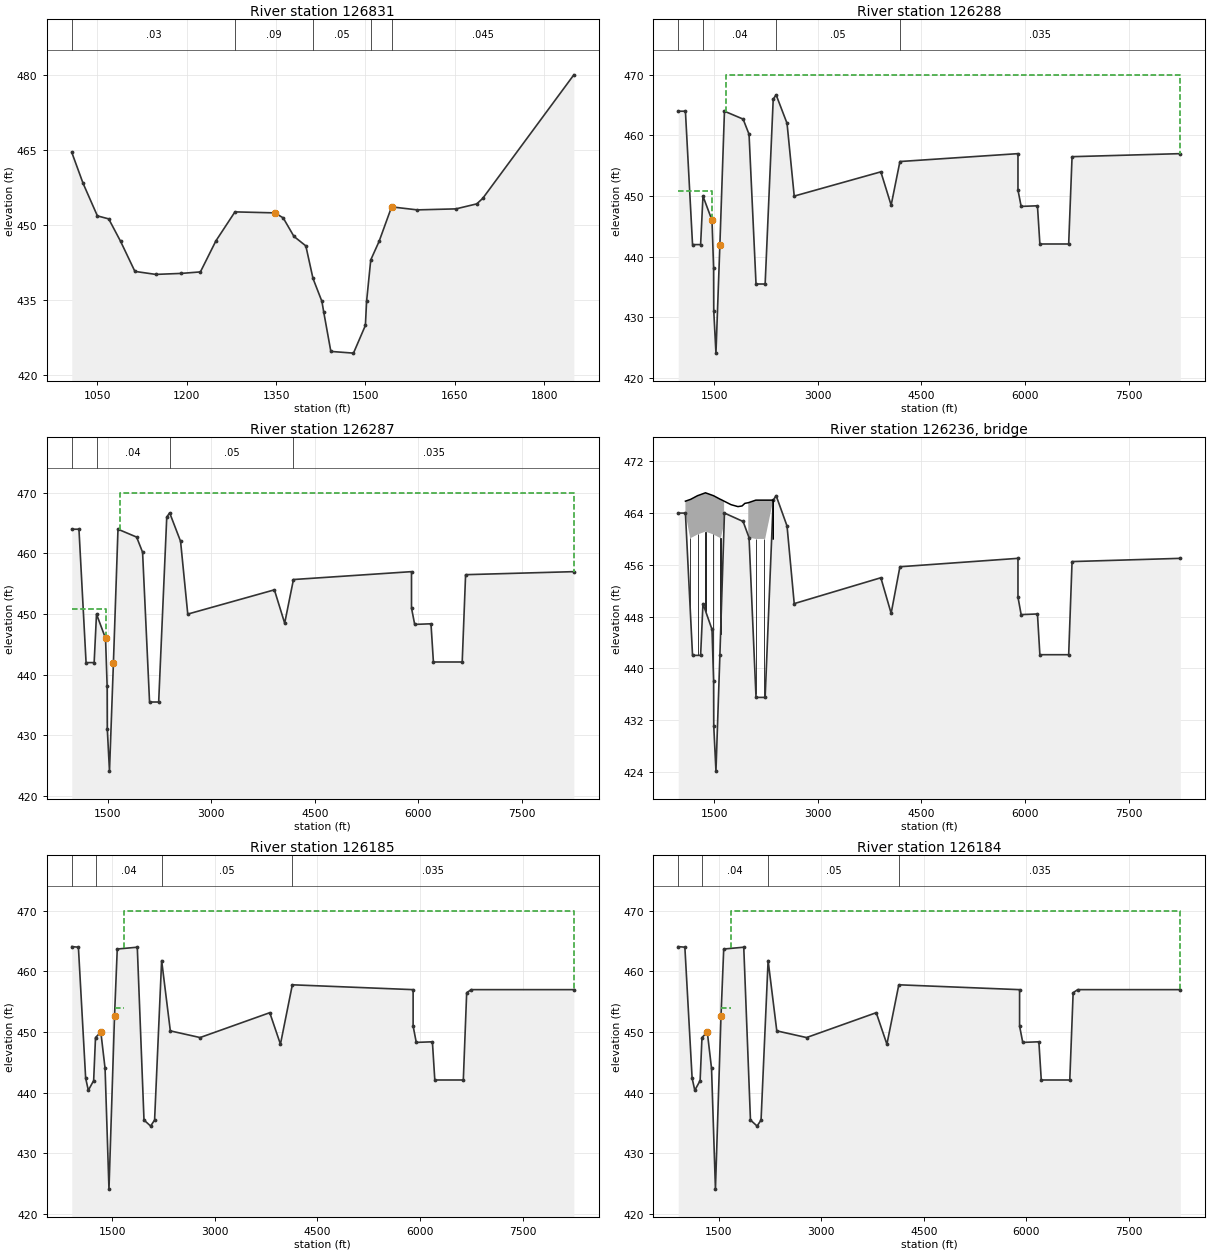
Type RM Length L Ch R = 1 ,126831  ,464,543,622
BEGIN DESCRIPTION:
This cross section corresponds to cross section 126818 of the non-georeferenced CDC model which was the source of this model.
END DESCRIPTION:
XS GIS Cut Line= 2
2443695.835737827055603.894781222442853.018853937055621.45347314
#Sta/Elev= 30
    1007   464.5    1026   458.3    1050   451.8    1069   451.2    1089   446.7
    1113   440.7    1148   440.1    1191   440.3    1223   440.6    1249   446.8
    1281   452.6    1348   452.4    1362   451.4    1380   447.7    1400   445.8
    1412   439.3    1427   434.7    1430   432.6    1442   424.7    1480  424.36
    1500   429.9    1502   434.7    1509     443    1523   446.7    1544   453.6
    1587     453    1652   453.2    1687   454.2    1697   455.3    1850     480
#Mann= 5 ,-1,0
    1007     .03       0    1281     .09       0    1412     .05       0
    1509     .08       0    1544    .045       0
Bank Sta=1348,1544
XS Rating Curve= 0 ,0
Exp/Cntr=0.3,0.1

Type RM Length L Ch R = 1 ,126288  ,1,1,1
BEGIN DESCRIPTION:
This cross section corresponds to cross section 126293 of the non-georeferenced CDC model which was the source of this model.
END DESCRIPTION:
XS GIS Cut Line= 4
2443872.004020667055219.654079882443102.852999937055025.20564988
2438857.507488017052432.10224029 2437577.41378997051650.20702732
#Sta/Elev= 30
     982     464    1086     464    1189     442    1306     442    1340     450
    1471     446    1494   438.1    1496   431.1    1528   424.1    1585     442
    1651     464    1921   462.7    2007   460.2    2108   435.5    2240   435.5
    2357     466    2399   466.7    2557     462    2661     450    3915     454
    4064   448.5    4191   455.7    5900     457    5900     451    5946   448.3
    6182   448.4    6217   442.1    6634   442.1    6683   456.5    8250     457
#Mann= 4 ,-1,0
     982     .03       0    1340     .04       0    2399     .05       0
    4191    .035       0
#XS Ineff= 3 ,-1
     982    1471   450.9    1585    1675     442    1675    8250     470
Permanent Ineff=
       F       F       F
Bank Sta=1471,1585
XS Rating Curve= 0 ,0
Exp/Cntr=0.5,0.3

Type RM Length L Ch R = 1 ,126287  ,102,102,102
BEGIN DESCRIPTION:
This cross section corresponds to cross section 126292 of the non-georeferenced CDC model which was the source of this model.
END DESCRIPTION:
XS GIS Cut Line= 4
2443872.324230027055218.918517052443101.958972847055024.08360489
2438858.160373847052430.888331962437578.205792177051648.76540757
#Sta/Elev= 30
     982     464    1086     464    1189     442    1306     442    1340     450
    1471     446    1494   438.1    1496   431.1    1528   424.1    1585     442
    1651     464    1921   462.7    2007   460.2    2108   435.5    2240   435.5
    2357     466    2399   466.7    2557     462    2661     450    3915     454
    4064   448.5    4191   455.7    5900     457    5900     451    5946   448.3
    6182   448.4    6217   442.1    6634   442.1    6683   456.5    8250     457
#Mann= 4 ,-1,0
     982     .03       0    1340     .04       0    2399     .05       0
    4191    .035       0
#XS Ineff= 3 ,-1
     982    1471   450.9    1585    1675     442    1675    8250     470
Permanent Ineff=
       F       F       F
Bank Sta=1471,1585
XS Rating Curve= 0 ,0
Exp/Cntr=0.5,0.3

Type RM Length L Ch R = 3 ,126236  ,,,
BEGIN DESCRIPTION:
Hebron Parkway
END DESCRIPTION:
Node Name=Hebron Parkway
Bridge Culvert--1,0,-1,-1, 0
Deck Dist Width WeirC Skew NumUp NumDn MinLoCord MaxHiCord MaxSubmerge Is_Ogee
1,100,2.6,0, 25, 25, , , 0.95, 0, ,,,
    1086    1155  1157.5    1265  1267.5    1375  1377.5    1486  1488.5    1596
  1598.5    1646    1646    1746    1846    1906    1946    1996    1996    2105
  2107.5    2215  2217.5    2357    2357
  465.84   466.1   466.1  466.71  466.71  467.13  467.13  466.71  466.71   466.1
   466.1  465.84  465.84   465.3     465   465.1   465.5   465.6   465.6     466
     466     466     466     466     460
  459.84   460.1   460.1  460.71  460.71  461.13  461.13  460.71  460.71   460.1
   460.1  459.84  465.84   465.3     465   465.1   465.5   465.6     460     460
     460     460     460     460     460
    1000    1069  1071.5    1179  1181.5    1289  1291.5    1400  1402.5    1510
  1512.5    1560    1560    1660    1760    1820    1860    1880    1880    2019
  2021.5    2129  2131.5    2213    2213
  465.84   466.1   466.1  466.71  466.71  467.13  467.13  466.71  466.71   466.1
   466.1  465.84  465.84   465.3     465   465.1   465.5   465.6   465.6     466
     466     466     466     466     460
  459.84   460.1   460.1  460.71  460.71  461.13  461.13  460.71  460.71   460.1
   460.1  459.84  465.84   465.3     465   465.1   465.5   465.6     460     460
     460     460     460     460     460
Pier Skew, UpSta & Num, DnSta & Num=  ,1156, 2 ,1081, 2 , 0 , 0 , 0 ,,
     2.5     2.5
       0   460.5
     2.5     2.5
       0   460.5
Pier Skew, UpSta & Num, DnSta & Num=  ,1266, 2 ,1191, 2 , 0 , 0 , 0 ,,
     2.5     2.5
       0     461
     2.5     2.5
       0     461
Pier Skew, UpSta & Num, DnSta & Num=  ,1376, 2 ,1301, 2 , 0 , 0 , 0 ,,
     2.5     2.5
       0   461.5
     2.5     2.5
       0   461.5
Pier Skew, UpSta & Num, DnSta & Num=  ,1487, 2 ,1412, 2 , 0 , 0 , 0 ,,
     2.5     2.5
       0     461
     2.5     2.5
       0     461
Pier Skew, UpSta & Num, DnSta & Num=  ,1595, 2 ,1520, 2 , 0 , 0 , 0 ,,
     2.5     2.5
       0   460.5
     2.5     2.5
       0   460.5
Pier Skew, UpSta & Num, DnSta & Num=  ,2106, 2 ,1974, 2 , 0 , 0 , 0 ,,
     2.5     2.5
       0     461
     2.5     2.5
       0     461
Pier Skew, UpSta & Num, DnSta & Num=  ,2219, 2 ,2087, 2 , 0 , 0 , 0 ,,
     2.5     2.5
       0     461
     2.5     2.5
       0     461
BR Coef= 1 , 0 , 0 ,1.05, 0 ,,,0.8,-1,0.5,1,
WSPro=,,,, 1 ,,,, 0 ,,,, 0 ,,,,-1 ,-1 ,-1 , 0 , 0 , 0 , 0 , 0
BC Design=,, 0 ,, 0 ,,,,,,
BC HTab HWMax=465.84
BC Use User HTab Curves=0
BC User HTab FreeFlow(D)= 0

Type RM Length L Ch R = 1 ,126185  ,1,1,1
BEGIN DESCRIPTION:
This cross section corresponds to cross section 126172 of the non-georeferenced CDC model which was the source of this model.
END DESCRIPTION:
XS GIS Cut Line= 4
     2443902.915     7055128.836     2442996.024     7054890.963
     2438858.338     7052259.767 2437592.58577287051454.86247191
#Sta/Elev= 30
     909   464.1    1006     464    1112   442.4    1151   440.4    1229     442
    1256   449.1    1334     450    1396     444    1453   424.1    1534   452.6
    1574   463.7    1867     464    1965   435.5    2062   434.5    2120   435.5
    2223   461.8    2350   450.2    2785   449.1    3804   453.2    3960     448
    4134   457.8    5900     457    5900     451    5946   448.3    6182   448.4
    6217   442.1    6634   442.1    6683   456.5    6750     457    8250     457
#Mann= 4 ,-1,0
     909     .03       0    1256     .04       0    2223     .05       0
    4134    .035       0
#XS Ineff= 3 ,-1
     909    1334     450    1539    1676     454    1676    8250     470
Permanent Ineff=
       F       F       F
Bank Sta=1334,1534
XS Rating Curve= 0 ,0
Exp/Cntr=0.5,0.3

Type RM Length L Ch R = 1 ,126184  ,0,0,0
BEGIN DESCRIPTION:
This cross section corresponds to cross section 126171 of the non-georeferenced CDC model which was the source of this model.
END DESCRIPTION:
XS GIS Cut Line= 4
2443903.383879187055127.946258052442996.492976437054890.07403038
2438858.806697997052258.877193052437593.054562257051453.97252114
#Sta/Elev= 30
     909   464.1    1006     464    1112   442.4    1151   440.4    1229     442
    1256   449.1    1334     450    1396     444    1453   424.1    1534   452.6
    1574   463.7    1867     464    1965   435.5    2062   434.5    2120   435.5
    2223   461.8    2350   450.2    2785   449.1    3804   453.2    3960     448
    4134   457.8    5900     457    5900     451    5946   448.3    6182   448.4
    6217   442.1    6634   442.1    6683   456.5    6750     457    8250     457
#Mann= 4 ,-1,0
     909     .03       0    1256     .04       0    2223     .05       0
    4134    .035       0
#XS Ineff= 3 ,-1
     909    1334     450    1539    1676     454    1676    8250     470
Permanent Ineff=
       F       F       F
Bank Sta=1334,1534
XS Rating Curve= 0 ,0
Exp/Cntr=0.5,0.3

River Reach=Elm Fork        ,ef3
Reach XY= 30
      2443507.86      7054781.77      2443915.37      7053909.89
      2443712.82      7053314.17      2443133.27      7052713.75
      2443336.18      7052124.19       2443690.1      7052046.36
      2444983.67      7052568.29      2445822.43      7052571.42
      2446558.92      7052244.63      2446983.77      7051618.15
      2446833.53      7051182.86      2445539.52      7051137.95
      2445258.66      7050815.85      2446648.28      7050138.14
      2446851.94      7049721.91      2446747.18      7049390.79
      2445718.34      7049007.95      2445520.89      7048288.45
      2444349.09      7048317.26      2443701.18      7047191.54
      2443845.71      7046976.55      2446154.44      7046114.48
      2446441.34      7045466.69      2446602.22      7043949.82
      2448092.76      7043729.22      2448101.07      7043184.86
      2447026.42      7042543.32      2447988.56      7041959.85
      2447709.25      7040463.12      2447850.52      7040050.17