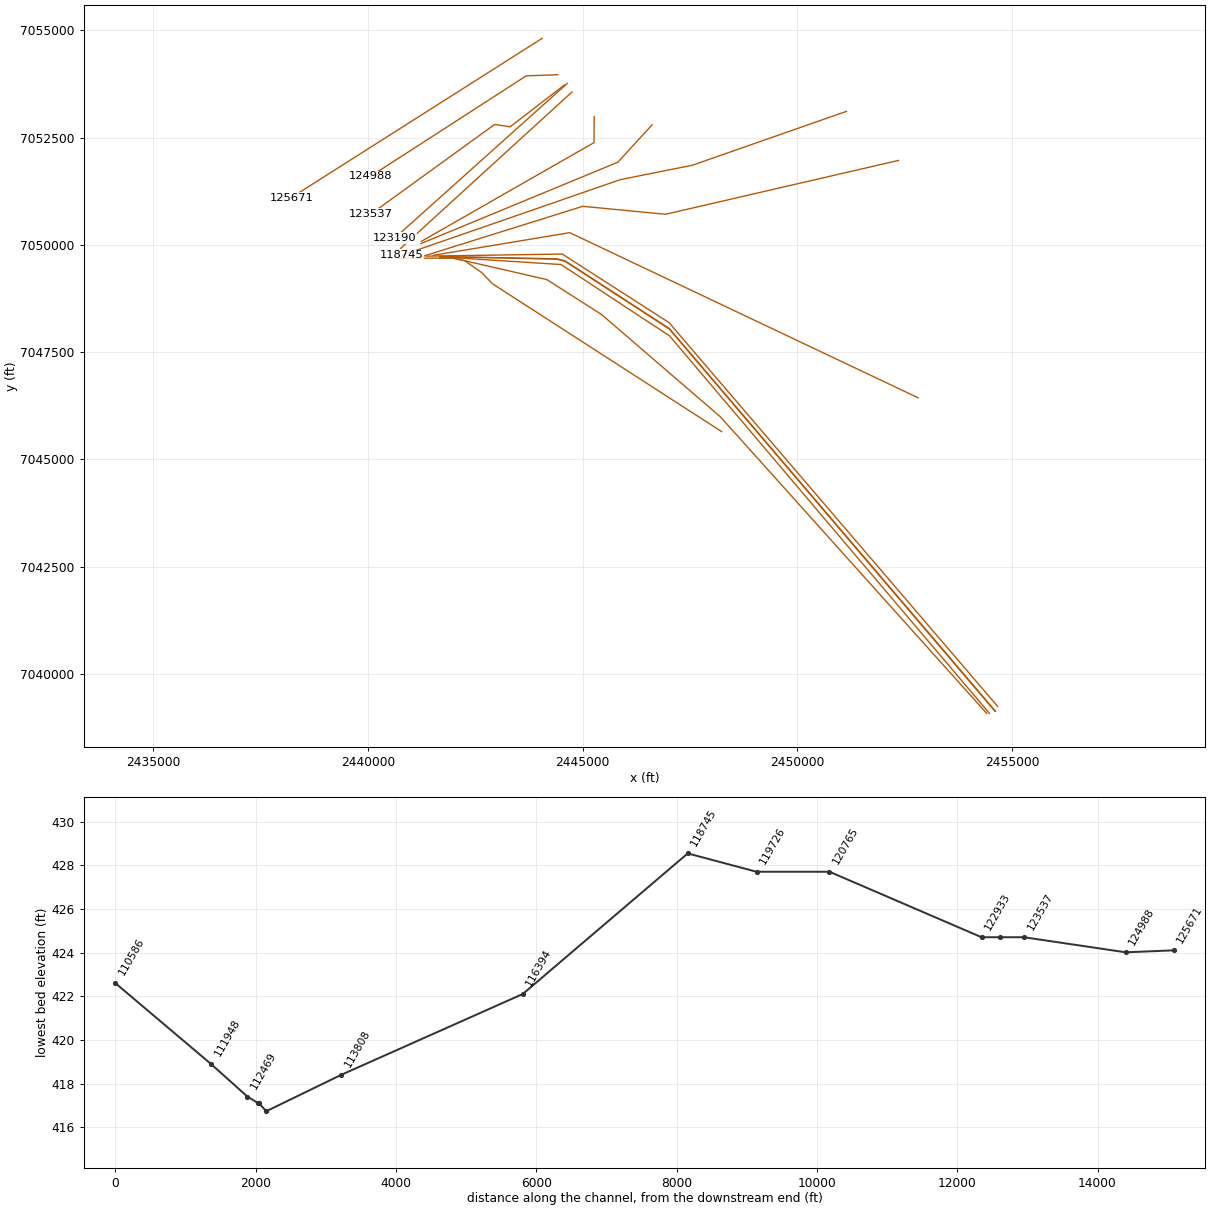
HEC-RAS study CDC_Consolidated_Model.prj: Upper Trinity CDC Consolidated Model

--- CDC_Consolidated_Model.g02 (geometry) --- (continued)

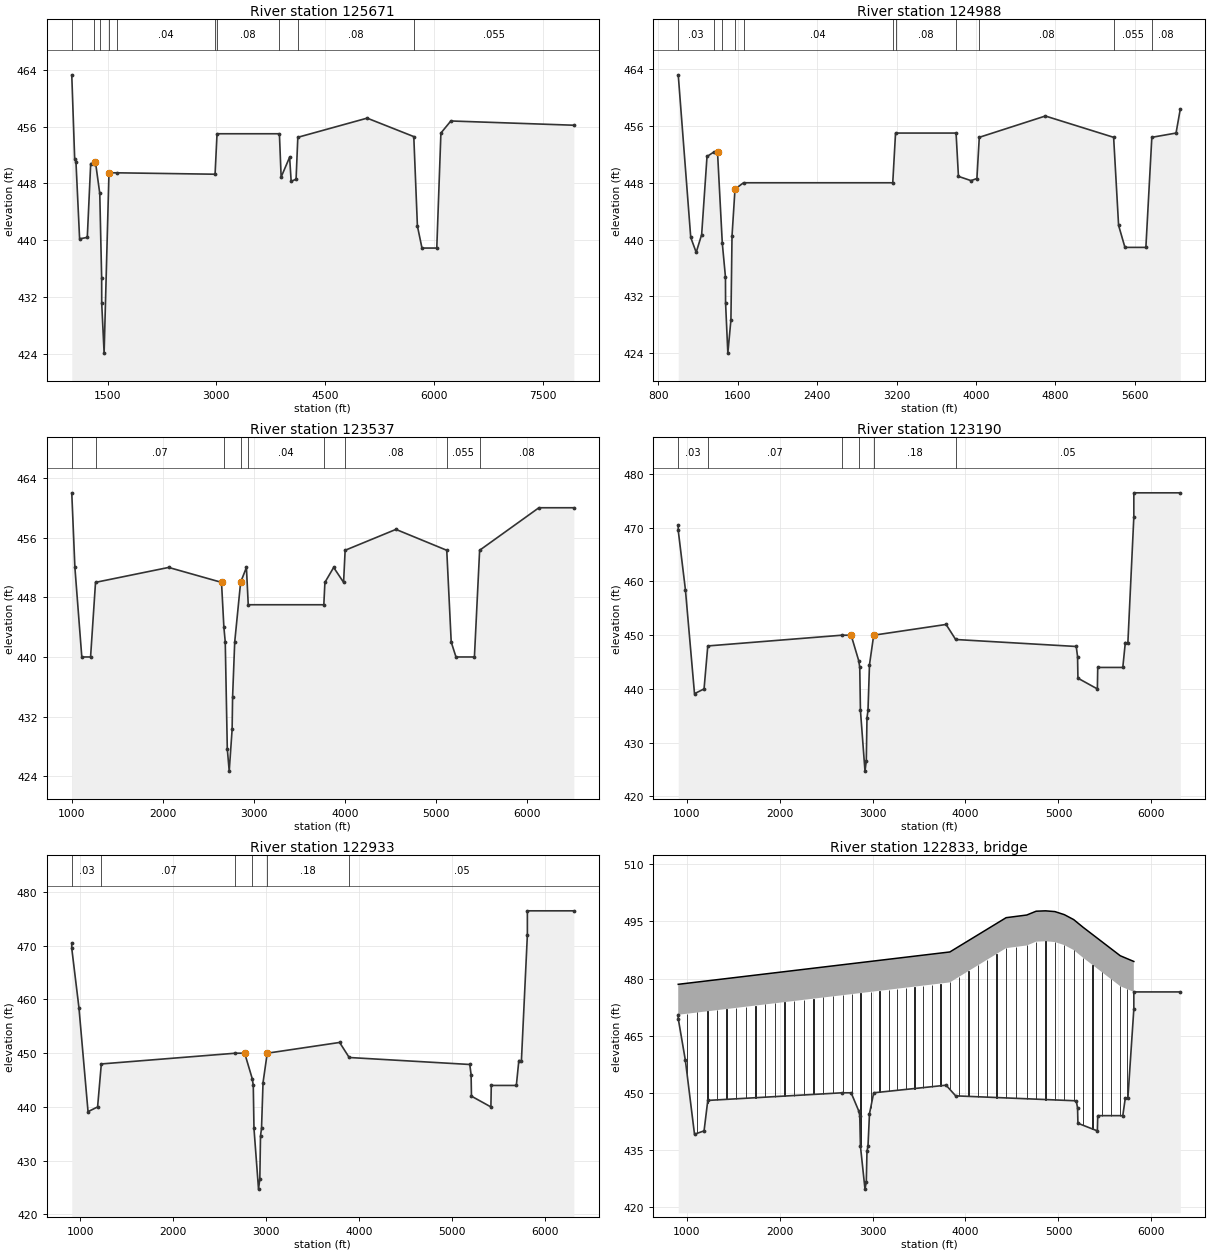
Type RM Length L Ch R = 1 ,125671  ,850,683,550
BEGIN DESCRIPTION:
This cross section corresponds to cross section 125658 of the non-georeferenced CDC model which was the source of this model.
Proposed lake, 2 fills
---------------------------------------------------------------------
CDC LEW121406-1 Waste Management Systems Landfill
Cross-section 125658 - 144474.  Includes split flow reach efs2.
This CDC incorporates CDC LEW102202-02
---------------------------------------------------------------------
END DESCRIPTION:
XS GIS Cut Line= 3
2444055.669007667054814.836976132439478.530524167051906.44712363
2438212.495522327051101.98744527
#Sta/Elev= 30
    1007   463.3    1047   451.5    1065     451    1115   440.2    1221   440.4
    1268   450.8    1311   450.8    1334     451    1393   446.6    1419   434.7
    1420   431.1    1453   424.1    1520   449.5    1624   449.5    2983   449.3
    3010     455    3870     455    3894   448.9    4011   451.7    4032   448.3
    4100   448.6    4124   454.5    5080   457.2    5723   454.6    5773     442
    5836   438.9    6040   438.9    6097   455.1    6234   456.8    7930   456.2
#Mann= 10 ,-1,0
    1007     .03       0    1311     .07       0    1393     .05       0
    1520    .055       0    1624     .04       0    2983    .055       0
    3010     .08       0    3870    .055       0    4124     .08       0
    5723    .055       0
Bank Sta=1334,1520
XS Rating Curve= 0 ,0
Exp/Cntr=0.3,0.1

Type RM Length L Ch R = 1 ,124988  ,500,1451,570
BEGIN DESCRIPTION:
This cross section corresponds to cross section 124975 of the non-georeferenced CDC model which was the source of this model.
Proposed:  1 lake, 1 transition from fill to lake, 1 fill
END DESCRIPTION:
XS GIS Cut Line= 3
2444422.009154267053966.009933642443685.355115747053940.60808155
2440054.028060857051595.18724747
#Sta/Elev= 30
    1000   463.2    1126   440.3    1181   438.2    1236   440.7    1290   451.7
    1356   452.3    1396   452.3    1444   439.5    1476   434.7    1477   431.1
    1500  424.01    1531   428.7    1542   440.5    1572   447.1    1658     448
    3162     448    3190     455    3800     455    3824   448.9    3951   448.3
    4010   448.6    4034   454.4    4700   457.4    5388   454.4    5438     442
    5502   438.9    5713   438.9    5773   454.4    6017     455    6060   458.4
#Mann= 11 ,-1,0
    1000     .03       0    1356     .07       0    1444     .05       0
    1572    .055       0    1658     .04       0    3162    .055       0
    3190     .08       0    3800    .055       0    4034     .08       0
    5388    .055       0    5773     .08       0
#XS Ineff= 2 , 0
       0    1396     451    1572       0   447.1
Permanent Ineff=
       F       F
Bank Sta=1396,1572
XS Rating Curve= 0 ,0
Exp/Cntr=0.3,0.1

Type RM Length L Ch R = 1 ,123537  ,36,347,534
BEGIN DESCRIPTION:
This cross section corresponds to cross section 123524 of the non-georeferenced CDC model which was the source of this model.
Proposed 1 lake, 2 fills
END DESCRIPTION:
XS GIS Cut Line= 4
   2444573.66683   7053727.27222 2443308.5848719 7052752.3411011
 2442949.3510104  7052807.722224 2440071.9335368 7050722.6827589
#Sta/Elev= 30
    1000     462  1034.3     452 1110.15     440 1206.55     440 1260.84     450
 2064.23     452 2644.49     450 2670.44     444  2685.5     442    2708   427.7
    2729   424.7    2761   430.3    2766   434.6 2789.39     442 2854.18     450
    2918     452    2938     447    3768     447    3780     450 3875.98     452
    3985     450    4002   454.3    4560   457.1    5118   454.3    5167     442
  5219.3     440 5421.82     440    5479   454.3    6130     460  6513.7     460
#Mann= 9 ,-1,0
    1000     .03       0 1260.84     .07       0 2670.44    .055       0
 2854.18     .07       0    2938     .04       0    3768     .05       0
    4002     .08       0    5118    .055       0    5479     .08       0
Bank Sta=2644.49,2854.18
XS Rating Curve= 0 ,0
Exp/Cntr=0.03,0.01

Type RM Length L Ch R = 1 ,123190  ,257,257,257
BEGIN DESCRIPTION:
This cross section corresponds to cross section 122944 of the non-georeferenced CDC model which was the source of this model.
Upstream bounding cross section for S.H. 121 Lewisville Bypass Bridge.
END DESCRIPTION:
XS GIS Cut Line= 3
     2444641.212     7053764.751     2440996.062     7050494.452
2440623.890644467050160.55308998
#Sta/Elev= 30
     910   470.5     910   469.5     987   458.5    1085  439.12 1187.82     440
 1227.84     448    2670     450    2770     450 2851.71  445.24 2862.58     444
    2870     436    2919   424.7    2933   426.6 2940.33   434.6 2951.24     436
 2967.41  444.52 3012.64     450 3791.38     452  3894.3   449.2 5191.51   447.9
 5205.77     446 5209.59     442 5418.76     440 5422.75     444 5692.37     444
 5719.38  448.64 5746.79  448.52    5811     472    5811   476.5    6311   476.5
#Mann= 6 ,-1,0
     910     .03       0 1227.84     .07       0    2670     .06       0
 2851.71    .055       0 3012.64     .18       0  3894.3     .05       0
Bank Sta=2770,3012.64
XS Rating Curve= 0 ,0
Exp/Cntr=0.03,0.01

Type RM Length L Ch R = 1 ,122933  ,904,2168,596
BEGIN DESCRIPTION:
This cross section corresponds to cross section 122934 of the non-georeferenced CDC model which was the source of this model.
Downstream bounding cross section for S.H. 121 Lewisville Bypass Bridge
END DESCRIPTION:
XS GIS Cut Line= 3
     2444750.112     7053563.612     2441131.486     7050257.816
 2440762.33638387049920.57934591
#Sta/Elev= 30
     910   470.5     910   469.5     987   458.5    1085  439.12 1187.82     440
 1227.84     448    2670     450    2770     450 2851.71  445.24 2862.58     444
    2870     436    2919   424.7    2933   426.6 2940.33   434.6 2951.24     436
 2967.41  444.52 3012.64     450 3791.38     452  3894.3   449.2 5191.51   447.9
 5205.77     446 5209.59     442 5418.76     440 5422.75     444 5692.37     444
 5719.38  448.64 5746.79  448.52    5811     472    5811   476.5    6311   476.5
#Mann= 6 ,-1,0
     910     .03       0 1227.84     .07       0    2670     .06       0
 2851.71    .055       0 3012.64     .18       0  3894.3     .05       0
Bank Sta=2770,3012.64
XS Rating Curve= 0 ,0
Exp/Cntr=0.03,0.01

Type RM Length L Ch R = 3 ,122833  ,,,
BEGIN DESCRIPTION:
SH 121 Lewisville Bypass
Note:  Bridge modeled from plans dated Oct. 1995 and supplied by TXDOT Aug. 1998.
END DESCRIPTION:
Node Name=SH 121
Bridge Culvert--1,0,-1,-1, 0
Deck Dist Width WeirC Skew NumUp NumDn MinLoCord MaxHiCord MaxSubmerge Is_Ogee
5,190,2.6,0, 12, 12, , , 0.95, 0, 0,0,,
     910    3832    4437    4659    4760    4861    4962    5063    5164    5264
    5665    5811
   478.5     487     496   496.7   497.7   497.8   497.6   496.8   495.5   493.5
     486   484.5
   470.5     479     488   488.7   489.7   489.8   489.6   488.8   487.5   485.5
     478   476.5
     910    3832    4437    4659    4760    4861    4962    5063    5164    5264
    5665    5811
   478.5     487     496   496.7   497.7   497.8   497.6   496.8   495.5   493.5
     486   484.5
   470.5     479     488   488.7   489.7   489.8   489.6   488.8   487.5   485.5
     478   476.5
Pier Skew, UpSta & Num, DnSta & Num=  ,1005, 2 ,1005, 2 , 0 , 0 , 0 ,,
       3       3
     400     475
       3       3
     400     475
Pier Skew, UpSta & Num, DnSta & Num=  ,1115, 2 ,1115, 2 , 0 , 0 , 0 ,,
       3       3
     400     475
       3       3
     400     475
Pier Skew, UpSta & Num, DnSta & Num=  ,1225, 2 ,1225, 2 , 0 , 0 , 0 ,,
       3       3
     400     475
       3       3
     400     475
Pier Skew, UpSta & Num, DnSta & Num=  ,1325, 2 ,1325, 2 , 0 , 0 , 0 ,,
       3       3
     400     475
       3       3
     400     475
Pier Skew, UpSta & Num, DnSta & Num=  ,1430, 2 ,1430, 2 , 0 , 0 , 0 ,,
       3       3
     400     475
       3       3
     400     475
Pier Skew, UpSta & Num, DnSta & Num=  ,1534, 2 ,1534, 2 , 0 , 0 , 0 ,,
       3       3
     400     475
       3       3
     400     475
Pier Skew, UpSta & Num, DnSta & Num=  ,1638, 2 ,1638, 2 , 0 , 0 , 0 ,,
       3       3
     400     480
       3       3
     400     480
Pier Skew, UpSta & Num, DnSta & Num=  ,1742, 2 ,1742, 2 , 0 , 0 , 0 ,,
       3       3
     400     480
       3       3
     400     480
Pier Skew, UpSta & Num, DnSta & Num=  ,1846, 2 ,1846, 2 , 0 , 0 , 0 ,,
       3       3
     400     480
       3       3
     400     480
Pier Skew, UpSta & Num, DnSta & Num=  ,1950, 2 ,1950, 2 , 0 , 0 , 0 ,,
       3       3
     400     480
       3       3
     400     480
Pier Skew, UpSta & Num, DnSta & Num=  ,2054, 2 ,2054, 2 , 0 , 0 , 0 ,,
       3       3
     400     480
       3       3
     400     480
Pier Skew, UpSta & Num, DnSta & Num=  ,2158, 2 ,2158, 2 , 0 , 0 , 0 ,,
       3       3
     400     480
       3       3
     400     480
Pier Skew, UpSta & Num, DnSta & Num=  ,2262, 2 ,2262, 2 , 0 , 0 , 0 ,,
       3       3
     400     480
       3       3
     400     480
Pier Skew, UpSta & Num, DnSta & Num=  ,2366, 2 ,2366, 2 , 0 , 0 , 0 ,,
       3       3
     400     480
       3       3
     400     480
Pier Skew, UpSta & Num, DnSta & Num=  ,2470, 2 ,2470, 2 , 0 , 0 , 0 ,,
       3       3
     400     480
       3       3
     400     480
Pier Skew, UpSta & Num, DnSta & Num=  ,2574, 2 ,2574, 2 , 0 , 0 , 0 ,,
       3       3
     400     480
       3       3
     400     480
Pier Skew, UpSta & Num, DnSta & Num=  ,2684, 2 ,2684, 2 , 0 , 0 , 0 ,,
       3       3
     400     480
       3       3
     400     480
Pier Skew, UpSta & Num, DnSta & Num=  ,2777, 2 ,2777, 2 , 0 , 0 , 0 ,,
       3       3
     400     480
       3       3
     400     480
Pier Skew, UpSta & Num, DnSta & Num=  ,2870, 2 ,2870, 2 , 0 , 0 , 0 ,,
       3       3
     400     480
       3       3
     400     480
Pier Skew, UpSta & Num, DnSta & Num=  ,2980, 2 ,2980, 2 , 0 , 0 , 0 ,,
       3       3
     400     480
       3       3
     400     480
Pier Skew, UpSta & Num, DnSta & Num=  ,3076, 2 ,3076, 2 , 0 , 0 , 0 ,,
       3       3
     400     480
       3       3
     400     480
Pier Skew, UpSta & Num, DnSta & Num=  ,3176, 2 ,3176, 2 , 0 , 0 , 0 ,,
       3       3
     400     480
       3       3
     400     480
Pier Skew, UpSta & Num, DnSta & Num=  ,3265, 2 ,3265, 2 , 0 , 0 , 0 ,,
       3       3
     400     480
       3       3
     400     480
Pier Skew, UpSta & Num, DnSta & Num=  ,3359, 2 ,3359, 2 , 0 , 0 , 0 ,,
       3       3
     400     480
       3       3
     400     480
Pier Skew, UpSta & Num, DnSta & Num=  ,3452, 2 ,3452, 2 , 0 , 0 , 0 ,,
       3       3
     400     480
       3       3
     400     480
Pier Skew, UpSta & Num, DnSta & Num=  ,3546, 2 ,3546, 2 , 0 , 0 , 0 ,,
       3       3
     400     480
       3       3
     400     480
Pier Skew, UpSta & Num, DnSta & Num=  ,3639, 2 ,3639, 2 , 0 , 0 , 0 ,,
       3       3
     400     480
       3       3
     400     480
Pier Skew, UpSta & Num, DnSta & Num=  ,3732, 2 ,3732, 2 , 0 , 0 , 0 ,,
       3       3
     400     480
       3       3
     400     480
Pier Skew, UpSta & Num, DnSta & Num=  ,3832, 2 ,3832, 2 , 0 , 0 , 0 ,,
       3       3
     400     480
       3       3
     400     480
Pier Skew, UpSta & Num, DnSta & Num=  ,3932, 2 ,3932, 2 , 0 , 0 , 0 ,,
       3       3
     400     485
       3       3
     400     485
Pier Skew, UpSta & Num, DnSta & Num=  ,4033, 2 ,4033, 2 , 0 , 0 , 0 ,,
       3       3
     400     485
       3       3
     400     485
Pier Skew, UpSta & Num, DnSta & Num=  ,4133, 2 ,4133, 2 , 0 , 0 , 0 ,,
       3       3
     400     485
       3       3
     400     485
Pier Skew, UpSta & Num, DnSta & Num=  ,4233, 2 ,4233, 2 , 0 , 0 , 0 ,,
       3       3
     400     490
       3       3
     400     490
Pier Skew, UpSta & Num, DnSta & Num=  ,4334, 2 ,4334, 2 , 0 , 0 , 0 ,,
       3       3
     400     490
       3       3
     400     490
Pier Skew, UpSta & Num, DnSta & Num=  ,4437, 2 ,4437, 2 , 0 , 0 , 0 ,,
       3       3
     400     490
       3       3
     400     490
Pier Skew, UpSta & Num, DnSta & Num=  ,4547, 2 ,4547, 2 , 0 , 0 , 0 ,,
       3       3
     400     490
       3       3
     400     490
Pier Skew, UpSta & Num, DnSta & Num=  ,4659, 2 ,4659, 2 , 0 , 0 , 0 ,,
       3       3
     400     490
       3       3
     400     490
Pier Skew, UpSta & Num, DnSta & Num=  ,4760, 2 ,4760, 2 , 0 , 0 , 0 ,,
       3       3
     400     490
       3       3
     400     490
Pier Skew, UpSta & Num, DnSta & Num=  ,4861, 2 ,4861, 2 , 0 , 0 , 0 ,,
       3       3
     400     490
       3       3
     400     490
Pier Skew, UpSta & Num, DnSta & Num=  ,4962, 2 ,4962, 2 , 0 , 0 , 0 ,,
       3       3
     400     490
       3       3
     400     490
Pier Skew, UpSta & Num, DnSta & Num=  ,5063, 2 ,5063, 2 , 0 , 0 , 0 ,,
       3       3
     400     490
       3       3
     400     490
Pier Skew, UpSta & Num, DnSta & Num=  ,5164, 2 ,5164, 2 , 0 , 0 , 0 ,,
       3       3
     400     490
       3       3
     400     490
Pier Skew, UpSta & Num, DnSta & Num=  ,5265, 2 ,5265, 2 , 0 , 0 , 0 ,,
       3       3
     400     490
       3       3
     400     490
Pier Skew, UpSta & Num, DnSta & Num=  ,5366, 2 ,5366, 2 , 0 , 0 , 0 ,,
       3       3
     400     490
       3       3
     400     490
Pier Skew, UpSta & Num, DnSta & Num=  ,5467, 2 ,5467, 2 , 0 , 0 , 0 ,,
       3       3
     400     488
       3       3
     400     488
Pier Skew, UpSta & Num, DnSta & Num=  ,5568, 2 ,5568, 2 , 0 , 0 , 0 ,,
       3       3
     400     485
       3       3
     400     485
Pier Skew, UpSta & Num, DnSta & Num=  ,5665, 2 ,5665, 2 , 0 , 0 , 0 ,,
       3       3
     400     485
       3       3
     400     485
Pier Skew, UpSta & Num, DnSta & Num=  ,5736, 2 ,5736, 2 , 0 , 0 , 0 ,,
       3       3
     400     484
       3       3
     400     484
BR Coef=-1 , 0 , 0 ,, 0 ,,,0.8,-1,,0,
WSPro=,,,, 1 ,,,, 0 ,,,, 0 ,,,,-1 ,-1 ,-1 , 0 , 0 , 0 , 0 , 0
BC Design=,, 0 ,, 0 ,,,,,,
BC HTab HWMax=476.5
BC Use User HTab Curves=0
BC User HTab FreeFlow(D)= 0

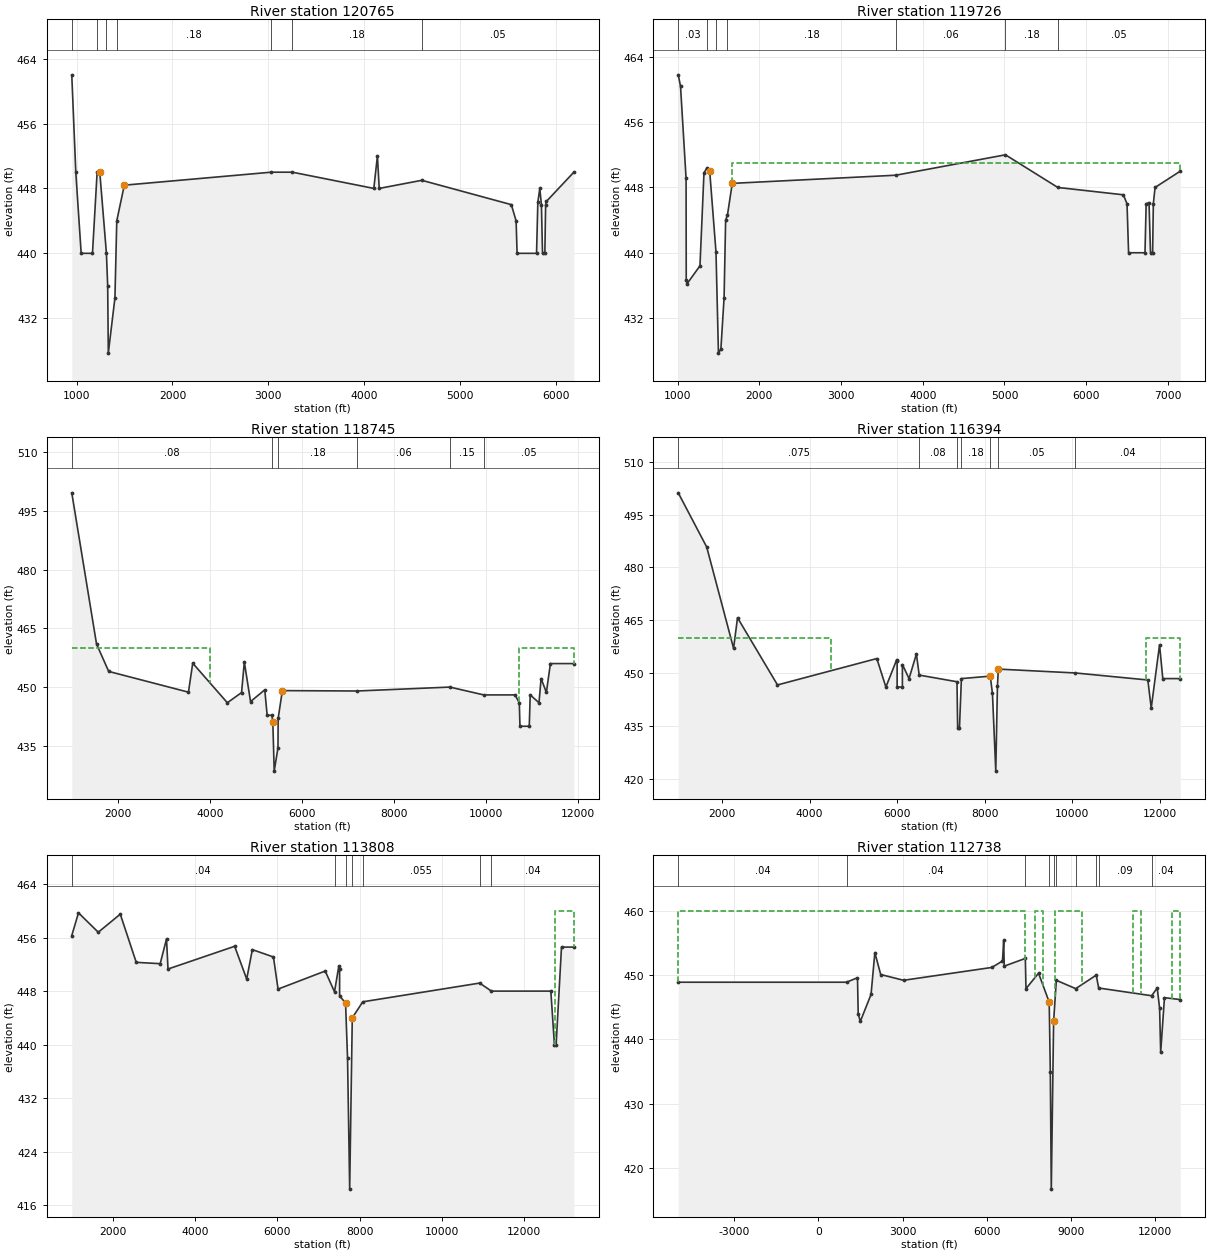
Type RM Length L Ch R = 1 ,120765  ,1201,1039,400
BEGIN DESCRIPTION:
This cross section corresponds to cross section 120752 of the non-georeferenced CDC model which was the source of this model.
Proposed: 1 lake
END DESCRIPTION:
XS GIS Cut Line= 3
2445267.590468357052991.55617388 2445262.22893057052383.13809939
2441246.677906517050084.84774847
#Sta/Elev= 30
     950     462     992     450    1048     440 1165.82     440 1214.47     450
 1241.98     450 1311.33     440 1324.46     436    1331   427.7    1400   434.5
 1419.24     444 1497.77   448.4    3030     450    3250     450 4099.42     448
  4137.1     452 4155.74     448    4600     449 5533.18     446 5583.16     444
 5593.37     440 5796.28     440 5809.64  446.27 5830.12     448 5847.11     446
 5858.49     440 5882.89     440 5891.04     446 5899.17   446.4 6185.19     450
#Mann= 7 ,-1,0
     950     .03       0 1214.47     .11       0 1311.33    .055       0
 1419.24     .18       0    3030     .06       0    3250     .18       0
    4600     .05       0
Bank Sta=1241.98,1497.77
XS Rating Curve= 0 ,0
Exp/Cntr=0.03,0.01

Type RM Length L Ch R = 1 ,119726  ,1349,981,300
BEGIN DESCRIPTION:
This cross section corresponds to cross section 119714 of the non-georeferenced CDC model which was the source of this model.
---------------------------------------------------------------------
CDC LEW042104-02 Trinity Place
Cross-section 119714 - 125658
Project located in ROB.
---------------------------------------------------------------------
Proposed: 1 lake
END DESCRIPTION:
XS GIS Cut Line= 3
2446616.14813867 7052797.84363482445818.140876417051927.28992972
2441231.914812687050030.39149255
#Sta/Elev= 30
    1008   461.8    1036   460.4    1104   449.1    1106   436.6    1116   436.2
    1274   438.4    1323   449.8    1360   450.4    1393     450    1470   440.1
    1500   427.7    1530   428.2    1569   434.5    1588     444    1610   444.6
    1669   448.5 3670.52   449.5 5012.09     452 5653.17     448    6455   447.1
 6499.98     446 6518.95     440 6719.67     440 6733.98     446 6769.15  446.14
  6787.2     440 6813.14     440 6821.97     446 6843.15     448    7152     450
#Mann= 7 ,-1,0
    1008     .03       0    1360     .15       0    1470    .055       0
    1610     .18       0 3670.52     .06       0 5012.09     .18       0
 5653.17     .05       0
#XS Ineff= 2 , 0
       0    1393     450    1669       0     451
Permanent Ineff=
       F       F
Bank Sta=1393,1669
XS Rating Curve= 0 ,0
Exp/Cntr=0.3,0.1

Type RM Length L Ch R = 1 ,118745  ,1000,2351,400
BEGIN DESCRIPTION:
This cross section corresponds to cross section 118732 of the non-georeferenced CDC model which was the source of this model.
END DESCRIPTION:
XS GIS Cut Line= 5
2451142.982917017053112.485065882447555.225984937051856.77005763
2445873.463928497051520.418040052441251.603749667049917.78541856
2440779.197917257049753.97842997
#Sta/Elev= 30
    1000   499.6    1538     461    1802     454    3535   448.7    3628   456.1
    4380     446    4689   448.6    4749   456.4    4884   446.3    5193   449.3
    5245   442.8    5348   442.8    5368   441.1    5398  428.54    5480   434.5
    5484     442    5575   449.1    7200     449 9215.07     450    9950     448
10629.15     44810723.16     44610737.34     44010939.21     44010960.53     448
11151.01     44611196.23  452.1811311.24  448.63   11399     45611908.06     456
#Mann= 6 ,-1,0
    1000     .08       0    5348    .055       0    5484     .18       0
    7200     .06       0 9215.07     .15       0    9950     .05       0
#XS Ineff= 2 , 0
       0    4000     460   10720       0     460
Permanent Ineff=
       F       F
Bank Sta=5368,5575
XS Rating Curve= 0 ,0
Exp/Cntr=0.3,0.1

Type RM Length L Ch R = 1 ,116394  ,2363,2586,719
BEGIN DESCRIPTION:
This cross section corresponds to cross section 116381 of the non-georeferenced CDC model which was the source of this model.
END DESCRIPTION:
XS GIS Cut Line= 5
2452353.851886337051968.887943642446927.367988687050713.17195113
2445002.181878427050899.48096171 2441600.99248667049834.71439047
2441219.261091727049715.21065762
#Sta/Elev= 30
    1000   501.2    1650   485.8    2264     457    2354   465.7    3267   446.6
    5536   454.1    5743     446    5991   453.8    6000  453.35    6000     446
    6120     446 6120.04   452.4    6272   448.4    6440   455.4    6504   449.4
    7367   447.5    7382   434.5    7424   434.5    7468   448.4    8127   449.1
    8177   444.2    8253   422.1    8291   446.3    8311   451.110071.73     450
11726.56     44811803.53     44011993.71     45812068.02   448.412468.02   448.4
#Mann= 7 ,-1,0
    1000    .075       0    6504     .08       0    7367    .055       0
    7468     .18       0    8127     .05       0    8311     .05       0
10071.73     .04       0
#XS Ineff= 2 , 0
       0    4500     460   11690       0     460
Permanent Ineff=
       F       F
Bank Sta=8127,8311
XS Rating Curve= 0 ,0
Exp/Cntr=0.3,0.1

Type RM Length L Ch R = 1 ,113808  ,945,1070,473
BEGIN DESCRIPTION:
This cross section corresponds to cross section 113864 of the non-georeferenced CDC model which was the source of this model.
---------------------------------------------------------------------
CDC CAR040202-1 Indian Creek Golf Course
Cross-section 113864 - 118732
Located in LOB.
---------------------------------------------------------------------
END DESCRIPTION:
XS GIS Cut Line= 4
2452814.946108527046433.737924712444698.272053187050284.53993438
2441818.028141777049806.243646892441522.080950917049757.09834981
#Sta/Elev= 30
    1000   456.3    1163   459.7    1644   456.8    2179   459.5    2567   452.3
    3149   452.1    3303   455.8    3339   451.3    4959   454.7    5252   449.8
    5389   454.2    5902   453.1    6014   448.3 7160.01     451    7386   447.9
    7490   451.7    7510   451.3 7510.01   447.3    7655   446.2    7703     438
    7755   418.4    7818     444    8073   446.4 10914.3   449.2   11200     448
12644.47     44812731.22     44012773.04     44012903.51  454.5813203.51  454.58
#Mann= 7 ,-1,0
    1000     .04       0    7386     .06       0    7655    .055       0
    7818     .15       0    8073    .055       0 10914.3     .15       0
   11200     .04       0
#XS Ineff= 2 , 0
       0                   12740       0     460
Permanent Ineff=
       F       F
Bank Sta=7655,7818
XS Rating Curve= 0 ,0
Exp/Cntr=0.3,0.1

Type RM Length L Ch R = 1 ,112738  ,106,106,101
BEGIN DESCRIPTION:
This cross section corresponds to cross section 112732 of the non-georeferenced CDC model which was the source of this model.
END DESCRIPTION:
XS GIS Cut Line= 6
2454665.08816644  7039240.349443  2450764.779933 7043799.6910275
 2447010.4459065 7048188.3932081 2444524.0758793 7049786.2551698
 2441752.9016316 7049743.81430982441355.426507167049737.72671332
#Sta/Elev= 30
   -5000   448.9    1000   448.9    1391   449.6    1416     444    1491   442.8
    1874     447    2010   453.5    2218   450.1    3033   449.2    6183   451.2
    6560   452.2    6603   455.4    6622   451.4    7375   452.6    7397   447.9
    7846   450.3    8226   445.8    8265     435    8300  416.73    8383   442.8
    8480   449.2    9170   447.9 9903.24     450 9988.57     44811877.94   446.8
12076.83     448 12161.5  444.86 12200.3     438   12335   446.5   12900   446.2
#Mann= 10 ,-1,0
   -5000     .04       0    1000     .04       0    7375     .07       0
    8226     .05       0    8383      .1       0    8480     .04       0
    9170     .09       0 9903.24     .04       0 9988.57     .09       0
11877.94     .04       0
#XS Ineff= 10 ,-1
   -5000    7377     460    7377    7710   445.8    7710    8020     460
    8020    8226   445.8    8383    8440   442.8    8440    9380     460
    9380   11200   442.8   11200   11500     460   1150012277.01   442.8
   12600   12900     460
Permanent Ineff=
       F       F       F       F       F       F       F       F       F       F
Bank Sta=8226,8383
XS Rating Curve= 0 ,0
Exp/Cntr=0.3,0.1

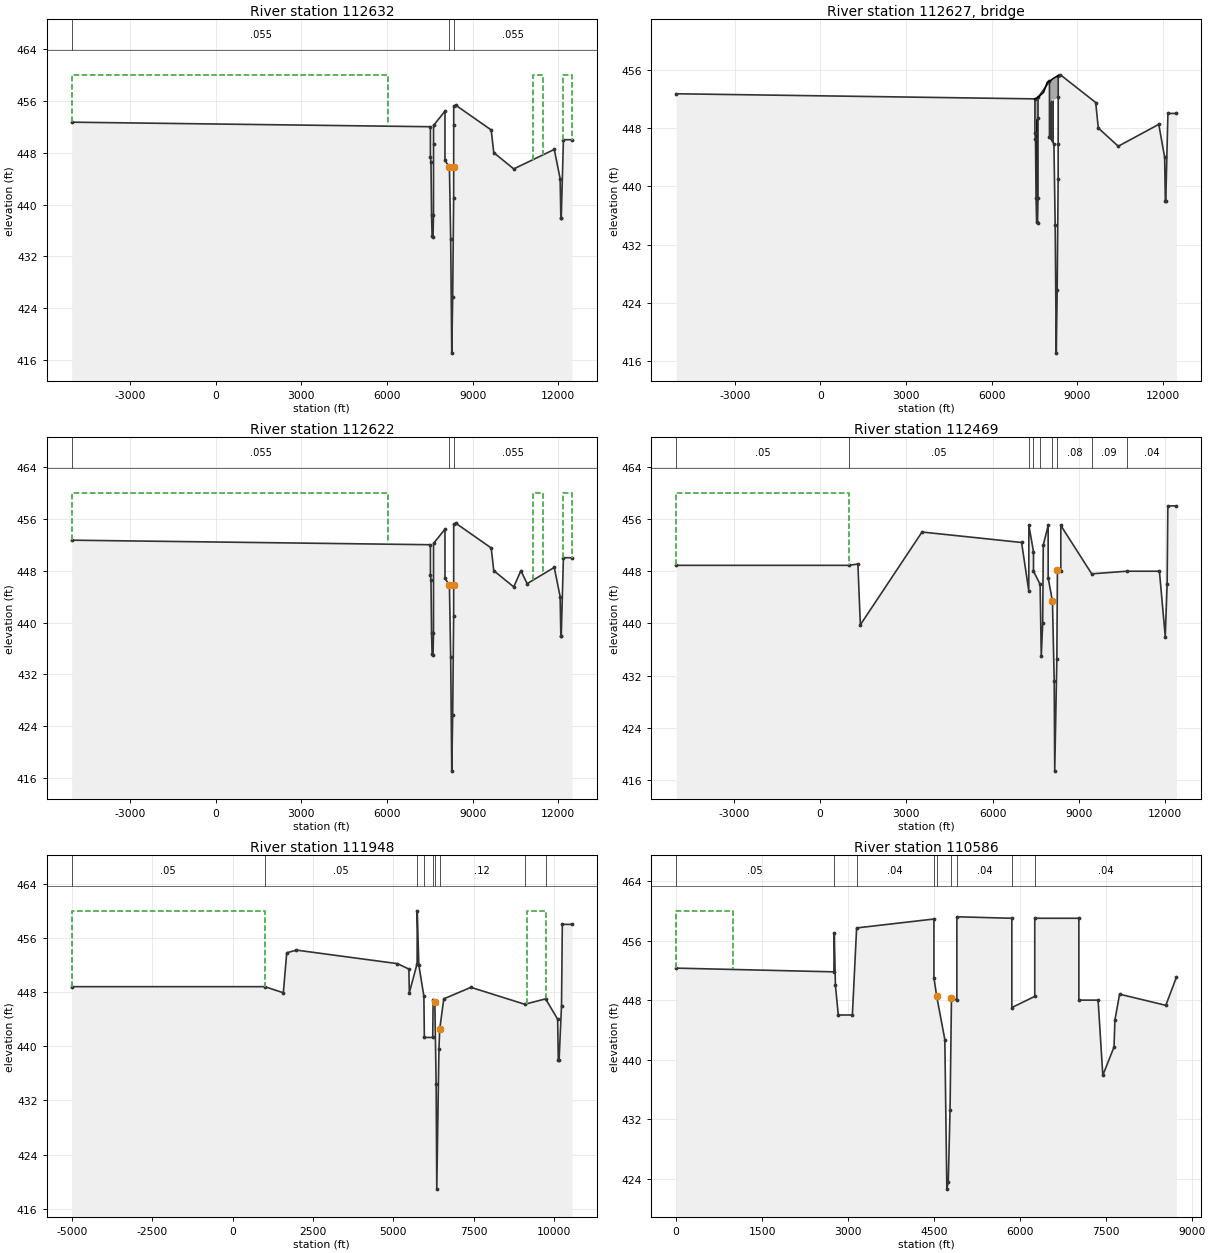
Type RM Length L Ch R = 1 ,112632  ,10,10,10
BEGIN DESCRIPTION:
This cross section corresponds to cross section 112627 of the non-georeferenced CDC model which was the source of this model.
END DESCRIPTION:
XS GIS Cut Line= 6
2454613.080887117039131.288608232447018.389460187048049.04506154
2447012.772017337048053.76519647 2444588.33264057049628.17707388
 2444391.28185357049676.493906382441676.266494257049727.68022084
#Sta/Elev= 30
   -5050   452.7    7520     452    7520   447.3    7540   446.5    7560   438.4
    7579   435.1    7612     435    7628   438.4    7629   449.4    7629   452.2
    8030   454.4    8030   446.8    8186   445.8    8230   434.7    8268   417.1
    8300   425.7    8334     441    8335   445.8    8336   452.2    8336   455.2
    8414   455.3    9650   451.5    9740     448   10440   445.5   11860   448.5
   12065     444   12090     438   12105     438   12180     450   12480     450
#Mann= 3 ,0,0
   -5050    .055       0    8186     .05       0    8335    .055       0
#XS Ineff= 3 ,-1
   11100   11480     460   -5050    6050     460   12180   12480     460
Permanent Ineff=
       F       F       F
Bank Sta=8186,8335
XS Rating Curve= 0 ,0
Exp/Cntr=0.5,0.3

Type RM Length L Ch R = 3 ,112627  ,,,
BEGIN DESCRIPTION:
Union Pacific Railroad
END DESCRIPTION:
Node Name=UP Railroad
Bridge Culvert--1,0,-1,-1, 0
Deck Dist Width WeirC Skew NumUp NumDn MinLoCord MaxHiCord MaxSubmerge Is_Ogee
1,8,2.6,0, 22, 22, , , 0.95, 0, ,,,
    7520  7545.2  7548.8  7572.2  7575.8  7599.2  7602.8    7629    7629    7826
    7952    8030    8030  8060.3  8065.7  8093.3  8098.7  8126.3  8131.7    8158
    8164    8336
     452  452.05  452.05   452.1   452.1  452.15  452.15   452.2   452.2   452.9
   454.3   454.4   454.4  454.49  454.51  454.59  454.61  454.69  454.71  454.79
  454.81   455.2
   449.2  449.25  449.25   449.3   449.3  449.35  449.35   449.4   452.2   452.9
   454.3   454.4   451.6  451.69  451.71  451.79  451.81  451.89  451.91  451.99
  451.81   452.2
    7520  7545.2  7548.8  7572.2  7575.8  7599.2  7602.8    7629    7629    7826
    7952    8030    8030  8060.3  8065.7  8093.3  8098.7  8126.3  8131.7    8158
    8164    8336
     452  452.05  452.05   452.1   452.1  452.15  452.15   452.2   452.2   452.9
   454.3   454.4   454.4  454.49  454.51  454.59  454.61  454.69  454.71  454.79
  454.81   455.2
   449.2  449.25  449.25   449.3   449.3  449.35  449.35   449.4   452.2   452.9
   454.3   454.4   451.6  451.69  451.71  451.79  451.81  451.89  451.91  451.99
  451.81   452.2
Pier Skew, UpSta & Num, DnSta & Num=  ,7547, 2 ,7547, 2 , 0 , 0 , 0 ,,
     3.6     3.6
     430     450
     3.6     3.6
     430     450
Pier Skew, UpSta & Num, DnSta & Num=  ,7574, 2 ,7574, 2 , 0 , 0 , 0 ,,
     3.6     3.6
     430     450
     3.6     3.6
     430     450
Pier Skew, UpSta & Num, DnSta & Num=  ,7601, 2 ,7601, 2 , 0 , 0 , 0 ,,
     3.6     3.6
     430     450
     3.6     3.6
     430     450
Pier Skew, UpSta & Num, DnSta & Num=  ,8063, 2 ,8063, 2 , 0 , 0 , 0 ,,
     5.4     5.4
     430     454
     5.4     5.4
     430     454
Pier Skew, UpSta & Num, DnSta & Num=  ,8096, 2 ,8096, 2 , 0 , 0 , 0 ,,
     5.4     5.4
     430     454
     5.4     5.4
     430     454
Pier Skew, UpSta & Num, DnSta & Num=  ,8129, 2 ,8129, 2 , 0 , 0 , 0 ,,
     5.4     5.4
     430     454
     5.4     5.4
     430     454
Pier Skew, UpSta & Num, DnSta & Num=  ,8161, 2 ,8161, 2 , 0 , 0 , 0 ,,
       6       6
     430     454
       6       6
     430     454
BR Coef= 1 , 0 , 0 ,1.05, 0 ,,,0.8,-1,0.5,1,
WSPro=,,,, 1 ,,,, 0 ,,,, 0 ,,,,-1 ,-1 ,-1 , 0 , 0 , 0 , 0 , 0
BC Design=,, 0 ,, 0 ,,,,,,
BC HTab HWMax=455.3
BC Use User HTab Curves=0
BC User HTab FreeFlow(D)= 0

Type RM Length L Ch R = 1 ,112622  ,162,153,124
BEGIN DESCRIPTION:
This cross section corresponds to cross section 112617 of the non-georeferenced CDC model which was the source of this model.
END DESCRIPTION:
XS GIS Cut Line= 6
2454605.014264917039124.507053422447018.87863243 7048036.0893788
2447013.258564927048040.778673892444593.936960017049613.46155213
2444398.688990927049666.366301972441667.776814547049726.94189283
#Sta/Elev= 30
   -5050   452.7    7520     452    7521   447.3    7540   446.5    7560   438.4
    7579   435.1    7612     435    7628   438.4    7629   452.2    8030   454.4
    8031   446.8    8186   445.8    8230   434.7    8268   417.1    8300   425.7
    8334     441    8335   445.8    8336   455.2    8414   455.3    9650   451.5
    9740     448   10440   445.5   10690     448   10910     446   11860   448.5
   12065     444   12090     438   12105     438   12180     450   12480     450
#Mann= 3 ,0,0
   -5050    .055       0    8186     .05       0    8335    .055       0
#XS Ineff= 3 ,-1
   11100   11480     460   -5050    6050     460   12180   12480     460
Permanent Ineff=
       F       F       F
Bank Sta=8186,8335
XS Rating Curve= 0 ,0
Exp/Cntr=0.5,0.3

Type RM Length L Ch R = 1 ,112469  ,512,521,326
BEGIN DESCRIPTION:
This cross section corresponds to cross section 112494 of the non-georeferenced CDC model which was the source of this model.
END DESCRIPTION:
XS GIS Cut Line= 6
  2454473.107568 7039078.9619397  2450596.258944  7043658.268082
 2447023.7788851 7047878.0562303 2444497.0109728 7049541.6582181
 2441966.4149841 7049704.1467382  2441667.031509 7049723.3700271
#Sta/Elev= 30
   -5000   448.9    1000   448.9    1316   449.1    1402   439.8    3545     454
    7006   452.4    7256     445    7260     455    7420     451    7420     448
    7650     446    7690     435    7740     440    7760     452    7930     455
    7930     447    8079   443.4    8140   431.2    8158   417.4    8232   434.5
    8252   448.2    8370     448    8370     455    9444   447.6   10658     448
   11797     448   12000     438   12065     446   12090     458   12390     458
#Mann= 9 ,-1,0
   -5000     .05       0    1000     .05       0    7260     .05       0
    7420     .03       0    7650     .06       0    8079     .05       0
    8252     .08       0    9444     .09       0   10658     .04       0
#XS Ineff= 3 ,-1
   -5050    1000     460    1000    8079   443.4    8252   12090   448.2
Permanent Ineff=
       F       F       F
Bank Sta=8079,8252
XS Rating Curve= 0 ,0
Exp/Cntr=0.3,0.1

Type RM Length L Ch R = 1 ,111948  ,800,1362,500
BEGIN DESCRIPTION:
This cross section corresponds to cross section 111934 of the non-georeferenced CDC model which was the source of this model.
END DESCRIPTION:
XS GIS Cut Line= 6
  2454410.107568 7039078.9619397 2448208.9070922 7045989.4530521
  2445438.210862 7048377.4951921 2444163.3745009 7049191.5850993
  2441975.089179  7049694.151679  2441675.089179  7049694.151679
#Sta/Elev= 30
   -5000   448.8    1000   448.8    1579   447.9    1684   453.8    1985   454.2
    5127   452.2    5481   451.4    5495   447.9    5737   452.2    5740     460
    5790     452    5947   447.4    5962   441.3    6222   441.3    6235   446.9
    6288   446.5    6328   434.4    6348   418.9    6415   439.6    6439   442.5
    6565     447    7410   448.7    9083   446.2    9730     447   10105     444
   10125     438   10150     438   10225     446   10250     458   10550     458
#Mann= 9 ,-1,0
   -5000     .05       0    1000     .05       0    5740     .05       0
    5947     .03       0    6235     .06       0    6288     .05       0
    6439     .12       0    9083    .055       0    9730     .04       0
#XS Ineff= 5 ,-1
    5740    6288   446.5    6439    9150   442.5    9150    9730     460
    9730   10250   442.5   -6000    1000     460
Permanent Ineff=
       F       F       F       F       F
Bank Sta=6288,6439
XS Rating Curve= 0 ,0
Exp/Cntr=0.3,0.1

Type RM Length L Ch R = 1 ,110586  ,98,98,98
BEGIN DESCRIPTION:
This cross section corresponds to cross section 110572 of the non-georeferenced CDC model which was the source of this model.
END DESCRIPTION:
XS GIS Cut Line= 6
2448239.216124777045645.43833622 2442902.2979548   7049091.26509
  2442643.503853 7049357.4450038 2442253.2192005 7049629.6347481
 2441975.9927208 7049693.0739257 2440726.5552591 7049685.8642945
#Sta/Elev= 30
       0   452.3    2753   451.8    2760     457    2780     450    2830     446
    3076     446    3150   457.7    4500   458.9    4500     451    4546   448.6
    4690   442.7    4725   422.6    4750   423.6    4781   433.2    4806   448.3
    4900     448    4900   459.2    5860     459    5860     447    6260   448.5
    6260     459    7030     459    7030     448    7366     448    7448   437.9
    7644   441.7    7659   445.3    7741   448.8    8548   447.3    8734   451.1
#Mann= 9 ,-1,0
       0     .05       0    2760     .05       0    3150     .04       0
    4500      .1       0    4546     .05       0    4806     .12       0
    4900     .04       0    5860     .12       0    6260     .04       0
#XS Ineff= 3 ,-1
       0    1000     460    1000    4546   448.6    4806    8734   448.3
Permanent Ineff=
       F       F       F
Bank Sta=4546,4806
XS Rating Curve= 0 ,0
Exp/Cntr=0.3,0.1