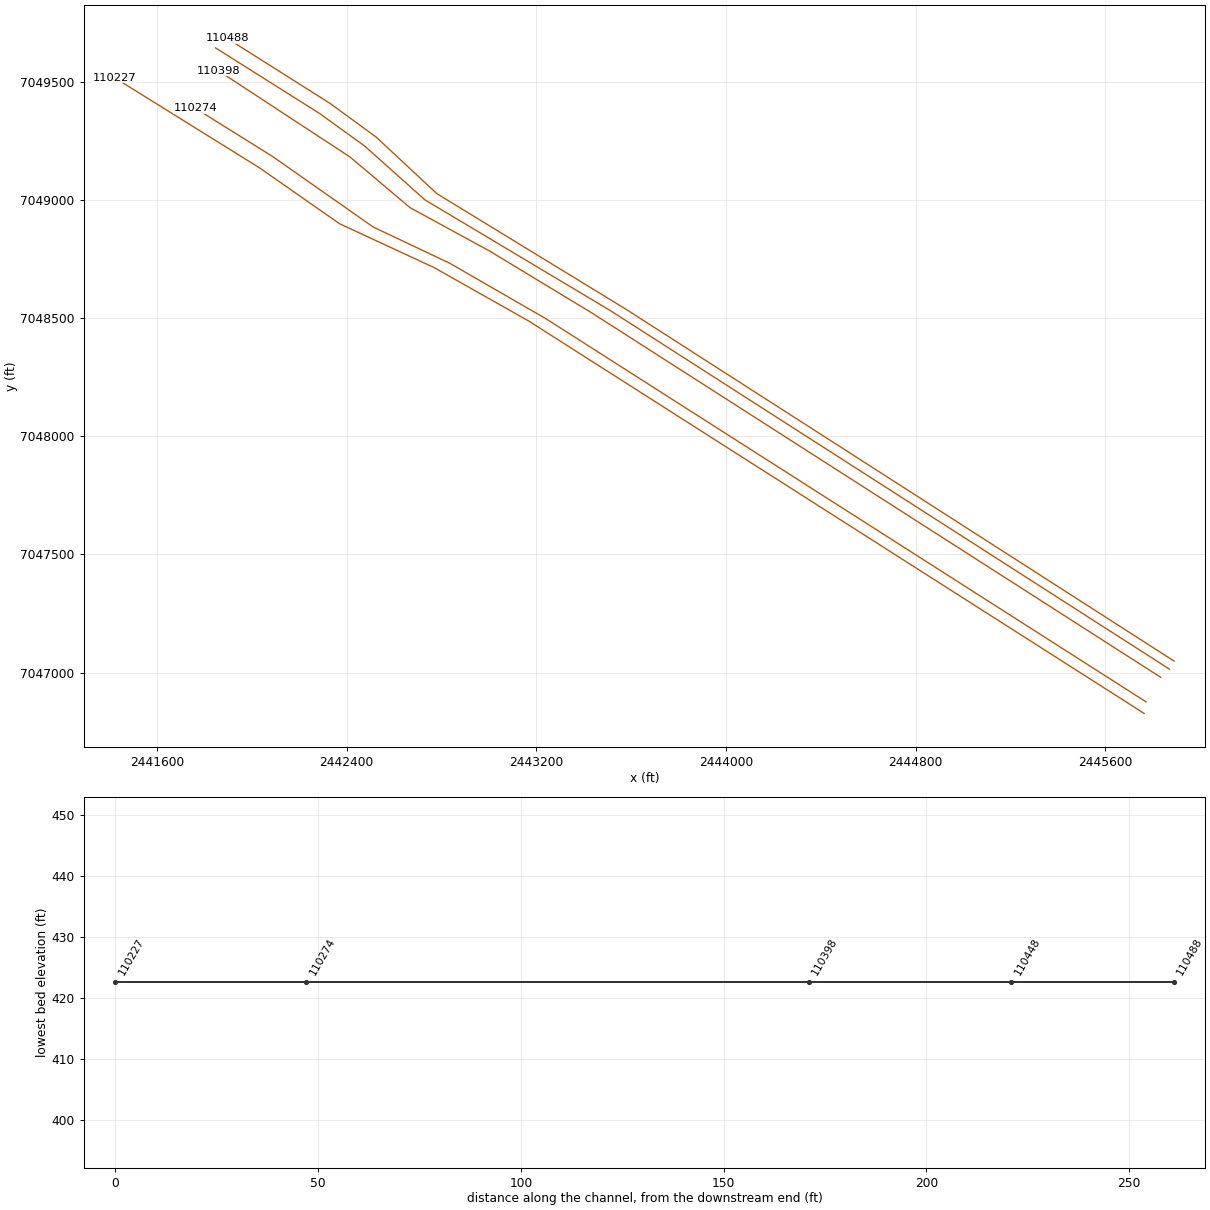
HEC-RAS study CDC_Consolidated_Model.prj: Upper Trinity CDC Consolidated Model

--- CDC_Consolidated_Model.g02 (geometry) --- (continued)

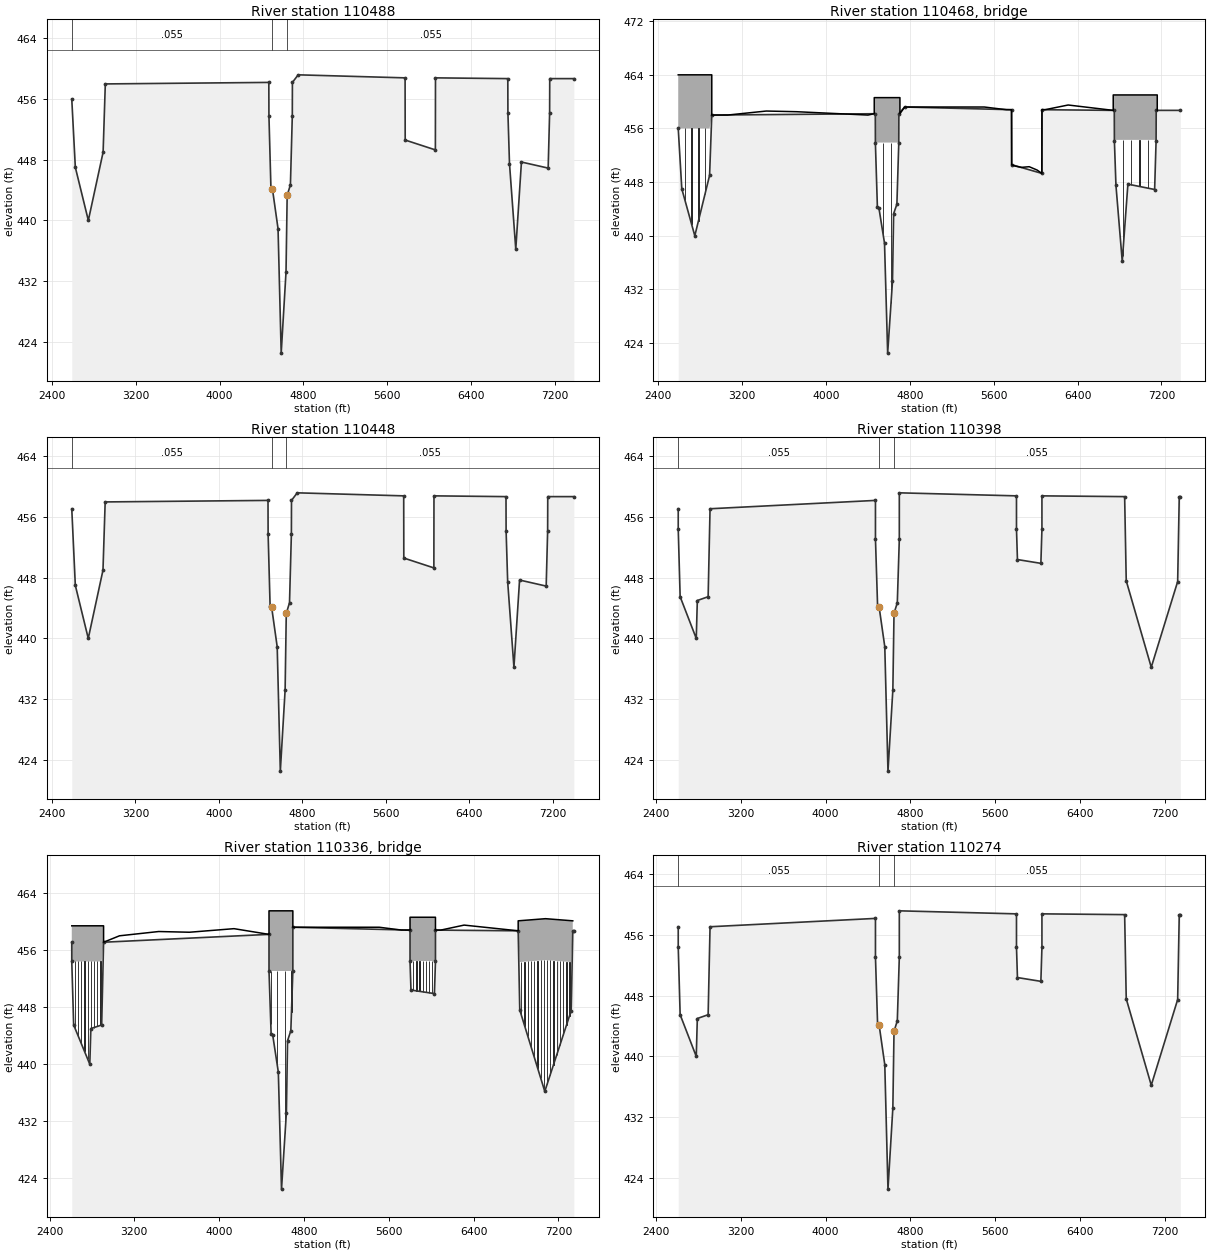
Type RM Length L Ch R = 1 ,110488  ,40,40,40
BEGIN DESCRIPTION:
This cross section corresponds to cross section 110475 of the non-georeferenced CDC model which was the source of this model.
END DESCRIPTION:
XS GIS Cut Line= 6
2445889.135157027047048.917468642443576.38125235 7048539.1297113
2442780.950100427049027.153669632442524.952580937049266.50358464
2442331.572390267049408.48361564 2441896.70743697049684.46347108
#Sta/Elev= 30
    2590     456    2624     447    2748     440    2889     449    2910     458
    4470   458.2    4471   453.8    4490   444.3    4505   444.1    4558   438.9
    4588   422.5    4634   433.2    4645   443.3    4676   444.7    4694   453.8
    4695   458.2    4750   459.2    5770   458.8    5771   450.6    6059   449.3
    6060   458.8    6750   458.7    6751   454.2    6766   447.5    6826   436.2
    6880   447.7    7135   446.9    7149   454.2    7150   458.7    7380   458.7
#Mann= 3 ,0,0
    2590    .055       0    4505     .05       0    4645    .055       0
#XS Ineff= 2 , 0
       0    4505   444.1    4645       0   443.3
Permanent Ineff=
       F       F
Bank Sta=4505,4645
XS Rating Curve= 0 ,0
Exp/Cntr=0.5,0.3

Type RM Length L Ch R = 3 ,110468  ,,,
BEGIN DESCRIPTION:
IH 35E Access Road North Bound
END DESCRIPTION:
Node Name=IH 35E access ro
Bridge Culvert--1,0,-1,-1, 0
Deck Dist Width WeirC Skew NumUp NumDn MinLoCord MaxHiCord MaxSubmerge Is_Ogee
2,36,2.6,0, 28, 28, , , 0.95, 0, ,,,
    2590    2910    2910    3060    3430    3720    4400    4460    4460    4705
    4705    4750    5510    5720    5770    5771    5802    5864    5938    6014
    6059    6060    6090    6310    6740    6740    7160    7160
     464     464     458     458   458.6   458.5     458   458.2   460.6   460.6
   458.2   459.2   459.2   458.8   458.8   450.6   450.4   450.2   450.3   449.8
   449.3   458.8   458.8   459.5   458.7     461     461   458.7
     456     456     458     458   458.6   458.5     458   458.2   453.9   453.9
   458.2   459.2   459.2   458.8   458.8   450.6   450.4   450.2   450.3   449.8
   449.3   458.8   458.8   459.5   458.7   454.3   454.3   458.7
    2590    2910    2910    3060    3430    3720    4400    4460    4460    4705
    4705    4750    5510    5720    5770    5771    5802    5864    5938    6014
    6059    6060    6090    6310    6740    6740    7160    7160
     464     464     458     458   458.6   458.5     458   458.2   460.6   460.6
   458.2   459.2   459.2   458.8   458.8   450.6   450.4   450.2   450.3   449.8
   449.3   458.8   458.8   459.5   458.7     461     461   458.7
     456     456     458     458   458.6   458.5     458   458.2   453.9   453.9
   458.2   459.2   459.2   458.8   458.8   450.6   450.4   450.2   450.3   449.8
   449.3   458.8   458.8   459.5   458.7   454.3   454.3   458.7
Pier Skew, UpSta & Num, DnSta & Num=  ,2654, 2 ,2654, 2 , 0 , 0 , 0 ,,
       3       3
     400     460
       3       3
     400     460
Pier Skew, UpSta & Num, DnSta & Num=  ,2718, 2 ,2718, 2 , 0 , 0 , 0 ,,
       3       3
     400     460
       3       3
     400     460
Pier Skew, UpSta & Num, DnSta & Num=  ,2782, 2 ,2782, 2 , 0 , 0 , 0 ,,
       3       3
     400     460
       3       3
     400     460
Pier Skew, UpSta & Num, DnSta & Num=  ,2846, 2 ,2846, 2 , 0 , 0 , 0 ,,
       3       3
     400     460
       3       3
     400     460
Pier Skew, UpSta & Num, DnSta & Num=  ,2910, 2 ,2910, 2 , 0 , 0 , 0 ,,
       3       3
     400     460
       3       3
     400     460
Pier Skew, UpSta & Num, DnSta & Num=  ,4545, 2 ,4545, 2 , 0 , 0 , 0 ,,
     2.5     2.5
     420     459
     2.5     2.5
     420     459
Pier Skew, UpSta & Num, DnSta & Num=  ,4620, 2 ,4620, 2 , 0 , 0 , 0 ,,
     2.5     2.5
     420     459
     2.5     2.5
     420     459
Pier Skew, UpSta & Num, DnSta & Num=  ,6830, 2 ,6830, 2 , 0 , 0 , 0 ,,
     2.5     2.5
     420     459
     2.5     2.5
     420     459
Pier Skew, UpSta & Num, DnSta & Num=  ,6910, 2 ,6910, 2 , 0 , 0 , 0 ,,
     2.5     2.5
     420     459
     2.5     2.5
     420     459
Pier Skew, UpSta & Num, DnSta & Num=  ,6990, 2 ,6990, 2 , 0 , 0 , 0 ,,
     2.5     2.5
     420     459
     2.5     2.5
     420     459
Pier Skew, UpSta & Num, DnSta & Num=  ,7070, 2 ,7070, 2 , 0 , 0 , 0 ,,
     2.5     2.5
     420     459
     2.5     2.5
     420     459
BR Coef= 1 , 0 , 0 ,1.05, 0 ,,,0.8,-1,0.5,1,
WSPro=,,,, 1 ,,,, 0 ,,,, 0 ,,,,-1 ,-1 ,-1 , 0 , 0 , 0 , 0 , 0
BC Design=,, 0 ,, 0 ,,,,,,
BC HTab HWMax=459.5
BC Use User HTab Curves=0
BC User HTab FreeFlow(D)= 0

Type RM Length L Ch R = 1 ,110448  ,50,50,50
BEGIN DESCRIPTION:
This cross section corresponds to cross section 110435 of the non-georeferenced CDC model which was the source of this model.
END DESCRIPTION:
XS GIS Cut Line= 6
2445869.466233077047014.833875392443513.550341257048531.47060588
2442730.790751937049000.757725052442476.094739027049228.98397464
2442285.974056247049366.696297632441847.896182547049644.10178698
#Sta/Elev= 30
    2590   457.1    2624     447    2748     440    2889     449    2910     458
    4470   458.2    4471   453.8    4490   444.3    4505   444.1    4558   438.9
    4588   422.5    4634   433.2    4645   443.3    4676   444.7    4694   453.8
    4695   458.2    4750   459.2    5770   458.8    5771   450.6    6059   449.3
    6060   458.8    6750   458.7    6751   454.2    6766   447.5    6826   436.2
    6880   447.7    7135   446.9    7149   454.2    7150   458.7    7400   458.7
#Mann= 3 ,0,0
    2590    .055       0    4505     .05       0    4645    .055       0
#XS Ineff= 2 , 0
       0    4505   444.1    4645       0   443.3
Permanent Ineff=
       F       F
Bank Sta=4505,4645
XS Rating Curve= 0 ,0
Exp/Cntr=0.5,0.3

Type RM Length L Ch R = 1 ,110398  ,124,124,124
BEGIN DESCRIPTION:
This cross section corresponds to cross section 110385 of the non-georeferenced CDC model which was the source of this model.
END DESCRIPTION:
XS GIS Cut Line= 6
2445832.607711027046980.278498312443436.633828437048520.88007589
 2443003.60385467048784.099693812442668.024801347048967.78633431
2442415.038758757049182.07429156 2441859.38173367049547.82224771
#Sta/Elev= 30
    2610   457.1    2610   454.4    2628   445.5    2780     440    2790     445
    2892   445.5    2910   457.1    4470   458.2    4470   453.1    4490   444.3
    4505   444.1    4558   438.9    4588   422.5    4634   433.2    4645   443.3
    4676   444.7    4695   453.1    4695   459.2    5800   458.8    5800   454.4
    5809   450.4    6030   449.9    6040   454.4    6040   458.8    6820   458.7
    6835   447.6    7071   436.2    7320   447.5    7335   458.7    7345   458.7
#Mann= 3 ,0,0
    2610    .055       0    4505     .05       0    4645    .055       0
#XS Ineff= 2 , 0
       0    4505   444.1    4645       0   443.3
Permanent Ineff=
       F       F
Bank Sta=4505,4645
XS Rating Curve= 0 ,0
Exp/Cntr=0.5,0.3

Type RM Length L Ch R = 3 ,110336  ,,,
BEGIN DESCRIPTION:
IH 35E/Stemmons Freeway
END DESCRIPTION:
Node Name=IH 635E
Bridge Culvert--1,0,-1,-1, 0
Deck Dist Width WeirC Skew NumUp NumDn MinLoCord MaxHiCord MaxSubmerge Is_Ogee
1,122,2.6,0, 25, 25, , , 0.95, 0, ,,,
    2610    2910    2910    3060    3430    3720    4140    4470    4470    4695
    4695    5510    5720  5783.5  5788.5    5800    5800    6040    6040    6090
    6310    6820    6820    7078    7335
   459.4   459.4   457.1     458   458.6   458.5     459   458.2   461.5   461.5
   459.2   459.2   458.8   458.8   458.8   458.8   460.6   460.6   458.8   458.8
   459.5   458.7   460.1   460.4   460.1
   454.4   454.4   457.1     458   458.6   458.5     459   458.2   453.1   453.1
   459.2   459.2   458.8   458.8   458.8   458.8   454.4   454.4   458.8   458.8
   459.5   458.7   454.3   454.6   454.3
    2610    2910    2910    3060    3430    3720    4140    4470    4470    4695
    4695    5510    5720  5783.5  5788.5    5800    5800    6040    6040    6090
    6310    6820    6820    7078    7335
   459.4   459.4   457.1     458   458.6   458.5     459   458.2   461.5   461.5
   459.2   459.2   458.8   458.8   458.8   458.8   460.6   460.6   458.8   458.8
   459.5   458.7   460.1   460.4   460.1
   454.4   454.4   457.1     458   458.6   458.5     459   458.2   453.1   453.1
   459.2   459.2   458.8   458.8   458.8   458.8   454.4   454.4   458.8   458.8
   459.5   458.7   454.3   454.6   454.3
Pier Skew, UpSta & Num, DnSta & Num=  ,2640, 2 ,2640, 2 , 0 , 0 , 0 ,,
     2.5     2.5
     400     457
     2.5     2.5
     400     457
Pier Skew, UpSta & Num, DnSta & Num=  ,2670, 2 ,2670, 2 , 0 , 0 , 0 ,,
     2.5     2.5
     420     458
     2.5     2.5
     420     458
Pier Skew, UpSta & Num, DnSta & Num=  ,2700, 2 ,2700, 2 , 0 , 0 , 0 ,,
     2.5     2.5
     400     457
     2.5     2.5
     400     457
Pier Skew, UpSta & Num, DnSta & Num=  ,2730, 2 ,2730, 2 , 0 , 0 , 0 ,,
     2.5     2.5
     400     457
     2.5     2.5
     400     457
Pier Skew, UpSta & Num, DnSta & Num=  ,2760, 2 ,2760, 2 , 0 , 0 , 0 ,,
     2.5     2.5
     400     457
     2.5     2.5
     400     457
Pier Skew, UpSta & Num, DnSta & Num=  ,2790, 2 ,2790, 2 , 0 , 0 , 0 ,,
     2.5     2.5
     400     457
     2.5     2.5
     400     457
Pier Skew, UpSta & Num, DnSta & Num=  ,2820, 2 ,2820, 2 , 0 , 0 , 0 ,,
     2.5     2.5
     400     457
     2.5     2.5
     400     457
Pier Skew, UpSta & Num, DnSta & Num=  ,2850, 2 ,2850, 2 , 0 , 0 , 0 ,,
     2.5     2.5
     400     457
     2.5     2.5
     400     457
Pier Skew, UpSta & Num, DnSta & Num=  ,2880, 2 ,2880, 2 , 0 , 0 , 0 ,,
     2.5     2.5
     400     457
     2.5     2.5
     400     457
Pier Skew, UpSta & Num, DnSta & Num=  ,4487, 2 ,4487, 2 , 0 , 0 , 0 ,,
     2.5     2.5
     428     458
     2.5     2.5
     428     458
Pier Skew, UpSta & Num, DnSta & Num=  ,4547, 2 ,4547, 2 , 0 , 0 , 0 ,,
     2.5     2.5
     428     458
     2.5     2.5
     428     458
Pier Skew, UpSta & Num, DnSta & Num=  ,4622, 2 ,4622, 2 , 0 , 0 , 0 ,,
     2.5     2.5
     428     458
     2.5     2.5
     428     458
Pier Skew, UpSta & Num, DnSta & Num=  ,4682, 2 ,4682, 2 , 0 , 0 , 0 ,,
     2.5     2.5
     428     458
     2.5     2.5
     428     458
Pier Skew, UpSta & Num, DnSta & Num=  ,5830, 2 ,5830, 2 , 0 , 0 , 0 ,,
     2.5     2.5
     400     460
     2.5     2.5
     400     460
Pier Skew, UpSta & Num, DnSta & Num=  ,5860, 2 ,5860, 2 , 0 , 0 , 0 ,,
     2.5     2.5
     400     460
     2.5     2.5
     400     460
Pier Skew, UpSta & Num, DnSta & Num=  ,5890, 2 ,5890, 2 , 0 , 0 , 0 ,,
     2.5     2.5
     400     460
     2.5     2.5
     400     460
Pier Skew, UpSta & Num, DnSta & Num=  ,5920, 2 ,5920, 2 , 0 , 0 , 0 ,,
     2.5     2.5
     400     460
     2.5     2.5
     400     460
Pier Skew, UpSta & Num, DnSta & Num=  ,5950, 2 ,5950, 2 , 0 , 0 , 0 ,,
     2.5     2.5
     400     460
     2.5     2.5
     400     460
Pier Skew, UpSta & Num, DnSta & Num=  ,5980, 2 ,5980, 2 , 0 , 0 , 0 ,,
     2.5     2.5
     400     460
     2.5     2.5
     400     460
Pier Skew, UpSta & Num, DnSta & Num=  ,6010, 2 ,6010, 2 , 0 , 0 , 0 ,,
     2.5     2.5
     400     460
     2.5     2.5
     400     460
Pier Skew, UpSta & Num, DnSta & Num=  ,6850, 2 ,6850, 2 , 0 , 0 , 0 ,,
     2.5     2.5
     400     460
     2.5     2.5
     400     460
Pier Skew, UpSta & Num, DnSta & Num=  ,6880, 2 ,6880, 2 , 0 , 0 , 0 ,,
     2.5     2.5
     400     460
     2.5     2.5
     400     460
Pier Skew, UpSta & Num, DnSta & Num=  ,6911, 2 ,6911, 2 , 0 , 0 , 0 ,,
     2.5     2.5
     400     460
     2.5     2.5
     400     460
Pier Skew, UpSta & Num, DnSta & Num=  ,6941, 2 ,6941, 2 , 0 , 0 , 0 ,,
     2.5     2.5
     400     460
     2.5     2.5
     400     460
Pier Skew, UpSta & Num, DnSta & Num=  ,6971, 2 ,6971, 2 , 0 , 0 , 0 ,,
     2.5     2.5
     400     460
     2.5     2.5
     400     460
Pier Skew, UpSta & Num, DnSta & Num=  ,7002, 2 ,7002, 2 , 0 , 0 , 0 ,,
     2.5     2.5
     400     460
     2.5     2.5
     400     460
Pier Skew, UpSta & Num, DnSta & Num=  ,7032, 2 ,7032, 2 , 0 , 0 , 0 ,,
     2.5     2.5
     400     460
     2.5     2.5
     400     460
Pier Skew, UpSta & Num, DnSta & Num=  ,7062, 2 ,7062, 2 , 0 , 0 , 0 ,,
     2.5     2.5
     400     460
     2.5     2.5
     400     460
Pier Skew, UpSta & Num, DnSta & Num=  ,7093, 2 ,7093, 2 , 0 , 0 , 0 ,,
     2.5     2.5
     400     460
     2.5     2.5
     400     460
Pier Skew, UpSta & Num, DnSta & Num=  ,7123, 2 ,7123, 2 , 0 , 0 , 0 ,,
     2.5     2.5
     400     460
     2.5     2.5
     400     460
Pier Skew, UpSta & Num, DnSta & Num=  ,7153, 2 ,7153, 2 , 0 , 0 , 0 ,,
     2.5     2.5
     400     460
     2.5     2.5
     400     460
Pier Skew, UpSta & Num, DnSta & Num=  ,7184, 2 ,7184, 2 , 0 , 0 , 0 ,,
     2.5     2.5
     400     460
     2.5     2.5
     400     460
Pier Skew, UpSta & Num, DnSta & Num=  ,7214, 2 ,7214, 2 , 0 , 0 , 0 ,,
     2.5     2.5
     400     460
     2.5     2.5
     400     460
Pier Skew, UpSta & Num, DnSta & Num=  ,7244, 2 ,7244, 2 , 0 , 0 , 0 ,,
     2.5     2.5
     400     460
     2.5     2.5
     400     460
Pier Skew, UpSta & Num, DnSta & Num=  ,7275, 2 ,7275, 2 , 0 , 0 , 0 ,,
     2.5     2.5
     400     460
     2.5     2.5
     400     460
Pier Skew, UpSta & Num, DnSta & Num=  ,7305, 2 ,7305, 2 , 0 , 0 , 0 ,,
     2.5     2.5
     400     460
     2.5     2.5
     400     460
BR Coef= 1 , 0 , 0 ,1.05, 0 ,,,0.8,-1,0.5,1,
WSPro=,,,, 1 ,,,, 0 ,,,, 0 ,,,,-1 ,-1 ,-1 , 0 , 0 , 0 , 0 , 0
BC Design=,, 0 ,, 0 ,,,,,,
BC HTab HWMax=459.5
BC Use User HTab Curves=0
BC User HTab FreeFlow(D)= 0

Type RM Length L Ch R = 1 ,110274  ,47,47,47
BEGIN DESCRIPTION:
This cross section corresponds to cross section 110261 of the non-georeferenced CDC model which was the source of this model.
END DESCRIPTION:
XS GIS Cut Line= 6
2445770.994973337046876.246882222443242.692287187048496.66194847
2442834.748877357048732.865872382442512.141582947048886.09588088
2442087.692300597049184.879075962441762.372741257049388.64999388
#Sta/Elev= 30
    2610   457.1    2610   454.4    2628   445.5    2780     440    2790     445
    2892   445.5    2910   457.1    4470   458.2    4470   453.1    4490   444.3
    4505   444.1    4558   438.9    4588   422.5    4634   433.2    4645   443.3
    4676   444.7    4695   453.1    4695   459.2    5800   458.8    5800   454.4
    5809   450.4    6030   449.9    6040   454.4    6040   458.8    6820   458.7
    6835   447.6    7071   436.2    7320   447.5    7335   458.7    7345   458.7
#Mann= 3 ,0,0
    2610    .055       0    4505     .05       0    4645    .055       0
#XS Ineff= 2 , 0
       0    4505   444.1    4645       0   443.3
Permanent Ineff=
       F       F
Bank Sta=4505,4645
XS Rating Curve= 0 ,0
Exp/Cntr=0.5,0.3

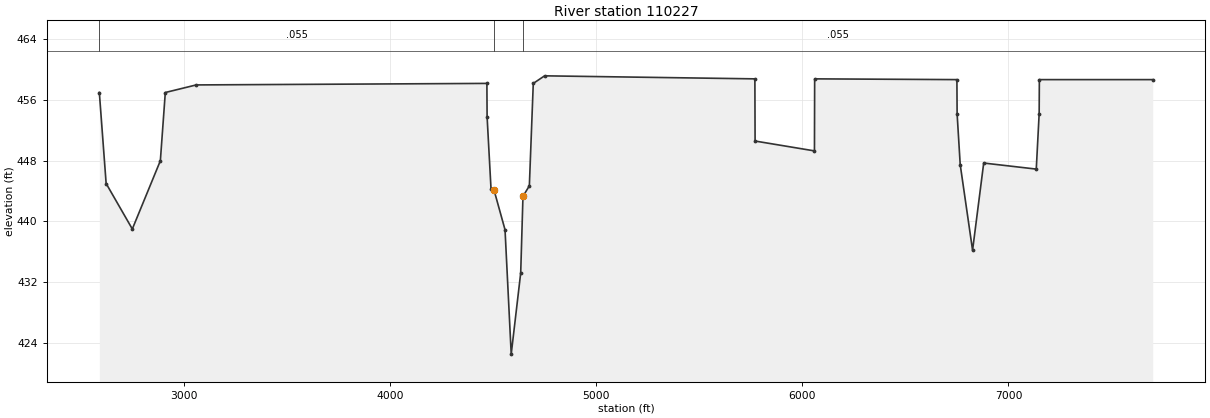
Type RM Length L Ch R = 1 ,110227  ,40,40,40
BEGIN DESCRIPTION:
This cross section corresponds to cross section 110214 of the non-georeferenced CDC model which was the source of this model.
END DESCRIPTION:
XS GIS Cut Line= 6
2445762.770580357046827.490746132443169.604178767048487.20986763
2442769.662065277048713.997471792442370.318375777048900.07616788
2442034.175019177049135.741707062441423.469173657049516.99107139
#Sta/Elev= 30
    2590     457    2623     445    2750     439    2886     448    2910     457
    3060     458    4470   458.2    4471   453.8    4490   444.3    4505   444.1
    4558   438.9    4588   422.5    4634   433.2    4645   443.3    4676   444.7
    4695   458.2    4750   459.2    5770   458.8    5771   450.6    6059   449.3
    6060   458.8    6750   458.7    6751   454.2    6766   447.5    6826   436.2
    6880   447.7    7135   446.9    7149   454.2    7150   458.7    7700   458.7
#Mann= 3 ,0,0
    2590    .055       0    4505     .05       0    4645    .055       0
#XS Ineff= 2 , 0
       0    4505   444.1    4645       0   443.3
Permanent Ineff=
       F       F
Bank Sta=4505,4645
XS Rating Curve= 0 ,0
Exp/Cntr=0.5,0.3