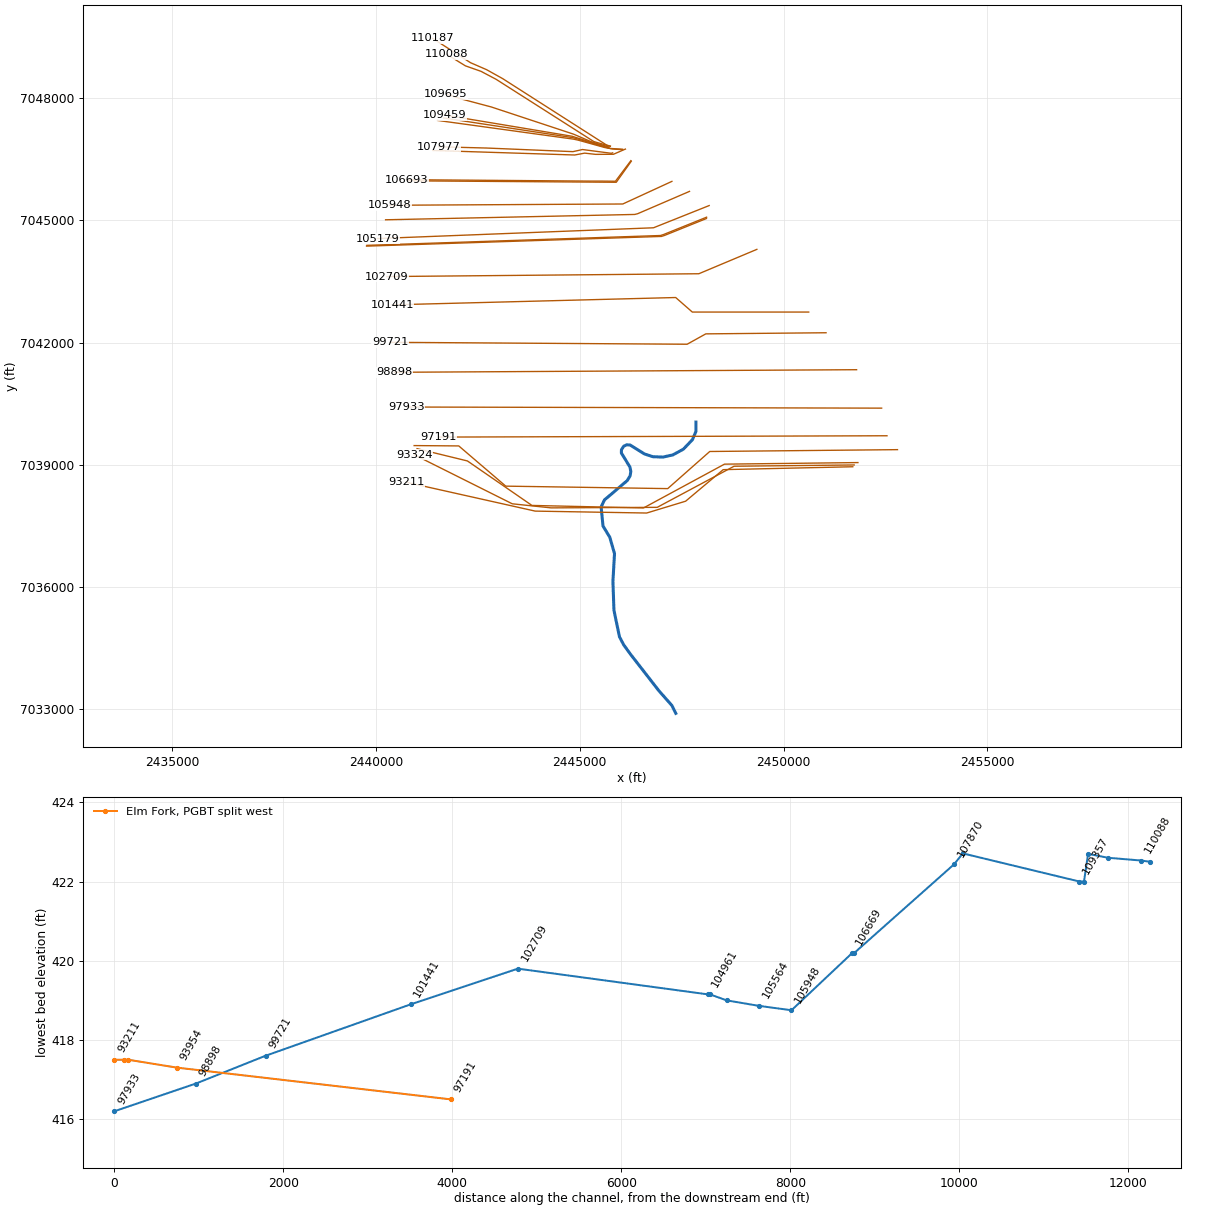
HEC-RAS study CDC_Consolidated_Model.prj: Upper Trinity CDC Consolidated Model

--- CDC_Consolidated_Model.g02 (geometry) --- (continued)

Type RM Length L Ch R = 3 ,110207  ,,,
BEGIN DESCRIPTION:
IH 35E Access Road South Bound
END DESCRIPTION:
Node Name=IH 35E access ro
Bridge Culvert--1,0,-1,-1, 0
Deck Dist Width WeirC Skew NumUp NumDn MinLoCord MaxHiCord MaxSubmerge Is_Ogee
1.5,37,2.6,0, 29, 29, , , 0.95, 0, ,,,
    2590    2910    2910    3060    3430    3720    4140    4400    4460    4460
    4705    4705    4750    5510    5720    5770    5771    5802    5864    5938
    6014    6059    6060    6090    6310    6740    6740    7160    7160
     464     464     457     458   458.6   458.5     459     458   458.2   460.6
   460.6   458.2   459.2   459.2   458.8   458.8   450.6   450.4   450.2   450.3
   449.8   449.3   458.8   458.8   459.5   458.7     461     461   458.7
     457     457     457     458   458.6   458.5     459     458   458.2   453.8
   453.8   458.2   459.2   459.2   458.8   458.8   450.6   450.4   450.2   450.3
   449.8   449.3   458.8   458.8   459.5   458.7   454.2   454.2   458.7
    2590    2910    2910    3060    3430    3720    4140    4400    4460    4460
    4705    4705    4750    5510    5720    5770    5771    5802    5864    5938
    6014    6059    6060    6090    6310    6740    6740    7160    7160
     464     464     457     458   458.6   458.5     459     458   458.2   460.6
   460.6   458.2   459.2   459.2   458.8   458.8   450.6   450.4   450.2   450.3
   449.8   449.3   458.8   458.8   459.5   458.7     461     461   458.7
     457     457     457     458   458.6   458.5     459     458   458.2   453.8
   453.8   458.2   459.2   459.2   458.8   458.8   450.6   450.4   450.2   450.3
   449.8   449.3   458.8   458.8   459.5   458.7   454.2   454.2   458.7
Pier Skew, UpSta & Num, DnSta & Num=  ,2654, 2 ,2654, 2 , 0 , 0 , 0 ,,
       3       3
     420     458
       3       3
     420     458
Pier Skew, UpSta & Num, DnSta & Num=  ,2718, 2 ,2718, 2 , 0 , 0 , 0 ,,
       3       3
     420     458
       3       3
     420     458
Pier Skew, UpSta & Num, DnSta & Num=  ,2782, 2 ,2782, 2 , 0 , 0 , 0 ,,
       3       3
     420     458
       3       3
     420     458
Pier Skew, UpSta & Num, DnSta & Num=  ,2846, 2 ,2846, 2 , 0 , 0 , 0 ,,
       3       3
     420     458
       3       3
     420     458
Pier Skew, UpSta & Num, DnSta & Num=  ,4545, 2 ,4545, 2 , 0 , 0 , 0 ,,
     2.5     2.5
     420     459
     2.5     2.5
     420     459
Pier Skew, UpSta & Num, DnSta & Num=  ,4620, 2 ,4620, 2 , 0 , 0 , 0 ,,
     2.5     2.5
     428     459
     2.5     2.5
     428     459
Pier Skew, UpSta & Num, DnSta & Num=  ,6830, 2 ,6830, 2 , 0 , 0 , 0 ,,
     2.5     2.5
     428     459
     2.5     2.5
     428     459
Pier Skew, UpSta & Num, DnSta & Num=  ,6910, 2 ,6910, 2 , 0 , 0 , 0 ,,
     2.5     2.5
     428     459
     2.5     2.5
     428     459
Pier Skew, UpSta & Num, DnSta & Num=  ,6990, 2 ,6990, 2 , 0 , 0 , 0 ,,
     2.5     2.5
     428     459
     2.5     2.5
     428     459
Pier Skew, UpSta & Num, DnSta & Num=  ,7070, 2 ,7070, 2 , 0 , 0 , 0 ,,
     2.5     2.5
     428     459
     2.5     2.5
     428     459
BR Coef= 1 , 0 , 0 ,1.05, 0 ,,,0.8,-1,0.5,1,
WSPro=,,,, 1 ,,,, 0 ,,,, 0 ,,,,-1 ,-1 ,-1 , 0 , 0 , 0 , 0 , 0
BC Design=,, 0 ,, 0 ,,,,,,
BC HTab HWMax=459.5
BC Use User HTab Curves=0
BC User HTab FreeFlow(D)= 0

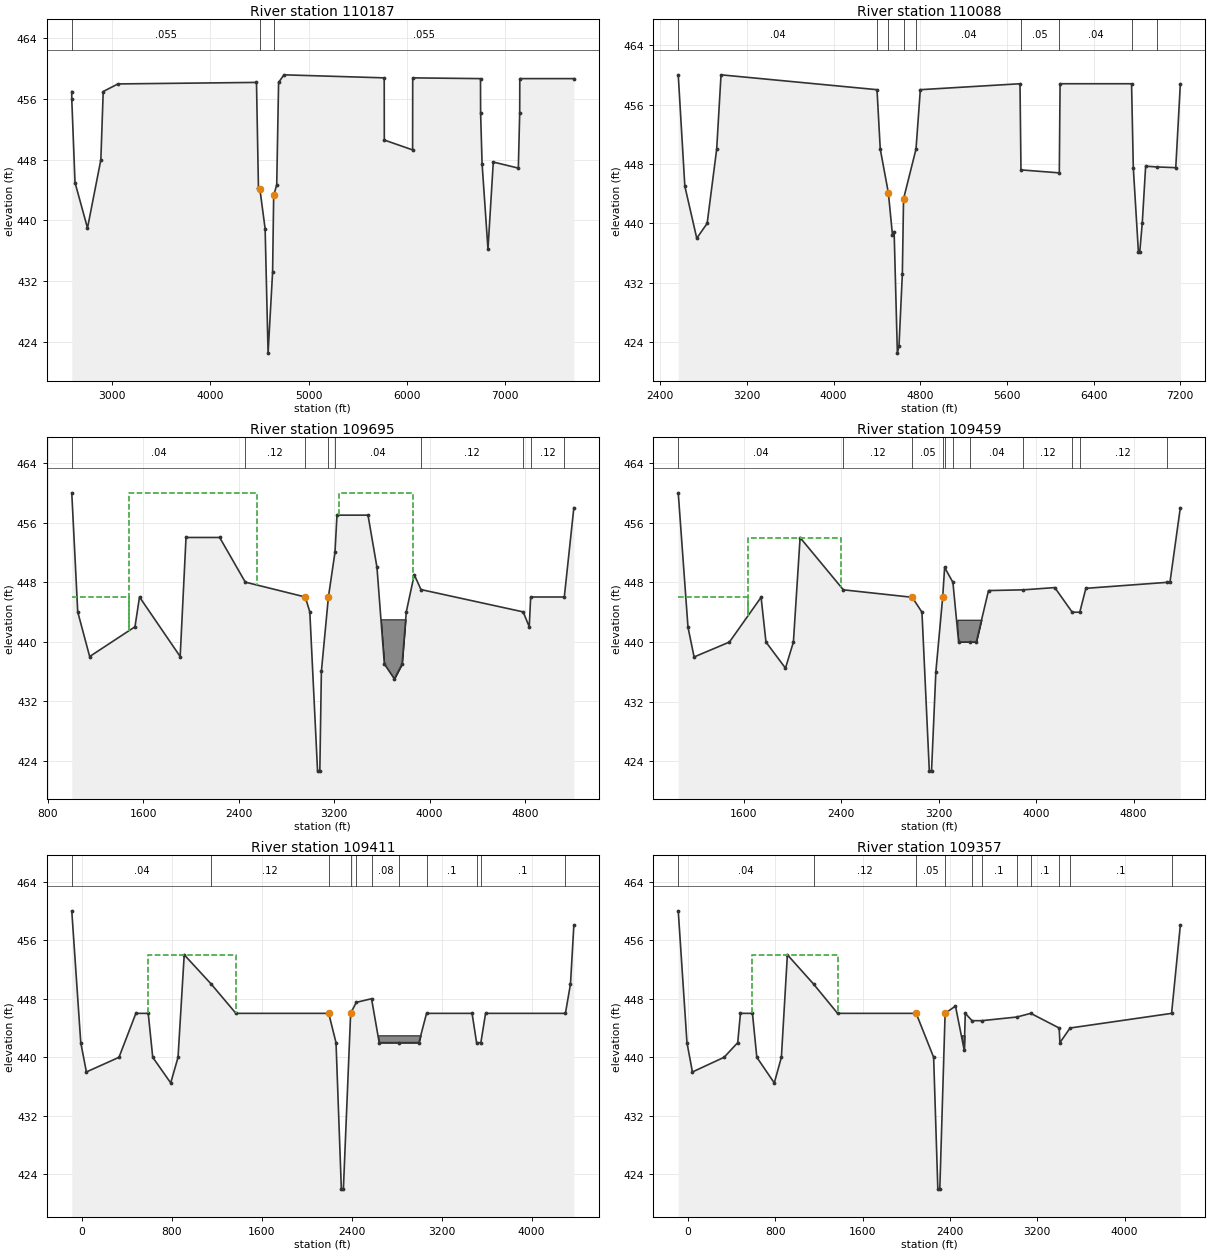
Type RM Length L Ch R = 1 ,110187  ,99,99,99
BEGIN DESCRIPTION:
This cross section corresponds to cross section 110174 of the non-georeferenced CDC model which was the source of this model.
END DESCRIPTION:
XS GIS Cut Line= 6
2445750.485499927046821.746006972445660.48272717 7046847.1055363
 2443106.16631357048479.944134132442715.727789917048697.22847646
2442320.171166337048869.14775205 2441389.32746057049466.92690246
#Sta/Elev= 30
    2590     457    2590     456    2623     445    2750     439    2886     448
    2910     457    3060     458    4470   458.2    4490   444.3    4505   444.1
    4558   438.9    4588   422.5    4634   433.2    4645   443.3    4676   444.7
    4695   458.2    4750   459.2    5770   458.8    5771   450.6    6059   449.3
    6060   458.8    6750   458.7    6751   454.2    6766   447.5    6826   436.2
    6880   447.7    7135   446.9    7149   454.2    7150   458.7    7700   458.7
#Mann= 3 ,0,0
    2590    .055       0    4505     .05       0    4645    .055       0
#XS Ineff= 2 , 0
       0    4505   444.1    4645       0   443.3
Permanent Ineff=
       F       F
Bank Sta=4505,4645
XS Rating Curve= 0 ,0
Exp/Cntr=0.5,0.3

Type RM Length L Ch R = 1 ,110088  ,350,393,827
BEGIN DESCRIPTION:
This cross section corresponds to cross section 110074 of the non-georeferenced CDC model which was the source of this model.
END DESCRIPTION:
XS GIS Cut Line= 6
2445751.427427177046817.661041382445345.934143667046933.79597972
2442947.968139087048461.571139382442577.363893427048657.23905513
2442194.711115427048791.875924962441731.779298517049077.63585213
#Sta/Elev= 30
    2565     460    2626     445    2736     438    2832     440    2920     450
    2960     460    4400     458    4430     450    4505   444.1    4543   438.4
    4558   438.9    4588  422.53    4603   423.5    4634   433.2    4645   443.3
    4760     450    4800     458    5720   458.8    5729   447.2    6083   446.8
    6090   458.8    6750   458.8    6766   447.5    6813   436.2    6826   436.2
    6849   440.1    6880   447.7    6981   447.6    7158   447.5    7200   458.7
#Mann= 9 ,-1,0
    2565     .04       0    4400      .1       0    4505     .05       0
    4645      .1       0    4760     .04       0    5729     .05       0
    6083     .04       0    6750     .09       0    6981     .03       0
#XS Ineff= 2 , 0
       0    4505   444.1    4645       0   443.3
Permanent Ineff=
       F       F
Bank Sta=4505,4645
XS Rating Curve= 0 ,0
Exp/Cntr=0.3,0.1

Type RM Length L Ch R = 1 ,109695  ,168,236,420
BEGIN DESCRIPTION:
This cross section corresponds to cross section 109670 of the non-georeferenced CDC model which was the source of this model.
NEW SECTION ADDED BY OEI
END DESCRIPTION:
XS GIS Cut Line= 6
2445715.926185857046800.19913405 2445277.68559257046930.58732472
2444848.563091167047115.495747552442828.366344187047783.47210188
2442094.442943257047978.625911062441716.040484857048101.30053447
#Sta/Elev= 30
    1000     460    1050     444    1150     438    1530     442    1568     446
    1909     438    1958     454    2240     454    2455     448    2958     446
    2996     444    3061   422.6    3080   422.6    3093     436    3152     446
    3207     452    3224     457    3484     457    3559     450    3621     437
    3705     435    3770     437    3805     444    3872     449    3928     447
    4785     444    4836     442    4848     446    5130     446    5210     458
#Mann= 9 ,-1,0
    1000     .04       0    2455     .12       0    2958     .05       0
    3152     .12       0    3207     .04       0    3928     .12       0
    4785     .06       0    4848     .12       0    5130     .03       0
#XS Ineff= 6 ,-1
    1000    1480     446    1480    2550     460    2550    2958     446
    3152    3240     446    3240    3860     460    3860    5210     446
Permanent Ineff=
       F       F       F       F       F       F
#Block Obstruct= 1 ,-1
    3559    3872     443
Bank Sta=2958,3152
XS Rating Curve= 0 ,0
Exp/Cntr=0.3,0.1

Type RM Length L Ch R = 1 ,109459  ,2,48,85
BEGIN DESCRIPTION:
This cross section corresponds to cross section 109445 of the non-georeferenced CDC model which was the source of this model.
END DESCRIPTION:
XS GIS Cut Line= 3
2445708.647000917046780.327782722444809.831869427047064.88495639
2441675.622914767047585.87604038
#Sta/Elev= 30
    1064     460    1144     442    1194     438    1484     440    1744     446
    1784     440    1944   436.5    2009     440    2064     454    2419     447
    2984     446    3064     444  3124.5   422.7  3142.5   422.7    3178     436
    3234     446    3250     450    3318     448    3365     440    3460     440
    3510     440    3610   446.9    3897     447    4154   447.3    4297     444
    4359     444    4409   447.2    5074     448    5099     448    5184     458
#Mann= 11 ,-1,0
    1064     .04       0    2419     .12       0    2984     .05       0
    3234      .1       0    3250     .05       0    3318     .06       0
    3460     .04       0    3897     .12       0    4297     .06       0
    4359     .12       0    5074     .03       0
#XS Ineff= 4 ,-1
    1064    1634     446    1634    2400     454    2400    2984     446
    3234    5184     446
Permanent Ineff=
       F       F       F       F
#Block Obstruct= 2 ,-1
    3354    3620     443    3760    3880     445
Bank Sta=2984,3234
XS Rating Curve= 0 ,0
Exp/Cntr=0.3,0.1

Type RM Length L Ch R = 1 ,109411  ,2,54,71
BEGIN DESCRIPTION:
This cross section corresponds to cross section 109304 of the non-georeferenced CDC model which was the source of this model.
NEW SECTION ADDED BY OEI,  Excavated Pond, no swale in hole #9 landing area.
END DESCRIPTION:
XS GIS Cut Line= 6
2446051.742115267046745.836709962445756.887061927046764.43575414
2445598.416578357046804.442563882444939.988433247047000.39591213
2444822.626135177047031.196375462441661.358835677047513.08255079
#Sta/Elev= 30
     -90     460     -10     442      40     438     330     440     480     446
     590     446     630     440     790   436.5     855     440     910     454
    1150     450    1370     446    2195     446    2260     442  2307.5     422
  2325.5     422    2390     446    2440   447.5    2576     448    2644     442
    2823     442    2997     442    3065     446    3470     446    3510     442
    3548     442    3590     446    4300     446    4345     450    4375     458
#Mann= 11 ,-1,0
     -90     .04       0    1150     .12       0    2195     .05       0
    2390     .12       0    2440     .05       0    2576     .08       0
    2823     .04       0    3065      .1       0    3510     .06       0
    3548      .1       0    4300     .03       0
#XS Ineff= 4 ,-1
     -90     590     446     590    1370     454    1370    2195     446
    2390    4375     446
Permanent Ineff=
       F       F       F       F
#Block Obstruct= 1 ,-1
    2620    3029     443
Bank Sta=2195,2390
XS Rating Curve= 0 ,0
Exp/Cntr=0.3,0.1

Type RM Length L Ch R = 1 ,109357  ,163,1380,221
BEGIN DESCRIPTION:
This cross section corresponds to cross section 109152 of the non-georeferenced CDC model which was the source of this model.
NEW SECTION ADDED BY OEI.
END DESCRIPTION:
XS GIS Cut Line= 6
2446048.402883087046735.230431962445808.778034277046751.33440238
2445618.218376017046786.543977632444954.597984087046970.67779572
2444836.601500937046994.919873222441511.208217357047452.72374763
#Sta/Elev= 30
     -90     460     -10     442      40     438     330     440     455     442
     480     446     590     446     630     440     790   436.5     855     440
     910     454    1150     450    1370     446    2090     446    2250     440
  2288.5     422  2306.5     422    2355     446    2450     447    2530     441
    2540     446    2602     445    2690     445    3012   445.5    3140     446
    3400     444    3407     442    3500     444    4430     446    4510     458
#Mann= 11 ,-1,0
     -90     .04       0    1150     .12       0    2090     .05       0
    2355     .12       0    2602     .05       0    2690      .1       0
    3012     .05       0    3140      .1       0    3400     .06       0
    3500      .1       0    4430     .03       0
#XS Ineff= 4 ,-1
     -90     590     446     590    1370     454    1370    2090     446
    2355    4510     446
Permanent Ineff=
       F       F       F       F
#Block Obstruct= 1 ,-1
    2492    2540     443
Bank Sta=2090,2355
XS Rating Curve= 0 ,0
Exp/Cntr=0.3,0.1

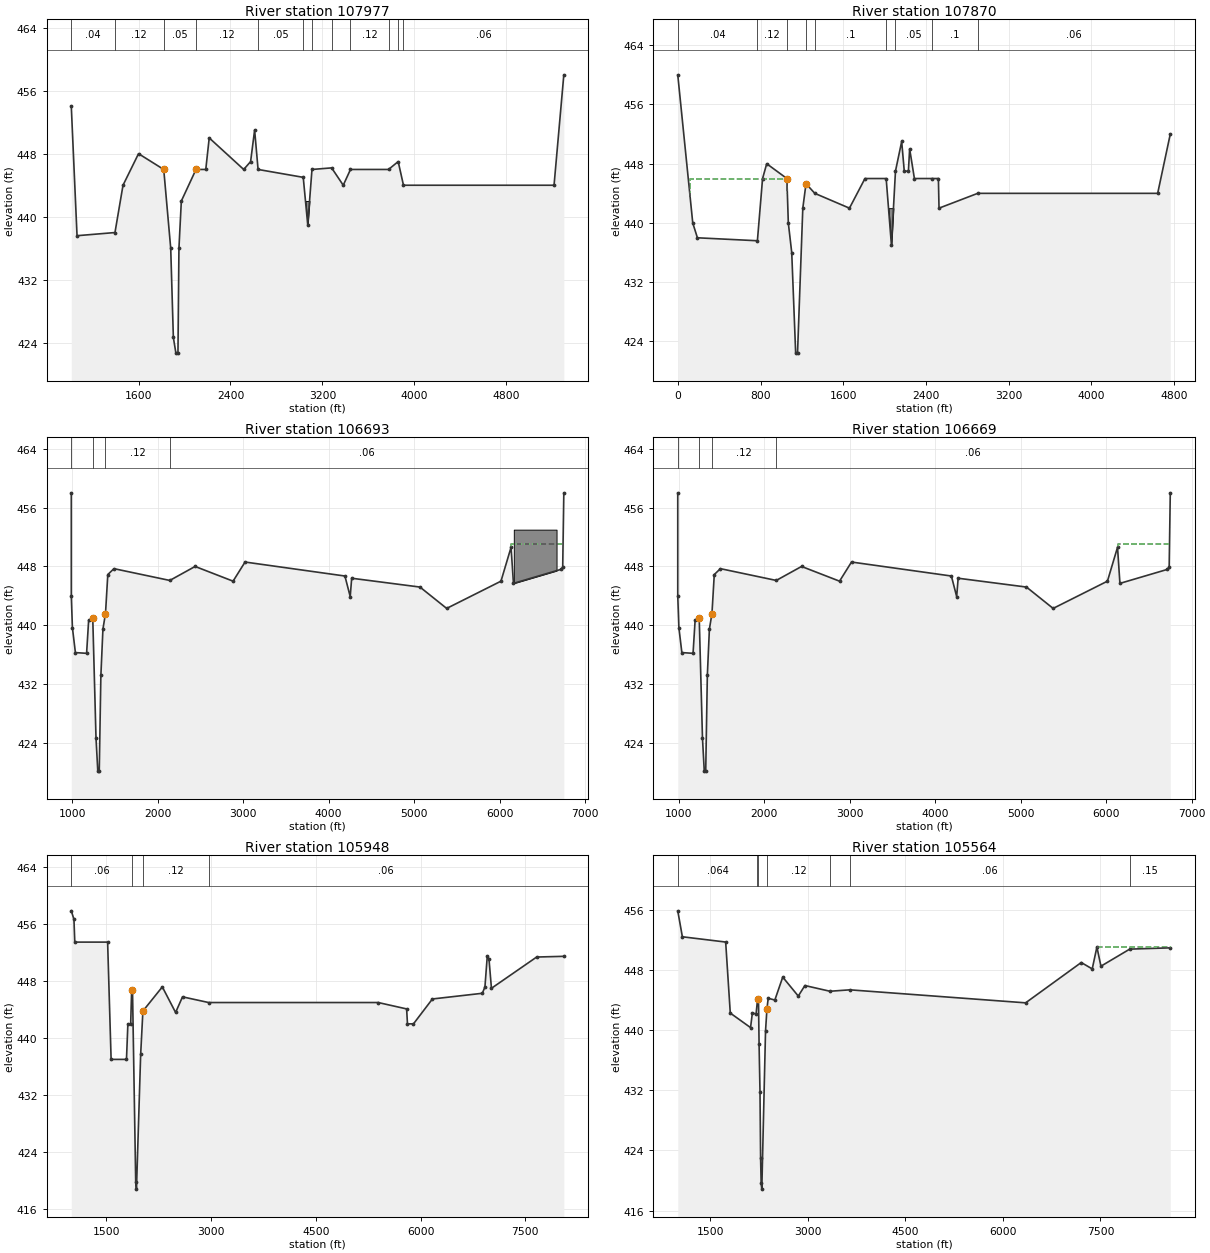
Type RM Length L Ch R = 1 ,107977  ,37,107,201
BEGIN DESCRIPTION:
This cross section corresponds to cross section 107964 of the non-georeferenced CDC model which was the source of this model.
FIS SECTION RECODED BY OEI, Added dense shrubs b/w fairways, mounds b/s 6 & 8
END DESCRIPTION:
XS GIS Cut Line= 6
2445808.357103357046657.124288962445775.275148517046645.97208031
2445068.484895417046738.446960972444833.605115837046686.63210396
2442716.03290743 7046775.21001082441539.11334527 7046806.0485318
#Sta/Elev= 30
    1015     454    1065   437.6    1395     438    1465     444    1600     448
  1819.3     446    1880     436    1903   424.7    1925  422.71    1943  422.71
  1951.5     436  1972.4     442    2100     446    2185     446    2215     450
    2515     446    2575     447    2610     451    2640     446    3033     445
    3072     439    3109     446    3280   446.2    3381     444    3444     446
    3775     446    3859     447    3905     444    5215     444    5300     458
#Mann= 12 ,-1,0
    1015     .04       0    1395     .12       0  1819.3     .05       0
    2100     .12       0    2640     .05       0    3033     .09       0
    3109     .12       0    3280     .05       0    3444     .12       0
    3775     .05       0    3859      .1       0    3905     .06       0
#XS Ineff= 2 ,-1
    1015  1819.3     446    2100    5300     446
Permanent Ineff=
       F       F
#Block Obstruct= 1 ,-1
    3033    3109     442
Bank Sta=1819.3,2100
XS Rating Curve= 0 ,0
Exp/Cntr=0.3,0.1

Type RM Length L Ch R = 1 ,107870  ,759,1177,557
BEGIN DESCRIPTION:
This cross section corresponds to cross section 107820 of the non-georeferenced CDC model which was the source of this model.
NEW SECTION ADDED BY OEI
---------------------------------------------------------------------
CDC LEW050102-01 Vista Ridge Golf Center
Cross-section 107820 - 109670
Located in ROB.
---------------------------------------------------------------------
END DESCRIPTION:
XS GIS Cut Line= 6
2446120.972947937046749.88591446 2445827.42858757046622.02593397
2445390.500983697046619.73591229 2445120.92442317046650.20566763
2444876.301224687046604.346507392441393.439424017046715.47030088
#Sta/Elev= 30
       0     460     145     440     190     438     770   437.6     820     446
     860     448    1055     446    1069     440    1102     436    1140  422.43
    1158  422.43    1209     442    1240   445.3    1325     444    1660     442
    1810     446    2015     446    2066     437    2105     447    2165     451
    2190     447    2230     447    2242     450    2288     446    2460     446
    2520     446    2526     442    2900     444    4640     444    4762     452
#Mann= 9 ,-1,0
       0     .04       0     770     .12       0    1055     .05       0
    1240     .05       0    1325      .1       0    2015     .09       0
    2105     .05       0    2460      .1       0    2900     .06       0
#XS Ineff= 2 ,-1
     120    1060     446    1240    4762   445.3
Permanent Ineff=
       F       F
#Block Obstruct= 1 ,-1
    2015    2105     442
Bank Sta=1055,1240
XS Rating Curve= 0 ,0
Exp/Cntr=0.3,0.1

Type RM Length L Ch R = 1 ,106693  ,24,24,24
BEGIN DESCRIPTION:
This cross section corresponds to cross section 106700 of the non-georeferenced CDC model which was the source of this model.
Water tank section DS Copied section.
END DESCRIPTION:
XS GIS Cut Line= 5
2446254.662969267046465.101050972445876.386822917045960.52594464
2445562.02557501 7045963.65257882445240.248987597045964.12501881
2440747.161517087045998.48026505
#Sta/Elev= 30
     990     458     990     444    1003   439.7    1038   436.3    1169   436.2
    1193   440.7    1241     441    1279   424.7    1300   420.2    1317   420.2
    1336   433.2    1360   439.5    1390   441.6    1417   446.9    1489   447.7
    2142   446.1    2438     448    2882     446    3022   448.6    4190   446.7
    4252   443.9    4269   446.4    5068   445.2    5380   442.3    6015     446
    6133   450.6    6161   445.7    6716   447.6    6737   447.9    6750     458
#Mann= 4 ,-1,0
     990     .06       0    1241     .05       0    1390     .12       0
    2142     .06       0
#XS Ineff= 3 ,-1
     200    1241     441    1390    1500   441.6    6133    6750     451
Permanent Ineff=
       F       F       F
#Block Obstruct= 1 ,-1
    6165    6665     453
Bank Sta=1241,1390
XS Rating Curve= 0 ,0
Exp/Cntr=0.3,0.1

Type RM Length L Ch R = 1 ,106669  ,850,721,560
BEGIN DESCRIPTION:
This cross section corresponds to cross section 106657 of the non-georeferenced CDC model which was the source of this model.
Water tank section DS
---------------------------------------------------------------------
CDC LEW052401-1 Water Storage Tank
Cross-section 106657 - 107964
Project located in far ROB west of Gun Club road.
---------------------------------------------------------------------
END DESCRIPTION:
XS GIS Cut Line= 3
2446264.197070937046450.406198472445896.118082677045935.09522122
2440769.508913347045970.63287979
#Sta/Elev= 30
     990     458     990     444    1003   439.7    1038   436.3    1169   436.2
    1193   440.7    1241     441    1279   424.7    1300   420.2    1317   420.2
    1336   433.2    1360   439.5    1390   441.6    1417   446.9    1489   447.7
    2142   446.1    2438     448    2882     446    3022   448.6    4190   446.7
    4252   443.9    4269   446.4    5068   445.2    5380   442.3    6015     446
    6133   450.6    6161   445.7    6716   447.6    6737   447.9    6750     458
#Mann= 4 ,-1,0
     990     .06       0    1241     .05       0    1390     .12       0
    2142     .06       0
#XS Ineff= 3 ,-1
     200    1241     441    1390    1500   441.6    6133    6750     451
Permanent Ineff=
       F       F       F
Bank Sta=1241,1390
XS Rating Curve= 0 ,0
Exp/Cntr=0.3,0.1

Type RM Length L Ch R = 1 ,105948  ,434,384,385
BEGIN DESCRIPTION:
This cross section corresponds to cross section 105936 of the non-georeferenced CDC model which was the source of this model.
END DESCRIPTION:
XS GIS Cut Line= 3
2447261.761020667045957.092224462446056.025899357045402.07004055
2440333.456307777045370.96642822
#Sta/Elev= 30
    1000   457.9    1038   456.7    1050   453.5    1520   453.5    1570     437
    1790     437    1810     442    1850     442    1864   446.7    1876   446.8
    1922   419.8    1933  418.75    1993   437.7    2025   443.8    2303   447.2
    2493   443.6    2592   445.8    2966     445    5393     445    5800   444.1
    5812     442    5898     442    6169   445.5    6884   446.3    6921   447.2
    6954   451.5    6979   451.1    7014     447    7661   451.4    8050   451.5
#Mann= 4 ,-1,0
    1000     .06       0    1876     .05       0    2025     .12       0
    2966     .06       0
#XS Ineff= 3 ,-1
    1000    1876   446.8    2025    6954   443.8    6954    8050   451.5
Permanent Ineff=
       F       F       F
Bank Sta=1876,2025
XS Rating Curve= 0 ,0
Exp/Cntr=0.3,0.1

Type RM Length L Ch R = 1 ,105564  ,436,385,385
BEGIN DESCRIPTION:
This cross section corresponds to cross section 105600 of the non-georeferenced CDC model which was the source of this model.
Interpolated cross-section.
END DESCRIPTION:
XS GIS Cut Line= 4
2447693.509501017045711.683266462446421.248922177045163.56658055
2446349.58863243 7045145.66602582440235.841673587045014.70926672
#Sta/Elev= 30
    1000  455.85 1070.85   452.4 1736.83   451.7 1807.68  442.26 2119.41  440.33
 2147.74   442.3 2204.43  442.12 2226.05     444 2241.27  444.18 2250.61   438.1
  2264.6  431.82 2273.93  423.04 2282.69  419.61 2292.59  418.86 2349.85  439.89
 2371.49   442.8 2390.77  444.23    2493  443.99 2614.51  447.04  2853.3  444.52
 2955.22  445.92 3340.26  445.16 3646.38  445.35 6349.51  443.62 7205.06  448.98
  7373.9  448.13 7445.97  451.04 7507.74  448.49 7950.43  450.76 8574.32  450.93
#Mann= 7 ,-1,0
    1000    .064       0 2226.05    .072       0 2241.27     .05       0
 2371.49     .12       0 3340.26    .066       0 3646.38     .06       0
 7950.43     .15       0
#XS Ineff= 3 ,-1
    1000 2241.27  444.18 2371.49 7445.97   442.8 7445.97 8574.32  451.04
Permanent Ineff=
       F       F       F
#Block Obstruct= 2 , 0
       0                    7950       0     458
Bank Sta=2241.27,2371.49
XS Rating Curve= 0 ,0
Exp/Cntr=0.3,0.1

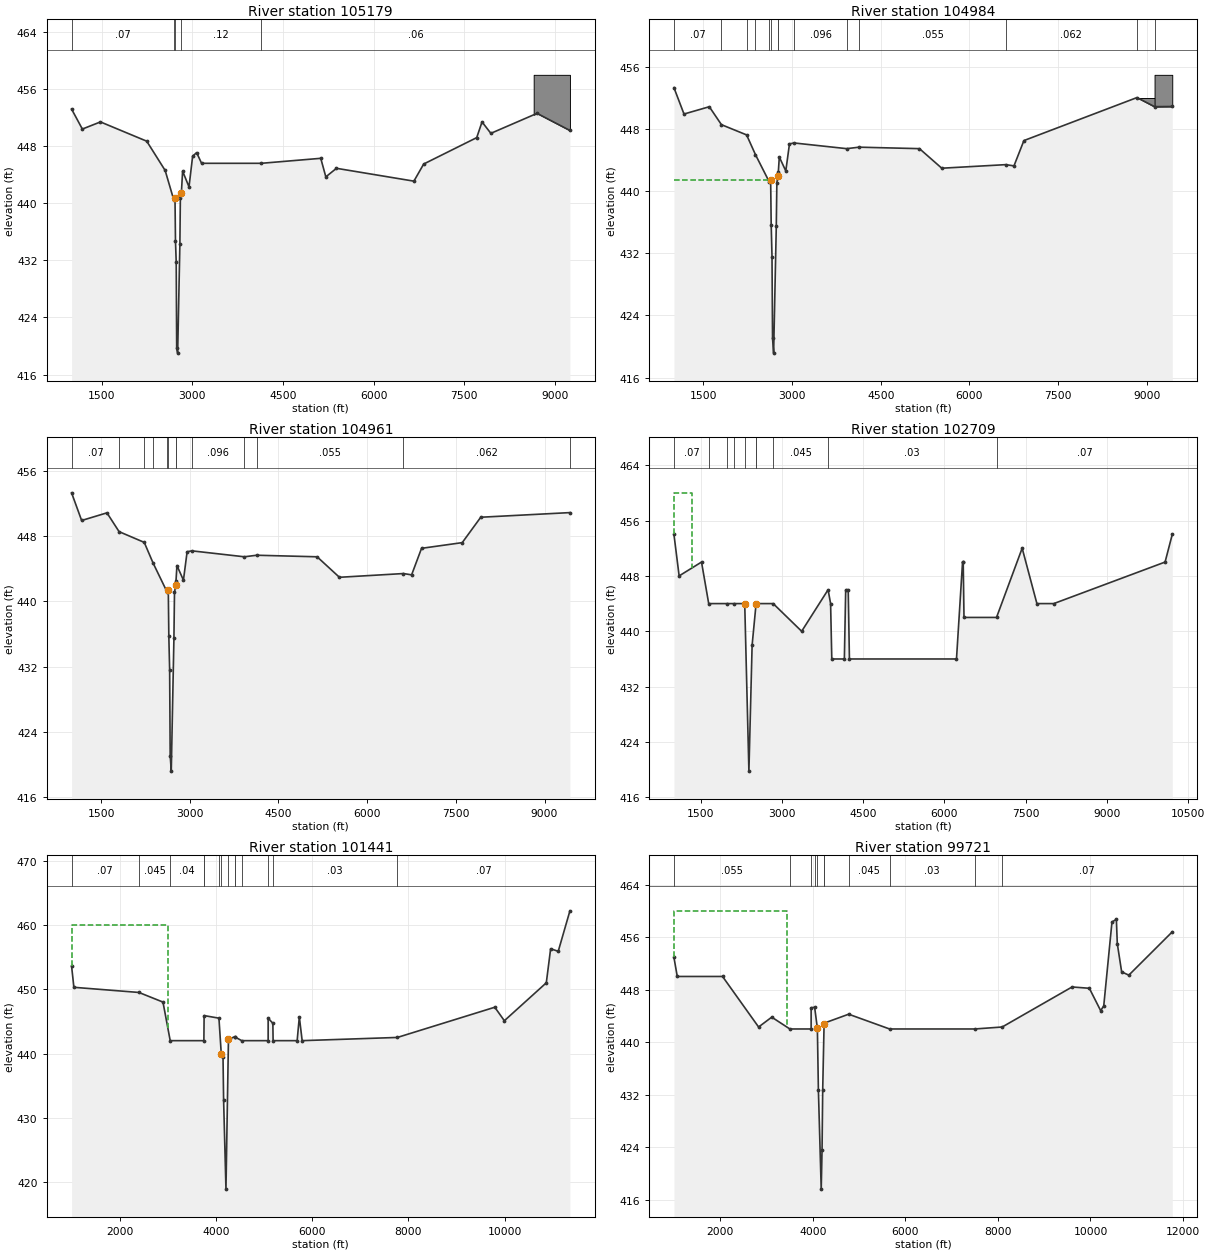
Type RM Length L Ch R = 1 ,105179  ,132,195,97
BEGIN DESCRIPTION:
This cross section corresponds to cross section 105167 of the non-georeferenced CDC model which was the source of this model.
END DESCRIPTION:
XS GIS Cut Line= 3
2448176.333010447045363.731206462446809.859037347044818.43997422
2440036.274159347044554.02285214
#Sta/Elev= 30
    1000   453.2    1178   450.4    1478   451.4    2244   448.7    2549   444.6
    2691   440.5    2712   440.8    2720   434.7    2732   431.8    2740   419.7
    2756     419    2793   434.3    2801   440.8    2818   441.5    2838   444.5
    2944   442.3    3004   446.6    3070   447.1    3152   445.6    4140   445.6
    5125   446.3    5209   443.7    5385   444.9    6667   443.1    6829   445.5
    7707   449.2    7795   451.4    7941   449.8    8706   452.6    9250   450.2
#Mann= 5 ,-1,0
    1000     .07       0    2691      .1       0    2712     .05       0
    2818     .12       0    4140     .06       0
#Block Obstruct= 1 ,-1
    8650    9250     458
Bank Sta=2712,2818
XS Rating Curve= 0 ,0
Exp/Cntr=0.3,0.1

Type RM Length L Ch R = 1 ,104984  ,23,23,23
BEGIN DESCRIPTION:
This cross section corresponds to cross section 104750 of the non-georeferenced CDC model which was the source of this model.
Copy of cross-section 104700.
---------------------------------------------------------------------
CDC COP070199-01 Windsor Estates
Cross-section 104750 - 105600
Located in ROB west of Denton Creek.
---------------------------------------------------------------------
END DESCRIPTION:
XS GIS Cut Line= 4
2448113.084121177045078.379086882447057.470746857044653.08531804
2446982.141501167044628.758923132439775.045022997044387.18558738
#Sta/Elev= 30
 1001.58  453.35 1171.64  449.95 1599.66  450.89 1804.88  448.58 2230.58  447.26
 2380.82  444.71 2617.17  441.16 2637.23   441.4 2646.37   435.7 2660.08  431.59
 2669.21  421.07 2687.48  419.15 2732.44  435.47 2742.16  441.12 2762.81  441.97
 2767.32   442.5 2783.54  444.41 2893.42  442.62 2955.61  446.11  3036.4  446.22
 3923.04  445.49 4133.14  445.68 5154.15  445.49 5531.46  442.97 6614.39  443.43
 6752.52  443.27 6920.44  446.53 8832.78  452.07    9130   450.9 9429.95  450.92
#Mann= 14 ,-1,0
 1001.58     .07       0 1804.88    .076       0 2230.58    .089       0
 2380.82    .096       0 2617.17    .091       0 2637.23     .05       0
 2762.81    .106       0 2767.32    .116       0  3036.4    .096       0
 3923.04    .062       0 4133.14    .055       0 6614.39    .062       0
 8832.78    .025       0    9130     .15       0
#XS Ineff= 2 , 0
       02637.235441.4023 2762.81       0  441.97
Permanent Ineff=
       F       F
#Block Obstruct= 2 ,-1
    8830    9130     452    9130  9429.5     455
Bank Sta=2637.23,2762.81
XS Rating Curve= 0 ,0
Exp/Cntr=0.3,0.1

Type RM Length L Ch R = 1 ,104961  ,1362,2252,998
BEGIN DESCRIPTION:
This cross section corresponds to cross section 104700 of the non-georeferenced CDC model which was the source of this model.
Interpolated cross-section.
END DESCRIPTION:
XS GIS Cut Line= 4
2448109.035572837045045.457892882447078.592751837044629.84028579
2447002.81534433 7044606.01553032439768.890507767044368.21974605
#Sta/Elev= 30
 1001.58  453.35 1171.64  449.95 1599.66  450.89 1804.88  448.58 2230.58  447.26
 2380.82  444.71 2617.17  441.16 2637.23   441.4 2646.37   435.7 2660.08  431.59
 2669.21  421.07 2687.48  419.15 2732.44  435.47 2742.16  441.12 2762.81  441.97
 2767.32   442.5 2783.54  444.41 2893.42  442.62 2955.61  446.11  3036.4  446.22
 3923.04  445.49 4133.14  445.68 5154.15  445.49 5531.46  442.97 6614.39  443.43
 6752.52  443.27 6920.44  446.53 7608.72  447.23 7921.76  450.35 9429.95  450.92
#Mann= 13 ,-1,0
 1001.58     .07       0 1804.88    .076       0 2230.58    .089       0
 2380.82    .096       0 2617.17    .091       0 2637.23     .05       0
 2762.81    .106       0 2767.32    .116       0  3036.4    .096       0
 3923.04    .062       0 4133.14    .055       0 6614.39    .062       0
 9429.95    .062       0
Bank Sta=2637.23,2762.81
XS Rating Curve= 0 ,0
Exp/Cntr=0.3,0.1

Type RM Length L Ch R = 1 ,102709  ,907,1268,605
BEGIN DESCRIPTION:
This cross section corresponds to cross section 102686 of the non-georeferenced CDC model which was the source of this model.
pond 1650-1990, forest 2110-2260,2530-2840
XS 102709 to 97192 retored  to  to 1991 topo to remove CAR 062309-01
END DESCRIPTION:
XS GIS Cut Line= 3
 2449346.20501457044288.79208338 2447922.35189117043690.69715096
2440269.43379802 7043621.4781293
#Sta/Elev= 30
  1008.4     454  1104.3     448  1517.4     450    1650     444    1990     444
    2110     444  2314.8     444    2392   419.8  2451.2     438  2524.8     444
    2530     444    2840     444  3365.7     440  3853.3     446  3899.7     444
  3921.7     436  4153.8     436  4178.4     446  4224.8     446  4247.2     436
  6223.3     436  6335.2     450  6347.4     450  6361.7     442  6962.2     442
  7435.4     452  7707.4     444  8018.6     444   10073     450   10206     454
#Mann= 10 ,-1,0
  1008.4     .07       0    1650     .04       0    1990     .07       0
    2110      .1       0  2314.8     .05       0  2524.8    .045       0
    2530      .1       0    2840    .045       0  3853.3     .03       0
  6962.2     .07       0
#XS Ineff= 2 , 0
       0    1350     460               0
Permanent Ineff=
       F       F
Bank Sta=2314.8,2524.8
XS Rating Curve= 0 ,0
Exp/Cntr=0.3,0.1

Type RM Length L Ch R = 1 ,101441  ,930,1720,870
BEGIN DESCRIPTION:
This cross section corresponds to cross section 101428 of the non-georeferenced CDC model which was the source of this model.
END DESCRIPTION:
XS GIS Cut Line= 4
2450618.600107497042750.521209812447762.271830687042750.52120981
2447354.618118447043107.218002962440395.945027927042927.45786379
#Sta/Elev= 30
    1000   453.6    1048   450.3    2400   449.5    2900     448    3050     442
    3750     442    3755   445.9    4063   445.5    4111     440    4148   439.4
    4160   432.8    4209   418.9    4261   442.2    4387   442.6    4390   442.6
    4537     442    5086     442    5086   445.5    5184   444.7    5189     442
    5689     442    5734   445.7    5793     442    7772   442.5    9797   447.2
    9996   445.1   10868     451   10958   456.3   11116   455.9   11359   462.2
#Mann= 14 ,-1,0
    1000     .07       0    2400    .045       0    3050     .04       0
    3750      .1       0    3755      .1       0    4063      .1       0
    4111     .05       0    4261      .1       0    4387    .045       0
    4390      .1       0    4537     .04       0    5086    .045       0
    5189     .03       0    7772     .07       0
#XS Ineff= 2 , 0
       0    3008     460               0
Permanent Ineff=
       F       F
Bank Sta=4111,4261
XS Rating Curve= 0 ,0
Exp/Cntr=0.3,0.1

Type RM Length L Ch R = 1 ,99721   ,899,823,899
BEGIN DESCRIPTION:
This cross section corresponds to cross section 99708 of the non-georeferenced CDC model which was the source of this model.
END DESCRIPTION:
XS GIS Cut Line= 4
2451043.622879517042242.79223838 2448093.4909845 7042215.4750358
2447634.88002509 7041960.69208082440342.924792777042008.16147405
#Sta/Elev= 30
    1000   452.9    1072     450    2050     450    2829   442.3    3113   443.8
    3505     442    3964     442    3964  445.23    4040   445.3    4099   442.1
    4121   432.7    4182   417.6    4200   423.5    4214   432.7    4244   442.8
    4250   442.9    4775  444.25    5659     442    7500     442    8092   442.3
    9602   448.4    9975   448.2   10219   444.8   10286   445.5   10464   458.3
   10559   458.7   10579     455   10673   450.7   10828   450.2   11767   456.8
#Mann= 11 ,-1,0
    1000    .055       0    3505     .04       0    3964      .1       0
    4040    .055       0    4099     .05       0    4244    .045       0
    4250      .1       0    4775    .045       0    5659     .03       0
    7500     .09       0    8092     .07       0
#XS Ineff= 2 , 0
       0    3453     460               0
Permanent Ineff=
       F       F
Bank Sta=4099,4244
XS Rating Curve= 0 ,0
Exp/Cntr=0.3,0.1

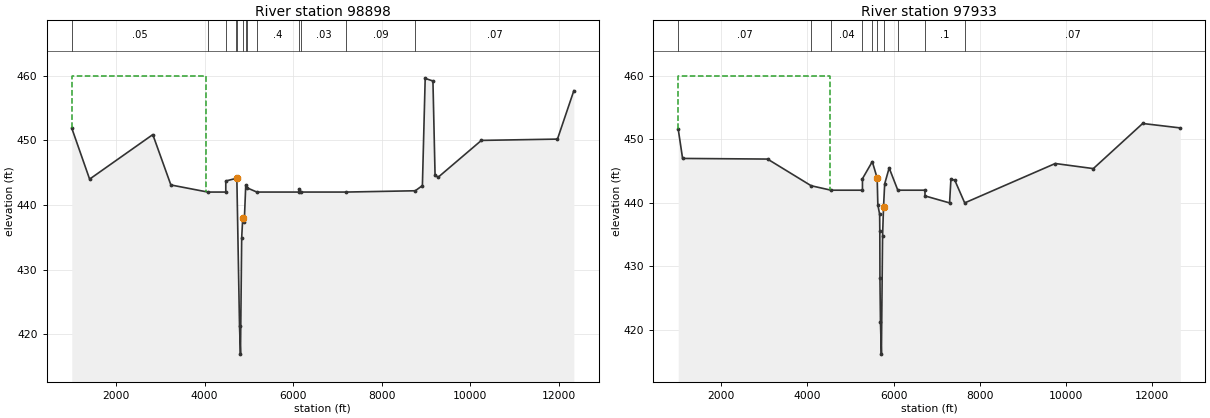
Type RM Length L Ch R = 1 ,98898   ,920,965,900
BEGIN DESCRIPTION:
This cross section corresponds to cross section 98884 of the non-georeferenced CDC model which was the source of this model.
END DESCRIPTION:
XS GIS Cut Line= 2
2451793.58496225 7041336.08112532440455.763149777041272.52350964
#Sta/Elev= 30
    1000   451.9    1403     444    2830   450.9    3238   443.1    4070     442
    4478     442    4478  443.71    4700   444.1    4728   444.1    4788   421.3
    4810   416.9    4837   434.9    4861     438    4895   437.3    4929   443.1
    4960  442.65    5179     442    6130     442    6130   442.4    6184     442
    7200     442    8757   442.2    8918     443    8981   459.6    9156   459.2
    9204   444.6    9275   444.3   10250     450   11968   450.2   12338   457.7
#Mann= 13 ,-1,0
    1000     .05       0    4070     .04       0    4478      .1       0
    4700     .05       0    4728    .045       0    4861      .1       0
    4929    .045       0    4960      .1       0    5179      .4       0
    6130    .045       0    6184     .03       0    7200     .09       0
    8757     .07       0
#XS Ineff= 2 , 0
       0    4030     460               0
Permanent Ineff=
       F       F
Bank Sta=4728,4861
XS Rating Curve= 0 ,0
Exp/Cntr=0.3,0.1

Type RM Length L Ch R = 1 ,97933   ,701,742,701
BEGIN DESCRIPTION:
This cross section corresponds to cross section 97919 of the non-georeferenced CDC model which was the source of this model.
END DESCRIPTION:
XS GIS Cut Line= 2
2452408.071922247040392.980977392440749.103770437040420.18794397
#Sta/Elev= 30
    1000   451.6    1101     447    3074   446.9    4087   442.7    4547     442
    5278     442    5278  443.81    5506   446.5    5620   443.9    5635   439.7
    5677   438.2    5681   435.5    5684   428.2    5696   421.2    5718   416.2
    5745   434.8    5767   439.3    5794     443    5898   445.5    6099     442
    6730     442    6730   441.1    7301     440    7332   443.7    7420   443.6
    7652     440    9755   446.2   10639   445.4   11785   452.5   12659   451.8
#Mann= 10 ,-1,0
    1000     .07       0    4087     .05       0    4547     .04       0
    5278      .1       0    5506      .1       0    5620     .05       0
    5767      .1       0    6099     .04       0    6730      .1       0
    7652     .07       0
#XS Ineff= 2 , 0
       0    4517     460               0
Permanent Ineff=
       F       F
Bank Sta=5620,5767
XS Rating Curve= 0 ,0
Exp/Cntr=0.3,0.1

River Reach=Elm Fork        ,PGBT split west
Reach XY= 30
      2447850.52      7040050.17      2447851.28      7039823.18
       2447765.5      7039618.88      2447543.86      7039386.42
      2447283.34      7039244.82      2447041.73      7039191.65
      2446794.53      7039201.31      2446590.32      7039267.69
      2446235.77      7039488.35      2446154.21      7039493.36
      2446079.96      7039459.22       2446023.8      7039374.59
      2446021.19      7039292.91      2446232.21      7038946.89
       2446253.3       7038838.4      2446235.52      7038729.33
      2446162.43      7038612.58      2445606.85      7038140.69
       2445524.8      7037970.04       2445570.8       7037501.1
      2445738.38      7037223.01      2445853.15       7036823.6
       2445814.6      7036141.12      2445839.38      7035433.75
       2445974.7      7034782.32      2446080.86      7034582.01
      2446241.32      7034359.76      2446941.68      7033458.66
      2447261.03       7033097.4      2447356.93      7032903.31

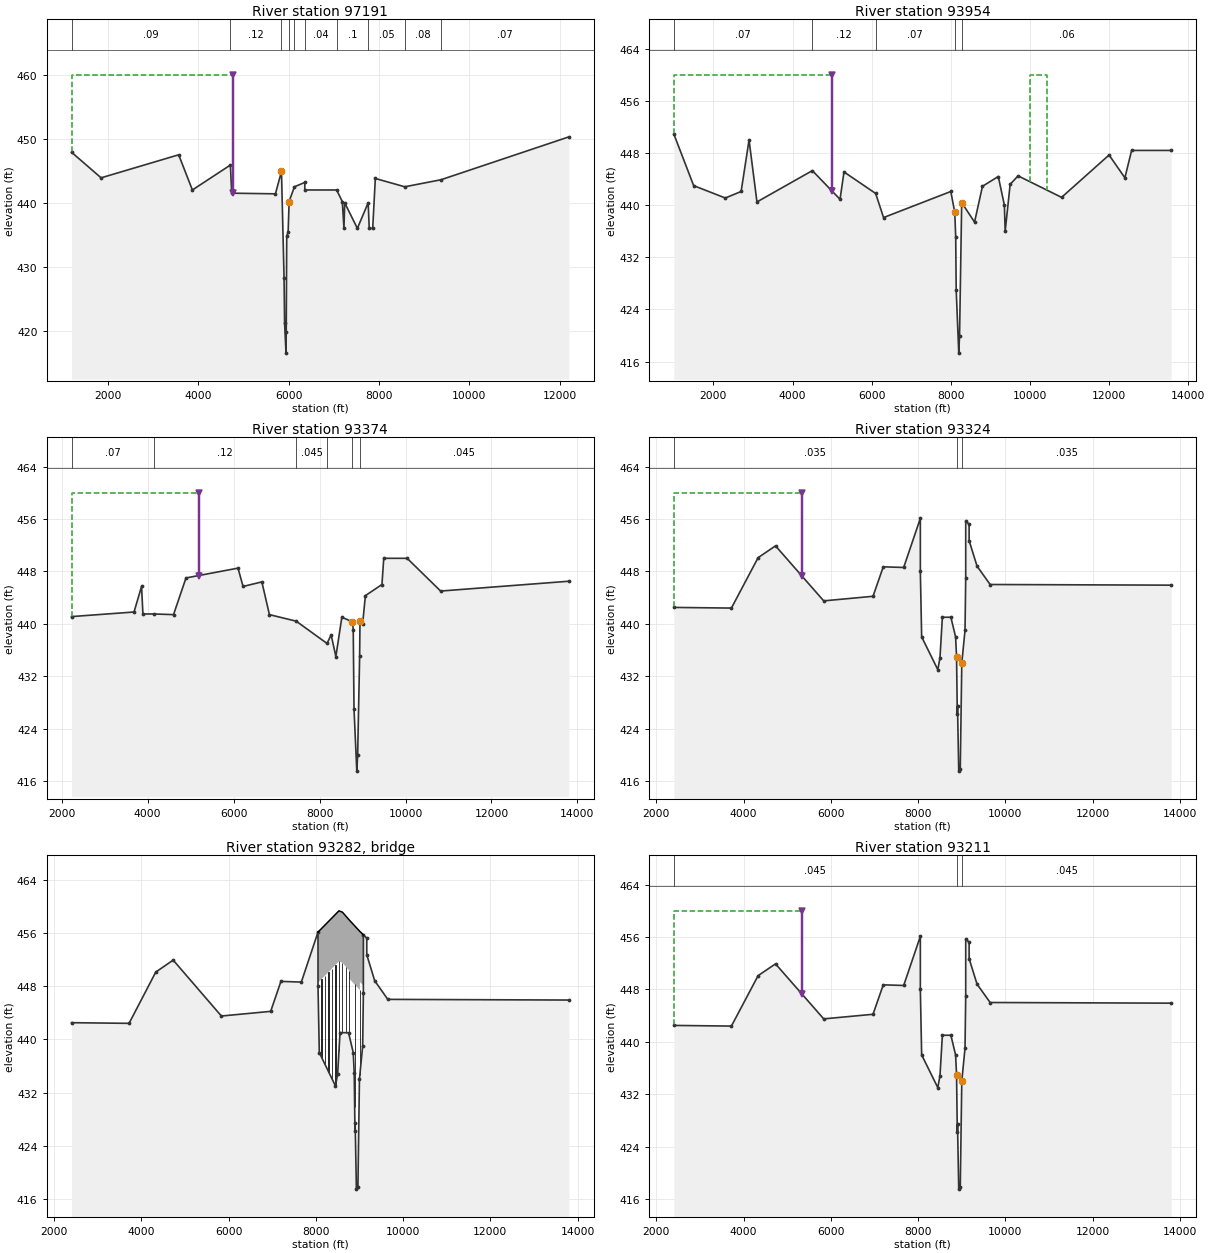
Type RM Length L Ch R = 1 ,97191   ,2199,3237,1350
BEGIN DESCRIPTION:
This cross section corresponds to cross section 97178 of the non-georeferenced CDC model which was the source of this model.
END DESCRIPTION:
XS GIS Cut Line= 2
2452539.652695837039715.174918292441539.700942527039682.66481271
#Sta/Elev= 30
    1200   447.9    1854   443.9    3570   447.5    3873     442    4714   445.9
    4743   441.5    5710   441.4    5844   444.9    5901   428.2    5913   421.2
    5944   416.5    5949   419.8    5960   434.8    5991   435.4    6013   440.2
    6130   442.5    6360  443.18    6360     442 7064.45     442    7189   440.2
  7225.9     436  7241.9     440  7522.7     436  7761.2     440  7785.3     436
  7861.8     436  7919.6   443.8    8571   442.5    9372   443.6   12200   450.3
#Mann= 10 ,-1,0
    1200     .09       0    4714     .12       0    5844     .05       0
    6013    .045       0    6130      .1       0    6360     .04       0
 7064.45      .1       0  7761.2     .05       0    8571     .08       0
    9372     .07       0
Levee=-1,4780,460,0,,,,
#XS Ineff= 2 , 0
       0    4780     460               0
Permanent Ineff=
       F       F
Bank Sta=5844,6013
XS Rating Curve= 0 ,0
Exp/Cntr=0.3,0.1

Type RM Length L Ch R = 1 ,93954   ,649,580,459
BEGIN DESCRIPTION:
This cross section corresponds to cross section 93940 of the non-georeferenced CDC model which was the source of this model.
--------------------------------------------
CDC CAR062309-1 WTP Pre-Sedimentation Basins
Cross-section 93940 - 105167
--------------------------------------------
Bridge blocked ROB as part of the project for SPF only.
No other impacts to 100-year or SPF conveyance models.
--------------------------------------------
CDC Cop 050812-01 River Oaks Assisted Living and Memory Care
Cross-section 93359 - 93940
Located in ROB.
--------------------------------------------
END DESCRIPTION:
XS GIS Cut Line= 6
  2452796.764058     7039374.541 2448190.2778644     7039329.194
 2447158.7989563     7038418.323 2443184.5719966     7038479.048
 2442031.7429374     7039465.8252440936.74876567 7039474.2485852
#Sta/Elev= 30
    1000   450.9    1500     443    2300   441.1    2700   442.1    2900     450
    3100   440.5    4500   445.3    5200   440.9    5300   445.1    6100   441.8
    6300   438.1    8000   442.1    8100   438.9    8124   435.1    8136     427
    8201   417.3    8221     420    8275   440.4    8600   437.4    8800   442.9
    9200   444.4    9354     440    9374     436    9500   443.2    9700   444.5
   10800   441.2   12000   447.7   12400   444.2   12570   448.4   13570   448.4
#Mann= 5 ,-1,0
    1000     .07       0    4500     .12       0    6100     .07       0
    8100     .05       0    8275     .06       0
Levee=-1,5000,460,0,,,,
#XS Ineff= 2 ,-1
    1000    5000     460   10000   10426     460
Permanent Ineff=
       F       F
Bank Sta=8100,8275
XS Rating Curve= 0 ,0
Exp/Cntr=0.3,0.1

Type RM Length L Ch R = 1 ,93374   ,50,50,50
BEGIN DESCRIPTION:
This cross section corresponds to cross section 93359 of the non-georeferenced CDC model which was the source of this model.
END DESCRIPTION:
XS GIS Cut Line= 6
2451825.857535517039057.255302382448551.367037277039018.65006463
2446565.057033517037943.830035812443827.059884857038005.64520088
2442244.274008427039096.973070712441008.350427037039398.64766707
#Sta/Elev= 30
    2230   441.1    3684   441.8    3859   445.7    3891   441.5    4146   441.5
    4603   441.4    4893     447    6103   448.5    6221   445.7    6658   446.4
    6834   441.4    7457   440.4    8174     437    8270   438.3    8380     435
    8519     441    8766   440.3    8784   439.1    8802     427    8867   417.5
    8887     420    8933   435.1    8941   440.4    9002     440    9067   444.3
    9452     446    9494     450   10038     450   10817     445   13800   446.5
#Mann= 6 ,-1,0
    2230     .07       0    4146     .12       0    7457    .045       0
    8174    .035       0    8766     .05       0    8941    .045       0
Levee=-1,5190,460,0,,,,
#XS Ineff= 2 , 0
       0    5190     460               0
Permanent Ineff=
       F       F
Bank Sta=8766,8941
XS Rating Curve= 0 ,0
Exp/Cntr=0.3,0.1

Type RM Length L Ch R = 1 ,93324   ,113,113,113
BEGIN DESCRIPTION:
This cross section corresponds to cross section 93297 of the non-georeferenced CDC model which was the source of this model.
Upstream bounding cross-section for Sandy Lake Road bridge
END DESCRIPTION:
XS GIS Cut Line= 6
2451734.592626187038998.613031222448786.985660497038967.59209588
2446901.668565017037959.034729792444298.008746097037945.72931021
2443344.115968857038045.839674292440940.74752348 7039248.2781476
#Sta/Elev= 30
    2400   442.5    3719   442.4    4331   450.1    4730   451.9    5835   443.5
    6965   444.2    7200   448.7    7668   448.6    8050   456.1    8050     448
    8080     438    8450     433    8500   434.8    8555     441    8750     441
    8858     438    8880     435    8897   426.3    8902   427.4    8930   417.5
    8965   417.8    9000     434    9074     439    9090     447    9090   455.7
    9168   455.2    9168   452.7    9350   448.8    9650     446   13800   445.9
#Mann= 3 ,0,0
    2400    .035       0    8880     .03       0    9000    .035       0
Levee=-1,5329,460,0,,,,
#XS Ineff= 2 , 0
       0    5329     460               0
Permanent Ineff=
       F       F
Bank Sta=8880,9000
XS Rating Curve= 0 ,0
Exp/Cntr=0.3,0.1

Type RM Length L Ch R = 3 ,93282   ,,,
BEGIN DESCRIPTION:
Sandy Lake Road
Note:  Bridge and roadway modeled from plans dated Dec. 1996 and stamped Dec. 1997.
END DESCRIPTION:
Node Name=Sandy Lake Road
Bridge Culvert--1,0,-1,-1, 0
Deck Dist Width WeirC Skew NumUp NumDn MinLoCord MaxHiCord MaxSubmerge Is_Ogee
1,83,2.6,0, 8, 8, , , 0.95, 0, ,,,
    8050    8530    8610    8770    8770    9010    9010    9090
   456.1   459.3   459.1   457.9   457.9   456.2   456.2   455.7
   448.5   451.7   451.5   450.3   449.1   447.4   448.6   448.1
    8050    8530    8610    8770    8770    9010    9010    9090
   456.1   459.3   459.1   457.9   457.9   456.2   456.2   455.7
   448.5   451.7   451.5   450.3   449.1   447.4   448.6   448.1
Pier Skew, UpSta & Num, DnSta & Num=  ,8130, 2 ,8130, 2 , 0 , 0 , 0 ,,
     2.5     2.5
     425     452
     2.5     2.5
     425     452
Pier Skew, UpSta & Num, DnSta & Num=  ,8210, 2 ,8210, 2 , 0 , 0 , 0 ,,
     2.5     2.5
     425     452
     2.5     2.5
     425     452
Pier Skew, UpSta & Num, DnSta & Num=  ,8290, 2 ,8290, 2 , 0 , 0 , 0 ,,
     2.5     2.5
     425     452
     2.5     2.5
     425     452
Pier Skew, UpSta & Num, DnSta & Num=  ,8370, 2 ,8370, 2 , 0 , 0 , 0 ,,
     2.5     2.5
     425     452
     2.5     2.5
     425     452
Pier Skew, UpSta & Num, DnSta & Num=  ,8450, 2 ,8450, 2 , 0 , 0 , 0 ,,
     2.5     2.5
     425     452
     2.5     2.5
     425     452
Pier Skew, UpSta & Num, DnSta & Num=  ,8530, 2 ,8530, 2 , 0 , 0 , 0 ,,
     2.5     2.5
     425     453
     2.5     2.5
     425     453
Pier Skew, UpSta & Num, DnSta & Num=  ,8610, 2 ,8610, 2 , 0 , 0 , 0 ,,
     2.5     2.5
     425     453
     2.5     2.5
     425     453
Pier Skew, UpSta & Num, DnSta & Num=  ,8690, 2 ,8690, 2 , 0 , 0 , 0 ,,
     2.5     2.5
     425     452
     2.5     2.5
     425     452
Pier Skew, UpSta & Num, DnSta & Num=  ,8770, 2 ,8770, 2 , 0 , 0 , 0 ,,
       3       3
     425     452
       3       3
     425     452
Pier Skew, UpSta & Num, DnSta & Num=  ,8890, 2 ,8890, 2 , 0 , 0 , 0 ,,
       3       3
     425     452
       3       3
     425     452
Pier Skew, UpSta & Num, DnSta & Num=  ,9010, 2 ,9010, 2 , 0 , 0 , 0 ,,
       3       3
     425     452
       3       3
     425     452
BR Coef= 1 , 0 , 0 ,1.05, 0 ,,,0.8,-1,0.5,1,
WSPro=,,,, 1 ,,,, 0 ,,,, 0 ,,,,-1 ,-1 ,-1 , 0 , 0 , 0 , 0 , 0
BC Design=,, 0 ,, 0 ,,,,,,
BC HTab HWMax=456.1
BC Use User HTab Curves=0
BC User HTab FreeFlow(D)= 0

Type RM Length L Ch R = 1 ,93211   ,2,3,4
BEGIN DESCRIPTION:
This cross section corresponds to cross section 93212 of the non-georeferenced CDC model which was the source of this model.
Downstream bounding cross-section for Sandy Lake Road bridge
END DESCRIPTION:
XS GIS Cut Line= 6
2451700.19735375 7038954.69809282448520.069527697038883.64377296
2447597.799390587038109.242434642446642.141196947037819.29157096
2443907.252637837037866.266214552440736.861069247038575.79107872
#Sta/Elev= 30
    2400   442.5    3719   442.4    4331   450.1    4730   451.9    5835   443.5
    6965   444.2    7200   448.7    7668   448.6    8050   456.1    8050     448
    8080     438    8450     433    8500   434.8    8555     441    8750     441
    8858     438    8880     435    8897   426.3    8902   427.4    8930   417.5
    8965   417.8    9000     434    9074     439    9090     447    9090   455.7
    9168   455.2    9168   452.7    9350   448.8    9650     446   13800   445.9
#Mann= 3 ,0,0
    2400    .045       0    8880     .05       0    9000    .045       0
Levee=-1,5329,460,0,,,,
#XS Ineff= 2 , 0
       0    5329     460               0
Permanent Ineff=
       F       F
Bank Sta=8880,9000
XS Rating Curve= 0 ,0
Exp/Cntr=0.3,0.1