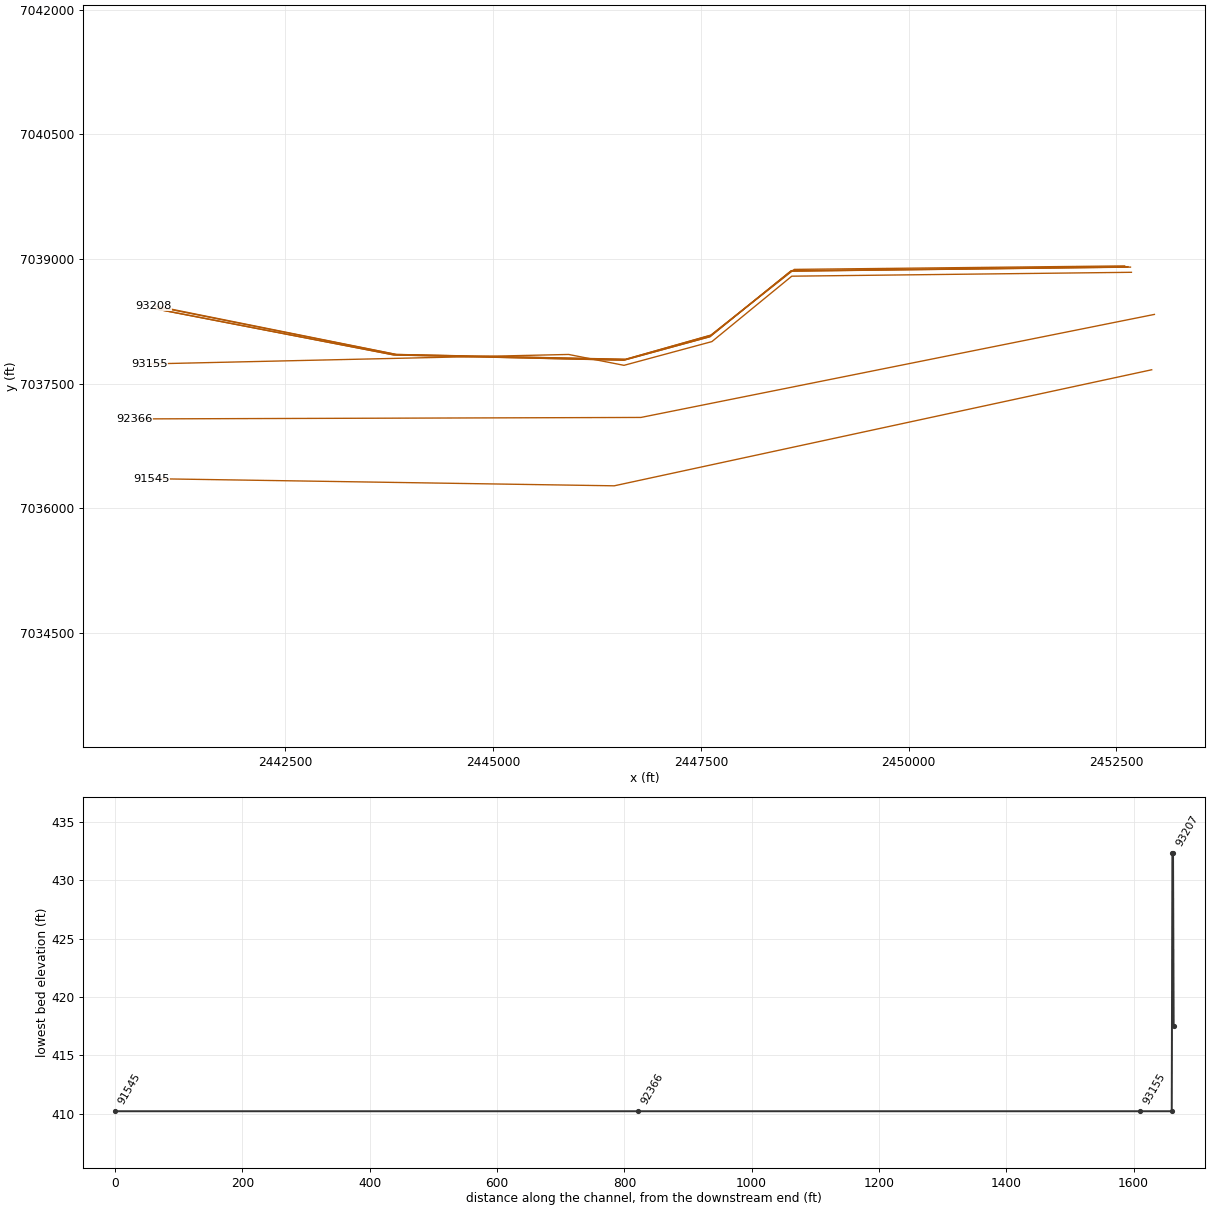
HEC-RAS study CDC_Consolidated_Model.prj: Upper Trinity CDC Consolidated Model

--- CDC_Consolidated_Model.g02 (geometry) --- (continued)

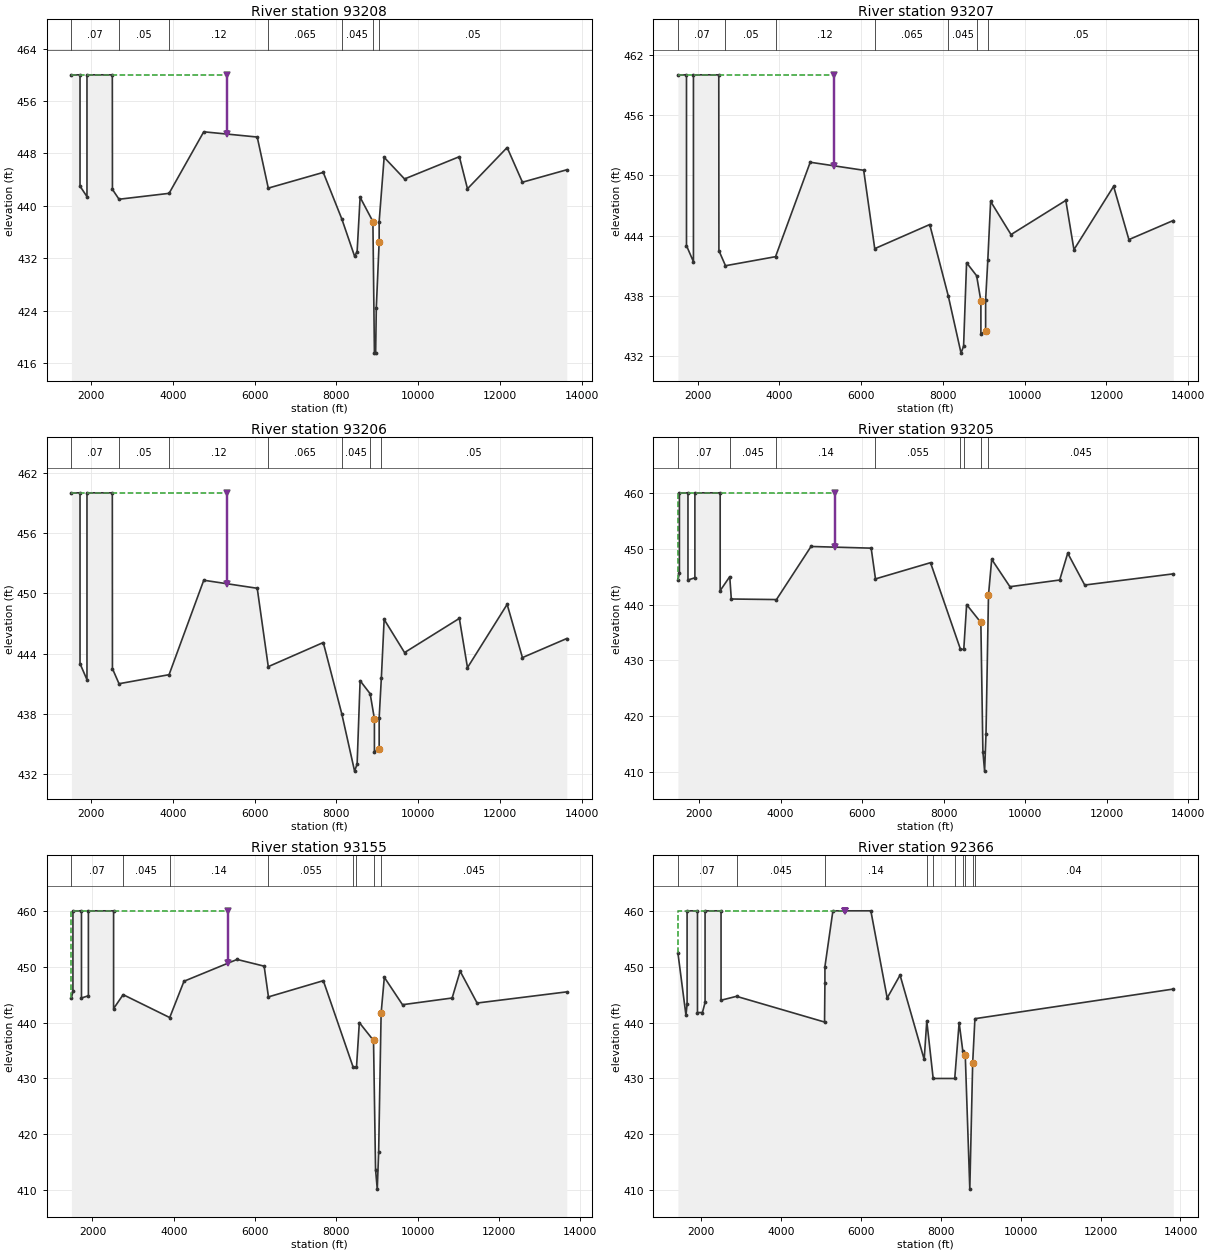
Type RM Length L Ch R = 1 ,93208   ,1,1,1
BEGIN DESCRIPTION:
This cross section corresponds to cross section 93197 of the non-georeferenced CDC model which was the source of this model.
END DESCRIPTION:
XS GIS Cut Line= 6
2452600.490828757038917.960305382448624.117547937038876.03912938
2447622.075260677038085.549240542446594.051726167037793.92941697
2443835.875484027037852.248854132440907.53596965  7038441.053893
#Sta/Elev= 30
    1520     460    1730     460    1730     443    1900   441.4    1900     460
    2520     460    2523   442.5    2684     441    3908   441.9    4756   451.3
    6064   450.5    6334   442.7    7679   445.1    8132     438    8445   432.3
    8507     433    8580   441.3    8893   437.6    8930   417.5    8960   417.5
    8976   424.4    9046   434.5    9046   437.6    9168   447.4    9667   444.1
   11007   447.5   11206   442.6   12176   448.9   12550   443.6   13635   445.5
#Mann= 7 ,-1,0
    1520     .07       0    2684     .05       0    3908     .12       0
    6334    .065       0    8132    .045       0    8893     .05       0
    9046     .05       0
Levee=-1,5329,460,0,,,,
#XS Ineff= 2 , 0
       0    5329     460               0
Permanent Ineff=
       F       F
Bank Sta=8893,9046
XS Rating Curve= 0 ,0
Exp/Cntr=0.3,0.1

Type RM Length L Ch R = 1 ,93207   ,1,1,1
BEGIN DESCRIPTION:
This cross section corresponds to cross section 93196 of the non-georeferenced CDC model which was the source of this model.
END DESCRIPTION:
XS GIS Cut Line= 6
2452641.390353267038908.900284132448592.968660097038861.20648189
2447619.803611677038082.320244392446590.514987837037792.19451229
2443830.769195027037851.319065972440941.944247077038428.13162729
#Sta/Elev= 30
    1520     460    1730     460    1730     443    1900   441.4    1900     460
    2520     460    2523   442.5    2684     441    3908   441.9    4756   451.3
    6064   450.5    6334   442.7    7679   445.1    8132     438    8445   432.3
    8507     433    8580   441.3    8826     440    8930   437.5    8930   434.2
    9046   434.5    9046   437.6    9100   441.6    9168   447.4    9667   444.1
   11007   447.5   11206   442.6   12176   448.9   12550   443.6   13635   445.5
#Mann= 7 ,-1,0
    1520     .07       0    2684     .05       0    3908     .12       0
    6334    .065       0    8132    .045       0    8826     .02       0
    9100     .05       0
Levee=-1,5329,460,0,,,,
#XS Ineff= 2 , 0
       0    5329     460               0
Permanent Ineff=
       F       F
Bank Sta=8930,9046
XS Rating Curve= 0 ,0
Exp/Cntr=0.3,0.1

Type RM Length L Ch R = 1 ,93206   ,1,1,1
BEGIN DESCRIPTION:
This cross section corresponds to cross section 93191 of the non-georeferenced CDC model which was the source of this model.
END DESCRIPTION:
XS GIS Cut Line= 6
2452633.708610097038904.114532552448582.513956587038855.67696539
2447608.631061857038066.236943222446572.952030847037783.50916222
2443805.37685734 7037846.64322232440933.827626397038401.55917062
#Sta/Elev= 30
    1520     460    1730     460    1730     443    1900   441.4    1900     460
    2520     460    2523   442.5    2684     441    3908   441.9    4756   451.3
    6064   450.5    6334   442.7    7679   445.1    8132     438    8445   432.3
    8507     433    8580   441.3    8826     440    8930   437.5    8930   434.2
    9046   434.5    9046   437.6    9100   441.6    9168   447.4    9667   444.1
   11007   447.5   11206   442.6   12176   448.9   12550   443.6   13635   445.5
#Mann= 7 ,-1,0
    1520     .07       0    2684     .05       0    3908     .12       0
    6334    .065       0    8132    .045       0    8826     .02       0
    9100     .05       0
Levee=-1,5329,460,0,,,,
#XS Ineff= 2 , 0
       0    5329     460               0
Permanent Ineff=
       F       F
Bank Sta=8930,9046
XS Rating Curve= 0 ,0
Exp/Cntr=0.3,0.1

Type RM Length L Ch R = 1 ,93205   ,50,50,50
BEGIN DESCRIPTION:
This cross section corresponds to cross section 93190 of the non-georeferenced CDC model which was the source of this model.
END DESCRIPTION:
XS GIS Cut Line= 6
   2452670.74636   7038903.30167     2448582.553     7038854.674
      2447608.67     7038065.234     2446572.991     7037782.506
     2443805.416     7037845.6412440933.865646337038400.55714905
#Sta/Elev= 30
    1483   444.4    1520   445.6    1520     460    1730     460    1730   444.4
    1900   444.8    1900     460    2520     460    2520   442.5    2755     445
    2793     441    3901   440.9    4749   450.4    6224   450.1    6330   444.6
    7680   447.5    8415     432    8496     432    8566     440    8915   436.8
    8965   413.7    9007   410.2    9041   416.8    9102   441.7    9181   448.1
    9628   443.2   10849   444.4   11046   449.2   11463   443.5   13635   445.5
#Mann= 8 ,-1,0
    1483     .07       0    2755    .045       0    3901     .14       0
    6330    .055       0    8415    .035       0    8496     .12       0
    8915     .05       0    9102    .045       0
Levee=-1,5329,460,0,,,,
#XS Ineff= 2 , 0
       0    5329     460               0
Permanent Ineff=
       F       F
Bank Sta=8915,9102
XS Rating Curve= 0 ,0
Exp/Cntr=0.3,0.1

Type RM Length L Ch R = 1 ,93155   ,759,789,739
BEGIN DESCRIPTION:
This cross section corresponds to cross section 93141 of the non-georeferenced CDC model which was the source of this model.
END DESCRIPTION:
XS GIS Cut Line= 6
 2452682.0648126 7038840.95028882448594.03788367 7038794.2240043
2447632.440069357038006.71606489  2446574.4408737037721.01223996
2445907.796865087037851.96014079 2440858.56340847037737.79077835
#Sta/Elev= 30
    1483   444.4    1520   445.6    1520     460    1730     460    1730   444.4
    1900   444.8    1900     460    2520     460    2520   442.5    2755     445
    3901   440.9    4252   447.4    5558   451.3    6224   450.1    6330   444.6
    7680   447.5    8415     432    8496     432    8566     440    8915   436.8
    8965   413.7    9007   410.2    9041   416.8    9102   441.7    9181   448.1
    9628   443.2   10849   444.4   11046   449.2   11463   443.5   13670   445.5
#Mann= 8 ,-1,0
    1483     .07       0    2755    .045       0    3901     .14       0
    6330    .055       0    8415    .035       0    8496     .12       0
    8915     .05       0    9102    .045       0
Levee=-1,5329,460,0,,,,
#XS Ineff= 2 , 0
       0    5329     460               0
Permanent Ineff=
       F       F
Bank Sta=8915,9102
XS Rating Curve= 0 ,0
Exp/Cntr=0.3,0.1

Type RM Length L Ch R = 1 ,92366   ,820,821,820
BEGIN DESCRIPTION:
This cross section corresponds to cross section 92351 of the non-georeferenced CDC model which was the source of this model.
END DESCRIPTION:
XS GIS Cut Line= 4
2452958.679744937038334.056289462446778.237053337037093.70312713
2441681.935894257037078.872448132440681.94012853 7037075.9623736
#Sta/Elev= 30
    1420   452.5    1622   441.3    1650   443.3    1650     460    1910     460
    1910   441.8    2034   441.8    2100   443.6    2100     460    2500     460
    2500     444    2887   444.7    5091   440.1    5100     447    5100     450
    5300     460    6250     460    6659   444.4    6981   448.5    7585   433.4
    7650   440.3    7810     430    8350     430    8460     440    8550     435
    8613   434.2    8727   410.2    8799   432.8    8855   440.7   13820     446
#Mann= 10 ,-1,0
    1420     .07       0    2887    .045       0    5100     .14       0
    7650     .05       0    7810     .03       0    8350     .05       0
    8550     .14       0    8613     .05       0    8799     .14       0
    8855     .04       0
Levee=-1,5608,460,0,,,,
#XS Ineff= 2 , 0
       0    5608     460               0
Permanent Ineff=
       F       F
Bank Sta=8613,8799
XS Rating Curve= 0 ,0
Exp/Cntr=0.3,0.1

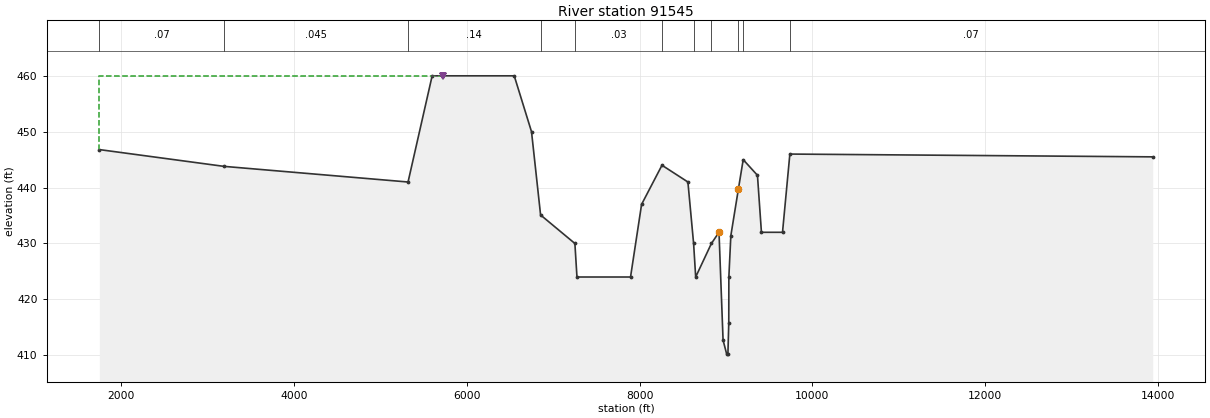
Type RM Length L Ch R = 1 ,91545   ,1000,998,1000
BEGIN DESCRIPTION:
This cross section corresponds to cross section 91530 of the non-georeferenced CDC model which was the source of this model.
END DESCRIPTION:
XS GIS Cut Line= 4
2452926.00067642 7037667.63373782446457.170110177036270.74315888
2441883.650057767036341.302400962440883.769044657036356.72834108
#Sta/Elev= 30
    1748   446.8    3190   443.8    5321     441    5600     460    6550     460
    6750     450    6855   435.1    7252     430    7276     424    7896     424
    8024     437    8260     444    8560     441    8626     430    8650     424
    8832     430    8920     432    8967   412.7    9009   410.2    9023   410.2
    9033   415.8    9034     424    9057   431.4    9145   439.8    9200     445
    9365   442.2    9411     432    9655     432    9740     446   13940   445.5
#Mann= 11 ,-1,0
    1748     .07       0    3190    .045       0    5321     .14       0
    6855    .035       0    7252     .03       0    8260    .045       0
    8626     .03       0    8832     .05       0    9145     .14       0
    9200    .035       0    9740     .07       0
Levee=-1,5730,460,0,,,,
#XS Ineff= 2 , 0
       0    5730     460               0
Permanent Ineff=
       F       F
Bank Sta=8920,9145
XS Rating Curve= 0 ,0
Exp/Cntr=0.3,0.1