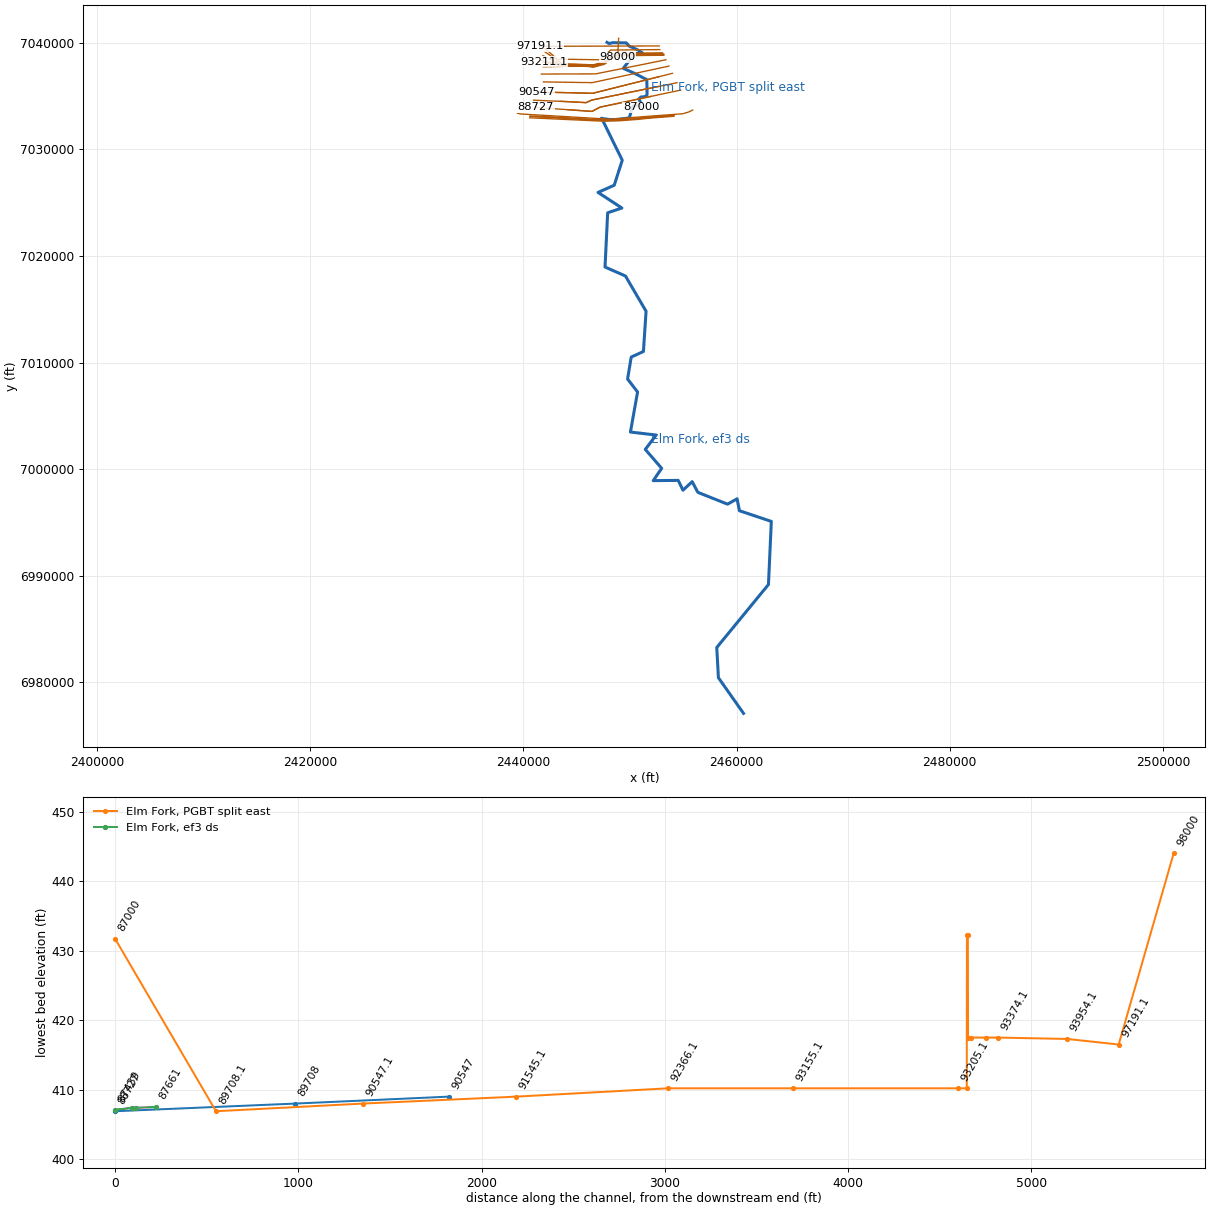
HEC-RAS study CDC_Consolidated_Model.prj: Upper Trinity CDC Consolidated Model

--- CDC_Consolidated_Model.g02 (geometry) --- (continued)

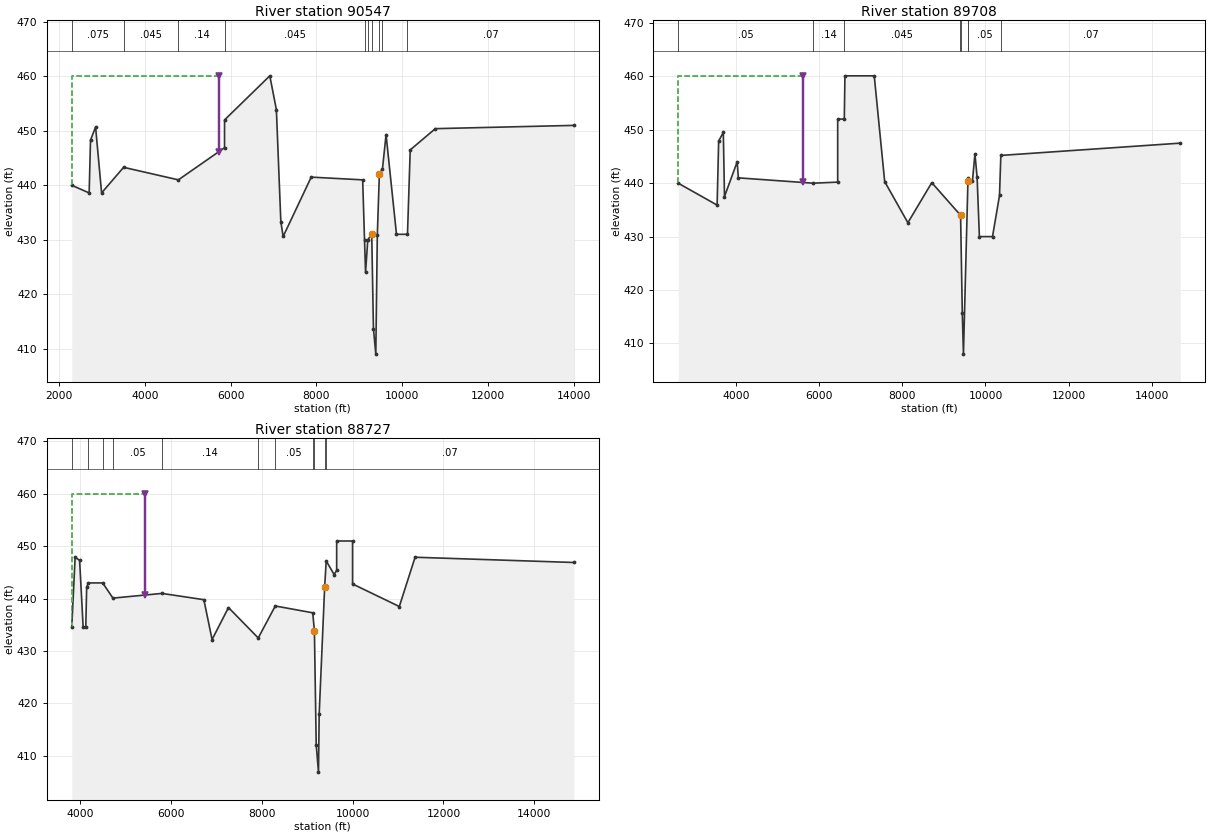
Type RM Length L Ch R = 1 ,90547   ,651,839,951
BEGIN DESCRIPTION:
This cross section corresponds to cross section 90532 of the non-georeferenced CDC model which was the source of this model.
END DESCRIPTION:
XS GIS Cut Line= 5
2452726.779946277036831.144925222446511.170002167035271.50893688
2443460.91166702 7035345.00649332442720.441363197035356.46742839
2441220.621005267035379.68151771
#Sta/Elev= 30
    2300     440    2705   438.6    2737   448.3    2855   450.7    2995   438.6
    3508   443.3    4784     441    5860   446.9    5860     452    6915   460.1
    7068   453.9    7172   433.3    7226   430.6    7880   441.5    9079     441
    9122     430    9146     424    9198     430    9290     431    9330   413.7
    9385     409    9420   430.8    9468   442.1    9540     443    9624   449.3
    9867     431   10123     431   10187   446.5   10772   450.4   14000     451
#Mann= 10 ,-1,0
    2300    .075       0    3508    .045       0    4784     .14       0
    5860    .045       0    9122     .03       0    9198    .045       0
    9290     .05       0    9468     .14       0    9540    .035       0
   10123     .07       0
Levee=-1,5720,460,0,,,,
#XS Ineff= 2 , 0
       0    5720     460               0
Permanent Ineff=
       F       F
Bank Sta=9290,9468
XS Rating Curve= 0 ,0
Exp/Cntr=0.3,0.1

Type RM Length L Ch R = 1 ,89708   ,799,981,999
BEGIN DESCRIPTION:
This cross section corresponds to cross section 89694 of the non-georeferenced CDC model which was the source of this model.
END DESCRIPTION:
XS GIS Cut Line= 6
2452828.585188847035942.362582042446415.268947247034636.62405179
2445895.703057267034393.601243882444214.567311917034485.10959105
2443457.398878757034518.245679632440959.789463927034627.54897753
#Sta/Elev= 30
    2620     440    3554   435.9    3591   447.9    3703   449.5    3731   437.5
    4036     444    4064     441    5860     440    6450   440.2    6450     452
    6609     452    6624   460.1    7328   460.1    7579   440.3    8136   432.6
    8710   440.1    9390   434.1    9402   434.1    9443   415.7    9471     408
    9579   440.5    9592   440.9    9688   440.5    9747   445.5    9799   441.1
    9854     430   10169     430   10337   437.7   10369   445.2   14680   447.5
#Mann= 8 ,-1,0
    2620     .05       0    5860     .14       0    6609    .045       0
    9390     .14       0    9402     .05       0    9579     .14       0
    9592     .05       0   10369     .07       0
Levee=-1,5621,460,0,,,,
#XS Ineff= 2 , 0
       0    5621     460               0
Permanent Ineff=
       F       F
Bank Sta=9402,9579
XS Rating Curve= 0 ,0
Exp/Cntr=0.3,0.1

Type RM Length L Ch R = 1 ,88727   ,1150,1067,950
BEGIN DESCRIPTION:
This cross section corresponds to cross section 88712 of the non-georeferenced CDC model which was the source of this model.
OEI Updated Ground Data and manning's n values  for proposed conditions on West Tracts
XS88727 restored to 1991 topo to remove project CAR 032511-01
END DESCRIPTION:
XS GIS Cut Line= 5
2452003.022207417034988.043296472447177.857973257033966.21692805
2446440.408988837033572.352230222444164.230142277033732.23708105
2441171.60391302 7033942.4470999
#Sta/Elev= 30
    3820   434.6    3894   447.9  3992.5   447.3    4071   434.5    4128   434.5
    4148   442.2  4185.7     443 4500.86     443    4726   440.1    5804     441
    6727   439.8    6908   432.2    7269   438.3    7924   432.5    8299   438.6
    9123   437.3    9160   433.9    9200   412.1    9250   406.9    9265   417.9
    9386   442.3    9420   447.2    9594   444.6    9650   445.4    9650     451
   10000     451   10000   442.8   11029   438.5   11376   447.9   14870   446.9
#Mann= 11 ,-1,0
    3820     .08       0  4185.7     .02       0 4500.86     .08       0
    4726     .05       0    5804     .14       0    7924     .07       0
    8299     .05       0    9123     .12       0    9160     .05       0
    9386     .12       0    9420     .07       0
Levee=-1,5432,460,0,,,,
#XS Ineff= 2 , 0
       0    5432     460               0
Permanent Ineff=
       F       F
Bank Sta=9160,9386
XS Rating Curve= 0 ,0
Exp/Cntr=0.3,0.1

River Reach=Elm Fork        ,PGBT split east
Reach XY= 30
      2447850.52      7040050.17      2448046.24      7039935.45
      2448387.09      7040023.41      2449651.56      7040001.42
      2449924.88      7039707.44      2450709.71      7039354.02
      2451168.18      7039051.97      2450533.58      7038983.11
      2450359.03      7038883.33      2449374.49      7037614.65
      2450454.81      7037133.85      2451581.78      7036549.12
      2451601.55      7035215.06      2451584.45      7035087.75
      2451531.25      7035025.05      2451364.04      7034954.75
      2451018.24      7034916.79      2450829.87      7034738.84
      2450963.55      7034496.21      2450955.74      7034358.19
      2450875.93      7034206.43      2450618.79      7034091.55
      2450352.95      7034104.98      2450186.47      7033984.14
      2450104.06      7033526.54      2449971.54      7033089.05
      2449875.18      7032951.03      2448864.61      7032823.42
      2448171.55      7032801.49      2447356.93      7032903.31

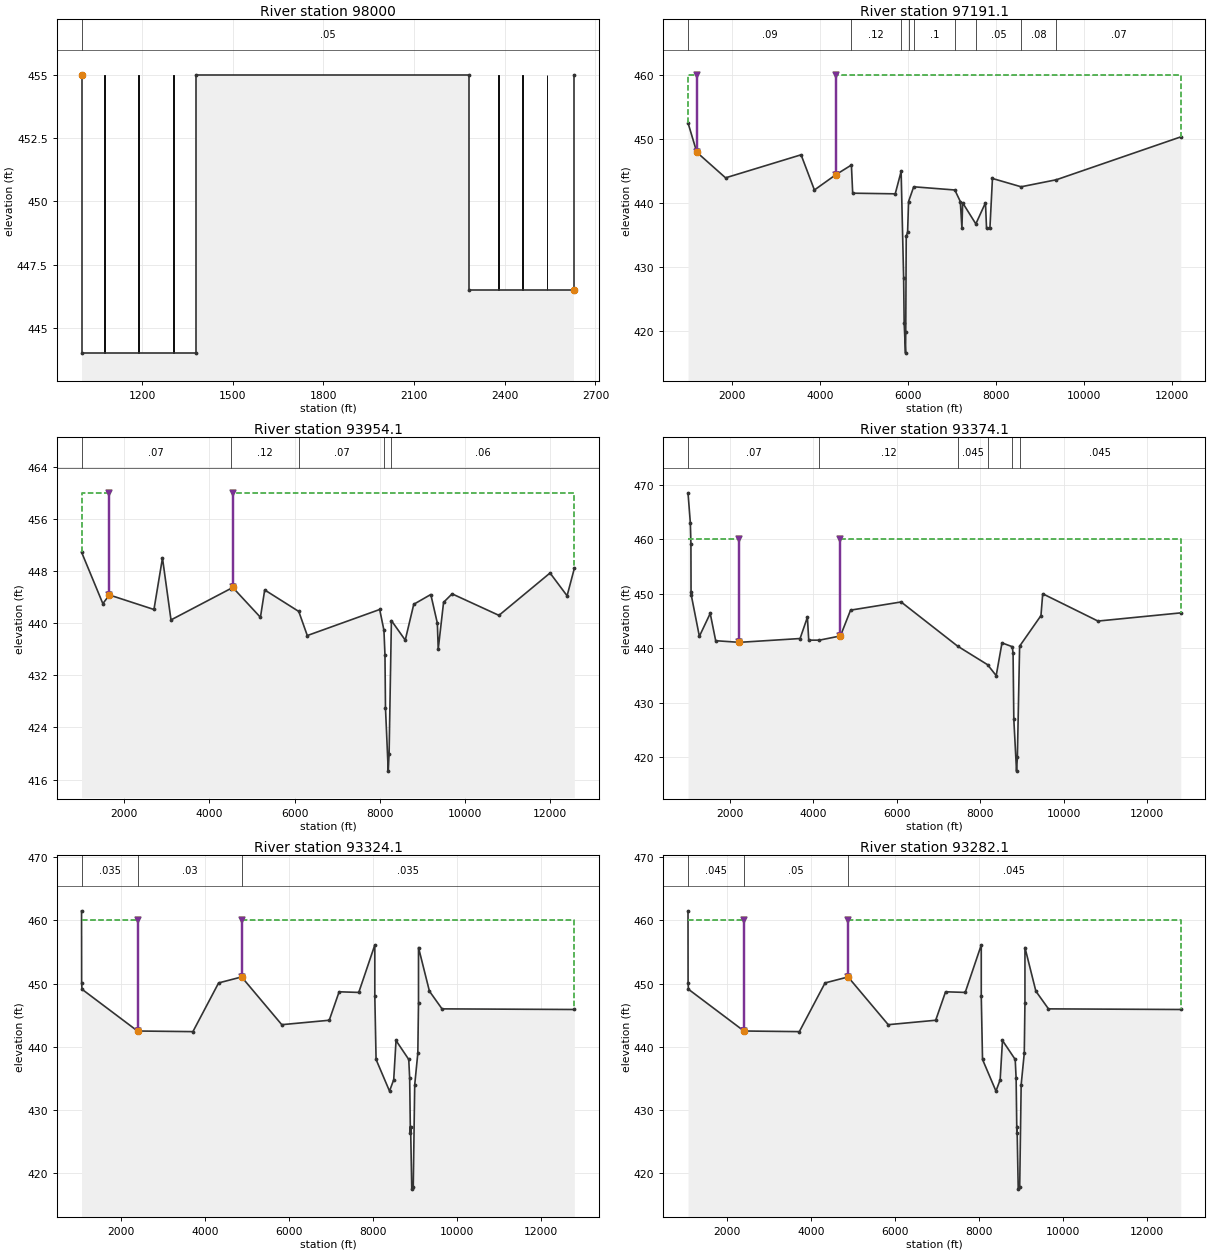
Type RM Length L Ch R = 1 ,98000   ,300,300,300
BEGIN DESCRIPTION:
This cross section corresponds to cross section 98000 of the non-georeferenced CDC model which was the source of this model.
At PGBT West Face of DWU Crossing,
380' +/- bridge opening
END DESCRIPTION:
XS GIS Cut Line= 2
2448936.862001187040430.24205771 2448843.40123017038643.49431889
#Sta/Elev= 8
    1000     455    1000     444    1380     444    1380     455    2280     455
    2280   446.5    2630   446.5    2630     455
#Mann= 1 ,-1,0
    1000     .05       0
#Block Obstruct= 6 ,-1
    1073    1076     455    1188    1191     455    1303    1306     455
    2378    2381     455    2458    2461     455    2538    2541     455
Bank Sta=1000,2630
XS Rating Curve= 0 ,0
Exp/Cntr=0.3,0.1

Type RM Length L Ch R = 1 ,97191.1 ,2200,280,1350
BEGIN DESCRIPTION:
This cross section corresponds to cross section 97178 of the non-georeferenced CDC model which was the source of this model.
END DESCRIPTION:
XS GIS Cut Line= 2
2452739.651967767039715.766124472441539.700942527039682.66481271
#Sta/Elev= 30
    1000   452.5    1200   447.9    1854   443.9    3570   447.5    3873     442
    4360444.3889    4714   445.9    4743   441.5    5710   441.4    5844   444.9
    5901   428.2    5913   421.2    5944   416.5    5949   419.8    5960   434.8
    5991   435.4    6013   440.2    6130   442.5 7064.45     442    7189   440.2
  7225.9     436  7241.9     440  7541.9   436.7  7761.2     440  7785.3     436
  7861.8     436  7919.6   443.8    8571   442.5    9372   443.6   12200   450.3
#Mann= 9 ,-1,0
    1000     .09       0    4714     .12       0    5844     .05       0
    6013    .045       0    6130      .1       0 7064.45      .1       0
  7541.9     .05       0    8571     .08       0    9372     .07       0
Levee=-1,1200,460,-1,4360,460,,
#XS Ineff= 2 , 0
       0    1200     460    4360       0     460
Permanent Ineff=
       T       T
Bank Sta=1200,4360
XS Rating Curve= 0 ,0
Exp/Cntr=0.3,0.1

Type RM Length L Ch R = 1 ,93954.1 ,650,380,460
BEGIN DESCRIPTION:
This cross section corresponds to cross section 93940 of the non-georeferenced CDC model which was the source of this model.
END DESCRIPTION:
XS GIS Cut Line= 6
2452796.764058267039374.541085142448190.277864437039329.19406296
2447158.79895625 7038418.3231813 2443184.57199667038479.04812546
2442031.742937427039465.825023292441936.719177347039466.55632105
#Sta/Elev= 30
    1000   450.9    1500     443    1654 444.328    2700   442.1    2900     450
    3100   440.5    4500   445.3    4550445.4833    5200   440.9    5300   445.1
    6100   441.8    6300   438.1    8000   442.1    8100   438.9    8124   435.1
    8136     427    8201   417.3    8221     420    8275   440.4    8600   437.4
    8800   442.9    9200   444.4    9354     440    9374     436    9500   443.2
    9700   444.5   10800   441.2   12000   447.7   12400   444.2   12570   448.4
#Mann= 5 ,-1,0
    1000     .07       0    4500     .12       0    6100     .07       0
    8100     .05       0    8275     .06       0
Levee=-1,1654,460,-1,4550,460,,
#XS Ineff= 2 , 0
       0    1654     460    4550       0     460
Permanent Ineff=
       T       T
Bank Sta=1654,4550
XS Rating Curve= 0 ,0
Exp/Cntr=0.3,0.1

Type RM Length L Ch R = 1 ,93374.1 ,62,62,62
BEGIN DESCRIPTION:
This cross section corresponds to cross section 93359 of the non-georeferenced CDC model which was the source of this model.
---------------------------------------------------------------------
CDC Cop 050812-01 River Oaks Assisted Living and Memory Care
Cross-section 93359 - 93940
Located in ROB.
---------------------------------------------------------------------
END DESCRIPTION:
XS GIS Cut Line= 6
2453055.818986337039066.976083472448551.367037277039018.65006463
2447550.309000027038212.535207052446565.057033517037943.83003581
 2443660.83088667038049.009943542441985.526494417039186.21665864
#Sta/Elev= 30
    1000   468.5    1056     463    1070   459.2    1073   450.4    1080   449.7
    1272   442.2    1532   446.4    1663   441.4    2230   441.1    3684   441.8
    3859   445.7    3891   441.5    4146   441.5    4650442.2752    4893     447
    6103   448.5    7457   440.4    8174     437    8380     435    8519     441
    8766   440.3    8784   439.1    8802     427    8867   417.5    8887     420
    8941   440.4    9452     446    9494     450   10817     445   12800   446.5
#Mann= 6 ,-1,0
    1000     .07       0    4146     .12       0    7457    .045       0
    8174    .035       0    8766     .05       0    8941    .045       0
Levee=-1,2230,460,-1,4650,460,,
#XS Ineff= 2 , 0
       0    2230     460    4650       0     460
Permanent Ineff=
       T       T
Bank Sta=2230,4650
XS Rating Curve= 0 ,0
Exp/Cntr=0.3,0.1

Type RM Length L Ch R = 1 ,93324.1 ,85,85,85
BEGIN DESCRIPTION:
This cross section corresponds to cross section 93297 of the non-georeferenced CDC model which was the source of this model.
Upstream bounding cross-section for Sandy Lake Road bridge.
END DESCRIPTION:
XS GIS Cut Line= 6
2453066.561747017039007.696674472448786.985660497038967.59209588
2447555.995668417038166.889629052446724.131518517037930.82809331
 2443517.29180367038005.28102839 2441834.59635017038799.91001655
#Sta/Elev= 30
    1068   461.5    1070   450.1    1079   449.1    2400   442.5    3719   442.4
    4331   450.1    4879451.0464    5835   443.5    6965   444.2    7200   448.7
    7668   448.6    8050   456.1    8050     448    8080     438    8400     433
    8500   434.8    8555     441    8858     438    8880     435    8897   426.3
    8902   427.4    8930   417.5    8965   417.8    9000     434    9074     439
    9090     447    9090   455.7    9350   448.8    9650     446   12800   445.9
#Mann= 3 ,0,0
    1068    .035       0    2400     .03       0    4879    .035       0
Levee=-1,2400,460,-1,4879,460,,
#XS Ineff= 2 , 0
       0    2400     460    4879       0     460
Permanent Ineff=
       T       T
Bank Sta=2400,4879
XS Rating Curve= 0 ,0
Exp/Cntr=0.3,0.1

Type RM Length L Ch R = 1 ,93282.1 ,10,15,20
BEGIN DESCRIPTION:
This cross section corresponds to cross section 93212 of the non-georeferenced CDC model which was the source of this model.
Downstream bounding cross-section for Sandy Lake Road bridge.
END DESCRIPTION:
XS GIS Cut Line= 6
2453032.140556017038966.992687632448520.069527697038883.64377296
2447597.799390587038109.242434642446642.141196947037819.29157096
2443907.252637837037866.266214552441707.816747997038336.53299055
#Sta/Elev= 30
    1068   461.5    1070   450.1    1079   449.1    2400   442.5    3719   442.4
    4331   450.1    4879451.0464    5835   443.5    6965   444.2    7200   448.7
    7668   448.6    8050   456.1    8050     448    8080     438    8400     433
    8500   434.8    8555     441    8858     438    8880     435    8897   426.3
    8902   427.4    8930   417.5    8965   417.8    9000     434    9074     439
    9090     447    9090   455.7    9350   448.8    9650     446   12800   445.9
#Mann= 3 ,0,0
    1068    .045       0    2400     .05       0    4879    .045       0
Levee=-1,2400,460,-1,4879,460,,
#XS Ineff= 2 , 0
       0    2400     460    4879       0     460
Permanent Ineff=
       T       T
Bank Sta=2400,4879
XS Rating Curve= 0 ,0
Exp/Cntr=0.3,0.1

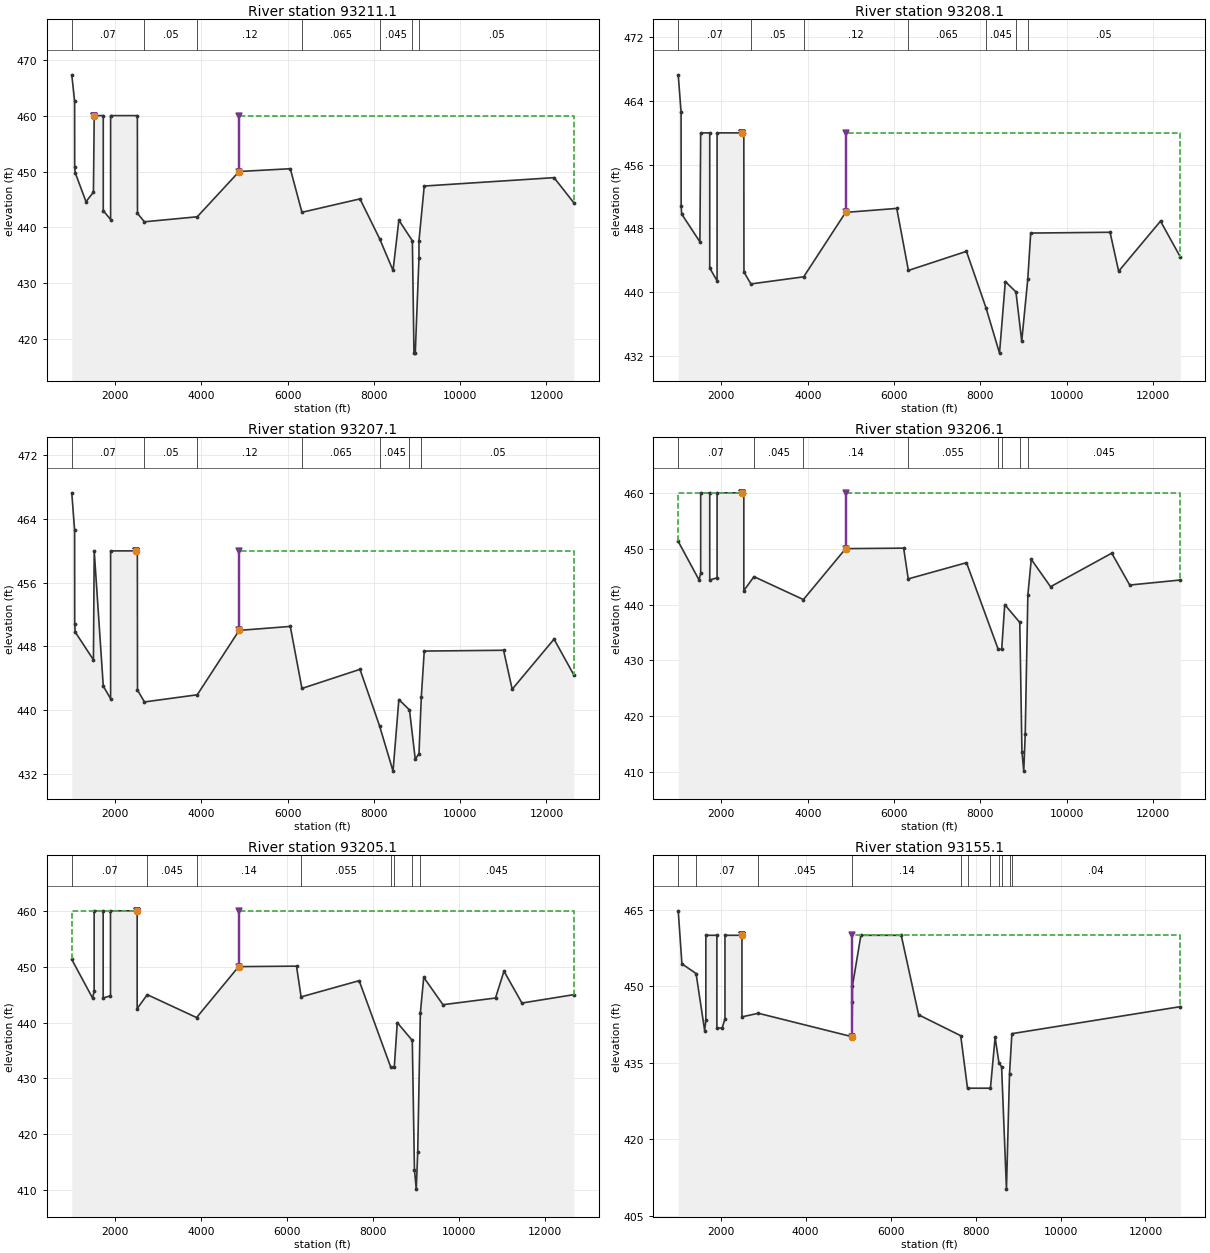
Type RM Length L Ch R = 1 ,93211.1 ,1,1,1
BEGIN DESCRIPTION:
This cross section corresponds to cross section 93197 of the non-georeferenced CDC model which was the source of this model.
END DESCRIPTION:
XS GIS Cut Line= 6
2453120.484211337038918.043310462448624.117547937038876.03912938
2447622.075260677038085.549240542446594.051726167037793.92941697
2443835.875484027037852.24885413 2441886.55884467038237.30353022
#Sta/Elev= 30
    1000   467.3    1066   462.6    1068   450.8    1079   449.8    1330   444.6
    1502   446.3    1520     460    1730     460    1730     443    1900   441.4
    1900     460    2520     460    2523   442.5    2684     441    3908   441.9
    4879450.0003    6064   450.5    6334   442.7    7679   445.1    8132     438
    8445   432.3    8580   441.3    8893   437.6    8930   417.5    8960   417.5
    9046   434.5    9046   437.6    9168   447.4   12176   448.9   12635   444.4
#Mann= 7 ,-1,0
    1000     .07       0    2684     .05       0    3908     .12       0
    6334    .065       0    8132    .045       0    8893     .05       0
    9046     .05       0
Levee=-1,1520,460,-1,4879,460,,
#XS Ineff= 2 , 0
       0    1520     460    4879       0     460
Permanent Ineff=
       T       T
Bank Sta=1520,4879
XS Rating Curve= 0 ,0
Exp/Cntr=0.3,0.1

Type RM Length L Ch R = 1 ,93208.1 ,5,5,5
BEGIN DESCRIPTION:
This cross section corresponds to cross section 93196 of the non-georeferenced CDC model which was the source of this model.
END DESCRIPTION:
XS GIS Cut Line= 6
2453161.383407747038911.607299722448592.968660097038861.20648189
2447619.803611677038082.320244392446590.514987837037792.19451229
2443830.769195027037851.319065972441921.452803677038226.72940439
#Sta/Elev= 30
    1000   467.3    1066   462.6    1068   450.8    1079   449.8    1502   446.3
    1520     460    1730     460    1730     443    1900   441.4    1900     460
    2480     460    2520     460    2523   442.5    2684     441    3908   441.9
    4879450.0003    6064   450.5    6334   442.7    7679   445.1    8132     438
    8445   432.3    8580   441.3    8826     440    8960   433.8    9100   441.6
    9168   447.4   11007   447.5   11206   442.6   12176   448.9   12635   444.4
#Mann= 7 ,-1,0
    1000     .07       0    2684     .05       0    3908     .12       0
    6334    .065       0    8132    .045       0    8826     .02       0
    9100     .05       0
Levee=-1,2480,460,-1,4879,460,,
#XS Ineff= 2 , 0
       0    2480     460    4879       0     460
Permanent Ineff=
       T       T
Bank Sta=2480,4879
XS Rating Curve= 0 ,0
Exp/Cntr=0.3,0.1

Type RM Length L Ch R = 1 ,93207.1 ,1,1,1
BEGIN DESCRIPTION:
This cross section corresponds to cross section 93191 of the non-georeferenced CDC model which was the source of this model.
END DESCRIPTION:
XS GIS Cut Line= 6
 2453153.70166467038906.782834312448582.513956587038855.67696539
2447608.631061857038066.236943222446572.952030847037783.50916222
2443805.37685734 7037846.64322232441915.66278902 7038211.8235943
#Sta/Elev= 30
    1000   467.3    1066   462.6    1068   450.8    1079   449.8    1502   446.3
    1520     460    1730     443    1900   441.4    1900     460    2480     460
    2520     460    2523   442.5    2684     441    3908   441.9    4879450.0003
    6064   450.5    6334   442.7    7679   445.1    8132     438    8445   432.3
    8580   441.3    8826     440    8960   433.8    9046   434.5    9100   441.6
    9168   447.4   11007   447.5   11206   442.6   12176   448.9   12635   444.4
#Mann= 7 ,-1,0
    1000     .07       0    2684     .05       0    3908     .12       0
    6334    .065       0    8132    .045       0    8826     .02       0
    9100     .05       0
Levee=-1,2480,460,-1,4879,460,,
#XS Ineff= 2 , 0
       0    2480     460    4879       0     460
Permanent Ineff=
       T       T
Bank Sta=2480,4879
XS Rating Curve= 0 ,0
Exp/Cntr=0.3,0.1

Type RM Length L Ch R = 1 ,93206.1 ,49,49,49
BEGIN DESCRIPTION:
This cross section corresponds to cross section 93190 of the non-georeferenced CDC model which was the source of this model.
END DESCRIPTION:
XS GIS Cut Line= 6
      2453153.74      7038905.78 2448582.5139566 7038855.6769654
 2447608.6310619 7038066.2369432 2446572.9520308 7037783.5091622
 2443805.3768573 7037846.6432223  2441915.662789 7038211.8232662
#Sta/Elev= 30
    1000   451.3    1483   444.4    1520   445.6    1520     460    1730     460
    1730   444.4    1900   444.8    1900     460    2480     460    2520     460
    2520   442.5    2755     445    3901   440.9    4879450.0134    6224   450.1
    6330   444.6    7680   447.5    8415     432    8496     432    8566     440
    8915   436.8    8965   413.7    9007   410.2    9041   416.8    9102   441.7
    9181   448.1    9628   443.2   11046   449.2   11463   443.5   12635   444.4
#Mann= 8 ,-1,0
    1000     .07       0    2755    .045       0    3901     .14       0
    6330    .055       0    8415    .035       0    8496     .12       0
    8915     .05       0    9102    .045       0
Levee=-1,2480,460,-1,4879,460,,
#XS Ineff= 2 , 0
       0    2480     460    4879       0     460
Permanent Ineff=
       T       T
Bank Sta=2480,4879
XS Rating Curve= 0 ,0
Exp/Cntr=0.3,0.1

Type RM Length L Ch R = 1 ,93205.1 ,760,900,740
BEGIN DESCRIPTION:
This cross section corresponds to cross section 93141 of the non-georeferenced CDC model which was the source of this model.
END DESCRIPTION:
XS GIS Cut Line= 6
2453165.058925337038843.361045142448594.03788367 7038794.2240043
2447632.440069357038006.71606489  2446574.4408737037721.01223996
2445907.796865087037851.960140792441858.408966517037755.36518963
#Sta/Elev= 30
    1000   451.3    1483   444.4    1520   445.6    1520     460    1730     460
    1730   444.4    1900   444.8    1900     460    2520     460    2520   442.5
    2755     445    3901   440.9    4879450.0134    6224   450.1    6330   444.6
    7680   447.5    8415     432    8496     432    8566     440    8915   436.8
    8965   413.7    9007   410.2    9041   416.8    9102   441.7    9181   448.1
    9628   443.2   10849   444.4   11046   449.2   11463   443.5   12670     445
#Mann= 8 ,-1,0
    1000     .07       0    2755    .045       0    3901     .14       0
    6330    .055       0    8415    .035       0    8496     .12       0
    8915     .05       0    9102    .045       0
Levee=-1,2520,460,-1,4879,460,,
#XS Ineff= 2 , 0
       0    2520     460    4879       0     460
Permanent Ineff=
       T       T
Bank Sta=2520,4879
XS Rating Curve= 0 ,0
Exp/Cntr=0.3,0.1

Type RM Length L Ch R = 1 ,93155.1 ,820,680,820
BEGIN DESCRIPTION:
This cross section corresponds to cross section 92351 of the non-georeferenced CDC model which was the source of this model.
END DESCRIPTION:
XS GIS Cut Line= 3
2453370.468947597038416.698184552446778.237053337037093.70312713
2441681.935894257037078.87244813
#Sta/Elev= 30
    1000   464.8    1087   454.4    1420   452.5    1622   441.3    1650   443.3
    1650     460    1910     460    1910   441.8    2034   441.8    2100   443.6
    2100     460    2500     460    2500     444    2887   444.7    5090440.1099
    5100     447    5100     450    5300     460    6250     460    6659   444.4
    7650   440.3    7810     430    8350     430    8460     440    8550     435
    8613   434.2    8727   410.2    8799   432.8    8855   440.7   12820     446
#Mann= 11 ,-1,0
    1000    .045       0    1420     .07       0    2887    .045       0
    5100     .14       0    7650     .05       0    7810     .03       0
    8350     .05       0    8550     .14       0    8613     .05       0
    8799     .14       0    8855     .04       0
Levee=-1,2500,460,-1,5090,460,,
#XS Ineff= 2 , 0
       0    2500     460    5090       0     460
Permanent Ineff=
       T       T
Bank Sta=2500,5090
XS Rating Curve= 0 ,0
Exp/Cntr=0.3,0.1

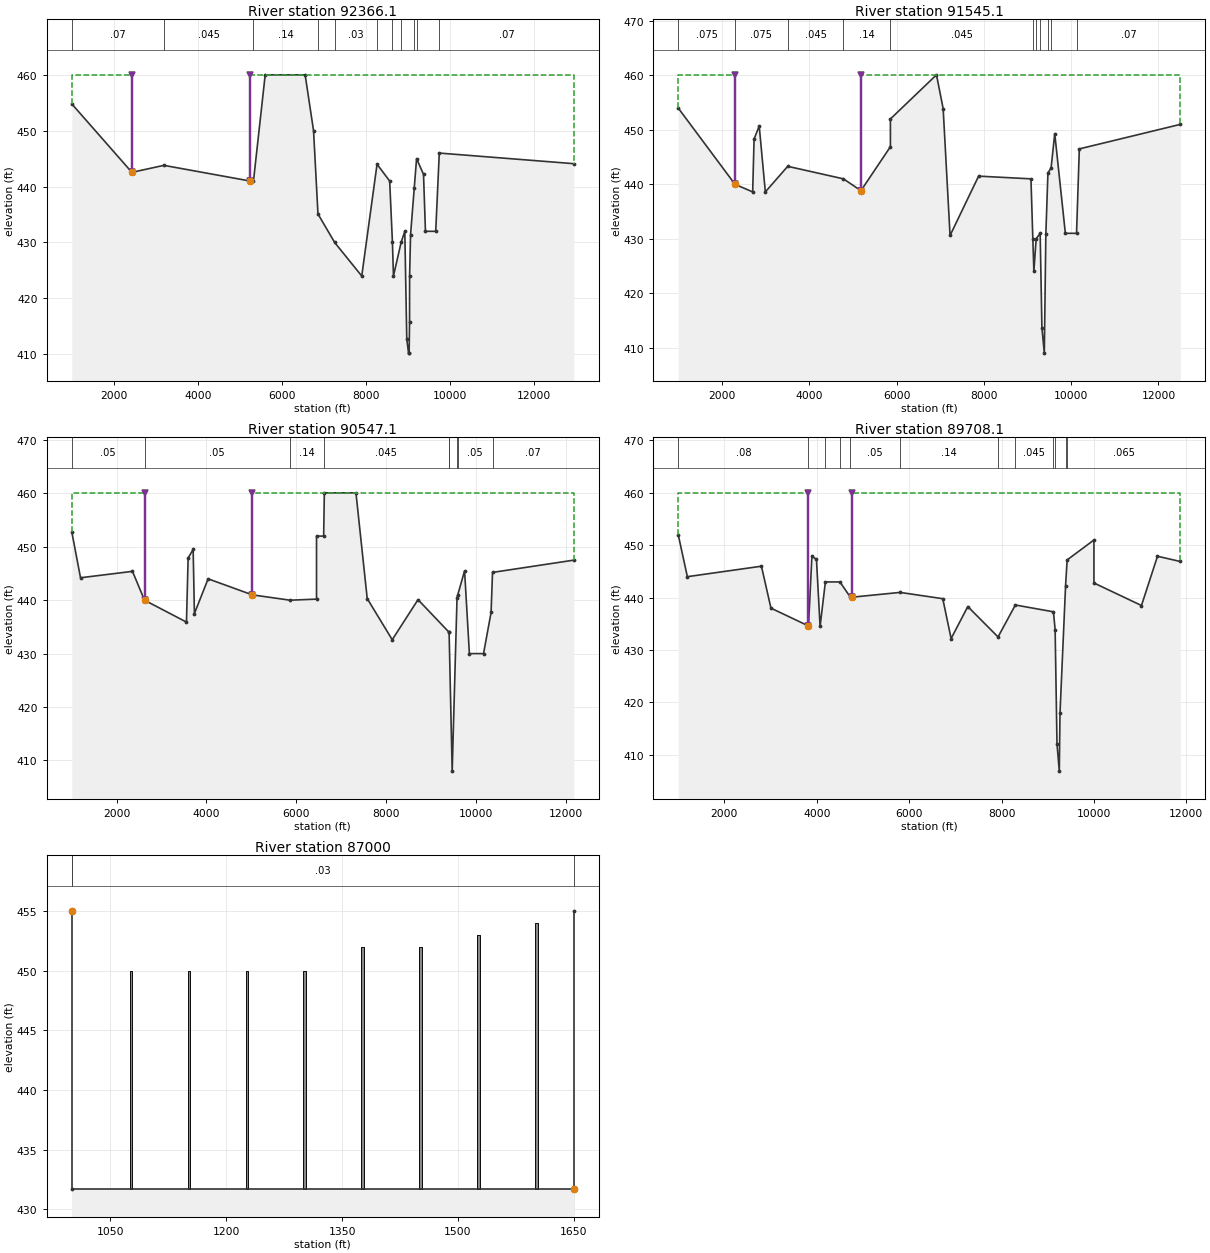
Type RM Length L Ch R = 1 ,92366.1 ,1000,830,1000
BEGIN DESCRIPTION:
This cross section corresponds to cross section 91530 of the non-georeferenced CDC model which was the source of this model.
END DESCRIPTION:
XS GIS Cut Line= 3
2453657.147836187037825.518920722446457.170110177036270.74315888
2441883.650057767036341.30240096
#Sta/Elev= 30
    1000   454.8    2430 442.549    3190   443.8    5240     441    5321     441
    5600     460    6550     460    6750     450    6855   435.1    7252     430
    7896     424    8260     444    8560     441    8626     430    8650     424
    8832     430    8920     432    8967   412.7    9009   410.2    9023   410.2
    9033   415.8    9034     424    9057   431.4    9145   439.8    9200     445
    9365   442.2    9411     432    9655     432    9740     446   12940   444.1
#Mann= 11 ,-1,0
    1000     .07       0    3190    .045       0    5321     .14       0
    6855    .035       0    7252     .03       0    8260    .045       0
    8626     .03       0    8832     .05       0    9145     .14       0
    9200    .035       0    9740     .07       0
Levee=-1,2430,460,-1,5240,460,,
#XS Ineff= 2 , 0
       0    2430     460    5240       0     460
Permanent Ineff=
       T       T
Bank Sta=2430,5240
XS Rating Curve= 0 ,0
Exp/Cntr=0.3,0.1

Type RM Length L Ch R = 1 ,91545.1 ,650,838,950
BEGIN DESCRIPTION:
This cross section corresponds to cross section 90532 of the non-georeferenced CDC model which was the source of this model.
END DESCRIPTION:
XS GIS Cut Line= 4
2453987.691138337037147.536024722446511.170002167035271.50893688
2443460.91166702 7035345.00649332442720.441363197035356.46742839
#Sta/Elev= 30
    1000     454    2300     440    2705   438.6    2737   448.3    2855   450.7
    2995   438.6    3508   443.3    4784     441    5185438.8321    5860   446.9
    5860     452    6915   460.1    7068   453.9    7226   430.6    7880   441.5
    9079     441    9122     430    9146     424    9198     430    9290     431
    9330   413.7    9385     409    9420   430.8    9468   442.1    9540     443
    9624   449.3    9867     431   10123     431   10187   446.5   12500     451
#Mann= 11 ,-1,0
    1000    .075       0    2300    .075       0    3508    .045       0
    4784     .14       0    5860    .045       0    9122     .03       0
    9198    .045       0    9290     .05       0    9468     .14       0
    9540    .035       0   10123     .07       0
Levee=-1,2300,460,-1,5185,460,,
#XS Ineff= 2 , 0
       0    2300     460    5185       0     460
Permanent Ineff=
       T       T
Bank Sta=2300,5185
XS Rating Curve= 0 ,0
Exp/Cntr=0.3,0.1

Type RM Length L Ch R = 1 ,90547.1 ,800,800,1000
BEGIN DESCRIPTION:
This cross section corresponds to cross section 89694 of the non-georeferenced CDC model which was the source of this model.
---------------------------------------------------------------------
CDC CAR040507-1 Western Extrusions
Cross-section 89694-91530
Located in LOB within ineffective flow area.
---------------------------------------------------------------------
END DESCRIPTION:
XS GIS Cut Line= 5
2454416.018037597036265.561082632446415.268947247034636.62405179
2445895.703057267034393.601243882444214.567311917034485.10959105
2443457.398878757034518.24567963
#Sta/Elev= 30
    1000   452.8    1195   444.2    2352   445.4    2620     440    3554   435.9
    3591   447.9    3703   449.5    3731   437.5    4036     444    5020     441
    5860     440    6450   440.2    6450     452    6609     452    6624   460.1
    7328   460.1    7579   440.3    8136   432.6    8710   440.1    9390   434.1
    9402   434.1    9471     408    9579   440.5    9592   440.9    9747   445.5
    9854     430   10169     430   10337   437.7   10369   445.2   12180   447.5
#Mann= 9 ,-1,0
    1000     .05       0    2620     .05       0    5860     .14       0
    6609    .045       0    9390     .14       0    9402     .05       0
    9579     .14       0    9592     .05       0   10369     .07       0
Levee=-1,2620,460,-1,5020,460,,
#XS Ineff= 2 , 0
       0    2620     460    5020       0     460
Permanent Ineff=
       T       T
Bank Sta=2620,5020
XS Rating Curve= 0 ,0
Exp/Cntr=0.3,0.1

Type RM Length L Ch R = 1 ,89708.1 ,1150,550,950
BEGIN DESCRIPTION:
This cross section corresponds to cross section 88712 of the non-georeferenced CDC model which was the source of this model.
OEI Updated Ground Data and manning's n values  for proposed conditions on West Tracts
END DESCRIPTION:
XS GIS Cut Line= 4
2454761.838868267035572.279004632447177.857973257033966.21692805
2446440.408988837033572.352230222444164.230142277033732.23708105
#Sta/Elev= 30
    1000     452 1197.54     444 2801.35     446 3006.98     438    3820   434.6
    3894   447.9  3992.5   447.3    4071   434.5  4185.7     443 4500.86     443
    4726   440.1    4770440.0958    5804     441    6727   439.8    6908   432.2
    7269   438.3    7924   432.5    8299   438.6    9123   437.3    9160   433.9
    9200   412.1    9250   406.9    9265   417.9    9386   442.3    9420   447.2
   10000     451   10000   442.8   11029   438.5   11376   447.9   11870   446.9
#Mann= 12 ,-1,0
    1000     .08       0    3820     .08       0  4185.7     .02       0
 4500.86     .08       0    4726     .05       0    5804     .14       0
    7924     .07       0    8299    .045       0    9123     .12       0
    9160     .05       0    9386     .12       0    9420    .065       0
Levee=-1,3820,460,-1,4770,460,,
#XS Ineff= 2 , 0
       0    3820     460    4770       0     460
Permanent Ineff=
       T       T
Bank Sta=3820,4770
XS Rating Curve= 0 ,0
Exp/Cntr=0.3,0.1

Type RM Length L Ch R = 1 ,87000   ,,,
BEGIN DESCRIPTION:
This cross section corresponds to cross section 87000 of the non-georeferenced CDC model which was the source of this model.
PGBT, West Face of Bridge Structure Approximated
END DESCRIPTION:
XS GIS Cut Line= 2
2450736.60840169 7034400.27806782451049.781003687033963.45840338
#Sta/Elev= 4
    1000     455    1000   431.7    1650   431.7    1650     455
#Mann= 3 ,0,0
    1000    .055       0    1000     .03       0    1650    .055       0
#Block Obstruct= 8 ,-1
    1075    1078     450    1150    1153     450    1225    1228     450
    1300    1303     450    1375    1378     452    1450    1453     452
    1525    1528     453    1600    1603     454
#XS Lid=3
    1000  452.62  448.27    1180  454.09  448.61    1650  457.92   453.7
Bank Sta=1000,1650
XS Rating Curve= 0 ,0
Exp/Cntr=0.3,0.1

River Reach=Elm Fork        ,ef3 ds
Reach XY= 30
      2447356.93      7032903.31      2449276.42      7028990.09
      2448521.48      7026637.83      2447000.53      7025969.64
       2449243.1      7024505.45      2447907.61      7024057.09
      2447661.34       7018966.6      2449579.68      7018119.64
      2451509.59      7014814.57      2451262.61      7011037.61
       2450116.3      7010513.16      2449776.69      7008454.84
      2450712.67      7007237.43      2450043.63      7003476.24
      2452456.92      7003195.07      2451436.24      7001846.74
      2452973.76      7000073.06      2452181.75      6998915.55
      2454526.25      6998940.04      2454971.66       6998016.3
      2455835.87      6998821.28      2456369.33      6997815.18
      2459151.98      6996708.01      2460049.87      6997211.53
      2460262.81      6996093.07      2463259.53      6995089.58
      2462990.63      6989165.68      2458140.49       6983253.5
      2458296.43      6980416.59       2460651.9      6977070.51

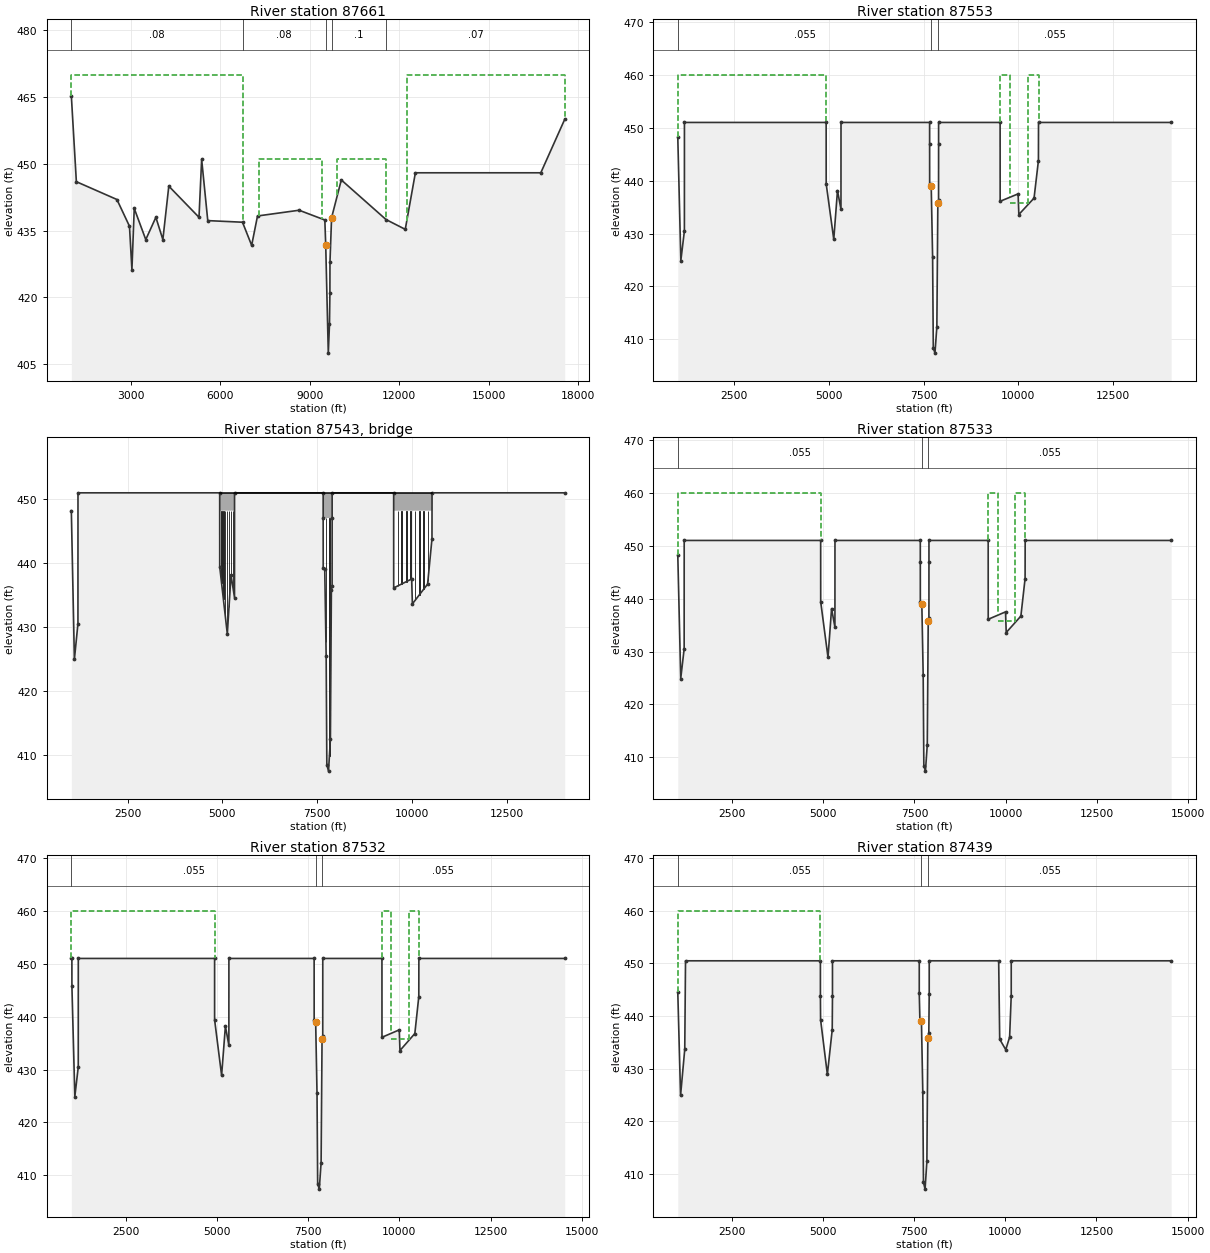
Type RM Length L Ch R = 1 ,87661   ,108,108,108
BEGIN DESCRIPTION:
This cross section corresponds to cross section 87645 of the non-georeferenced CDC model which was the source of this model.
Luna Road Extension USACE Permit Number 199300443
Cross-section 8764 - 90532
Located in LOB.
---------------------------------------
CDC CAR171221-01 Valwood Crossing
In LOB between cross-sections 87541 - 88712.
This project supercedes previous two CDC projects listed below.
CDC PROJECTS: CAR032511-1 AND CAR032511-2 PROPOSED LUNA ROAD LP and #2 LP
************************
END DESCRIPTION:
XS GIS Cut Line= 6
2455887.09514791 7033701.99403132455520.128034097033523.18992697
  2454945.8729497033352.136135222448091.474912437032838.97213531
2439726.696366437033333.714256052439450.78484476 7033400.9532948
#Sta/Elev= 30
    1000  465.29 1168.59     446 2528.56     442 2949.73     436 3031.52  426.22
 3109.47     440 3496.07     433  3834.8     438  4069.4     433  4268.4     445
 5281.31     438  5370.2     451 5575.21  437.26    6740   436.9    7047   431.7
    7243   438.3 8639.04  439.59    9501   437.4    9531   431.7    9617   407.5
    9657     414    9671   421.1    9673   427.9    9727   437.910053.13  446.39
11552.79   437.5   12198   435.312537.56     448 16743.4     448 17544.8     460
#Mann= 5 ,-1,0
    1000     .08       0    6740     .08       0    9531     .05       0
    9727      .1       011552.79     .07       0
#XS Ineff= 4 ,-1
    1000 6740.01     470    7280    9420     451    9920   11560     451
 12249.9 17544.8     470
Permanent Ineff=
       F       F       F       F
Bank Sta=9531,9727
XS Rating Curve= 0 ,0
Exp/Cntr=0.3,0.1

Type RM Length L Ch R = 1 ,87553   ,20,20,20
BEGIN DESCRIPTION:
This cross section corresponds to cross section 87541 of the non-georeferenced CDC model which was the source of this model.
---------------------------------------------------------------------
CDC PROJECTS: CAR032511-1 AND CAR032511-2 PROPOSED LUNA ROAD LP and #2 LP
CROSS-SECTION 87541 - 89694
---------------------------------------------------------------------
END DESCRIPTION:
XS GIS Cut Line= 6
2454102.120371437033203.139057892451323.501912927032973.65756147
2449224.330586347032814.517131722447823.491196427032749.33812821
 2446156.59164317032832.145377292441112.34216543 7033123.6423869
#Sta/Elev= 30
  1015.6   448.2    1096   424.9    1190   430.5    1191     451    4930     451
    4931   439.4    5131   428.9    5229  438.12    5321   434.6    5322     451
    7660     451    7660     447    7661   439.3    7702     439    7739   425.5
    7757   408.4    7801   407.4    7851   412.4    7877   435.8    7896   436.4
    7897     447    7897     451    9520     451    9521   436.1    9995   437.5
   10014   433.6 10415.5   436.7   10531   443.8   10533     451   14033     451
#Mann= 3 ,0,0
  1015.6    .055       0    7702     .05       0    7877    .055       0
#XS Ineff= 6 ,-1
    1000    4930     460    4930    7702     439    7877    9520   435.8
    9520    9778     460    9778   10268   435.8   10268   10533     460
Permanent Ineff=
       F       F       F       F       F       F
Bank Sta=7702,7877
XS Rating Curve= 0 ,0
Exp/Cntr=0.5,0.3

Type RM Length L Ch R = 3 ,87543   ,,,
BEGIN DESCRIPTION:
Southern Pacific Railroad
END DESCRIPTION:
Node Name=Southern Pacific
Bridge Culvert--1,0,-1,-1, 0
Deck Dist Width WeirC Skew NumUp NumDn MinLoCord MaxHiCord MaxSubmerge Is_Ogee
1,18,2.6,0, 46, 46, , , 0.95, 0, ,,,
    4930    4930    4974    4984    5023    5033    5072    5082    5121    5131
    5170    5180    5219    5229    5268    5278    5322    5322    7660    7660
    7729    7737    7820    7828    7897    7897    9520    9520  9624.5  9641.5
  9737.5  9754.5  9850.5  9867.5  9963.5  9980.5 10076.5 10093.5 10189.5 10206.5
 10302.5 10319.5 10415.5 10432.5   10533   10533
     451     451     451     451     451     451     451     451     451     451
     451     451     451     451     451     451     451     451     451     451
     451     451     451     451     451     451     451     451     451     451
     451     451     451     451     451     451     451     451     451     451
     451     451     451     451     451     451
     451   448.2   448.2   448.2   448.2   448.2   448.2   448.2   448.2   448.2
   448.2   448.2   448.2   448.2   448.2   448.2   448.2     451     451     447
     447     447     447     447     447     451     451   448.2   448.2   448.2
   448.2   448.2   448.2   448.2   448.2   448.2   448.2   448.2   448.2   448.2
   448.2   448.2   448.2   448.2   448.2     451
    4930    4930    4974    4984    5023    5033    5072    5082    5121    5131
    5170    5180    5219    5229    5268    5278    5322    5322    7660    7660
    7729    7737    7820    7828    7897    7897    9520    9520  9624.5  9641.5
  9737.5  9754.5  9850.5  9867.5  9963.5  9980.5 10076.5 10093.5 10189.5 10206.5
 10302.5 10319.5 10415.5 10432.5   10533   10533
     451     451     451     451     451     451     451     451     451     451
     451     451     451     451     451     451     451     451     451     451
     451     451     451     451     451     451     451     451     451     451
     451     451     451     451     451     451     451     451     451     451
     451     451     451     451     451     451
     451   448.2   448.2   448.2   448.2   448.2   448.2   448.2   448.2   448.2
   448.2   448.2   448.2   448.2   448.2   448.2   448.2     451     451     447
     447     447     447     447     447     451     451   448.2   448.2   448.2
   448.2   448.2   448.2   448.2   448.2   448.2   448.2   448.2   448.2   448.2
   448.2   448.2   448.2   448.2   448.2     451
Pier Skew, UpSta & Num, DnSta & Num=  ,4979, 2 ,4979, 2 , 0 , 0 , 0 ,,
      10      10
     420     450
      10      10
     420     450
Pier Skew, UpSta & Num, DnSta & Num=  ,5028, 2 ,5028, 2 , 0 , 0 , 0 ,,
      10      10
     420     450
      10      10
     420     450
Pier Skew, UpSta & Num, DnSta & Num=  ,5077, 2 ,5077, 2 , 0 , 0 , 0 ,,
      10      10
     420     450
      10      10
     420     450
Pier Skew, UpSta & Num, DnSta & Num=  ,5126, 2 ,5126, 2 , 0 , 0 , 0 ,,
      10      10
     420     450
      10      10
     420     450
Pier Skew, UpSta & Num, DnSta & Num=  ,5175, 2 ,5175, 2 , 0 , 0 , 0 ,,
      10      10
     420     450
      10      10
     420     450
Pier Skew, UpSta & Num, DnSta & Num=  ,5224, 2 ,5224, 2 , 0 , 0 , 0 ,,
      10      10
     420     450
      10      10
     420     450
Pier Skew, UpSta & Num, DnSta & Num=  ,5273, 2 ,5273, 2 , 0 , 0 , 0 ,,
      10      10
     420     450
      10      10
     420     450
Pier Skew, UpSta & Num, DnSta & Num=  ,7733, 2 ,7733, 2 , 0 , 0 , 0 ,,
       8       8
     420     450
       8       8
     420     450
Pier Skew, UpSta & Num, DnSta & Num=  ,7824, 2 ,7824, 2 , 0 , 0 , 0 ,,
       8       8
     420     450
       8       8
     420     450
Pier Skew, UpSta & Num, DnSta & Num=  ,9633, 2 ,9633, 2 , 0 , 0 , 0 ,,
      17      17
     420     450
      17      17
     420     450
Pier Skew, UpSta & Num, DnSta & Num=  ,9729, 2 ,9729, 2 , 0 , 0 , 0 ,,
      17      17
     420     450
      17      17
     420     450
Pier Skew, UpSta & Num, DnSta & Num=  ,9859, 2 ,9859, 2 , 0 , 0 , 0 ,,
      17      17
     420     450
      17      17
     420     450
Pier Skew, UpSta & Num, DnSta & Num=  ,9972, 2 ,9972, 2 , 0 , 0 , 0 ,,
      17      17
     420     450
      17      17
     420     450
Pier Skew, UpSta & Num, DnSta & Num=  ,10085, 2 ,10085, 2 , 0 , 0 , 0 ,,
      17      17
     420     450
      17      17
     420     450
Pier Skew, UpSta & Num, DnSta & Num=  ,10198, 2 ,10198, 2 , 0 , 0 , 0 ,,
      17      17
     420     450
      17      17
     420     450
Pier Skew, UpSta & Num, DnSta & Num=  ,10311, 2 ,10311, 2 , 0 , 0 , 0 ,,
      17      17
     420     450
      17      17
     420     450
Pier Skew, UpSta & Num, DnSta & Num=  ,10424, 2 ,10424, 2 , 0 , 0 , 0 ,,
      17      17
     420     450
      17      17
     420     450
BR Coef= 1 , 0 , 0 ,1.05, 0 ,,,0.8,-1,0.5,1,
WSPro=,,,, 1 ,,,, 0 ,,,, 0 ,,,,-1 ,-1 ,-1 , 0 , 0 , 0 , 0 , 0
BC Design=,, 0 ,, 0 ,,,,,,
BC HTab HWMax=451
BC Use User HTab Curves=0
BC User HTab FreeFlow(D)= 0

Type RM Length L Ch R = 1 ,87533   ,1,1,1
BEGIN DESCRIPTION:
This cross section corresponds to cross section 87522 of the non-georeferenced CDC model which was the source of this model.
END DESCRIPTION:
XS GIS Cut Line= 6
2454120.089167517033189.222747132451256.687085937032950.51850013
2449170.19257125 7032792.92695182447774.69765884 7032732.9585678
2446114.146846097032813.27960138 2440630.59999147033120.73640699
#Sta/Elev= 30
  1015.6   448.2    1096   424.9    1190   430.5    1191     451    4930     451
    4931   439.4    5131   428.9    5229  438.12    5321   434.6    5322     451
    7660     451    7660     447    7661   439.3    7702     439    7739   425.5
    7757   408.4    7801   407.4    7851   412.4    7877   435.8    7896   436.4
    7897     447    7897     451    9520     451    9521   436.1    9995   437.5
   10014   433.6 10415.5   436.7   10531   443.8   10533     451   14533     451
#Mann= 3 ,0,0
  1015.6    .055       0    7702     .05       0    7877    .055       0
#XS Ineff= 6 ,-1
    1000    4930     460    4930    7702     439    7877    9520   435.8
    9520    9778     460    9778   10268   435.8   10268   10533     460
Permanent Ineff=
       F       F       F       F       F       F
Bank Sta=7702,7877
XS Rating Curve= 0 ,0
Exp/Cntr=0.5,0.3

Type RM Length L Ch R = 1 ,87532   ,120,93,70
BEGIN DESCRIPTION:
This cross section corresponds to cross section 87521 of the non-georeferenced CDC model which was the source of this model.
END DESCRIPTION:
XS GIS Cut Line= 6
2454132.295179847033189.360870212451253.417079337032949.31935555
2449167.344807927032791.790799222447772.13106292 7032732.0963648
2446111.913910937032812.286493142440627.212328417033119.31093543
#Sta/Elev= 30
    1000     451    1015     451    1016   445.7    1096   424.9    1190   430.5
    1191     451    4930     451    4930   439.4    5122   428.9    5226   438.2
    5321   434.6    5322     451    7660     451    7661   439.3    7702     439
    7739   425.5    7757   408.4    7801   407.4    7851   412.4    7877   435.8
    7896   436.4    7897     451    9520     451    9521   436.1    9995   437.5
   10014   433.6   10422   436.8   10531   443.8   10533     451   14533     451
#Mann= 3 ,0,0
    1000    .055       0    7702     .05       0    7877    .055       0
#XS Ineff= 6 ,-1
    1000    4930     460    4930    7702     439    7877    9520   435.8
    9520    9778     460    9778   10268   435.8   10268   10533     460
Permanent Ineff=
       F       F       F       F       F       F
Bank Sta=7702,7877
XS Rating Curve= 0 ,0
Exp/Cntr=0.5,0.3

Type RM Length L Ch R = 1 ,87439   ,85,85,85
BEGIN DESCRIPTION:
This cross section corresponds to cross section 87428 of the non-georeferenced CDC model which was the source of this model.
END DESCRIPTION:
XS GIS Cut Line= 6
  2454099.7762167033113.246849212451670.286324357032924.21146613
2450948.477072427032837.734276882448898.740358267032685.89796638
2447533.458640017032651.919687882440595.786211237032971.39049108
#Sta/Elev= 30
    1020   444.5    1096   424.9    1211   433.7    1232   450.5    4931   450.5
    4931  443.78    4936   439.3    5122   428.9    5255   437.4    5262  443.78
    5262   450.5    7642   450.5    7642  444.29    7659   439.3    7702     439
    7739   425.5    7757   408.4    7801   407.1    7851   412.4    7877   435.8
    7904   436.8    7915  444.18    7915   450.5    9820   450.5    9848   435.6
   10014   433.6   10120     436   10164   443.9   10164   450.5   14550   450.5
#Mann= 3 ,0,0
    1020    .055       0    7702     .05       0    7877    .055       0
#XS Ineff= 2 , 0
       0    4931     460               0
Permanent Ineff=
       F       F
Bank Sta=7702,7877
XS Rating Curve= 0 ,0
Exp/Cntr=0.5,0.3