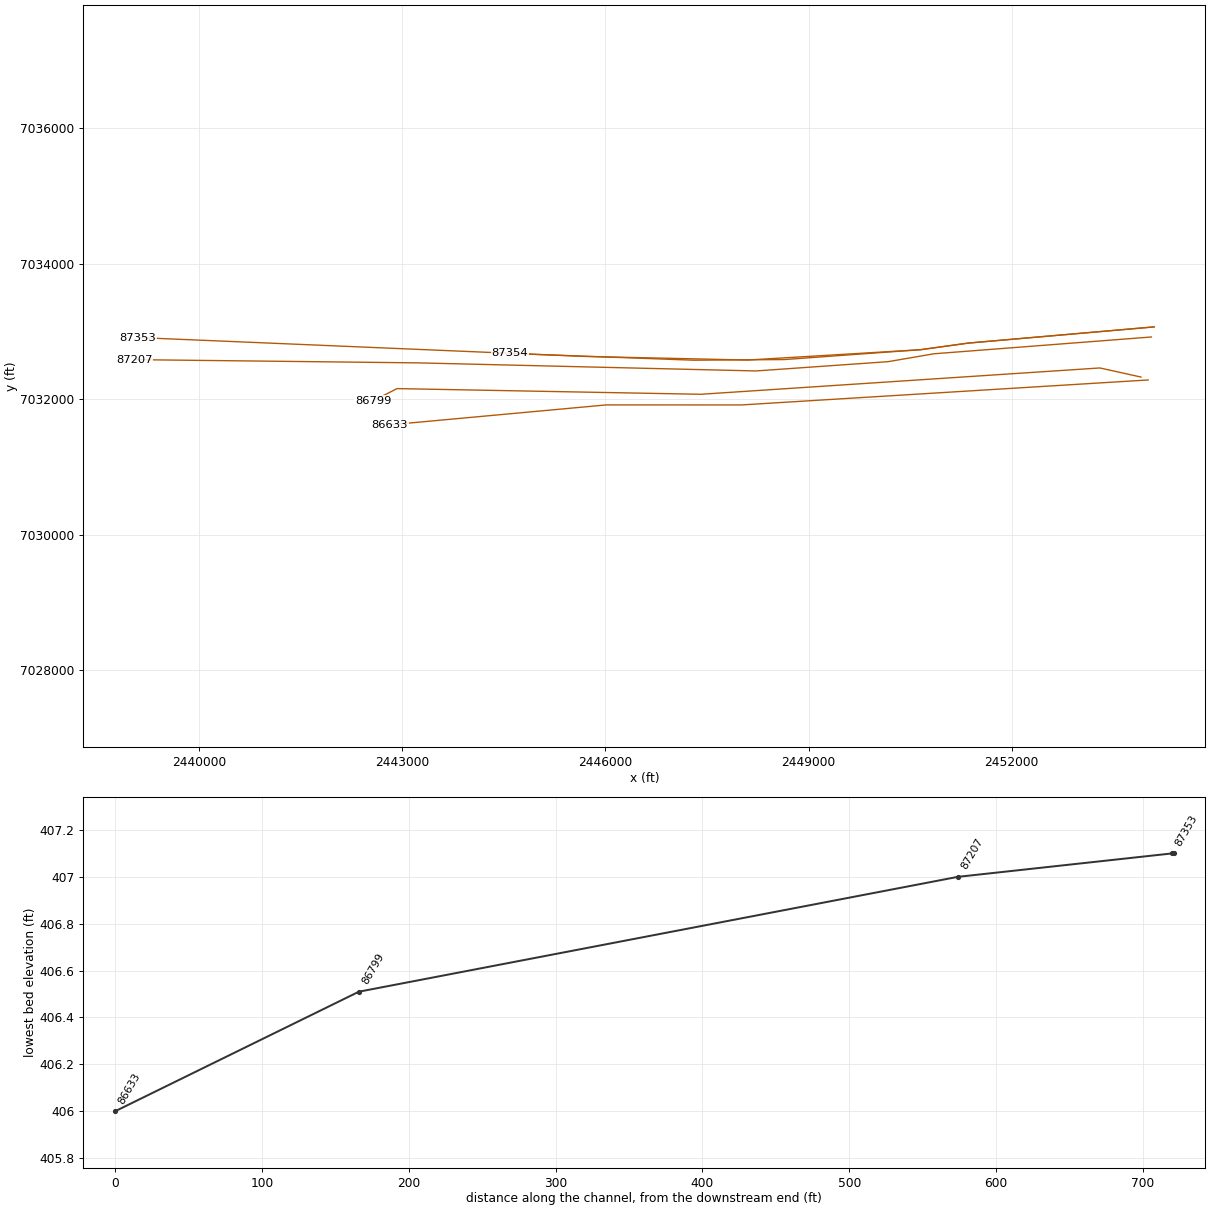
HEC-RAS study CDC_Consolidated_Model.prj: Upper Trinity CDC Consolidated Model

--- CDC_Consolidated_Model.g02 (geometry) --- (continued)

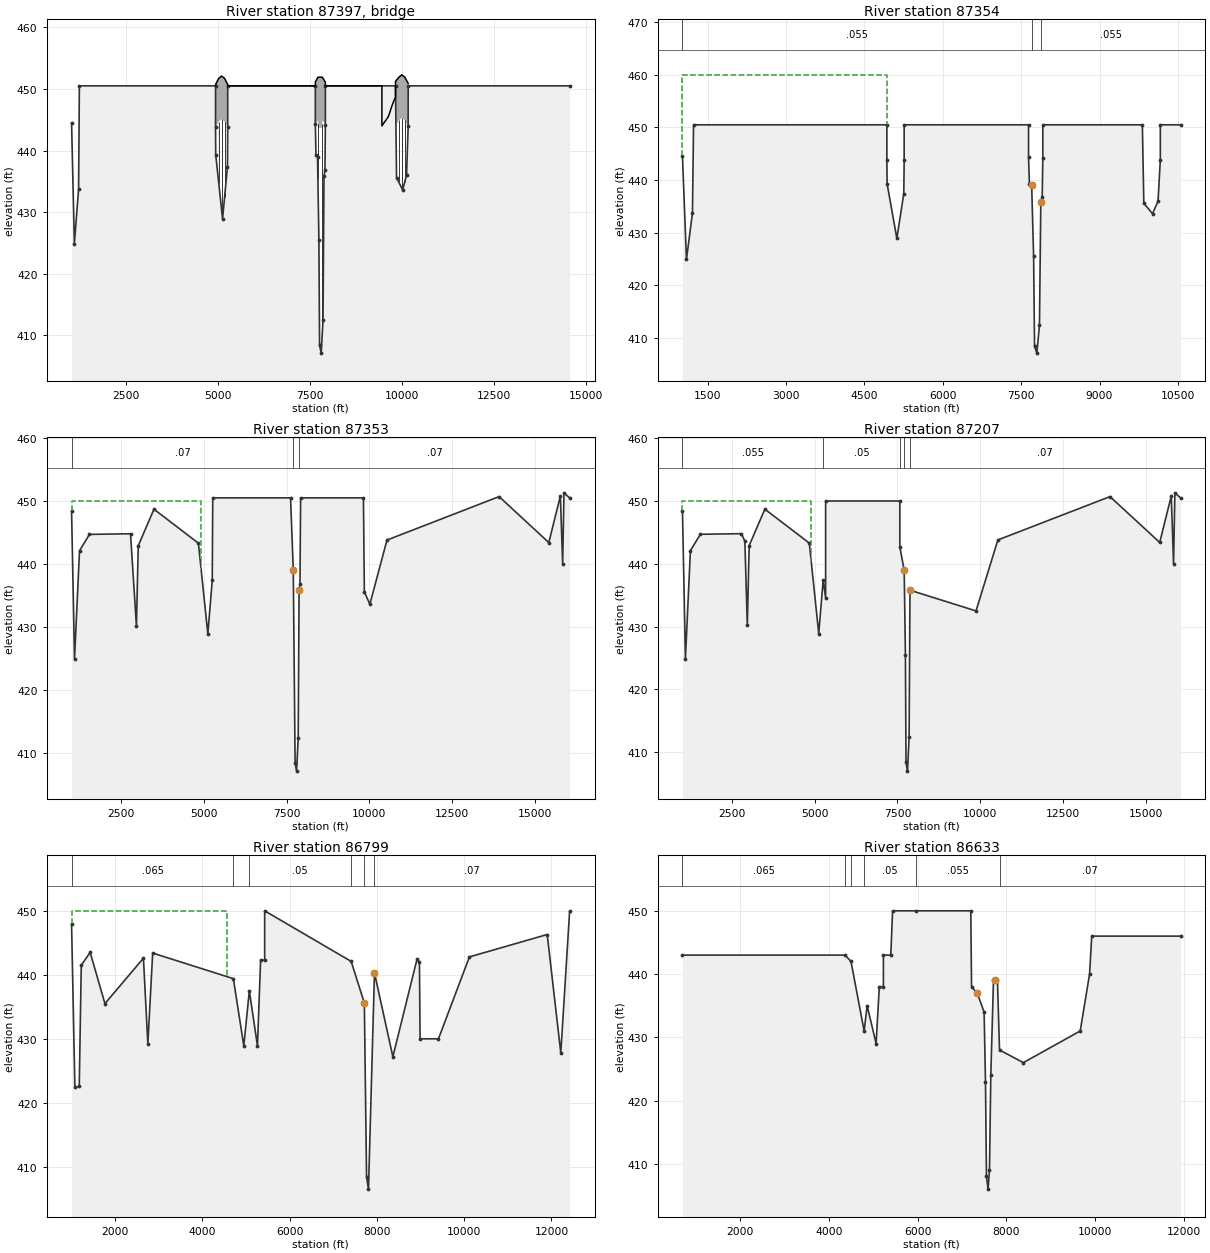
Type RM Length L Ch R = 3 ,87397   ,,,
BEGIN DESCRIPTION:
Belt Line Road
END DESCRIPTION:
Node Name=Belt Line Road
Bridge Culvert--1,0,-1,-1, 0
Deck Dist Width WeirC Skew NumUp NumDn MinLoCord MaxHiCord MaxSubmerge Is_Ogee
0.5,84,2.6,0, 38, 38, , , 0.95, 0, ,,,
    4931    4931  5015.8  5018.3  5095.8  5098.3  5175.8  5178.3    5262    5262
    5369    7520    7642    7642  7710.8  7713.3  7830.8  7833.3    7915    7915
    8024    9450    9451    9508    9593    9639    9720    9791    9820    9820
    9830  9910.8  9913.3  9990.8  9993.3 10070.8 10073.3   10164
   450.5   450.7  451.69  451.71  452.09  452.09  451.71  451.69   450.7   450.5
   450.5   450.5   450.5   451.1  451.89   451.9   451.9  451.89   451.1   450.5
   450.5   450.5     444   444.5   445.2   445.7   447.2   448.3   448.6   451.2
   451.3  451.89  451.91  452.29  452.29  451.91  451.89   450.9
   450.5  443.78  444.69  444.71  445.09  445.09  444.71  444.69  443.78   450.5
   450.5   450.5   450.5  444.29  444.89   443.7   443.7  444.89  444.29   450.5
   450.5   450.5     444   444.5   445.2   445.7   447.2   448.3   448.6   443.9
     444  444.89  444.91  445.29  445.29  444.91  444.89   443.9
    4931    4931  5015.8  5018.3  5095.8  5098.3  5175.8  5178.3    5262    5262
    5369    7520    7642    7642  7710.8  7713.3  7830.8  7833.3    7915    7915
    8024    9450    9451    9508    9593    9639    9720    9791    9820    9820
    9830  9910.8  9913.3  9990.8  9993.3 10070.8 10073.3   10164
   450.5   450.7  451.69  451.71  452.09  452.09  451.71  451.69   450.7   450.5
   450.5   450.5   450.5   451.1  451.89   451.9   451.9  451.89   451.1   450.5
   450.5   450.5     444   444.5   445.2   445.7   447.2   448.3   448.6   451.2
   451.3  451.89  451.91  452.29  452.29  451.91  451.89   450.9
   450.5  443.78  444.69  444.71  445.09  445.09  444.71  444.69  443.78   450.5
   450.5   450.5   450.5  444.29  444.89   443.7   443.7  444.89  444.29   450.5
   450.5   450.5     444   444.5   445.2   445.7   447.2   448.3   448.6   443.9
     444  444.89  444.91  445.29  445.29  444.91  444.89   443.9
Pier Skew, UpSta & Num, DnSta & Num=  ,5017.05, 2 ,5017.05, 2 , 0 , 0 , 0 ,,
     2.5     2.5
     430     450
     2.5     2.5
     430     450
Pier Skew, UpSta & Num, DnSta & Num=  ,5097.05, 2 ,5097.05, 2 , 0 , 0 , 0 ,,
     2.5     2.5
     430     450
     2.5     2.5
     430     450
Pier Skew, UpSta & Num, DnSta & Num=  ,5177.05, 2 ,5177.05, 2 , 0 , 0 , 0 ,,
     2.5     2.5
     430     450
     2.5     2.5
     430     450
Pier Skew, UpSta & Num, DnSta & Num=  ,7712.05, 2 ,7712.05, 2 , 0 , 0 , 0 ,,
     2.5     2.5
     410     450
     2.5     2.5
     410     450
Pier Skew, UpSta & Num, DnSta & Num=  ,7832.05, 2 ,7832.05, 2 , 0 , 0 , 0 ,,
     2.5     2.5
     410     450
     2.5     2.5
     410     450
Pier Skew, UpSta & Num, DnSta & Num=  ,9912.05, 2 ,9912.05, 2 , 0 , 0 , 0 ,,
     2.5     2.5
     410     450
     2.5     2.5
     410     450
Pier Skew, UpSta & Num, DnSta & Num=  ,9992.05, 2 ,9992.05, 2 , 0 , 0 , 0 ,,
     2.5     2.5
     410     450
     2.5     2.5
     410     450
Pier Skew, UpSta & Num, DnSta & Num=  ,10072.05, 2 ,10072.05, 2 , 0 , 0 , 0 ,,
     2.5     2.5
     410     450
     2.5     2.5
     410     450
BR Coef= 1 , 0 , 0 ,1.05, 0 ,,,0.8,-1,0.5,1,
WSPro=,,,, 1 ,,,, 0 ,,,, 0 ,,,,-1 ,-1 ,-1 , 0 , 0 , 0 , 0 , 0
BC Design=,, 0 ,, 0 ,,,,,,
BC HTab HWMax=450.5
BC Use User HTab Curves=0
BC User HTab FreeFlow(D)= 0

Type RM Length L Ch R = 1 ,87354   ,1,1,1
BEGIN DESCRIPTION:
This cross section corresponds to cross section 87339 of the non-georeferenced CDC model which was the source of this model.
END DESCRIPTION:
XS GIS Cut Line= 6
2454096.437968087033066.68066938 2451360.00446467032828.53350788
2450655.638419247032730.874910552448644.077809847032584.72428422
2447305.792756777032575.173778382444591.557699687032674.81465521
#Sta/Elev= 30
    1020   444.5    1096   424.9    1211   433.7    1232   450.5    4931   450.5
    4931  443.78    4936   439.3    5122   428.9    5255   437.4    5262  443.78
    5262   450.5    7642   450.5    7642  444.29    7659   439.3    7702     439
    7739   425.5    7757   408.4    7801   407.1    7851   412.4    7877   435.8
    7904   436.8    7915  444.18    7915   450.5    9820   450.5    9848   435.6
   10014   433.6   10120     436   10164   443.9   10164   450.5   10550   450.5
#Mann= 3 ,0,0
    1020    .055       0    7702     .05       0    7877    .055       0
#XS Ineff= 2 , 0
       0    4931     460               0
Permanent Ineff=
       F       F
Bank Sta=7702,7877
XS Rating Curve= 0 ,0
Exp/Cntr=0.5,0.3

Type RM Length L Ch R = 1 ,87353   ,99,146,258
BEGIN DESCRIPTION:
This cross section corresponds to cross section 87338 of the non-georeferenced CDC model which was the source of this model.
END DESCRIPTION:
XS GIS Cut Line= 6
  2454105.186966 7033067.3151826 2451356.5897733 7032827.4649405
 2450652.3930189 7032729.6787187 2448100.9394604 7032577.6547446
 2445703.8589528 7032630.5614629 2439097.1060902 7032909.7754714
#Sta/Elev= 30
    1007   448.4    1096   424.9    1247   442.1    1548   444.7    2787   444.8
    2965   430.2    3021   442.9    3495   448.7    4837   443.3    5122   428.9
    5255   437.4    5270   450.5    7620   450.5    7702     439    7757   408.4
    7801   407.1    7851   412.4    7877   435.8    7904   436.8    7924   450.5
    9820   450.5    9848   435.6   10014   433.6   10531   443.8   13917   450.7
   15418   443.4   15767   450.8   15836     440   15876   451.3   16046   450.5
#Mann= 3 ,0,0
    1007     .07       0    7702    .055       0    7877     .07       0
#XS Ineff= 2 , 0
       0    4925     450               0
Permanent Ineff=
       F       F
Bank Sta=7702,7877
XS Rating Curve= 0 ,0
Exp/Cntr=0.3,0.1

Type RM Length L Ch R = 1 ,87207   ,308,408,390
BEGIN DESCRIPTION:
This cross section corresponds to cross section 87191 of the non-georeferenced CDC model which was the source of this model.
---------------------------------------------------------------------
UPSTREAM END OF CDC COP082301-1 DEVELOPMENT AT 1550 E. BELT LINE ROAD.
CROSS-SECTION 86107 - 87191
---------------------------------------------------------------------
END DESCRIPTION:
XS GIS Cut Line= 6
   2454060.74775 7032917.9004551 2450850.1058781 7032670.0259509
 2450173.5688453 7032553.5389791 2448224.0310777 7032416.5881376
 2443228.3750586 7032535.8631615 2439047.8611099 7032583.4418065
#Sta/Elev= 30
    1007   448.4    1096   424.9    1247   442.1    1548   444.7    2787   444.8
    2891   443.6    2965   430.2    3021   442.9    3495   448.7    4837   443.3
    5122   428.9    5255   437.4    5330   434.6    5330     450    7570     450
    7570   442.7    7702     439    7739   425.5    7757   408.4    7801     407
    7851   412.4    7877   435.8    9871   432.5   10531   443.8   13917   450.7
   15418   443.4   15767   450.8   15836     440   15876   451.3   16046   450.5
#Mann= 5 ,-1,0
    1007    .055       0    5255     .05       0    7570      .1       0
    7702    .055       0    7877     .07       0
#XS Ineff= 2 , 0
       0    4900     450               0
Permanent Ineff=
       F       F
Bank Sta=7702,7877
XS Rating Curve= 0 ,0
Exp/Cntr=0.3,0.1

Type RM Length L Ch R = 1 ,86799   ,140,166,166
BEGIN DESCRIPTION:
This cross section corresponds to cross section 86793 of the non-georeferenced CDC model which was the source of this model.
XS 86799 to 87207 retored to 1991 topo to remove project COP 082310-01
END DESCRIPTION:
XS GIS Cut Line= 5
  2453906.375684 7032326.3898271 2453299.8099682 7032460.7291254
 2447409.0589544 7032071.9759659 2442924.8950225 7032155.9000106
 2442570.1162045 7031975.0332464
#Sta/Elev= 30
    1007   447.9    1083   422.4    1183   422.6    1229   441.5    1433   443.5
    1771   435.5    2653   442.6    2754   429.2    2865   443.4    4713   439.4
    4952   428.9    5079   437.5    5265   428.9    5337   442.3    5430   442.3
    5430     450    7411   442.1    7713   435.6    7764   408.4    7808  406.51
    7945   440.3  8366.6   427.2  8918.4   442.4  8974.8     442    8990     430
    9411     430   10120   442.8   11902   446.3   12213   427.8   12415   449.9
#Mann= 6 ,-1,0
    1007    .065       0    4713    .055       0    5079     .05       0
    7411      .1       0    7713    .055       0    7945     .07       0
#XS Ineff= 2 , 0
       0    4560     450               0
Permanent Ineff=
       F       F
Bank Sta=7713,7945
XS Rating Curve= 0 ,0
Exp/Cntr=0.3,0.1

Type RM Length L Ch R = 1 ,86633   ,431,510,1114
BEGIN DESCRIPTION:
This cross section corresponds to cross section 86551 of the non-georeferenced CDC model which was the source of this model.
END DESCRIPTION:
XS GIS Cut Line= 6
2454012.779178877032283.428838422453713.343142387032265.04242904
2452715.223020747032203.754397792448004.311044757031914.48809189
2446014.163122187031915.053707552442816.607098677031620.84253979
#Sta/Elev= 30
     700     443    4362     443    4497     442    4793     431    4861     435
    5063     429    5135     438    5227     438    5227     443    5394     443
    5434     450    5960     450    7196     450    7213     438    7340     437
    7496     434    7527     423    7549     408    7585     406    7617     409
    7647     424    7707     439    7737     439    7797     439    7843     428
    8380     426    9661     431    9872     440    9921     446   11921     446
#Mann= 6 ,-1,0
     700    .065       0    4362    .065       0    4497    .055       0
    4793     .05       0    5960    .055       0    7843     .07       0
Bank Sta=7340,7737
XS Rating Curve= 0 ,0
Exp/Cntr=0.3,0.1