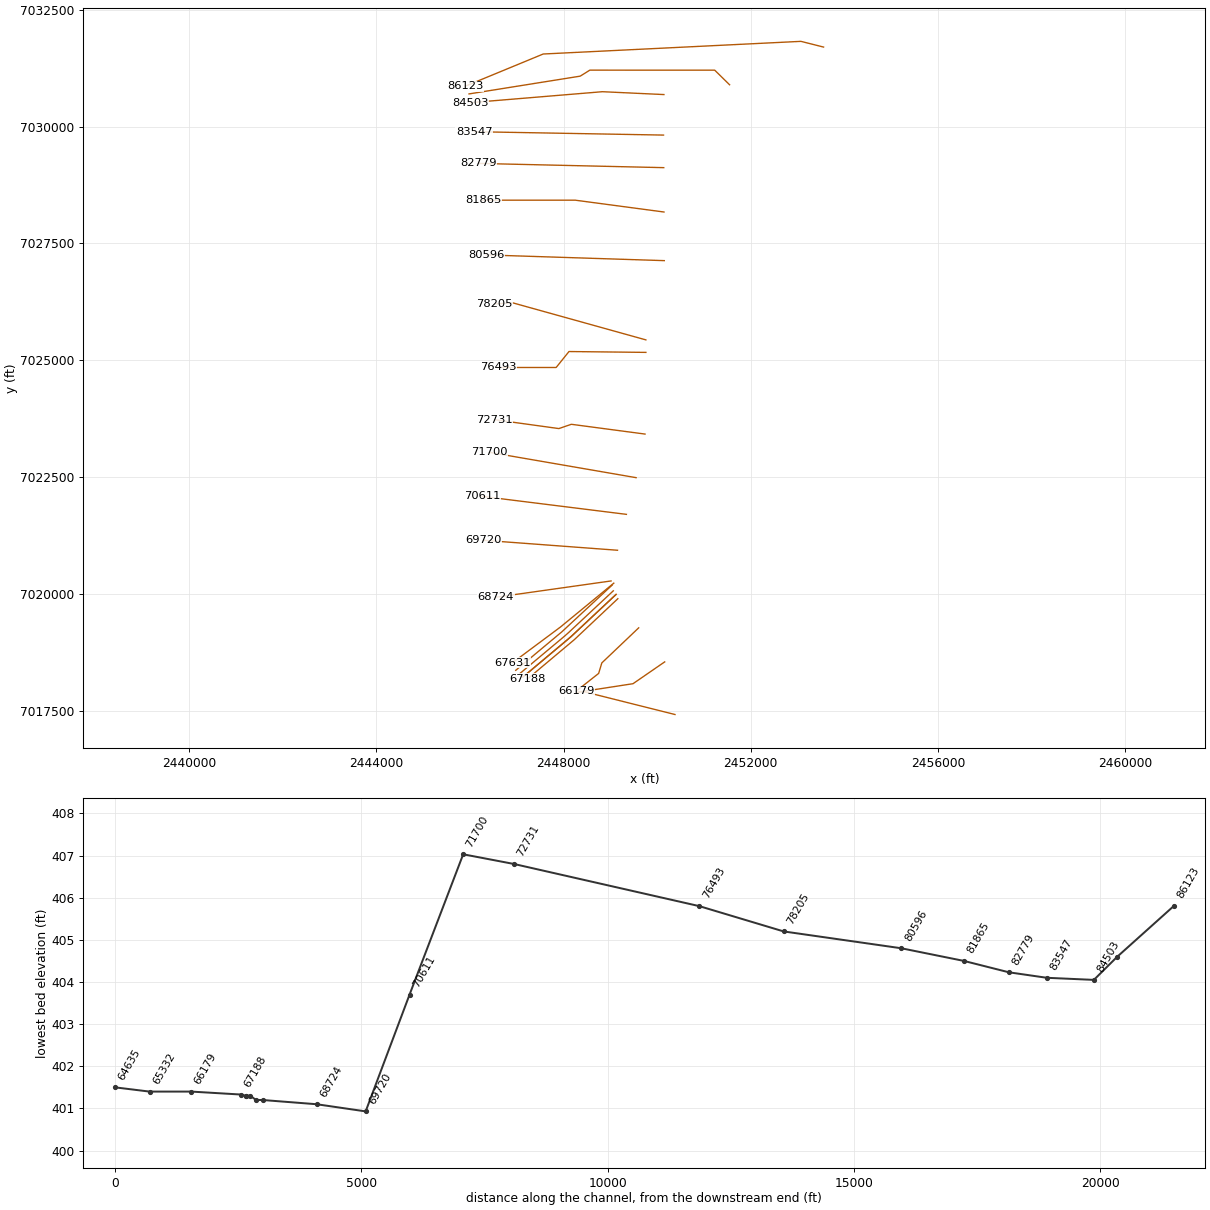
HEC-RAS study CDC_Consolidated_Model.prj: Upper Trinity CDC Consolidated Model

--- CDC_Consolidated_Model.g02 (geometry) --- (continued)

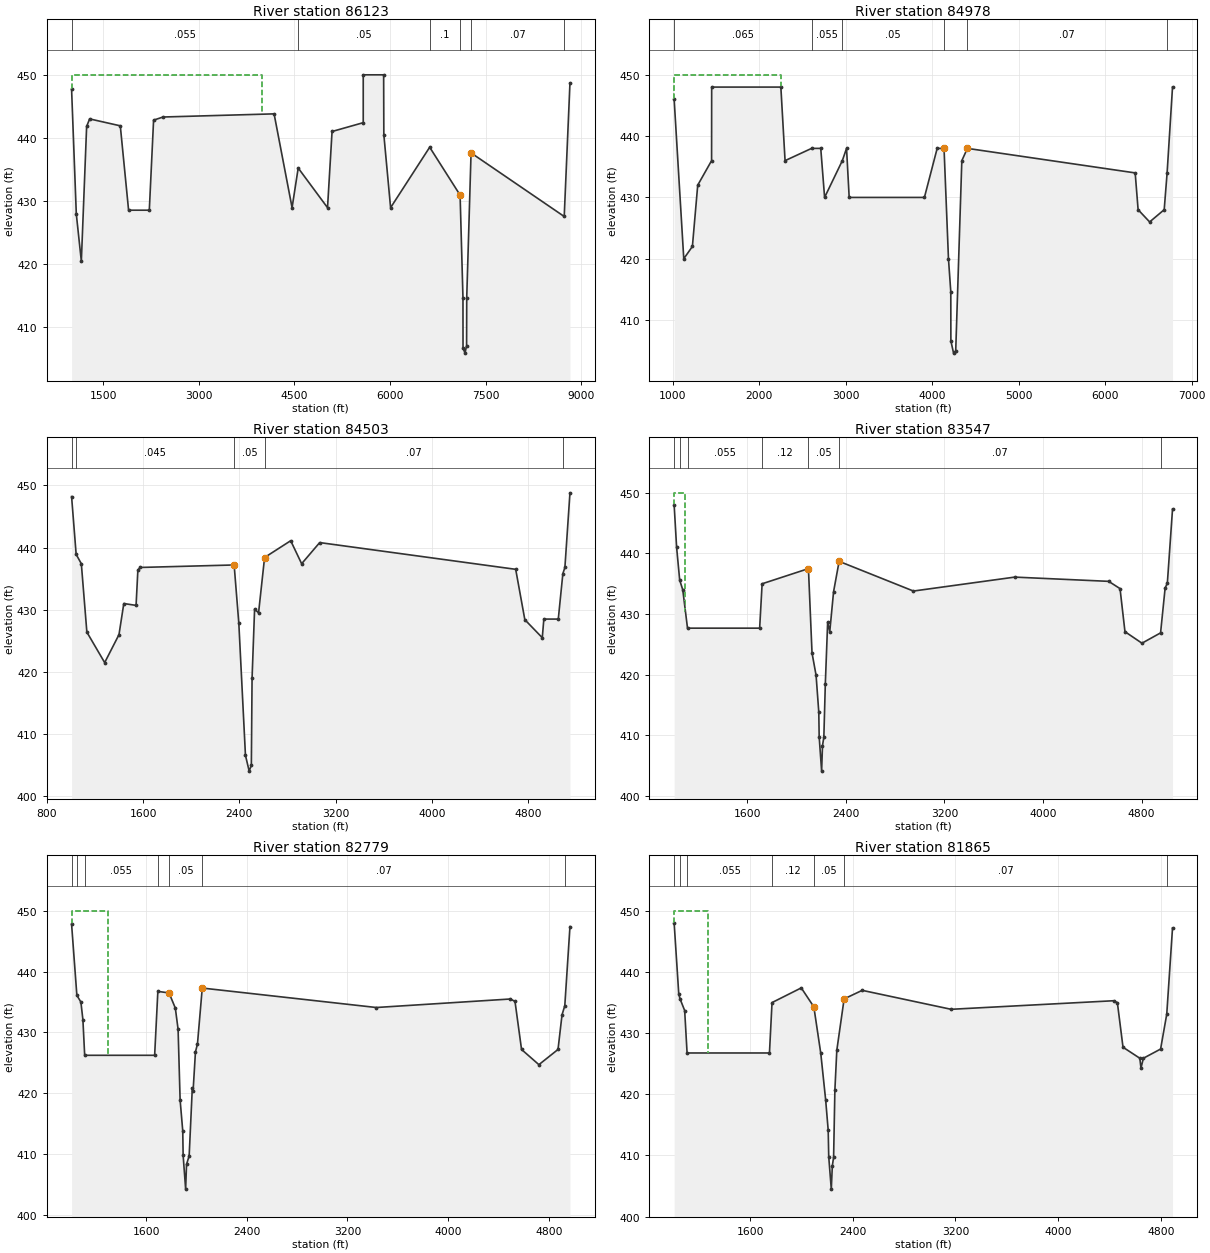
Type RM Length L Ch R = 1 ,86123   ,479,1145,299
BEGIN DESCRIPTION:
This cross section corresponds to cross section 86107 of the non-georeferenced CDC model which was the source of this model.
---------------------------------------------------------------------
DOWNSTREAM END OF CDC COP082301-1 DEVELOPMENT AT 1550 E. BELT LINE ROAD.
CROSS-SECTION 86107 - 87191
---------------------------------------------------------------------
END DESCRIPTION:
XS GIS Cut Line= 4
2453555.21398494 7031698.60040032453070.766134927031820.77404046
2447563.644931357031550.248990972445897.360862347030862.53908031
#Sta/Elev= 30
    1006   447.7    1080   427.9    1159   420.4    1242   441.8    1289     443
    1770   441.9    1900   428.5    2225   428.5    2292   442.8    2440   443.3
    4182   443.8    4464   428.9    4560   435.2    5020   428.9    5091     441
    5580   442.4    5580     450    5900     450    5903   440.5    6009   428.9
    6622   438.5    7099   430.9    7144   414.6    7145   406.6    7176   405.8
    7201     407    7203   414.6    7271   437.6    8732   427.5    8822   448.7
#Mann= 6 ,-1,0
    1006    .055       0    4560     .05       0    6622      .1       0
    7099     .05       0    7271     .07       0    8732     .03       0
#XS Ineff= 2 , 0
       0    4000     450               0
Permanent Ineff=
       F       F
Bank Sta=7099,7271
XS Rating Curve= 0 ,0
Exp/Cntr=0.3,0.1

Type RM Length L Ch R = 1 ,84978   ,512,475,221
BEGIN DESCRIPTION:
This cross section corresponds to cross section 84959 of the non-georeferenced CDC model which was the source of this model.
END DESCRIPTION:
XS GIS Cut Line= 5
 2451546.38565357030892.684361222451228.805908087031204.77297588
  2448559.7479267031205.354995712448354.105948847031077.09901863
  2445978.1664757030697.18212755
#Sta/Elev= 30
  1016.1     446  1127.3     420  1227.1     422  1288.7     432    1449     436
    1450     448    2250     448  2298.6     436  2605.3     438  2711.4     438
  2755.8     430  2960.7     436  3009.5     438    3040     430    3910     430
  4057.5     438  4136.9     438  4188.1     420    4215   414.6    4216   406.6
    4247   404.6    4272     405  4342.6     436  4407.1     438  6347.1     434
    6381     428  6514.3     426  6682.7     428  6716.3     434  6778.9     448
#Mann= 6 ,-1,0
  1016.1    .065       0  2605.3    .055       0  2960.7     .05       0
  4136.9    .055       0  4407.1     .07       0  6716.3     .03       0
#XS Ineff= 2 , 0
       0    2250     450               0
Permanent Ineff=
       F       F
Bank Sta=4136.9,4407.1
XS Rating Curve= 0 ,0
Exp/Cntr=0.3,0.1

Type RM Length L Ch R = 1 ,84503   ,900,956,650
BEGIN DESCRIPTION:
This cross section corresponds to cross section 84436 of the non-georeferenced CDC model which was the source of this model.
END DESCRIPTION:
XS GIS Cut Line= 3
2450143.405519847030683.264832562448828.647978757030744.41595696
2446012.520736997030510.55126722
#Sta/Elev= 30
    1006   448.2    1044   438.9    1087   437.4    1133   426.4    1281   421.5
    1400     426    1440     431    1542   430.7    1557   436.4    1576   436.8
    2357   437.2    2396   427.8    2451   406.6    2482  404.05    2500     405
    2506     419    2527   430.1    2560   429.5    2610   438.4    2827   441.1
    2918   437.4    3068   440.8    4697   436.5    4773   428.4    4918   425.5
    4931   428.5    5051   428.5    5089   435.8    5106   436.8    5148   448.8
#Mann= 5 ,-1,0
    1006     .03       0    1044    .045       0    2357     .05       0
    2610     .07       0    5089     .03       0
Bank Sta=2357,2610
XS Rating Curve= 0 ,0
Exp/Cntr=0.3,0.1

Type RM Length L Ch R = 1 ,83547   ,700,768,690
BEGIN DESCRIPTION:
This cross section corresponds to cross section 83530 of the non-georeferenced CDC model which was the source of this model.
END DESCRIPTION:
XS GIS Cut Line= 2
2450134.949828097029817.165514892446090.594727847029889.38584289
#Sta/Elev= 30
    1006     448    1026     441    1051   435.6    1076     434  1114.4  427.68
    1700  427.68    1720     435    2096   437.5    2125   423.6    2158   419.9
    2180   413.8    2183   409.8    2203   404.1    2210   408.3    2221   409.7
    2233   418.5    2252   428.7    2269   427.1    2300   433.7    2345   438.7
    2948   433.8    3770   436.1    4533   435.4    4625   434.2    4665   427.1
    4803   425.2    4954   426.9    4991   434.3    5009   435.1    5051   447.3
#Mann= 7 ,-1,0
    1006     .03       0    1051    .045       0  1114.4    .055       0
    1720     .12       0    2096     .05       0    2345     .07       0
    4954     .03       0
#XS Ineff= 2 , 0
       0    1098     450               0
Permanent Ineff=
       F       F
Bank Sta=2096,2345
XS Rating Curve= 0 ,0
Exp/Cntr=0.3,0.1

Type RM Length L Ch R = 1 ,82779   ,920,914,780
BEGIN DESCRIPTION:
This cross section corresponds to cross section 82762 of the non-georeferenced CDC model which was the source of this model.
END DESCRIPTION:
XS GIS Cut Line= 2
2450139.973768177029120.920844382446178.006298427029211.37670022
#Sta/Elev= 30
    1006   447.8    1048   436.1    1080     435    1096   432.1 1110.11  426.24
 1666.53  426.24    1692  436.75    1781   436.5    1831     434    1853   430.5
    1869   418.9    1890   413.8    1893   409.8    1913  404.23    1920   408.3
    1941   409.7    1966   420.9    1972   420.3    1991   426.8    2007   428.1
    2045   437.3    3429   434.1    4496   435.5    4532   435.1    4584   427.2
    4722   424.7    4874   427.2    4906   432.9    4928   434.4    4969   447.4
#Mann= 7 ,-1,0
    1006     .03       0    1048    .045       0 1110.11    .055       0
    1692     .12       0    1781     .05       0    2045     .07       0
    4928     .03       0
#XS Ineff= 2 , 0
       0    1298     450               0
Permanent Ineff=
       F       F
Bank Sta=1781,2045
XS Rating Curve= 0 ,0
Exp/Cntr=0.3,0.1

Type RM Length L Ch R = 1 ,81865   ,1090,1269,1200
BEGIN DESCRIPTION:
This cross section corresponds to cross section 81848 of the non-georeferenced CDC model which was the source of this model.
END DESCRIPTION:
XS GIS Cut Line= 3
2450144.67126533 7028172.55627132448247.31088683 7028425.5380488
2446276.46246633 7028425.5380488
#Sta/Elev= 30
    1007     448    1043   436.4    1053   435.6    1089   433.7  1107.8  426.76
    1750  426.76    1770     435    1998   437.4    2096   434.3    2150   426.7
    2188   419.1    2208   414.1    2212   409.8    2232   404.5    2240   408.3
    2250   409.7    2260   420.7    2275   427.2    2332   435.6    2473     437
    3166   433.9    4432   435.3    4462     435    4506   427.7    4637   425.9
    4646   424.3    4665   425.9    4799   427.4    4847   433.1    4892   447.2
#Mann= 7 ,-1,0
    1007     .03       0    1053    .045       0  1107.8    .055       0
    1770     .12       0    2096     .05       0    2332     .07       0
    4847     .03       0
#XS Ineff= 2 , 0
       0    1274     450               0
Permanent Ineff=
       F       F
Bank Sta=2096,2332
XS Rating Curve= 0 ,0
Exp/Cntr=0.3,0.1

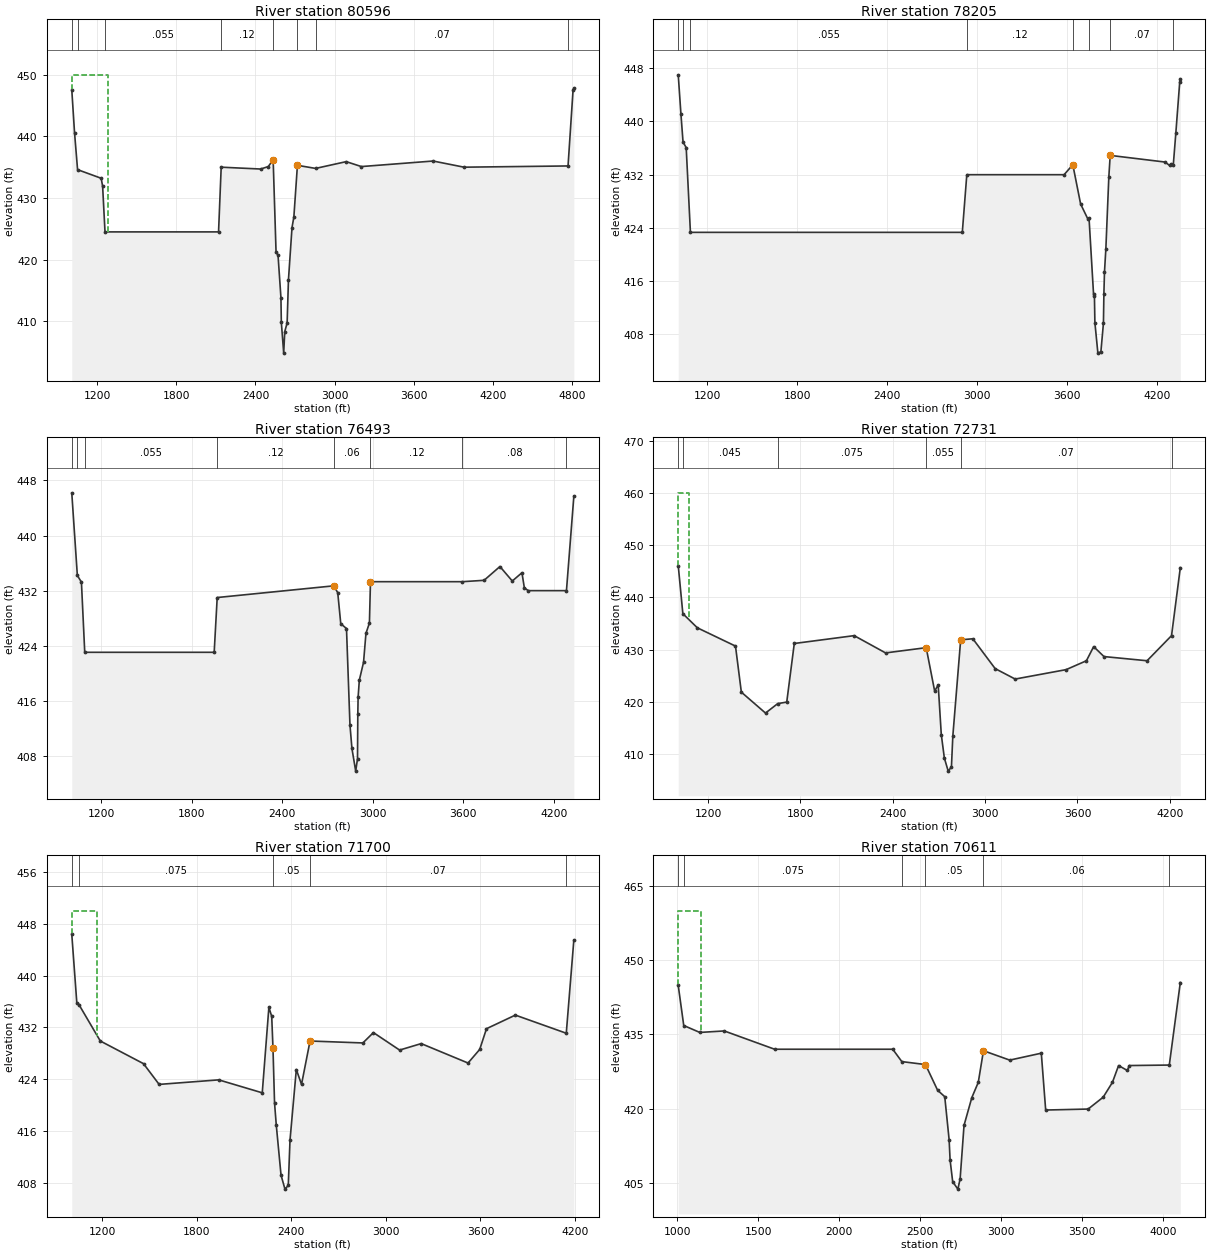
Type RM Length L Ch R = 1 ,80596   ,1599,2391,1030
BEGIN DESCRIPTION:
This cross section corresponds to cross section 80579 of the non-georeferenced CDC model which was the source of this model.
END DESCRIPTION:
XS GIS Cut Line= 2
2450151.002617517027133.076722962446345.963639687027255.25626864
#Sta/Elev= 30
    1007   447.6    1028   440.6    1051   434.6    1230   433.2    1241   431.9
    1259  424.49    2120  424.49    2140     435    2439   434.7    2497   435.1
    2534   436.2    2556   421.2    2571   420.7    2593   413.8    2596   409.8
    2614   404.8    2622   408.3    2640   409.7    2650   416.7    2677   425.2
    2691   426.9    2718   435.3    2856   434.8    3088   435.9    3203   435.1
    3747     436    3981     435    4770   435.2    4808   447.5    4814   447.8
#Mann= 8 ,-1,0
    1007     .03       0    1051    .045       0    1259    .055       0
    2140     .12       0    2534    .055       0    2718     .12       0
    2856     .07       0    4770     .03       0
#XS Ineff= 2 , 0
       0    1279     450               0
Permanent Ineff=
       F       F
Bank Sta=2534,2718
XS Rating Curve= 0 ,0
Exp/Cntr=0.3,0.1

Type RM Length L Ch R = 1 ,78205   ,800,1712,1380
BEGIN DESCRIPTION:
This cross section corresponds to cross section 78187 of the non-georeferenced CDC model which was the source of this model.
END DESCRIPTION:
XS GIS Cut Line= 3
2449757.539821747025438.934770052446916.428049927026229.58115463
2446522.145373917026207.05101597
#Sta/Elev= 30
    1008     447    1026   441.1    1040   436.9    1061  436.07 1089.14  423.34
    2900  423.34    2930     432    3578     432    3636   433.5    3688   427.6
    3735   425.4    3744   425.5    3774   414.1    3780   413.8    3783   409.8
    3803   405.2    3823   405.4    3840   409.7    3843   414.1    3847   417.4
    3856   420.8    3876   431.7    3885   434.9    4250   433.9    4280   433.4
    4289   433.6    4305   433.4    4322   438.2    4348   445.9    4352   446.4
#Mann= 8 ,-1,0
    1008     .03       0    1040    .045       0 1089.14    .055       0
    2930     .12       0    3636     .12       0    3744    .055       0
    3885     .07       0    4305     .03       0
Bank Sta=3636,3885
XS Rating Curve= 0 ,0
Exp/Cntr=0.3,0.1

Type RM Length L Ch R = 1 ,76493   ,1740,3762,1200
BEGIN DESCRIPTION:
This cross section corresponds to cross section 76475 of the non-georeferenced CDC model which was the source of this model.
END DESCRIPTION:
XS GIS Cut Line= 4
2449757.729453927025171.567522632448114.222898427025189.82896905
2447839.728040587024848.789952962446593.120297587024848.78995296
#Sta/Elev= 30
    1006   446.2    1043   434.2    1070  433.24 1091.99  423.05    1950  423.05
    1970     431    2743   432.7    2769   431.7    2789   427.2    2827   426.5
    2850   412.5    2863   409.1    2888   405.8    2900   407.6    2902   414.1
    2904   416.5    2912     419    2940   421.6    2956   425.8    2979   427.3
    2986   433.3    3595   433.3    3739   433.5    3844   435.5    3926   433.4
    3990   434.6    4006   432.4    4032     432    4285     432    4334   445.7
#Mann= 8 ,-1,0
    1006     .03       0    1043    .045       0 1091.99    .055       0
    1970     .12       0    2743     .06       0    2986     .12       0
    3595     .08       0    4285     .03       0
Bank Sta=2743,2986
XS Rating Curve= 0 ,0
Exp/Cntr=0.3,0.1

Type RM Length L Ch R = 1 ,72731   ,940,1031,740
BEGIN DESCRIPTION:
This cross section corresponds to cross section 72713 of the non-georeferenced CDC model which was the source of this model.
END DESCRIPTION:
XS GIS Cut Line= 4
2449740.069056187023425.39581813 2448164.13093517023634.35898288
2447897.953974017023542.861134382446520.236257027023733.20392954
#Sta/Elev= 30
    1006   446.1    1036   436.9    1130   434.2    1378   430.7    1416   421.9
    1573   417.9    1652   419.7    1711     420    1760   431.2    2149   432.7
    2353   429.4    2617   430.4    2672   422.1    2695   423.3    2715   413.8
    2735   409.3    2760   406.8    2781   407.6    2790   413.5    2841   431.9
    2920   432.1    3065   426.4    3195   424.4    3526   426.2    3658   427.9
    3705   430.6    3772   428.7    4052   427.9    4211   432.7    4268   445.7
#Mann= 6 ,-1,0
    1006     .03       0    1036    .045       0    1652    .075       0
    2617    .055       0    2841     .07       0    4211     .03       0
#XS Ineff= 2 , 0
       0    1077     460               0
Permanent Ineff=
       F       F
Bank Sta=2617,2841
XS Rating Curve= 0 ,0
Exp/Cntr=0.3,0.1

Type RM Length L Ch R = 1 ,71700   ,850,1089,920
BEGIN DESCRIPTION:
This cross section corresponds to cross section 71682 of the non-georeferenced CDC model which was the source of this model.
END DESCRIPTION:
XS GIS Cut Line= 2
  2449549.1829557022493.442301472446411.683324527023035.61608589
#Sta/Elev= 30
    1008   446.4    1040   435.8    1054   435.5    1189   429.9    1463   426.4
    1562   423.2    1940   423.9    2216   421.9    2258   435.1    2276   433.7
    2284   428.8    2294   420.3    2305   416.9    2335   409.2    2360  407.03
    2381   407.6    2392   414.6    2432   425.5    2465   423.2    2519   429.9
    2854   429.6    2921   431.2    3087   428.5    3224   429.5    3521   426.5
    3595   428.6    3638   431.8    3821   433.9    4144   431.1    4192   445.5
#Mann= 5 ,-1,0
    1008     .03       0    1054    .075       0    2284     .05       0
    2519     .07       0    4144     .03       0
#XS Ineff= 2 , 0
       0    1171     450               0
Permanent Ineff=
       F       F
Bank Sta=2284,2519
XS Rating Curve= 0 ,0
Exp/Cntr=0.3,0.1

Type RM Length L Ch R = 1 ,70611   ,829,891,899
BEGIN DESCRIPTION:
This cross section corresponds to cross section 70593 of the non-georeferenced CDC model which was the source of this model.
END DESCRIPTION:
XS GIS Cut Line= 2
2449341.456992517021709.253253042446266.247591767022092.51364139
#Sta/Elev= 30
    1006   444.9    1040   436.8    1139   435.4    1290   435.7    1601     432
    2330     432    2386   429.5    2532   428.9    2607   423.7    2651   422.4
    2678   413.7    2684   409.6    2700   405.2    2732   403.7    2746   405.8
    2770   416.6    2818   422.2    2858   425.3    2890   431.7    3052   429.8
    3247   431.2    3274   419.7    3536   419.9    3629   422.3    3686   425.3
    3724   428.7    3778   427.7    3790   428.7    4037   428.8    4105   445.5
#Mann= 6 ,-1,0
    1006     .03       0    1040    .075       0    2386      .1       0
    2532     .05       0    2890     .06       0    4037     .03       0
#XS Ineff= 2 , 0
       0    1148     460               0
Permanent Ineff=
       F       F
Bank Sta=2532,2890
XS Rating Curve= 0 ,0
Exp/Cntr=0.3,0.1

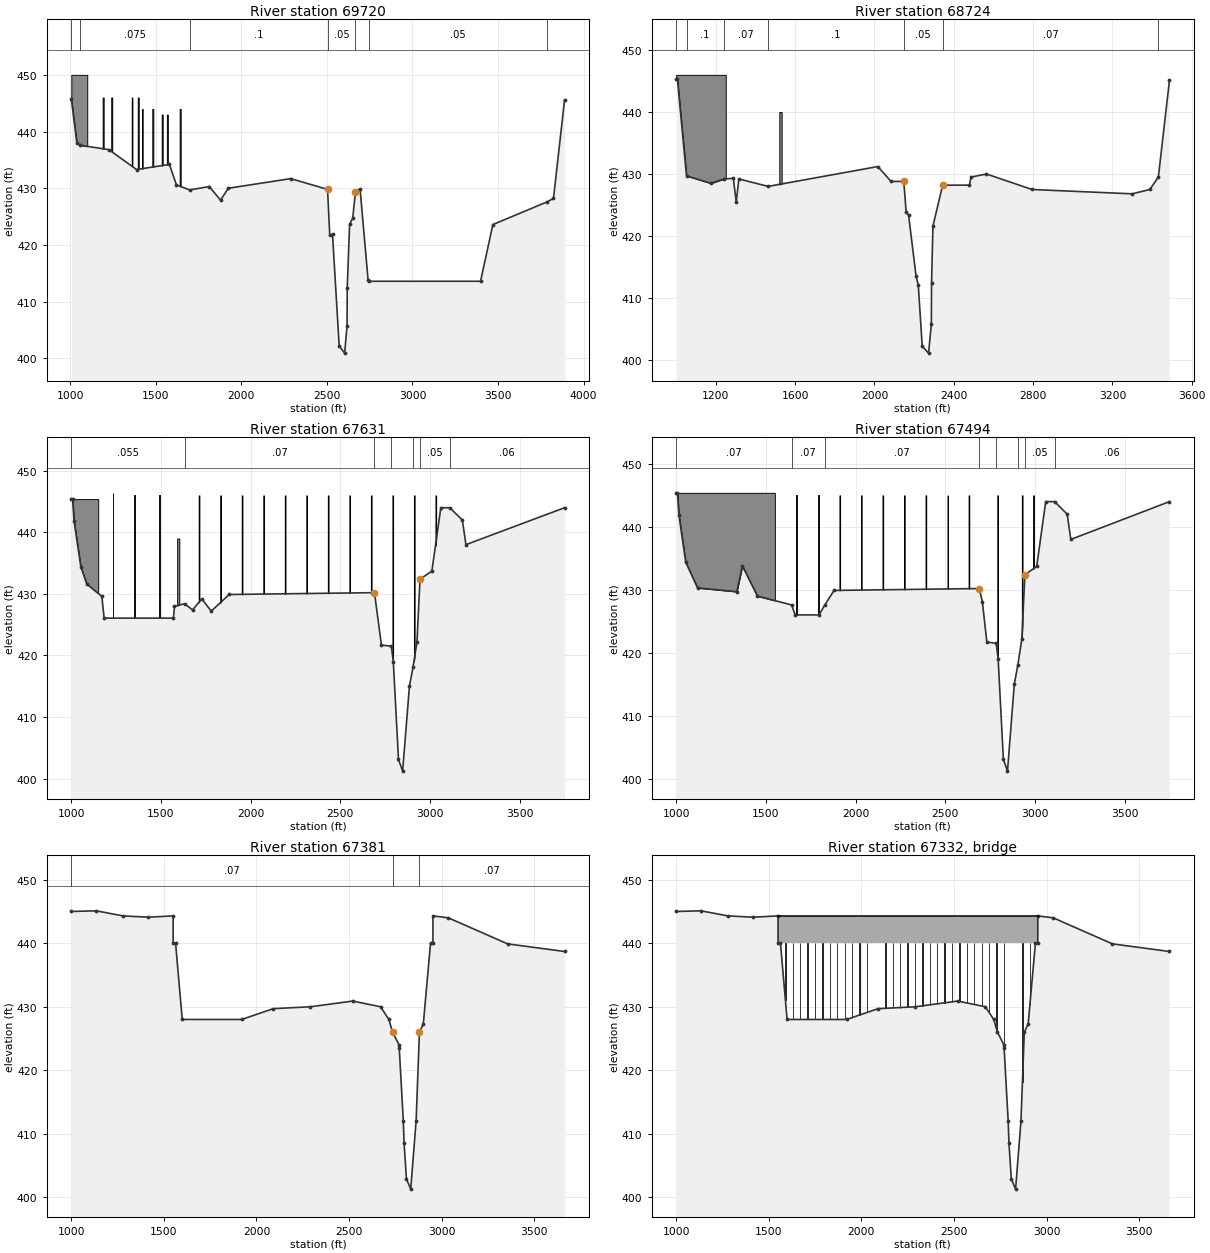
Type RM Length L Ch R = 1 ,69720   ,800,996,1100
BEGIN DESCRIPTION:
This cross section corresponds to cross section 69701 of the non-georeferenced CDC model which was the source of this model.
END DESCRIPTION:
XS GIS Cut Line= 2
2449151.346480347020941.635365712446277.318763857021155.84917614
#Sta/Elev= 30
    1007   445.8    1039     438    1056   437.6    1227   436.8    1388   433.3
    1580   434.2    1621   430.6    1698   429.7    1813   430.3    1879   427.9
    1924     430    2289   431.7    2504   429.8    2517   421.7    2533   421.9
    2572   402.2    2604  400.93    2618   405.8    2619   412.4    2633   423.7
    2651   424.7    2667   429.3    2694   429.9    2741   413.8    2749   413.6
    3398   413.6    3470   423.6    3787   427.6    3824   428.2    3889   445.6
#Mann= 7 ,-1,0
    1007     .03       0    1056    .075       0    1698      .1       0
    2504     .05       0    2667      .1       0    2749     .05       0
    3787     .03       0
#Block Obstruct= 10 ,-1
    1007    1100     450    1190    1196     446    1240    1246     446
    1395    1401     446    1360    1364     446    1420    1424     444
    1480    1486     444    1535    1541     443    1565    1571     443
    1640    1646     444
#XS Lid=4
    1160     449     445    1620     445     441    1620   447.5   443.5
    1665   447.5   443.5
Bank Sta=2504,2667
XS Rating Curve= 0 ,0
Exp/Cntr=0.3,0.1

Type RM Length L Ch R = 1 ,68724   ,581,1093,1087
BEGIN DESCRIPTION:
This cross section corresponds to cross section 68705 of the non-georeferenced CDC model which was the source of this model.
END DESCRIPTION:
XS GIS Cut Line= 2
2449013.525889847020285.36108771 2446550.06920267019936.75811039
#Sta/Elev= 30
    1000   445.3    1006   445.3    1052   429.7    1175   428.5    1240   429.2
    1288   429.3    1303   425.5    1316   429.2    1464     428    2017   431.2
    2084   428.8    2148   428.8    2160   423.8    2172   423.4    2210   413.5
    2221   412.1    2241   402.2    2273   401.1    2287   405.8    2288   412.4
    2295   421.6    2344   428.2    2479   428.2    2487   429.5    2565     430
    2795   427.5    3300   426.8    3389   427.5    3432   429.5    3488   445.1
#Mann= 7 ,-1,0
    1000     .03       0    1052      .1       0    1240     .07       0
    1464      .1       0    2148     .05       0    2344     .07       0
    3432     .03       0
#Block Obstruct= 2 ,-1
    1000    1250     446    1520    1532     440
#XS Lid=2
    1490  441.63  437.46    1570  446.11  441.94
Bank Sta=2148,2344
XS Rating Curve= 0 ,0
Exp/Cntr=0.3,0.1

Type RM Length L Ch R = 1 ,67631   ,166,137,161
BEGIN DESCRIPTION:
This cross section corresponds to cross section 67474 of the non-georeferenced CDC model which was the source of this model.
END DESCRIPTION:
XS GIS Cut Line= 3
2449072.05825308 7020238.17450232447929.897151597019298.86306071
  2446910.4126427018539.51418571
#Sta/Elev= 30
    1000   445.4    1007   445.4    1015   441.9    1053   434.4    1086   431.6
    1170   429.6 1182.88  426.06 1569.37  426.06 1575.14  427.99    1631   428.4
    1676   427.4    1727   429.2    1780   427.2    1880   429.9    2690   430.2
 2728.77  421.68    2784   421.5    2795     419    2824   403.1    2847   401.2
    2885     415    2905   418.1    2927   422.2    2944   432.4    3010   433.7
    3060     444    3110     444    3180     442    3200     438    3750     444
#Mann= 7 ,-1,0
    1000    .055       0    1631     .07       0    2690     .05       0
    2784     .05       0    2905     .07       0    2944     .05       0
    3110     .06       0
#Block Obstruct= 17 ,-1
    1000    1150   445.4    1230    1234  446.42    1350    1354     446
    1490    1494     446    1590    1602     439    1710    1714     446
    1830    1834     446    1950    1954     446    2070    2074     446
    2190    2194     446    2310    2314     446    2430    2434     446
    2550    2554     446    2670    2674     446    2790    2794     446
    2910    2914     446    3030    3034     446
#XS Lid=2
    1554  440.97   436.8    1634  444.33  440.16
Bank Sta=2690,2944
XS Rating Curve= 0 ,0
Exp/Cntr=0.3,0.1

Type RM Length L Ch R = 1 ,67494   ,113,113,113
BEGIN DESCRIPTION:
This cross section corresponds to cross section 67474 of the non-georeferenced CDC model which was the source of this model.
---------------------------------------------------------------------
CDC CAR012102-1 President George Bush Turnpike
Cross-section 67474 - 110074
---------------------------------------------------------------------
END DESCRIPTION:
XS GIS Cut Line= 3
2449035.995989267020196.284166132447959.731081437019196.17199314
2446976.700567197018375.14804463
#Sta/Elev= 30
    1000   445.4    1007   445.4    1015   441.9    1053   434.4    1119   430.3
    1338   429.7    1369   433.8    1453     429    1643   427.6  1663.4  426.01
 1796.24  426.01 1827.56  427.54    1880   429.9    2690   430.2 2707.26  428.04
 2731.85   421.7    2784   421.5    2795     419    2824   403.1    2847   401.2
    2885     415    2905   418.1    2927   422.2    2944   432.4    3010   433.7
    3060     444    3110     444    3180     442    3200     438    3750     444
#Mann= 8 ,-1,0
    1000     .07       0    1643     .07       0 1827.56     .07       0
    2690     .05       0    2784     .05       0    2905     .07       0
    2944     .05       0    3110     .06       0
#Block Obstruct= 13 ,-1
    1000    1550   445.4    1670    1674     445    1790    1794     445
    1910    1914     445    2030    2034     445    2150    2154     445
    2270    2274     445    2390    2394     445 2513.51    2514     445
    2630    2634     445    2790    2794     445    2927    2931     445
    2990    2994     445
Bank Sta=2690,2944
XS Rating Curve= 0 ,0
Exp/Cntr=0.3,0.1

Type RM Length L Ch R = 1 ,67381   ,98,98,98
BEGIN DESCRIPTION:
This cross section corresponds to cross section 67364 of the non-georeferenced CDC model which was the source of this model.
END DESCRIPTION:
XS GIS Cut Line= 4
2449061.80860168 7020074.49766432448108.346597857019184.48664905
2448027.991443577019112.388696132447067.966788837018309.14620814
#Sta/Elev= 30
    1000     445    1135   445.1    1279   444.3    1416   444.1    1550   444.3
    1550     440    1563     440    1599     428    1920     428    2090   429.7
    2291     430    2520   430.9    2670     430    2715     428    2735     426
    2769  424.06    2771   423.5    2793     412    2797   408.6    2810   402.9
    2833   401.3    2862     412    2880     426    2901   427.3    2940     440
    2953     440    2953   444.3    3036     444    3356   439.9    3664   438.7
#Mann= 3 ,0,0
    1000     .07       0    2735     .05       0    2880     .07       0
Bank Sta=2735,2880
XS Rating Curve= 0 ,0
Exp/Cntr=0.5,0.3

Type RM Length L Ch R = 3 ,67332   ,,,
BEGIN DESCRIPTION:
Valley View Lane
END DESCRIPTION:
Node Name=Valley View Lane
Bridge Culvert--1,0,-1,-1, 0
Deck Dist Width WeirC Skew NumUp NumDn MinLoCord MaxHiCord MaxSubmerge Is_Ogee
2,95,2.6,0, 49, 49, , , 0.95, 0, ,,,
    1550    1589    1591    1628    1632    1709    1711    1748    1752    1829
    1831    1868    1872    1949    1951    1989    1991    2029    2031    2129
    2131    2169    2171    2171    2208    2212    2289    2291    2328    2332
    2409    2411    2448    2452    2529    2531    2568    2572    2649    2651
    2688    2692    2769    2771    2869    2871    2909    2911    2953
   444.3   444.3   444.3   444.3   444.3   444.3   444.3   444.3   444.3   444.3
   444.3   444.3   444.3   444.3   444.3   444.3   444.3   444.3   444.3   444.3
   444.3   444.3   444.3   444.3   444.3   444.3   444.3   444.3   444.3   444.3
   444.3   444.3   444.3   444.3   444.3   444.3   444.3   444.3   444.3   444.3
   444.3   444.3   444.3   444.3   444.3   444.3   444.3   444.3   444.3
     440     440     440     440     440     440     440     440     440     440
     440     440     440     440     440     440     440     440     440     440
     440     440     440     440     440     440     440     440     440     440
     440     440     440     440     440     440     440     440     440     440
     440     440     440     440     440     440     440     440     440
    1550    1589    1591    1628    1632    1709    1711    1748    1752    1829
    1831    1868    1872    1949    1951    1989    1991    2029    2031    2129
    2131    2169    2171    2171    2208    2212    2289    2291    2328    2332
    2409    2411    2448    2452    2529    2531    2568    2572    2649    2651
    2688    2692    2769    2771    2869    2871    2909    2911    2953
   444.3   444.3   444.3   444.3   444.3   444.3   444.3   444.3   444.3   444.3
   444.3   444.3   444.3   444.3   444.3   444.3   444.3   444.3   444.3   444.3
   444.3   444.3   444.3   444.3   444.3   444.3   444.3   444.3   444.3   444.3
   444.3   444.3   444.3   444.3   444.3   444.3   444.3   444.3   444.3   444.3
   444.3   444.3   444.3   444.3   444.3   444.3   444.3   444.3   444.3
     440     440     440     440     440     440     440     440     440     440
     440     440     440     440     440     440     440     440     440     440
     440     440     440     440     440     440     440     440     440     440
     440     440     440     440     440     440     440     440     440     440
     440     440     440     440     440     440     440     440     440
Pier Skew, UpSta & Num, DnSta & Num=  ,1590, 2 ,1590, 2 , 0 , 0 , 0 ,,
       2       2
     410     442
       2       2
     410     442
Pier Skew, UpSta & Num, DnSta & Num=  ,1630, 2 ,1630, 2 , 0 , 0 , 0 ,,
       2       2
     410     442
       2       2
     410     442
Pier Skew, UpSta & Num, DnSta & Num=  ,1670, 2 ,1670, 2 , 0 , 0 , 0 ,,
       2       2
     410     442
       2       2
     410     442
Pier Skew, UpSta & Num, DnSta & Num=  ,1710, 2 ,1710, 2 , 0 , 0 , 0 ,,
       2       2
     410     442
       2       2
     410     442
Pier Skew, UpSta & Num, DnSta & Num=  ,1750, 2 ,1750, 2 , 0 , 0 , 0 ,,
       2       2
     410     442
       2       2
     410     442
Pier Skew, UpSta & Num, DnSta & Num=  ,1790, 2 ,1790, 2 , 0 , 0 , 0 ,,
       2       2
     410     442
       2       2
     410     442
Pier Skew, UpSta & Num, DnSta & Num=  ,1830, 2 ,1830, 2 , 0 , 0 , 0 ,,
       2       2
     410     442
       2       2
     410     442
Pier Skew, UpSta & Num, DnSta & Num=  ,1870, 2 ,1870, 2 , 0 , 0 , 0 ,,
       2       2
     410     442
       2       2
     410     442
Pier Skew, UpSta & Num, DnSta & Num=  ,1910, 2 ,1910, 2 , 0 , 0 , 0 ,,
       2       2
     410     442
       2       2
     410     442
Pier Skew, UpSta & Num, DnSta & Num=  ,1950, 2 ,1950, 2 , 0 , 0 , 0 ,,
       2       2
     410     442
       2       2
     410     442
Pier Skew, UpSta & Num, DnSta & Num=  ,1990, 2 ,1990, 2 , 0 , 0 , 0 ,,
       2       2
     410     442
       2       2
     410     442
Pier Skew, UpSta & Num, DnSta & Num=  ,2030, 2 ,2030, 2 , 0 , 0 , 0 ,,
       2       2
     410     442
       2       2
     410     442
Pier Skew, UpSta & Num, DnSta & Num=  ,2130, 2 ,2130, 2 , 0 , 0 , 0 ,,
       2       2
     410     442
       2       2
     410     442
Pier Skew, UpSta & Num, DnSta & Num=  ,2170, 2 ,2170, 2 , 0 , 0 , 0 ,,
       2       2
     410     442
       2       2
     410     442
Pier Skew, UpSta & Num, DnSta & Num=  ,2210, 2 ,2210, 2 , 0 , 0 , 0 ,,
       2       2
     410     442
       2       2
     410     442
Pier Skew, UpSta & Num, DnSta & Num=  ,2250, 2 ,2250, 2 , 0 , 0 , 0 ,,
       2       2
     410     442
       2       2
     410     442
Pier Skew, UpSta & Num, DnSta & Num=  ,2290, 2 ,2290, 2 , 0 , 0 , 0 ,,
       2       2
     410     442
       2       2
     410     442
Pier Skew, UpSta & Num, DnSta & Num=  ,2330, 2 ,2330, 2 , 0 , 0 , 0 ,,
       2       2
     410     442
       2       2
     410     442
Pier Skew, UpSta & Num, DnSta & Num=  ,2370, 2 ,2370, 2 , 0 , 0 , 0 ,,
       2       2
     410     442
       2       2
     410     442
Pier Skew, UpSta & Num, DnSta & Num=  ,2410, 2 ,2410, 2 , 0 , 0 , 0 ,,
       2       2
     410     442
       2       2
     410     442
Pier Skew, UpSta & Num, DnSta & Num=  ,2450, 2 ,2450, 2 , 0 , 0 , 0 ,,
       2       2
     410     442
       2       2
     410     442
Pier Skew, UpSta & Num, DnSta & Num=  ,2490, 2 ,2490, 2 , 0 , 0 , 0 ,,
       2       2
     410     442
       2       2
     410     442
Pier Skew, UpSta & Num, DnSta & Num=  ,2530, 2 ,2530, 2 , 0 , 0 , 0 ,,
       2       2
     410     442
       2       2
     410     442
Pier Skew, UpSta & Num, DnSta & Num=  ,2570, 2 ,2570, 2 , 0 , 0 , 0 ,,
       2       2
     410     442
       2       2
     410     442
Pier Skew, UpSta & Num, DnSta & Num=  ,2610, 2 ,2610, 2 , 0 , 0 , 0 ,,
       2       2
     410     442
       2       2
     410     442
Pier Skew, UpSta & Num, DnSta & Num=  ,2650, 2 ,2650, 2 , 0 , 0 , 0 ,,
       2       2
     410     442
       2       2
     410     442
Pier Skew, UpSta & Num, DnSta & Num=  ,2690, 2 ,2690, 2 , 0 , 0 , 0 ,,
       2       2
     410     442
       2       2
     410     442
Pier Skew, UpSta & Num, DnSta & Num=  ,2730, 2 ,2730, 2 , 0 , 0 , 0 ,,
       2       2
     410     442
       2       2
     410     442
Pier Skew, UpSta & Num, DnSta & Num=  ,2770, 2 ,2770, 2 , 0 , 0 , 0 ,,
       2       2
     410     442
       2       2
     410     442
Pier Skew, UpSta & Num, DnSta & Num=  ,2870, 2 ,2870, 2 , 0 , 0 , 0 ,,
       2       2
     410     442
       2       2
     410     442
Pier Skew, UpSta & Num, DnSta & Num=  ,2910, 2 ,2910, 2 , 0 , 0 , 0 ,,
       2       2
     410     442
       2       2
     410     442
BR Coef= 1 , 0 , 0 ,1.05, 0 ,,,0.8,-1,0.5,1,
WSPro=,,,, 1 ,,,, 0 ,,,, 0 ,,,,-1 ,-1 ,-1 , 0 , 0 , 0 , 0 , 0
BC Design=,, 0 ,, 0 ,,,,,,
BC HTab HWMax=445.1
BC Use User HTab Curves=0
BC User HTab FreeFlow(D)= 0

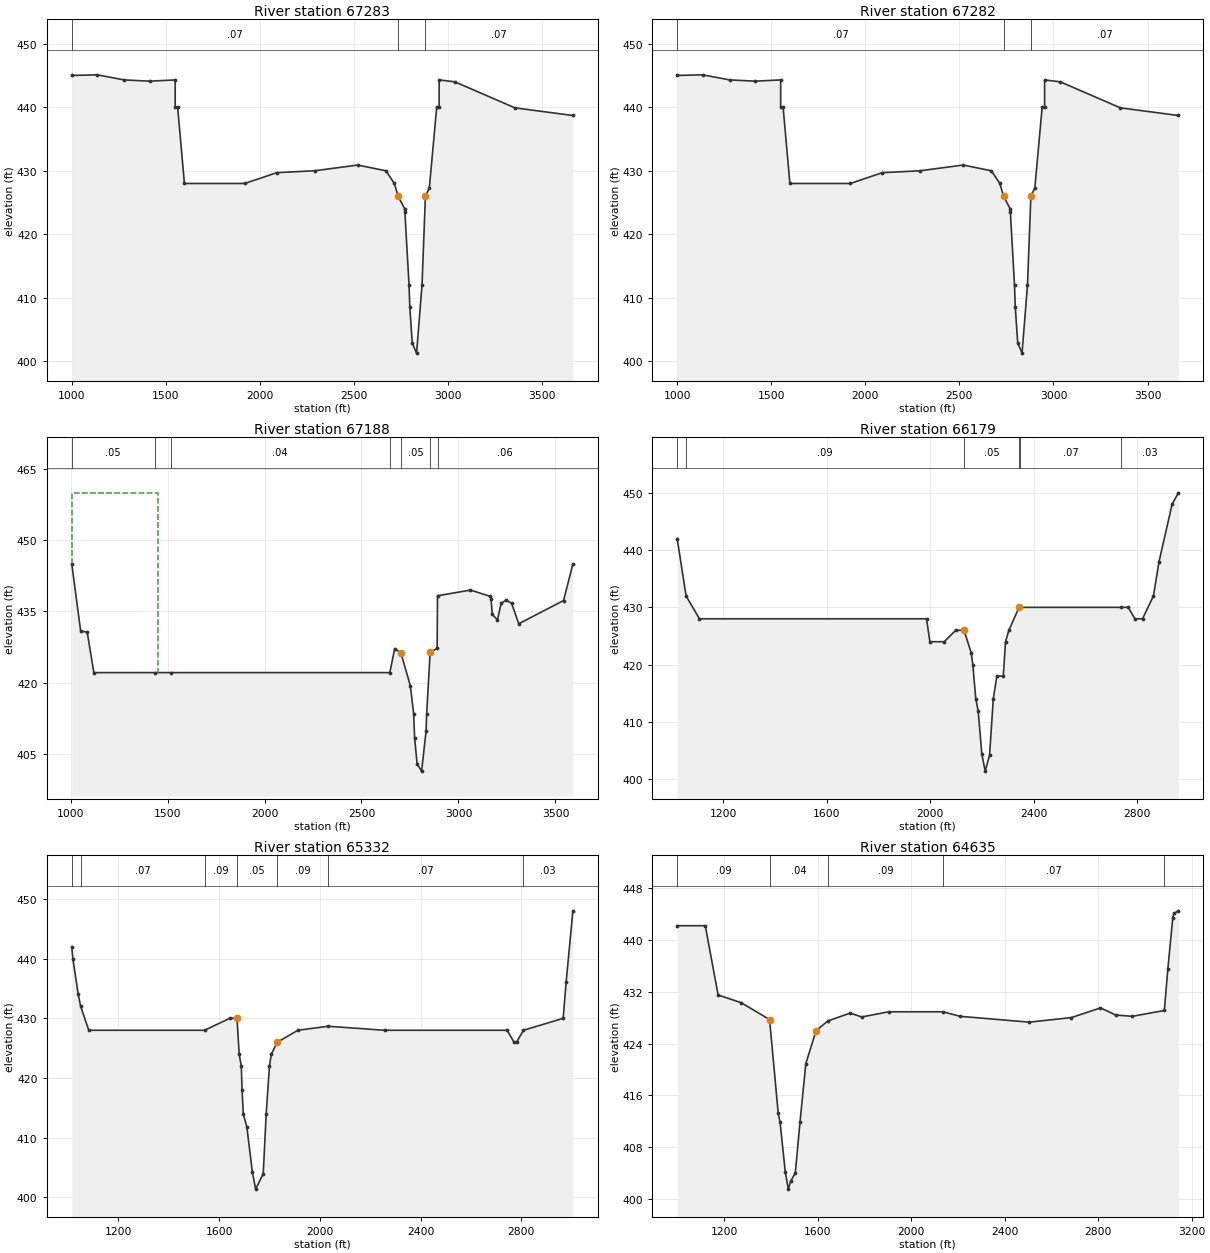
Type RM Length L Ch R = 1 ,67283   ,1,1,1
BEGIN DESCRIPTION:
This cross section corresponds to cross section 67265 of the non-georeferenced CDC model which was the source of this model.
END DESCRIPTION:
XS GIS Cut Line= 4
2449119.763210187019997.30195256  2448169.327447 7019106.3460573
2448089.431937527019036.988584472447127.216998437018230.56336005
#Sta/Elev= 30
    1000     445    1135   445.1    1279   444.3    1416   444.1    1550   444.3
    1550     440    1563     440    1599     428    1920     428    2090   429.7
    2291     430    2520   430.9    2670     430    2715     428    2735     426
    2769  424.06    2771   423.5    2793     412    2797   408.6    2810   402.9
    2833   401.3    2862     412    2880     426    2901   427.3    2940     440
    2953     440    2953   444.3    3036     444    3356   439.9    3664   438.7
#Mann= 3 ,0,0
    1000     .07       0    2735     .05       0    2880     .07       0
Bank Sta=2735,2880
XS Rating Curve= 0 ,0
Exp/Cntr=0.5,0.3

Type RM Length L Ch R = 1 ,67282   ,94,94,94
BEGIN DESCRIPTION:
This cross section corresponds to cross section 67264 of the non-georeferenced CDC model which was the source of this model.
END DESCRIPTION:
XS GIS Cut Line= 4
2449120.164128017019996.349854722448169.94555601 7019105.5586573
2448090.052671167019036.227103052447127.622509427018229.60732521
#Sta/Elev= 30
    1000     445    1135   445.1    1279   444.3    1416   444.1    1550   444.3
    1550     440    1563     440    1599     428    1920     428    2090   429.7
    2291     430    2520   430.9    2670     430    2715     428    2735     426
    2769  424.06    2771   423.5    2793     412    2797   408.6    2810   402.9
    2833   401.3    2862     412    2880     426    2901   427.3    2940     440
    2953     440    2953   444.3    3036     444    3356   439.9    3664   438.7
#Mann= 3 ,0,0
    1000     .07       0    2735     .05       0    2880     .07       0
Bank Sta=2735,2880
XS Rating Curve= 0 ,0
Exp/Cntr=0.3,0.1

Type RM Length L Ch R = 1 ,67188   ,769,1009,899
BEGIN DESCRIPTION:
This cross section corresponds to cross section 67169 of the non-georeferenced CDC model which was the source of this model.
---------------------------------------------------------------------
LOMR#14-06-2597P & CDC# FB100113-1 Mercer Crossing
Cross-sections 67169 & 62351.  Fill was added in innefective flow area so no physical cross-section change.
---------------------------------------------------------------------
END DESCRIPTION:
XS GIS Cut Line= 3
2449158.240167357019905.903185222448228.452000687019030.56504089
2447227.433005337018190.19861138
#Sta/Elev= 30
    1006   445.1    1052   430.9    1086   430.6    1120   422.1    1433   422.1
    1516   422.1    2646   422.1    2671   427.1    2703   426.3    2752   419.3
    2769   413.4    2774   408.3    2787   402.8    2810  401.33    2833   409.8
    2836   413.4    2854   426.4    2890   427.2    2892   438.3    3062   439.5
    3162   438.2    3168   437.7    3174   434.4    3201   433.2    3220   436.7
    3246   437.4    3274   436.7    3311   432.4    3542   437.3    3590     445
#Mann= 7 ,-1,0
    1006     .05       0    1433     .03       0    1516     .04       0
    2646     .08       0    2703     .05       0    2854     .08       0
    2892     .06       0
#XS Ineff= 2 , 0
       0    1450     460               0
Permanent Ineff=
       F       F
Bank Sta=2703,2854
XS Rating Curve= 0 ,0
Exp/Cntr=0.3,0.1

Type RM Length L Ch R = 1 ,66179   ,851,847,400
BEGIN DESCRIPTION:
This cross section corresponds to cross section 66159 of the non-georeferenced CDC model which was the source of this model.
END DESCRIPTION:
XS GIS Cut Line= 4
2449603.804564927019282.871622892448816.365851077018533.54306905
2448747.909951277018308.544175222448264.921087837017927.13942622
#Sta/Elev= 30
  1022.3     442  1056.6     432  1108.3     428  1986.3     428  1999.2     424
  2054.6     424  2099.3     426  2131.2     426  2159.4     422  2165.1     420
  2176.8     414    2186   411.9    2200   404.4    2213   401.4    2230   404.2
  2244.3     414  2258.1     418    2283     418  2291.7     424  2304.6     426
    2344     430  2349.3     430  2736.8     430  2766.1     430  2791.8     428
  2821.3     428  2863.6     432  2885.2     438  2935.7     448  2959.9     450
#Mann= 6 ,-1,0
  1022.3     .03       0  1056.6     .09       0  2131.2     .05       0
    2344     .09       0  2349.3     .07       0  2736.8     .03       0
Bank Sta=2131.2,2344
XS Rating Curve= 0 ,0
Exp/Cntr=0.3,0.1

Type RM Length L Ch R = 1 ,65332   ,951,697,351
BEGIN DESCRIPTION:
This cross section corresponds to cross section 65313 of the non-georeferenced CDC model which was the source of this model.
END DESCRIPTION:
XS GIS Cut Line= 3
2450159.545579437018554.918682472449482.115831917018088.76508722
2448328.394386087017910.71393414
#Sta/Elev= 30
  1014.7     442  1019.2     440  1040.5     434  1050.2     432  1082.5     428
  1541.9     428  1642.4     430  1670.9     430  1679.5     424  1687.9     422
  1690.9     418  1695.8     414    1710   411.8    1732   404.2    1745   401.4
    1775     404  1786.8  414.06  1799.8     422  1807.1     424  1830.8     426
  1912.7     428  2032.7  428.67  2256.5     428  2743.4     428  2770.7     426
  2780.6     426  2808.1     428  2965.8     430  2977.4     436  3004.4     448
#Mann= 7 ,-1,0
  1014.7     .03       0  1050.2     .07       0  1541.9     .09       0
  1670.9     .05       0  1830.8     .09       0  2032.7     .07       0
  2808.1     .03       0
Bank Sta=1670.9,1830.8
XS Rating Curve= 0 ,0
Exp/Cntr=0.3,0.1

Type RM Length L Ch R = 1 ,64635   ,131,131,131
BEGIN DESCRIPTION:
This cross section corresponds to cross section 64617 of the non-georeferenced CDC model which was the source of this model.
END DESCRIPTION:
XS GIS Cut Line= 3
2450379.504128997017430.195210132448417.995912917017922.35433079
2448298.746479517017903.75791129
#Sta/Elev= 30
    1000   442.2    1120   442.2    1175   431.5    1274   430.3    1395   427.7
    1432   413.2    1440   411.8    1462   404.2    1475   401.5    1485   402.7
    1505     404    1525   411.8    1550   420.9    1594     426    1645   427.5
    1740   428.7    1789   428.1    1904   428.9    2136   428.9    2210   428.2
    2505   427.3    2685     428    2810   429.5    2875   428.4    2946   428.2
    3083   429.1    3098   435.5    3119   443.4    3124   444.1    3143   444.5
#Mann= 5 ,-1,0
    1000     .09       0    1395     .04       0    1645     .09       0
    2136     .07       0    3083     .03       0
Bank Sta=1395,1594
XS Rating Curve= 0 ,0
Exp/Cntr=0.3,0.1