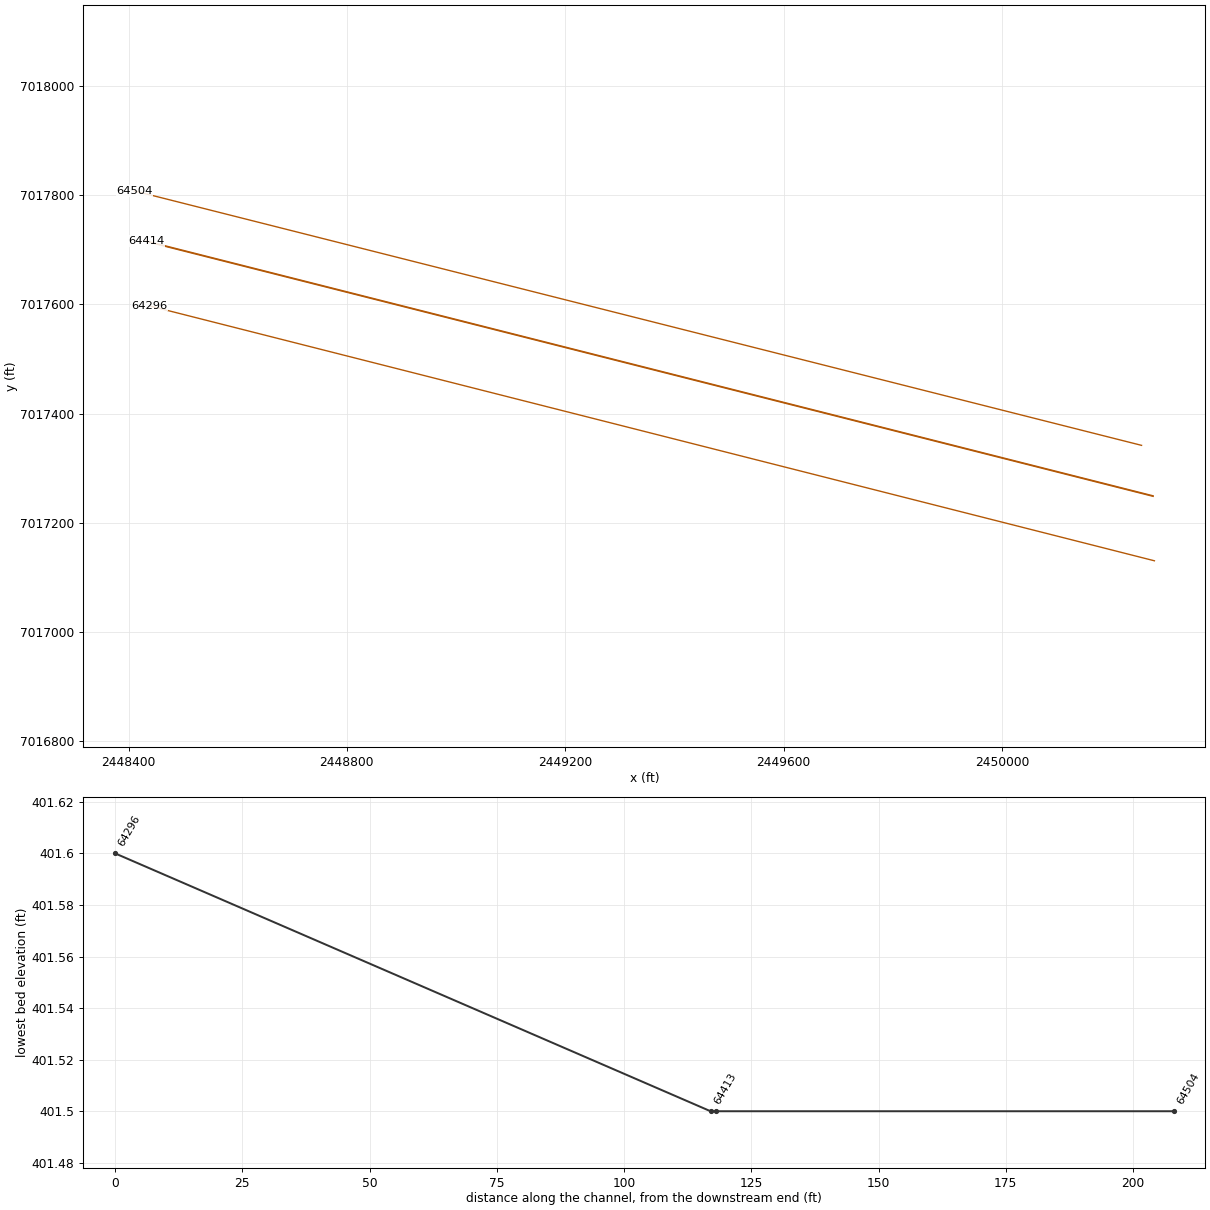
HEC-RAS study CDC_Consolidated_Model.prj: Upper Trinity CDC Consolidated Model

--- CDC_Consolidated_Model.g02 (geometry) --- (continued)

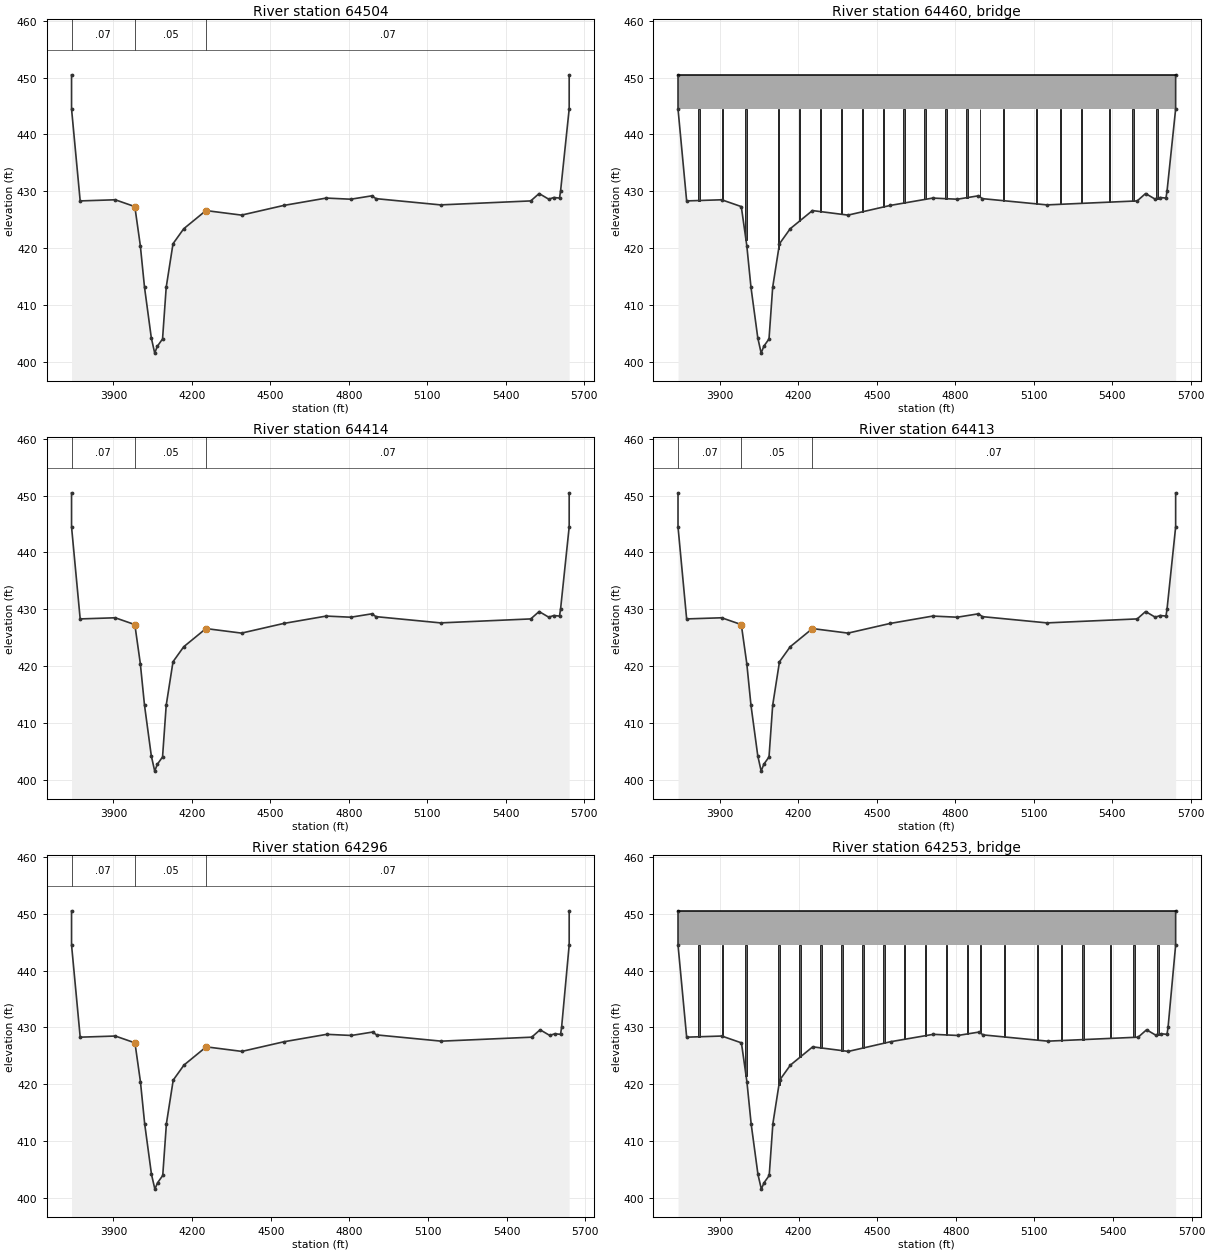
Type RM Length L Ch R = 1 ,64504   ,90,90,90
BEGIN DESCRIPTION:
This cross section corresponds to cross section 64495 of the non-georeferenced CDC model which was the source of this model.
END DESCRIPTION:
XS GIS Cut Line= 2
2450255.885609847017341.984428552448410.824667427017807.98710546
#Sta/Elev= 30
    3740   450.5    3740   444.5    3773   428.3    3907   428.5    3982   427.3
    4003  420.44    4019   413.1    4045   404.2    4058   401.5    4068   402.7
    4088     404    4102   413.1    4128  420.76    4169   423.4    4254   426.6
    4390   425.8    4551   427.5    4714   428.8    4808   428.6    4889   429.2
    4904   428.7    5151   427.6    5496   428.3    5528   429.6    5565   428.6
    5584   428.9    5606   428.8    5610     430    5643   444.5    5643   450.5
#Mann= 3 ,0,0
    3740     .07       0    3982     .05       0    4254     .07       0
Bank Sta=3982,4254
XS Rating Curve= 0 ,0
Exp/Cntr=0.5,0.3

Type RM Length L Ch R = 3 ,64460   ,,,
BEGIN DESCRIPTION:
IH 635/LBJ Freeway West Bound
END DESCRIPTION:
Node Name=IH 635
Bridge Culvert--1,0,-1,-1, 0
Deck Dist Width WeirC Skew NumUp NumDn MinLoCord MaxHiCord MaxSubmerge Is_Ogee
2,85,2.6,0, 44, 44, , , 0.95, 0, ,,,
    3740    3817    3823    3907    3913    3997    4003    4122    4128    4202
    4208    4282    4288    4362    4368    4442    4448    4522    4528    4602
    4608    4682    4688    4762    4768    4842    4848  4893.5  4896.5  4984.5
  4987.5  5109.5  5112.5  5201.5  5204.5    5283    5289    5387    5393    5477
    5483    5567    5573    5643
   450.5   450.5   450.5   450.5   450.5   450.5   450.5   450.5   450.5   450.5
   450.5   450.5   450.5   450.5   450.5   450.5   450.5   450.5   450.5   450.5
   450.5   450.5   450.5   450.5   450.5   450.5   450.5   450.5   450.5   450.5
   450.5   450.5   450.5   450.5   450.5   450.5   450.5   450.5   450.5   450.5
   450.5   450.5   450.5   450.5
   444.5   444.5   444.5   444.5   444.5   444.5   444.5   444.5   444.5   444.5
   444.5   444.5   444.5   444.5   444.5   444.5   444.5   444.5   444.5   444.5
   444.5   444.5   444.5   444.5   444.5   444.5   444.5   444.5   444.5   444.5
   444.5   444.5   444.5   444.5   444.5   444.5   444.5   444.5   444.5   444.5
   444.5   444.5   444.5   444.5
    3740    3817    3823    3907    3913    3997    4003    4122    4128    4202
    4208    4282    4288    4362    4368    4442    4448    4522    4528    4602
    4608    4682    4688    4762    4768    4842    4848  4893.5  4896.5  4984.5
  4987.5  5109.5  5112.5  5201.5  5204.5    5283    5289    5387    5393    5477
    5483    5567    5573    5643
   450.5   450.5   450.5   450.5   450.5   450.5   450.5   450.5   450.5   450.5
   450.5   450.5   450.5   450.5   450.5   450.5   450.5   450.5   450.5   450.5
   450.5   450.5   450.5   450.5   450.5   450.5   450.5   450.5   450.5   450.5
   450.5   450.5   450.5   450.5   450.5   450.5   450.5   450.5   450.5   450.5
   450.5   450.5   450.5   450.5
   444.5   444.5   444.5   444.5   444.5   444.5   444.5   444.5   444.5   444.5
   444.5   444.5   444.5   444.5   444.5   444.5   444.5   444.5   444.5   444.5
   444.5   444.5   444.5   444.5   444.5   444.5   444.5   444.5   444.5   444.5
   444.5   444.5   444.5   444.5   444.5   444.5   444.5   444.5   444.5   444.5
   444.5   444.5   444.5   444.5
Pier Skew, UpSta & Num, DnSta & Num=  ,3820, 2 ,3820, 2 , 0 , 0 , 0 ,,
       6       6
     415     450
       6       6
     415     450
Pier Skew, UpSta & Num, DnSta & Num=  ,3910, 2 ,3910, 2 , 0 , 0 , 0 ,,
       6       6
     415     450
       6       6
     415     450
Pier Skew, UpSta & Num, DnSta & Num=  ,4000, 2 ,4000, 2 , 0 , 0 , 0 ,,
       6       6
     415     450
       6       6
     415     450
Pier Skew, UpSta & Num, DnSta & Num=  ,4125, 2 ,4125, 2 , 0 , 0 , 0 ,,
       6       6
     415     450
       6       6
     415     450
Pier Skew, UpSta & Num, DnSta & Num=  ,4205, 2 ,4205, 2 , 0 , 0 , 0 ,,
       6       6
     415     450
       6       6
     415     450
Pier Skew, UpSta & Num, DnSta & Num=  ,4285, 2 ,4285, 2 , 0 , 0 , 0 ,,
       6       6
     415     450
       6       6
     415     450
Pier Skew, UpSta & Num, DnSta & Num=  ,4365, 2 ,4365, 2 , 0 , 0 , 0 ,,
       6       6
     415     450
       6       6
     415     450
Pier Skew, UpSta & Num, DnSta & Num=  ,4445, 2 ,4445, 2 , 0 , 0 , 0 ,,
       6       6
     415     450
       6       6
     415     450
Pier Skew, UpSta & Num, DnSta & Num=  ,4525, 2 ,4525, 2 , 0 , 0 , 0 ,,
       6       6
     415     450
       6       6
     415     450
Pier Skew, UpSta & Num, DnSta & Num=  ,4605, 2 ,4605, 2 , 0 , 0 , 0 ,,
       6       6
     415     450
       6       6
     415     450
Pier Skew, UpSta & Num, DnSta & Num=  ,4685, 2 ,4685, 2 , 0 , 0 , 0 ,,
       6       6
     415     450
       6       6
     415     450
Pier Skew, UpSta & Num, DnSta & Num=  ,4765, 2 ,4765, 2 , 0 , 0 , 0 ,,
       6       6
     415     450
       6       6
     415     450
Pier Skew, UpSta & Num, DnSta & Num=  ,4845, 2 ,4845, 2 , 0 , 0 , 0 ,,
       6       6
     415     450
       6       6
     415     450
Pier Skew, UpSta & Num, DnSta & Num=  ,4895, 2 ,4895, 2 , 0 , 0 , 0 ,,
       3       3
     415     450
       3       3
     415     450
Pier Skew, UpSta & Num, DnSta & Num=  ,4986, 2 ,4986, 2 , 0 , 0 , 0 ,,
       3       3
     415     450
       3       3
     415     450
Pier Skew, UpSta & Num, DnSta & Num=  ,5111, 2 ,5111, 2 , 0 , 0 , 0 ,,
       3       3
     415     450
       3       3
     415     450
Pier Skew, UpSta & Num, DnSta & Num=  ,5203, 2 ,5203, 2 , 0 , 0 , 0 ,,
       3       3
     415     450
       3       3
     415     450
Pier Skew, UpSta & Num, DnSta & Num=  ,5283, 2 ,5283, 2 , 0 , 0 , 0 ,,
       6       6
     415     450
       6       6
     415     450
Pier Skew, UpSta & Num, DnSta & Num=  ,5390, 2 ,5390, 2 , 0 , 0 , 0 ,,
       6       6
     415     450
       6       6
     415     450
Pier Skew, UpSta & Num, DnSta & Num=  ,5480, 2 ,5480, 2 , 0 , 0 , 0 ,,
       6       6
     415     450
       6       6
     415     450
Pier Skew, UpSta & Num, DnSta & Num=  ,5571, 2 ,5571, 2 , 0 , 0 , 0 ,,
       6       6
     415     450
       6       6
     415     450
BR Coef= 1 , 0 , 0 ,1.05, 0 ,,,0.8,-1,0.5,1,
WSPro=,,,, 1 ,,,, 0 ,,,, 0 ,,,,-1 ,-1 ,-1 , 0 , 0 , 0 , 0 , 0
BC Design=,, 0 ,, 0 ,,,,,,
BC HTab HWMax=450.5
BC Use User HTab Curves=0
BC User HTab FreeFlow(D)= 0

Type RM Length L Ch R = 1 ,64414   ,1,1,1
BEGIN DESCRIPTION:
This cross section corresponds to cross section 64406 of the non-georeferenced CDC model which was the source of this model.
END DESCRIPTION:
XS GIS Cut Line= 2
2450277.056499247017249.557776142448432.189782177017716.32948038
#Sta/Elev= 30
    3740   450.5    3740   444.5    3773   428.3    3907   428.5    3982   427.3
    4003  420.44    4019   413.1    4045   404.2    4058   401.5    4068   402.7
    4088     404    4102   413.1    4128  420.76    4169   423.4    4254   426.6
    4390   425.8    4551   427.5    4714   428.8    4808   428.6    4889   429.2
    4904   428.7    5151   427.6    5496   428.3    5528   429.6    5565   428.6
    5584   428.9    5606   428.8    5610     430    5643   444.5    5643   450.5
#Mann= 3 ,0,0
    3740     .07       0    3982     .05       0    4254     .07       0
Bank Sta=3982,4254
XS Rating Curve= 0 ,0
Exp/Cntr=0.5,0.3

Type RM Length L Ch R = 1 ,64413   ,117,117,117
BEGIN DESCRIPTION:
This cross section corresponds to cross section 64405 of the non-georeferenced CDC model which was the source of this model.
END DESCRIPTION:
XS GIS Cut Line= 2
2450277.07618424 7017248.57418232448432.211763777017715.35441671
#Sta/Elev= 30
    3740   450.5    3740   444.5    3773   428.3    3907   428.5    3982   427.3
    4003  420.44    4019   413.1    4045   404.2    4058   401.5    4068   402.7
    4088     404    4102   413.1    4128  420.76    4169   423.4    4254   426.6
    4390   425.8    4551   427.5    4714   428.8    4808   428.6    4889   429.2
    4904   428.7    5151   427.6    5496   428.3    5528   429.6    5565   428.6
    5584   428.9    5606   428.8    5610     430    5643   444.5    5643   450.5
#Mann= 3 ,0,0
    3740     .07       0    3982     .05       0    4254     .07       0
Bank Sta=3982,4254
XS Rating Curve= 0 ,0
Exp/Cntr=0.5,0.3

Type RM Length L Ch R = 1 ,64296   ,85,85,85
BEGIN DESCRIPTION:
This cross section corresponds to cross section 64285 of the non-georeferenced CDC model which was the source of this model.
END DESCRIPTION:
XS GIS Cut Line= 2
2450279.475457677017130.556373722448438.749152247017597.38286789
#Sta/Elev= 30
    3740   450.5    3740   444.5    3773   428.3    3907   428.5    3982   427.3
    4003  420.44    4019   413.1    4045   404.2    4058   401.6    4068   402.7
    4088     404    4102   413.1    4128  420.76    4169   423.4    4254   426.6
    4390   425.8    4551   427.5    4714   428.8    4808   428.6    4889   429.2
    4904   428.7    5151   427.6    5496   428.3    5528   429.6    5565   428.6
    5584   428.9    5606   428.8    5610     430    5639   444.5    5639   450.5
#Mann= 3 ,0,0
    3740     .07       0    3982     .05       0    4254     .07       0
Bank Sta=3982,4254
XS Rating Curve= 0 ,0
Exp/Cntr=0.5,0.3

Type RM Length L Ch R = 3 ,64253   ,,,
BEGIN DESCRIPTION:
IH 635/L BJ Freeway East Bound
END DESCRIPTION:
Node Name=IH 635
Bridge Culvert--1,0,-1,-1, 0
Deck Dist Width WeirC Skew NumUp NumDn MinLoCord MaxHiCord MaxSubmerge Is_Ogee
2,82,2.6,0, 45, 45, , , 0.95, 0, ,,,
    3740    3817    3823    3907    3913    3997    4003    4122    4128    4202
    4208    4282    4288    4362    4368    4368    4442    4448    4522    4528
    4602    4608    4682    4688    4762    4768    4842    4848  4893.5  4896.5
  4984.5  4987.5  5109.5  5112.5  5201.5  5204.5    5283    5289    5387    5393
    5477    5483    5568    5574    5639
   450.5   450.5   450.5   450.5   450.5   450.5   450.5   450.5   450.5   450.5
   450.5   450.5   450.5   450.5   450.5   450.5   450.5   450.5   450.5   450.5
   450.5   450.5   450.5   450.5   450.5   450.5   450.5   450.5   450.5   450.5
   450.5   450.5   450.5   450.5   450.5   450.5   450.5   450.5   450.5   450.5
   450.5   450.5   450.5   450.5   450.5
   444.5   444.5   444.5   444.5   444.5   444.5   444.5   444.5   444.5   444.5
   444.5   444.5   444.5   444.5   444.5   444.5   444.5   444.5   444.5   444.5
   444.5   444.5   444.5   444.5   444.5   444.5   444.5   444.5   444.5   444.5
   444.5   444.5   444.5   444.5   444.5   444.5   444.5   444.5   444.5   444.5
   444.5   444.5   444.5   444.5   444.5
    3740    3817    3823    3907    3913    3997    4003    4122    4128    4202
    4208    4282    4288    4362    4368    4368    4442    4448    4522    4528
    4602    4608    4682    4688    4762    4768    4842    4848  4893.5  4896.5
  4984.5  4987.5  5109.5  5112.5  5201.5  5204.5    5283    5289    5387    5393
    5477    5483    5568    5574    5639
   450.5   450.5   450.5   450.5   450.5   450.5   450.5   450.5   450.5   450.5
   450.5   450.5   450.5   450.5   450.5   450.5   450.5   450.5   450.5   450.5
   450.5   450.5   450.5   450.5   450.5   450.5   450.5   450.5   450.5   450.5
   450.5   450.5   450.5   450.5   450.5   450.5   450.5   450.5   450.5   450.5
   450.5   450.5   450.5   450.5   450.5
   444.5   444.5   444.5   444.5   444.5   444.5   444.5   444.5   444.5   444.5
   444.5   444.5   444.5   444.5   444.5   444.5   444.5   444.5   444.5   444.5
   444.5   444.5   444.5   444.5   444.5   444.5   444.5   444.5   444.5   444.5
   444.5   444.5   444.5   444.5   444.5   444.5   444.5   444.5   444.5   444.5
   444.5   444.5   444.5   444.5   444.5
Pier Skew, UpSta & Num, DnSta & Num=  ,3820, 2 ,3820, 2 , 0 , 0 , 0 ,,
       6       6
     415     450
       6       6
     415     450
Pier Skew, UpSta & Num, DnSta & Num=  ,3910, 2 ,3910, 2 , 0 , 0 , 0 ,,
       6       6
     415     450
       6       6
     415     450
Pier Skew, UpSta & Num, DnSta & Num=  ,4000, 2 ,4000, 2 , 0 , 0 , 0 ,,
       6       6
     415     450
       6       6
     415     450
Pier Skew, UpSta & Num, DnSta & Num=  ,4125, 2 ,4125, 2 , 0 , 0 , 0 ,,
       6       6
     415     450
       6       6
     415     450
Pier Skew, UpSta & Num, DnSta & Num=  ,4205, 2 ,4205, 2 , 0 , 0 , 0 ,,
       6       6
     415     450
       6       6
     415     450
Pier Skew, UpSta & Num, DnSta & Num=  ,4285, 2 ,4285, 2 , 0 , 0 , 0 ,,
       6       6
     415     450
       6       6
     415     450
Pier Skew, UpSta & Num, DnSta & Num=  ,4365, 2 ,4365, 2 , 0 , 0 , 0 ,,
       6       6
     415     450
       6       6
     415     450
Pier Skew, UpSta & Num, DnSta & Num=  ,4445, 2 ,4445, 2 , 0 , 0 , 0 ,,
       6       6
     415     450
       6       6
     415     450
Pier Skew, UpSta & Num, DnSta & Num=  ,4525, 2 ,4525, 2 , 0 , 0 , 0 ,,
       6       6
     415     450
       6       6
     415     450
Pier Skew, UpSta & Num, DnSta & Num=  ,4605, 2 ,4605, 2 , 0 , 0 , 0 ,,
       6       6
     415     450
       6       6
     415     450
Pier Skew, UpSta & Num, DnSta & Num=  ,4685, 2 ,4685, 2 , 0 , 0 , 0 ,,
       6       6
     415     450
       6       6
     415     450
Pier Skew, UpSta & Num, DnSta & Num=  ,4765, 2 ,4765, 2 , 0 , 0 , 0 ,,
       6       6
     415     450
       6       6
     415     450
Pier Skew, UpSta & Num, DnSta & Num=  ,4845, 2 ,4845, 2 , 0 , 0 , 0 ,,
       6       6
     415     450
       6       6
     415     450
Pier Skew, UpSta & Num, DnSta & Num=  ,4895, 2 ,4895, 2 , 0 , 0 , 0 ,,
       3       3
     415     450
       3       3
     415     450
Pier Skew, UpSta & Num, DnSta & Num=  ,4986, 2 ,4986, 2 , 0 , 0 , 0 ,,
       3       3
     415     450
       3       3
     415     450
Pier Skew, UpSta & Num, DnSta & Num=  ,5111, 2 ,5111, 2 , 0 , 0 , 0 ,,
       3       3
     415     450
       3       3
     415     450
Pier Skew, UpSta & Num, DnSta & Num=  ,5203, 2 ,5203, 2 , 0 , 0 , 0 ,,
       3       3
     415     450
       3       3
     415     450
Pier Skew, UpSta & Num, DnSta & Num=  ,5285, 2 ,5285, 2 , 0 , 0 , 0 ,,
       6       6
     415     450
       6       6
     415     450
Pier Skew, UpSta & Num, DnSta & Num=  ,5390, 2 ,5390, 2 , 0 , 0 , 0 ,,
       6       6
     415     450
       6       6
     415     450
Pier Skew, UpSta & Num, DnSta & Num=  ,5480, 2 ,5480, 2 , 0 , 0 , 0 ,,
       6       6
     415     450
       6       6
     415     450
Pier Skew, UpSta & Num, DnSta & Num=  ,5571, 2 ,5571, 2 , 0 , 0 , 0 ,,
       6       6
     415     450
       6       6
     415     450
BR Coef= 1 , 0 , 0 ,1.05, 0 ,,,0.8,-1,0.5,1,
WSPro=,,,, 1 ,,,, 0 ,,,, 0 ,,,,-1 ,-1 ,-1 , 0 , 0 , 0 , 0 , 0
BC Design=,, 0 ,, 0 ,,,,,,
BC HTab HWMax=450.5
BC Use User HTab Curves=0
BC User HTab FreeFlow(D)= 0