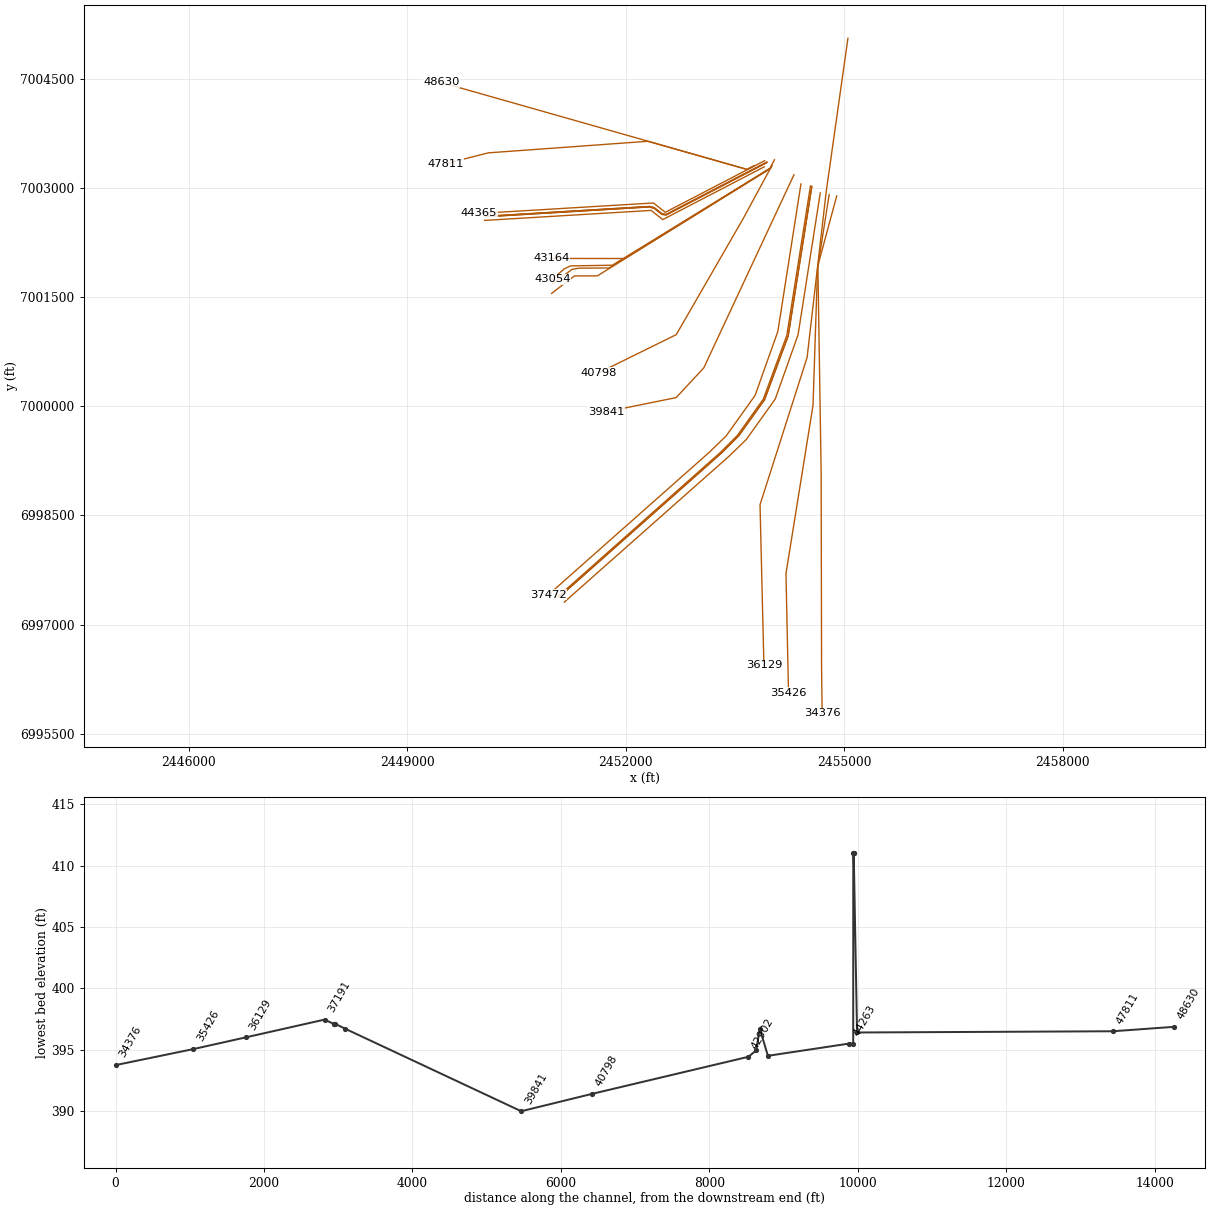
HEC-RAS study CDC_Consolidated_Model.prj: Upper Trinity CDC Consolidated Model

--- CDC_Consolidated_Model.g02 (geometry) --- (continued)

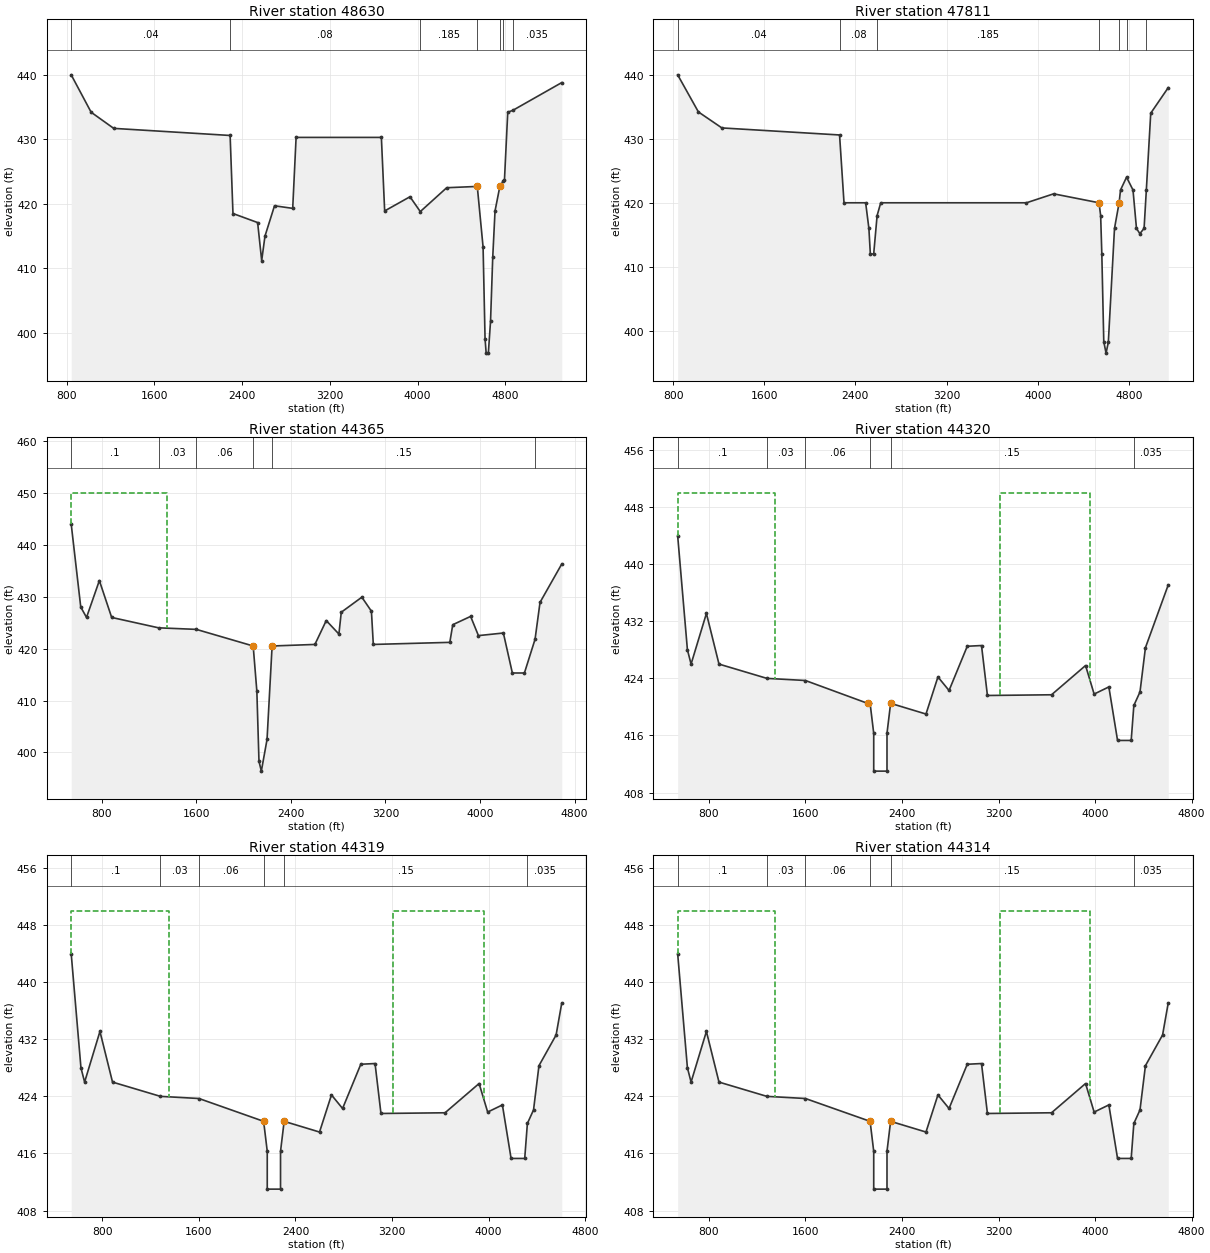
Type RM Length L Ch R = 1 ,48630   ,600,819,1000
BEGIN DESCRIPTION:
This cross section corresponds to cross section 48610 of the non-georeferenced CDC model which was the source of this model.
END DESCRIPTION:
XS GIS Cut Line= 4
 2453764.65516717003306.71722355 2453757.06069417003302.77366188
2453666.417174587003255.705842632449467.509890027004449.46526614
#Sta/Elev= 30
     840     440    1022   434.2    1228   431.7    2290   430.6    2316   418.5
    2541   417.1    2578   411.2    2608     415    2695   419.7    2861   419.3
    2892   430.3    3670   430.3    3700   418.9    3931   421.1    4025   418.8
    4266   422.5    4545   422.7    4598   413.3    4616   399.1    4626  396.86
    4646  396.86    4666   401.8    4686   411.7    4707   418.9    4751   422.7
    4784   423.6    4793   423.7    4823   434.2    4870   434.5    5316   438.8
#Mann= 7 ,-1,0
     840     .04       0    2290     .08       0    4025    .185       0
    4545     .04       0    4751     .12       0    4784     .06       0
    4870    .035       0
Bank Sta=4545,4751
XS Rating Curve= 0 ,0
Exp/Cntr=0.3,0.1

Type RM Length L Ch R = 1 ,47811   ,1200,3446,1000
BEGIN DESCRIPTION:
This cross section corresponds to cross section 47791 of the non-georeferenced CDC model which was the source of this model.
END DESCRIPTION:
XS GIS Cut Line= 6
2453744.767739687003293.939033882453666.132070187003253.49324863
2452308.200402837003640.129286382452294.250955677003640.68210679
2450112.615883267003482.20703004 2449527.06128017003333.13810247
#Sta/Elev= 30
     840     440    1022   434.2    1228   431.7    2261   430.6    2300     420
    2490     420  2518.4     416  2531.2     412  2560.6     412  2590.6     418
  2622.4     420  3901.6     420    4140   421.4  4538.2     420  4552.6     418
  4562.9     412    4580   398.3    4600   396.5    4620   398.2  4674.2     416
  4714.6     420    4727     422    4780     424  4836.5     422    4867     416
  4896.7  415.17  4933.8     416  4953.6     422  4992.2     434  5145.9     438
#Mann= 7 ,-1,0
     840     .04       0    2261     .08       0  2590.6    .185       0
  4538.2     .05       0  4714.6     .12       0    4780     .06       0
  4953.6    .035       0
Bank Sta=4538.2,4714.6
XS Rating Curve= 0 ,0
Exp/Cntr=0.3,0.1

Type RM Length L Ch R = 1 ,44365   ,45,45,45
BEGIN DESCRIPTION:
This cross section corresponds to cross section 44345 of the non-georeferenced CDC model which was the source of this model.
END DESCRIPTION:
XS GIS Cut Line= 6
2453908.592871347003374.810263222453798.294535527003317.45276639
2453675.029362087003253.351844712452543.712070917002665.04199772
2452381.33608335 7002793.41608482449981.857614587002649.19097956
#Sta/Elev= 30
   541.8     444  622.61     428  671.44     426     780   433.1  884.13     426
  1280.9     424    1600   423.7    2081   420.5    2112   411.8    2130   398.3
    2150   396.4 2198.22   402.5    2241   420.5    2603   420.8    2699   425.4
    2806   422.8    2826     427    3000   429.9    3081   427.2    3097   420.8
    3744   421.2    3769   424.6    3920   426.2    3986   422.5    4197     423
    4273   415.3    4375   415.3    4465   421.8    4507   428.9    4691   436.3
#Mann= 6 ,-1,0
   541.8      .1       0  1280.9     .03       0    1600     .06       0
    2081     .05       0    2241     .15       0    4465    .035       0
#XS Ineff= 3 ,-1
   541.8    1350     450    1350    2081   420.5    2241    4606     420
Permanent Ineff=
       F       F       F
Bank Sta=2081,2241
XS Rating Curve= 0 ,0
Exp/Cntr=0.3,0.1

Type RM Length L Ch R = 1 ,44320   ,1,1,1
BEGIN DESCRIPTION:
This cross section corresponds to cross section 44300 of the non-georeferenced CDC model which was the source of this model.
END DESCRIPTION:
XS GIS Cut Line= 6
2453938.622010777003354.405448382452554.999121847002634.89081129
2452497.740378087002645.147352472452390.996497097002729.53858788
2452327.989405247002746.012308212450086.727155517002611.29702647
#Sta/Elev= 30
   541.8     444  622.61     428  652.95     426     780   433.1  884.13     426
  1280.9     424    1600   423.7    2115   420.5    2136   420.5    2166   416.3
    2166     411    2276     411    2276   416.3    2306   420.5    2599     419
    2698   424.2    2790   422.3    2941   428.5    3059   428.6    3108   421.6
    3639   421.7    3921   425.8    3992   421.8    4114   422.8    4186   415.3
    4299   415.3    4321   420.2    4372   422.1    4417   428.3    4606   437.1
#Mann= 6 ,-1,0
   541.8      .1       0  1280.9     .03       0    1600     .06       0
    2136     .05       0    2306     .15       0    4321    .035       0
#XS Ineff= 2 ,-1
   541.8    1350     450    3210    3960     450
Permanent Ineff=
       F       F
Bank Sta=2115,2306
XS Rating Curve= 0 ,0
Exp/Cntr=0.3,0.1

Type RM Length L Ch R = 1 ,44319   ,5,5,5
BEGIN DESCRIPTION:
This cross section corresponds to cross section 44299 of the non-georeferenced CDC model which was the source of this model.
END DESCRIPTION:
XS GIS Cut Line= 6
2453938.599373017003353.593114052452555.162179267002634.17526154
2452498.00973451 7002643.7844943  2452391.2717597002728.07139921
2452328.480874097002744.959160722450086.617903777002610.30851138
#Sta/Elev= 30
   541.8     444  622.61     428  652.95     426     780   433.1  884.13     426
  1280.9     424    1600   423.7    2136   420.5    2166   416.3    2166     411
    2276     411    2276   416.3    2306   420.5    2599     419    2698   424.2
    2790   422.3    2941   428.5    3059   428.6    3108   421.6    3639   421.7
    3921   425.8    3992   421.8    4114   422.8    4186   415.3    4299   415.3
    4321   420.2    4372   422.1    4417   428.3    4559   432.6    4606   437.1
#Mann= 6 ,-1,0
   541.8      .1       0  1280.9     .03       0    1600     .06       0
    2136     .02       0    2306     .15       0    4321    .035       0
#XS Ineff= 2 ,-1
   541.8    1350     450    3210    3960     450
Permanent Ineff=
       F       F
Bank Sta=2136,2306
XS Rating Curve= 0 ,0
Exp/Cntr=0.3,0.1

Type RM Length L Ch R = 1 ,44314   ,1,1,1
BEGIN DESCRIPTION:
This cross section corresponds to cross section 44294 of the non-georeferenced CDC model which was the source of this model.
California Crossing Dam
END DESCRIPTION:
XS GIS Cut Line= 6
 2453929.61349867003344.918262632452555.965655337002630.59062305
2452499.360125517002636.973156212452392.653317937002720.73020655
2452322.295190937002739.77708447  2450076.2724527002604.77604213
#Sta/Elev= 30
   541.8     444  622.61     428  652.95     426     780   433.1  884.13     426
  1280.9     424    1600   423.7    2136   420.5    2166   416.3    2166     411
    2276     411    2276   416.3    2306   420.5    2599     419    2698   424.2
    2790   422.3    2941   428.5    3059   428.6    3108   421.6    3639   421.7
    3921   425.8    3992   421.8    4114   422.8    4186   415.3    4299   415.3
    4321   420.2    4372   422.1    4417   428.3    4559   432.6    4606   437.1
#Mann= 6 ,-1,0
   541.8      .1       0  1280.9     .03       0    1600     .06       0
    2136     .02       0    2306     .15       0    4321    .035       0
#XS Ineff= 2 ,-1
   541.8    1350     450    3210    3960     450
Permanent Ineff=
       F       F
Bank Sta=2136,2306
XS Rating Curve= 0 ,0
Exp/Cntr=0.3,0.1

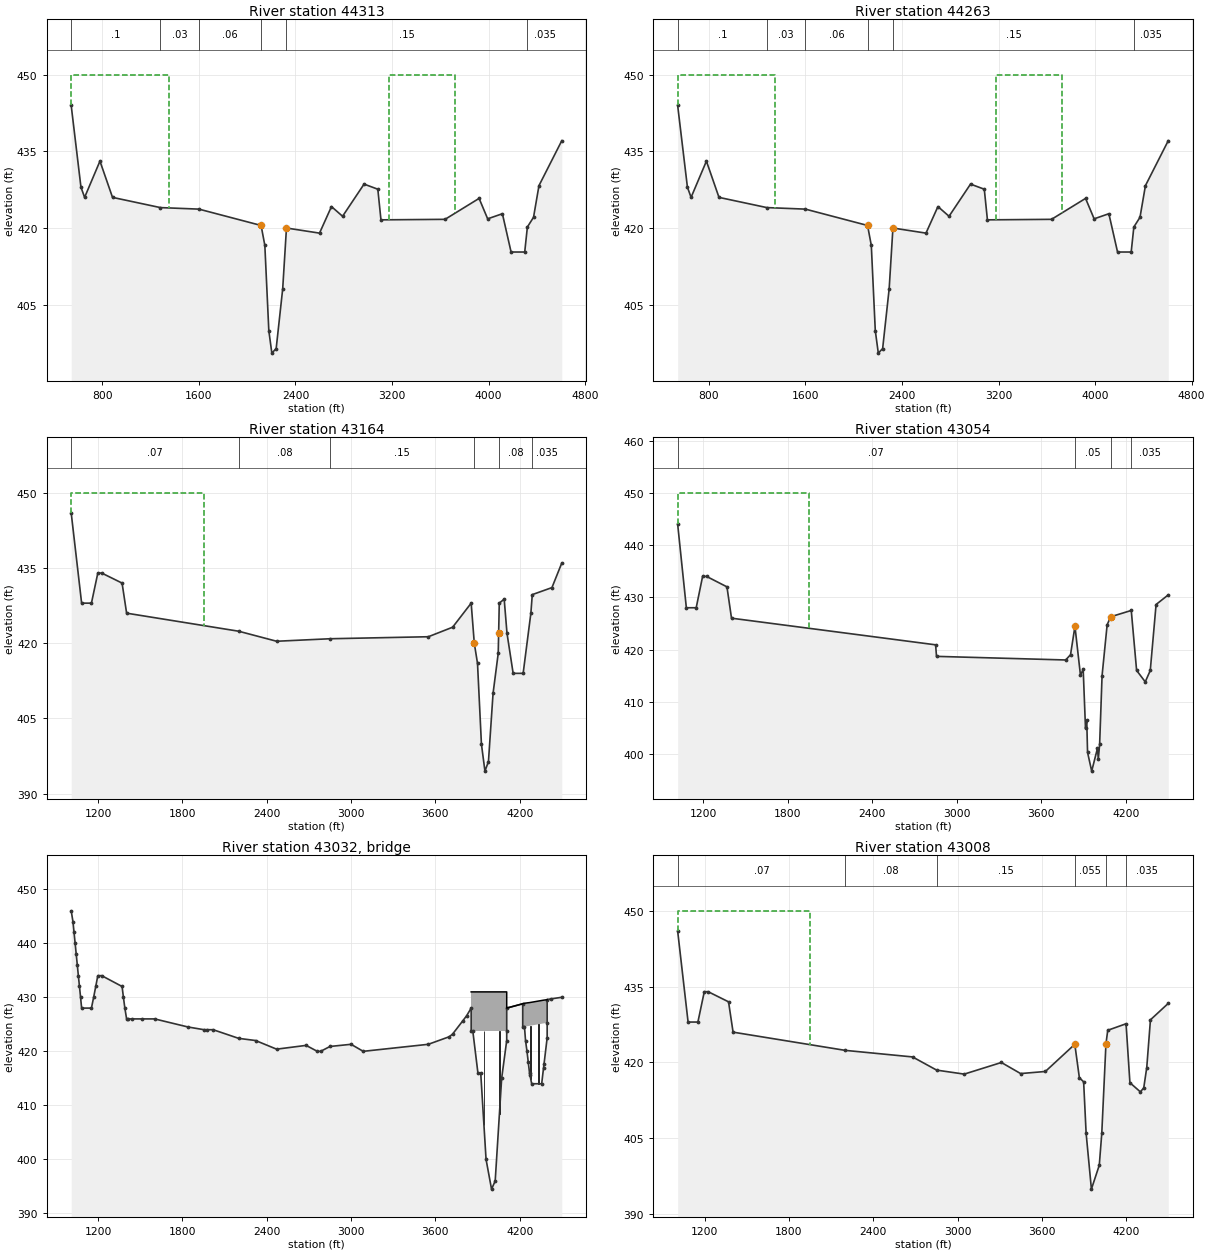
Type RM Length L Ch R = 1 ,44313   ,50,50,50
BEGIN DESCRIPTION:
This cross section corresponds to cross section 44293 of the non-georeferenced CDC model which was the source of this model.
END DESCRIPTION:
XS GIS Cut Line= 6
2453938.462890337003348.719436142452556.114605167002629.86785546
2452499.634731267002635.612922712452392.936453857002719.25645621
2452322.839153087002738.814487962450086.216329757002604.39120038
#Sta/Elev= 30
   541.8     444  622.61     428  652.95     426     780   433.1  884.13     426
  1280.9     424    1600   423.7    2115   420.5    2146   416.6    2179   399.9
    2204   395.5    2240   396.4    2294   408.1 2325.16     420    2599     419
    2698   424.2    2790   422.3    2968   428.6    3082   427.6    3108   421.6
    3639   421.7    3921   425.8    3992   421.8    4114   422.8    4186   415.3
    4299   415.3    4321   420.2    4372   422.1    4417   428.3    4606   437.1
#Mann= 6 ,-1,0
   541.8      .1       0  1280.9     .03       0    1600     .06       0
    2115     .05       0 2325.16     .15       0    4321    .035       0
#XS Ineff= 2 ,-1
   541.8    1350     450    3175    3725     450
Permanent Ineff=
       F       F
Bank Sta=2115,2325.16
XS Rating Curve= 0 ,0
Exp/Cntr=0.3,0.1

Type RM Length L Ch R = 1 ,44263   ,180,1099,750
BEGIN DESCRIPTION:
This cross section corresponds to cross section 44243 of the non-georeferenced CDC model which was the source of this model.
END DESCRIPTION:
XS GIS Cut Line= 4
2453901.838291677003289.65065663  2452508.7439657002565.21116063
2452349.248877177002691.307037062450062.69406709 7002553.8693198
#Sta/Elev= 30
   541.8     444  622.61     428  652.95     426     780   433.1  884.13     426
  1280.9     424    1600   423.7    2115   420.5    2146   416.6    2179   399.9
    2204   395.5    2240   396.4    2294   408.1 2325.16     420    2599     419
    2698   424.2    2790   422.3    2968   428.6    3082   427.6    3108   421.6
    3639   421.7    3921   425.8    3992   421.8    4114   422.8    4186   415.3
    4299   415.3    4321   420.2    4372   422.1    4417   428.3    4606   437.1
#Mann= 6 ,-1,0
   541.8      .1       0  1280.9     .03       0    1600     .06       0
    2115     .05       0 2325.16     .15       0    4321    .035       0
#XS Ineff= 2 ,-1
   541.8    1350     450    3175    3725     450
Permanent Ineff=
       F       F
Bank Sta=2115,2325.16
XS Rating Curve= 0 ,0
Exp/Cntr=0.3,0.1

Type RM Length L Ch R = 1 ,43164   ,110,110,110
BEGIN DESCRIPTION:
This cross section corresponds to cross section 43144 of the non-georeferenced CDC model which was the source of this model.
END DESCRIPTION:
XS GIS Cut Line= 5
2454042.977773167003387.689502552454031.395119167003364.59276396
2453984.925395857003271.930547712451985.799800937002030.01603679
2450976.579706527002031.33230713
#Sta/Elev= 30
  1007.8     446    1082     428  1151.9     428  1197.3     434  1225.2     434
    1370     432  1402.3     426    2200   422.4    2470   420.4    2850   420.9
    3550   421.3    3723   423.2    3855     428  3877.2     420  3900.1     416
    3928   399.9    3953   394.5    3978   396.4  4010.8     410  4047.6     418
  4050.6     422    4055     428    4090   428.8    4110     422  4153.8     414
    4225     414    4280     426    4290   429.7    4430   431.1    4500     436
#Mann= 6 ,-1,0
  1007.8     .07       0    2200     .08       0    2850     .15       0
  3877.2     .05       0  4050.6     .08       0    4290    .035       0
#XS Ineff= 2 , 0
       0    1950     450               0
Permanent Ineff=
       F       F
Bank Sta=3877.2,4050.6
XS Rating Curve= 0 ,0
Exp/Cntr=0.3,0.1

Type RM Length L Ch R = 1 ,43054   ,46,46,46
BEGIN DESCRIPTION:
This cross section corresponds to cross section 43026 of the non-georeferenced CDC model which was the source of this model.
---------------------------------------------------------------------
CDC DAL071508-1 California Crossing
Cross-section 42984 - 43026
---------------------------------------------------------------------
Cross-section was imported from Geopak.
END DESCRIPTION:
XS GIS Cut Line= 6
2454008.696345697003310.946545792453987.395207177003270.87543172
 2451817.26732967001938.14548564 2451241.2389541 7001928.7367118
2451157.605263087001887.965139812450991.633810257001747.51069631
#Sta/Elev= 30
  1020.4     444    1082     428  1151.9     428  1197.3     434  1225.2     434
    1370     432  1402.3     426    2850   420.9 2856.34  418.69 3772.38     418
 3806.94  419.01 3838.27  424.44 3877.32   415.1  3896.7  416.22 3913.15  404.89
 3921.92  406.44 3927.63  400.32    3957  396.72 3998.06  401.09 4003.98  399.05
 4013.35  401.85 4030.62     415 4066.61  424.74  4091.7  426.27 4237.68  427.48
 4275.57     416 4336.88  413.81  4372.5  415.99 4413.74  428.62    4500  430.46
#Mann= 4 ,-1,0
  1020.4     .07       0 3838.27     .05       0  4091.7     .08       0
 4237.68    .035       0
#XS Ineff= 2 , 0
       0    1950     450               0
Permanent Ineff=
       F       F
Bank Sta=3838.27,4091.7
XS Rating Curve= 0 ,0
Exp/Cntr=0.5,0.3

Type RM Length L Ch R = 3 ,43032   ,,,
BEGIN DESCRIPTION:
California Crossing Road
Data from TXDOT bridge plans 2008.
END DESCRIPTION:
Node Name=California Cross
Bridge Culvert--1,0,-1,-1, 0
Deck Dist Width WeirC Skew NumUp NumDn MinLoCord MaxHiCord MaxSubmerge Is_Ogee
1.25,42.5,2.6,0, 13, 13, , , 0.95, 0, ,,,
    3855    4108    4108    4108 4221.94 4221.94 4234.44 4270.74 4273.44 4370.44
 4373.44 4373.44 4395.94
     431     431     428     428   428.8   428.8   428.9  429.02  429.03  429.47
  429.48  429.48  429.56
   423.7   423.7   423.7     428   428.8   424.5  424.56  424.72  424.73  425.17
  425.18  425.18  425.26
    3855    4108    4108    4108 4221.94 4221.94 4234.44 4270.74 4273.44 4370.44
 4373.44 4373.44 4395.94
     431     431     428     428   428.8   428.8   428.9  429.02  429.03  429.47
  429.48  429.48  429.56
   423.7   423.7   423.7     428   428.8   424.5  424.56  424.72  424.73  425.17
  425.18  425.18  425.26
Pier Skew, UpSta & Num, DnSta & Num=  ,3946, 2 ,3946, 2 , 0 , 0 , 0 ,,
     3.5     3.5
     405     425
     3.5     3.5
     405     425
Pier Skew, UpSta & Num, DnSta & Num=  ,4056, 2 ,4056, 2 , 0 , 0 , 0 ,,
     3.5     3.5
     405     425
     3.5     3.5
     405     425
Pier Skew, UpSta & Num, DnSta & Num=  ,4278.438, 2 ,4278.438, 2 , 0 , 0 , 0 ,,
       3       3
     405     425
       3       3
     405     425
Pier Skew, UpSta & Num, DnSta & Num=  ,4334.94, 2 ,4334.94, 2 , 0 , 0 , 0 ,,
       3       3
     405     426
       3       3
     405     426
BR Coef= 1 , 0 , 0 ,1.05, 0 ,,,0.8,-1,0.5,1,
WSPro=,,,, 1 ,,,, 0 ,,,, 0 ,,,,-1 ,-1 ,-1 , 0 , 0 , 0 , 0 , 0
BR U #Sta/Elev= 70
  1007.8     446  1020.4     444  1028.1     442  1035.8     440  1043.5     438
  1051.2     436  1058.8     434  1066.7     432  1074.5     430    1082     428
  1151.9     428  1167.6     430  1182.5     432  1197.3     434  1225.2     434
    1370     432  1379.6     430  1389.7     428  1402.3     426  1415.5     426
  1442.6     426  1509.2     426  1601.7     426    1840   424.5  1953.8     424
  1977.8     424  2018.2     424    2200   422.4  2320.3     422    2470   420.4
    2680   421.1  2759.6     420  2783.4     420    2850   420.9    3000   421.3
  3086.6     420    3550   421.3    3699   422.7    3723   423.2    3797   425.7
    3823   426.6    3855     428    3855   423.7  3866.9   423.7    3903     416
    3923     416    3961     400    4000   394.5    4026     396    4072     415
    4108     422    4108   423.7    4108     428 4221.94   428.8 4221.94   424.5
 4234.44  424.56 4241.94     422 4252.34     420 4261.34     418 4270.44     416
 4273.44  415.61 4285.74     414 4356.94     414 4370.44     417 4373.44   417.6
 4395.94  422.51 4395.94  425.26 4395.94  429.56 4421.94   429.7    4500     430
BR U #Mann= 1
  1007.8     .05
BR U Banks=3866.9,4108
BR D #Sta/Elev= 70
  1007.8     446  1020.4     444  1028.1     442  1035.8     440  1043.5     438
  1051.2     436  1058.8     434  1066.7     432  1074.5     430    1082     428
  1151.9     428  1167.6     430  1182.5     432  1197.3     434  1225.2     434
    1370     432  1379.6     430  1389.7     428  1402.3     426  1415.5     426
  1442.6     426  1509.2     426  1601.7     426    1840   424.5  1953.8     424
  1977.8     424  2018.2     424    2200   422.4  2320.3     422    2470   420.4
    2680   421.1  2759.6     420  2783.4     420    2850   420.9    3000   421.3
  3086.6     420    3550   421.3    3699   422.7    3723   423.2    3797   425.7
    3823   426.6    3855     428    3855   423.7  3866.9   423.7    3903     416
    3923     416    3961     400    4000   394.5    4026     396    4072     415
    4108     422    4108   423.7    4108     428 4221.94   428.8 4221.94   424.5
 4234.44  424.56 4241.94     422 4252.34     420 4261.34     418 4270.44     416
 4273.44  415.61 4285.74     414 4356.94     414 4370.44     417 4373.44   417.6
 4395.94  422.51 4395.94  425.26 4395.94  429.56 4421.94   429.7    4500     430
BR D #Mann= 1
  1007.8     .05
BR D Banks=3866.9,4108
BC Design=,, 0 ,, 0 ,,,,,,
BC HTab HWMax=446
BC Use User HTab Curves=0
BC User HTab FreeFlow(D)= 0

Type RM Length L Ch R = 1 ,43008   ,106,106,106
BEGIN DESCRIPTION:
This cross section corresponds to cross section 42984 of the non-georeferenced CDC model which was the source of this model.
---------------------------------------------------------------------
CDC DAL071508-1 California Crossing
Cross-section 42984 - 43026
---------------------------------------------------------------------
Cross-section was imported from Geopak
END DESCRIPTION:
XS GIS Cut Line= 6
2454006.047400837003304.068934892453987.987069527003270.23829389
2451773.359609017001900.510062222451355.190169757001897.37391363
2451264.302884347001881.240415722450992.833939087001679.36352289
#Sta/Elev= 30
  1007.8     446    1082     428  1151.9     428  1197.3     434  1225.2     434
    1370     432  1402.3     426    2200   422.4    2680   421.1 2851.44  418.49
 3047.67   417.7 3312.26     420 3449.05  417.81 3625.17  418.22 3834.86   423.6
 3867.21     417 3897.69  416.17 3915.39     406 3953.03  394.95 4009.07  399.68
 4026.88     406 4056.57   423.7 4069.38  426.37 4199.62  427.66 4227.09     416
 4301.84  414.18 4325.73     415 4347.02     419 4373.27  428.44    4500  431.69
#Mann= 6 ,-1,0
  1007.8     .07       0    2200     .08       0 2851.44     .15       0
 3834.86    .055       0 4056.57     .08       0 4199.62    .035       0
#XS Ineff= 2 , 0
       0    1950     450               0
Permanent Ineff=
       F       F
Bank Sta=3834.86,4056.57
XS Rating Curve= 0 ,0
Exp/Cntr=0.5,0.3

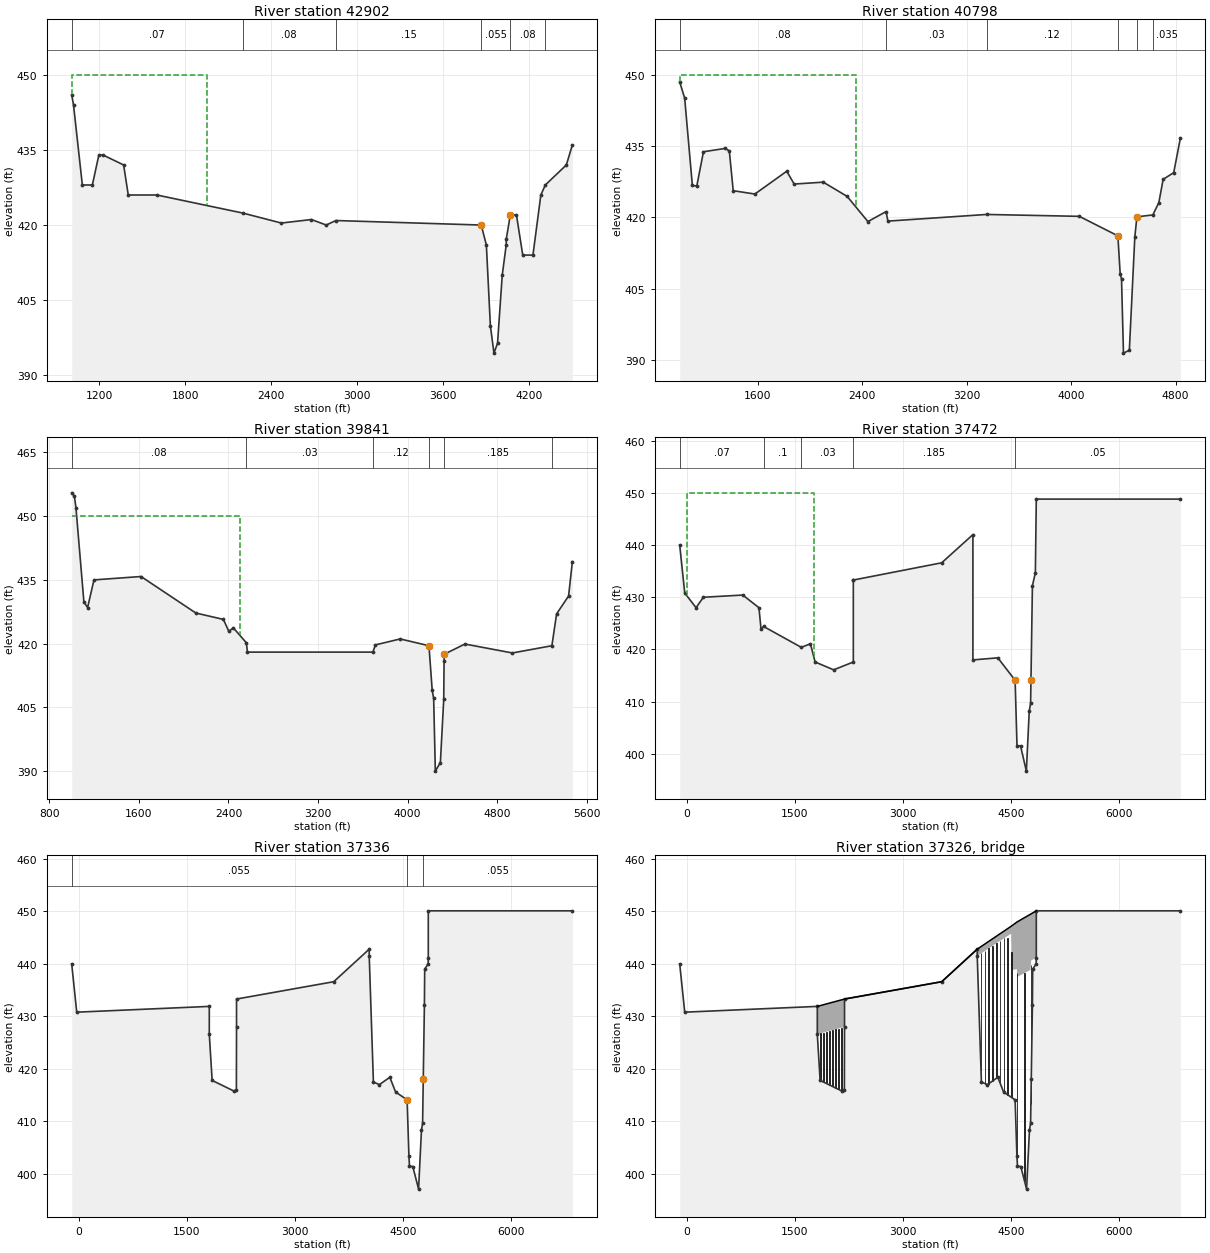
Type RM Length L Ch R = 1 ,42902   ,796,2104,1343
BEGIN DESCRIPTION:
This cross section corresponds to cross section 42882 of the non-georeferenced CDC model which was the source of this model.
END DESCRIPTION:
XS GIS Cut Line= 4
2453974.397201667003259.504391462451611.506914357001791.61001755
2451295.09809834 7001790.61297232450982.647935847001550.47532922
#Sta/Elev= 30
  1007.8     446  1020.4     444    1082     428  1151.9     428  1197.3     434
  1225.2     434    1370     432  1402.3     426  1601.7     426    2200   422.4
    2470   420.4    2680   421.1  2783.4     420    2850   420.9  3864.3     420
  3900.1     416    3928   399.9    3953  394.42    3978   396.4  4010.8     410
  4038.4     416    4039   417.2    4067     422    4110     422  4153.8     414
    4225     414    4280     426  4311.3     428  4457.9     432    4500     436
#Mann= 6 ,-1,0
  1007.8     .07       0    2200     .08       0    2850     .15       0
  3864.3    .055       0    4067     .08       0  4311.3    .035       0
#XS Ineff= 2 , 0
       0    1950     450               0
Permanent Ineff=
       F       F
Bank Sta=3864.3,4067
XS Rating Curve= 0 ,0
Exp/Cntr=0.5,0.3

Type RM Length L Ch R = 1 ,40798   ,525,957,707
BEGIN DESCRIPTION:
This cross section corresponds to cross section 40767 of the non-georeferenced CDC model which was the source of this model.
END DESCRIPTION:
XS GIS Cut Line= 6
2454001.208171677003293.61259097 2453989.58155457003272.17201705
2453988.809902527003270.749447722453605.335931937002563.61798796
2452694.625154917000983.939060722451634.198798097000461.40992205
#Sta/Elev= 30
    1000   448.5    1038   445.1    1097   426.7    1131   426.6    1182   433.8
    1347   434.5    1380     434    1410   425.6    1576   424.9    1820   429.7
    1877     427    2100   427.4    2283   424.4    2442   419.1    2581   421.2
    2595   419.2    3352   420.6    4062   420.2    4357   416.1    4375     408
    4385   407.1    4400   391.4    4445     392    4487   415.9    4503   420.1
    4625   420.5    4671   423.1    4704     428    4785   429.4    4836   436.7
#Mann= 6 ,-1,0
    1000     .08       0    2581     .03       0    3352     .12       0
    4357    .055       0    4503    .185       0    4625    .035       0
#XS Ineff= 2 , 0
       0    2350     450               0
Permanent Ineff=
       F       F
Bank Sta=4357,4503
XS Rating Curve= 0 ,0
Exp/Cntr=0.5,0.3

Type RM Length L Ch R = 1 ,39841   ,800,2369,1649
BEGIN DESCRIPTION:
This cross section corresponds to cross section 39820 of the non-georeferenced CDC model which was the source of this model.
END DESCRIPTION:
XS GIS Cut Line= 4
 2454311.15013717003180.989128542453072.949857597000527.49017046
2452693.306916097000118.645187632451727.137916686999922.39164314
#Sta/Elev= 30
    1000   455.5    1024   454.7    1038     452    1109   429.8    1142   428.5
    1199     435    1619   435.8    2109   427.2    2355   425.7    2403   422.9
    2444   423.7    2560   420.2    2570     418    3690     418    3713   419.7
    3934   421.1    4191   419.5    4220     409    4233   407.1    4248  389.98
    4293     392    4323   406.9    4326   415.9    4328   417.5    4512   419.9
    4936   417.8    5289   419.5    5331     427    5438   431.2    5472   439.3
#Mann= 6 ,-1,0
    1000     .08       0    2560     .03       0    3690     .12       0
    4191     .05       0    4328    .185       0    5289    .035       0
#XS Ineff= 2 , 0
       0    2500     450               0
Permanent Ineff=
       F       F
Bank Sta=4191,4328
XS Rating Curve= 0 ,0
Exp/Cntr=0.5,0.3

Type RM Length L Ch R = 1 ,37472   ,136,136,136
BEGIN DESCRIPTION:
This cross section corresponds to cross section 37450 of the non-georeferenced CDC model which was the source of this model.
END DESCRIPTION:
XS GIS Cut Line= 6
2454407.025273417003054.568121552454090.067902097001029.25524305
2453776.884145267000147.81409255   2453380.139866999592.24893072
2453144.702994916999363.637183222450936.798971556997406.74613178
#Sta/Elev= 30
    -100     440     -30   430.8  127.31     428  228.07     430  775.63  430.42
    1000     428    1029   423.9    1065   424.4    1589   420.4    1714   421.1
    1780   417.6    2037   416.1    2310   417.6    2310   433.3    2311   433.3
    3537   436.6    3970     442    3970     418    4316   418.4    4556   414.1
    4582   401.6    4632   401.5    4712   396.7    4752   408.2    4771   409.7
    4776   414.1    4796   432.2    4837   434.7    4850   448.8    6850   448.8
#Mann= 5 ,-1,0
    -100     .07       0    1065      .1       0    1589     .03       0
    2311    .185       0    4556     .05       0
#XS Ineff= 2 , 0
       0    1769     450               0
Permanent Ineff=
       F       F
Bank Sta=4556,4776
XS Rating Curve= 0 ,0
Exp/Cntr=0.5,0.3

Type RM Length L Ch R = 1 ,37336   ,19,19,19
BEGIN DESCRIPTION:
This cross section corresponds to cross section 37317 of the non-georeferenced CDC model which was the source of this model.
END DESCRIPTION:
XS GIS Cut Line= 6
2454537.668712917003028.402163392454213.076186277000974.06178388
2453890.112921427000096.861438542453534.077544246999598.14196356
2453302.281091846999366.248726552451066.22281674 6997379.8996082
#Sta/Elev= 30
    -100     440     -30   430.8    1810   431.9    1810   426.6  1849.5   417.8
  2148.5   415.8    2186   415.9    2188     428    2188   433.3    3537   436.6
    4030   442.8    4030   441.5    4088   417.5    4171     417    4316   418.4
    4396   415.6    4556   414.1    4581  403.38    4589  401.49    4635   401.4
    4715   397.1    4755   408.3    4771   409.7    4780     418    4796   432.2
    4800     439    4848     440    4850   441.2    4850   450.1    6850   450.1
#Mann= 3 ,0,0
    -100    .055       0    4556     .05       0    4780    .055       0
Bank Sta=4556,4780
XS Rating Curve= 0 ,0
Exp/Cntr=0.5,0.3

Type RM Length L Ch R = 3 ,37326   ,,,
BEGIN DESCRIPTION:
Burlington Northern Railroad
END DESCRIPTION:
Node Name=BN Railroad
Bridge Culvert--1,0,-1,-1, 0
Deck Dist Width WeirC Skew NumUp NumDn MinLoCord MaxHiCord MaxSubmerge Is_Ogee
2,16,2.6,0, 47, 47, , , 0.95, 0, ,,,
    1810  1849.5  1854.5  1891.5  1896.5  1933.5  1938.5  1975.5  1980.5  2017.5
  2022.5  2059.5  2064.5  2101.5  2106.5  2143.5  2148.5    2188    2188    3537
    4030    4030    4079    4087    4132    4140    4185    4193    4238    4246
    4291    4299    4344    4352    4397    4405    4450    4458    4501    4509
    4581    4589    4681    4689    4771    4779    4850
   431.9  432.05  432.06   432.2  432.22  432.36  432.38  432.51  432.53  432.67
  432.69  432.82  432.84  432.98     433  433.14  433.15   433.3   433.3   436.6
   442.8   442.8  443.25  443.33  443.74  443.82  444.24  444.31  444.73   444.8
  445.22  445.29  445.71  445.78   446.2  446.27  446.69  446.76  447.16  447.24
  447.96  448.02  448.76  448.82  449.47  449.53   450.1
   426.6  426.75  426.76   426.9  426.92  427.06  427.08  427.21  427.23  427.37
  427.39  427.52  427.54  427.68   427.7  427.84  427.85     428   433.3   436.6
   442.8   441.5  441.94  442.02  442.42   442.5   442.9  442.98  443.38  443.46
  443.86  443.94  444.34  444.41  444.82  444.89   445.3  445.37  445.76  438.81
  438.99  437.53  438.21  438.26  438.87  440.63   441.2
    1810  1849.5  1854.5  1891.5  1896.5  1933.5  1938.5  1975.5  1980.5  2017.5
  2022.5  2059.5  2064.5  2101.5  2106.5  2143.5  2148.5    2188    2188    3537
    4030    4030    4079    4087    4132    4140    4185    4193    4238    4246
    4291    4299    4344    4352    4397    4405    4450    4458    4501    4509
    4581    4589    4681    4689    4771    4779    4850
   431.9  432.05  432.06   432.2  432.22  432.36  432.38  432.51  432.53  432.67
  432.69  432.82  432.84  432.98     433  433.14  433.15   433.3   433.3   436.6
   442.8   442.8  443.25  443.33  443.74  443.82  444.24  444.31  444.73   444.8
  445.22  445.29  445.71  445.78   446.2  446.27  446.69  446.76  447.16  447.24
  447.96  448.02  448.76  448.82  449.47  449.53   450.1
   426.6  426.75  426.76   426.9  426.92  427.06  427.08  427.21  427.23  427.37
  427.39  427.52  427.54  427.68   427.7  427.84  427.85     428   433.3   436.6
   442.8   441.5  441.94  442.02  442.42   442.5   442.9  442.98  443.38  443.46
  443.86  443.94  444.34  444.41  444.82  444.89   445.3  445.37  445.76  438.81
  438.99  437.53  438.21  438.26  438.87  440.63   441.2
Pier Skew, UpSta & Num, DnSta & Num=  ,1852, 2 ,1852, 2 , 0 , 0 , 0 ,,
       5       5
     415     430
       5       5
     415     430
Pier Skew, UpSta & Num, DnSta & Num=  ,1894, 2 ,1894, 2 , 0 , 0 , 0 ,,
       5       5
     415     430
       5       5
     415     430
Pier Skew, UpSta & Num, DnSta & Num=  ,1936, 2 ,1936, 2 , 0 , 0 , 0 ,,
       5       5
     415     430
       5       5
     415     430
Pier Skew, UpSta & Num, DnSta & Num=  ,1978, 2 ,1978, 2 , 0 , 0 , 0 ,,
       5       5
     415     430
       5       5
     415     430
Pier Skew, UpSta & Num, DnSta & Num=  ,2020, 2 ,2020, 2 , 0 , 0 , 0 ,,
       5       5
     415     430
       5       5
     415     430
Pier Skew, UpSta & Num, DnSta & Num=  ,2062, 2 ,2062, 2 , 0 , 0 , 0 ,,
       5       5
     415     430
       5       5
     415     430
Pier Skew, UpSta & Num, DnSta & Num=  ,2104, 2 ,2104, 2 , 0 , 0 , 0 ,,
       5       5
     415     430
       5       5
     415     430
Pier Skew, UpSta & Num, DnSta & Num=  ,2146, 2 ,2146, 2 , 0 , 0 , 0 ,,
       5       5
     415     430
       5       5
     415     430
Pier Skew, UpSta & Num, DnSta & Num=  ,4083, 2 ,4083, 2 , 0 , 0 , 0 ,,
       8       8
     410     442
       8       8
     410     442
Pier Skew, UpSta & Num, DnSta & Num=  ,4136, 2 ,4136, 2 , 0 , 0 , 0 ,,
       8       8
     410     443
       8       8
     410     443
Pier Skew, UpSta & Num, DnSta & Num=  ,4189, 2 ,4189, 2 , 0 , 0 , 0 ,,
       8       8
     410     444
       8       8
     410     444
Pier Skew, UpSta & Num, DnSta & Num=  ,4242, 2 ,4242, 2 , 0 , 0 , 0 ,,
       8       8
     410     444
       8       8
     410     444
Pier Skew, UpSta & Num, DnSta & Num=  ,4295, 2 ,4295, 2 , 0 , 0 , 0 ,,
       8       8
     410     444
       8       8
     410     444
Pier Skew, UpSta & Num, DnSta & Num=  ,4348, 2 ,4348, 2 , 0 , 0 , 0 ,,
       8       8
     410     445
       8       8
     410     445
Pier Skew, UpSta & Num, DnSta & Num=  ,4401, 2 ,4401, 2 , 0 , 0 , 0 ,,
       8       8
     410     445
       8       8
     410     445
Pier Skew, UpSta & Num, DnSta & Num=  ,4454, 2 ,4454, 2 , 0 , 0 , 0 ,,
       8       8
     410     445
       8       8
     410     445
Pier Skew, UpSta & Num, DnSta & Num=  ,4505, 2 ,4505, 2 , 0 , 0 , 0 ,,
       8       8
     390     446
       8       8
     390     446
Pier Skew, UpSta & Num, DnSta & Num=  ,4585, 2 ,4585, 2 , 0 , 0 , 0 ,,
       8       8
     390     446
       8       8
     390     446
Pier Skew, UpSta & Num, DnSta & Num=  ,4685, 2 ,4685, 2 , 0 , 0 , 0 ,,
       8       8
     390     446
       8       8
     390     446
Pier Skew, UpSta & Num, DnSta & Num=  ,4775, 2 ,4775, 2 , 0 , 0 , 0 ,,
       8       8
     390     446
       8       8
     390     446
BR Coef= 1 , 0 , 0 ,1.05, 0 ,,,0.8,-1,0.5,1,
WSPro=,,,, 1 ,,,, 0 ,,,, 0 ,,,,-1 ,-1 ,-1 , 0 , 0 , 0 , 0 , 0
BC Design=,, 0 ,, 0 ,,,,,,
BC HTab HWMax=450.1
BC Use User HTab Curves=0
BC User HTab FreeFlow(D)= 0

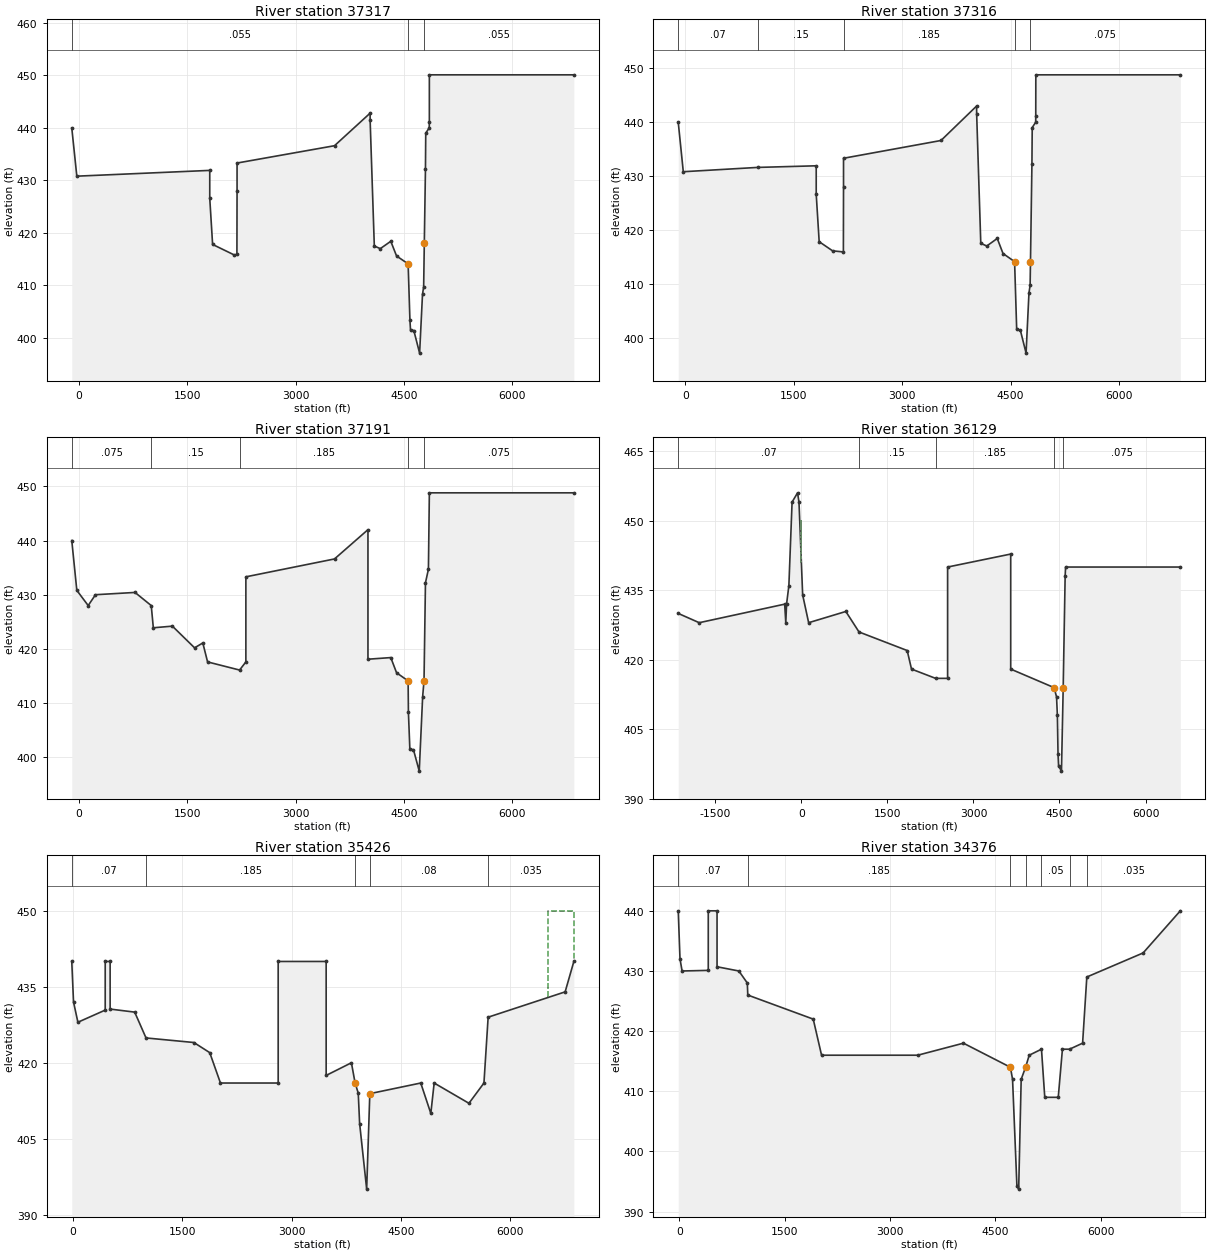
Type RM Length L Ch R = 1 ,37317   ,1,1,1
BEGIN DESCRIPTION:
This cross section corresponds to cross section 37298 of the non-georeferenced CDC model which was the source of this model.
END DESCRIPTION:
XS GIS Cut Line= 6
 2454555.66933317003020.430066472454230.642752177000966.15300705
2453906.289070167000089.583565972453549.882630776999591.12885422
2453317.539919596999359.582073212451081.265758266997373.63392849
#Sta/Elev= 30
    -100     440     -30   430.8    1810   431.9    1810   426.6  1849.5   417.8
  2148.5   415.8    2186   415.9    2188     428    2188   433.3    3537   436.6
    4030   442.8    4030   441.5    4088   417.5    4171     417    4316   418.4
    4396   415.6    4556   414.1    4581  403.38    4589  401.49    4635   401.4
    4715   397.1    4755   408.3    4771   409.7    4780     418    4796   432.2
    4800     439    4848     440    4850   441.2    4850   450.1    6850   450.1
#Mann= 3 ,0,0
    -100    .055       0    4556     .05       0    4780    .055       0
Bank Sta=4556,4780
XS Rating Curve= 0 ,0
Exp/Cntr=0.5,0.3

Type RM Length L Ch R = 1 ,37316   ,98,125,98
BEGIN DESCRIPTION:
This cross section corresponds to cross section 37297 of the non-georeferenced CDC model which was the source of this model.
END DESCRIPTION:
XS GIS Cut Line= 6
2454556.616837777003020.010447892454231.56729099 7000965.7366693
2453907.140446427000089.20036463  2453550.7143226999590.75943239
2453318.336834016999359.225118552451082.057928556997373.30469787
#Sta/Elev= 30
    -100     440     -30   430.8    1000   431.6    1810   431.9    1810   426.6
    1851   417.8    2037   416.1    2186   415.9    2188     428    2188   433.3
    3537   436.6    4030     443    4031   441.5    4088   417.5    4171     417
    4316   418.4    4396   415.6    4556   414.1    4585   401.5    4635   401.4
    4715   397.1    4755   408.3    4771   409.7    4776   414.1    4796   432.2
    4800     439    4848     440    4849   441.2    4850   448.8    6850   448.8
#Mann= 5 ,-1,0
    -100     .07       0    1000     .15       0    2188    .185       0
    4556     .05       0    4776    .075       0
Bank Sta=4556,4776
XS Rating Curve= 0 ,0
Exp/Cntr=0.3,0.1

Type RM Length L Ch R = 1 ,37191   ,600,1062,1150
BEGIN DESCRIPTION:
This cross section corresponds to cross section 37169 of the non-georeferenced CDC model which was the source of this model.
END DESCRIPTION:
XS GIS Cut Line= 6
2454672.473233347002931.723879052454367.111967417000980.50894947
2454053.927882497000099.068127052453657.183925336999543.50296521
2453421.747060276999314.891217722451157.647179466997308.33043539
#Sta/Elev= 30
    -100     440     -30   430.8  127.31     428  228.07     430  775.63  430.42
    1000     428    1029   423.9    1293   424.2    1600   420.2    1714   421.1
    1780   417.6    2223   416.1    2310   417.6    2310   433.3    3537   436.6
    4000     442    4000   418.1    4316   418.4    4396   415.6    4556   414.1
    4560   408.3    4580   401.5    4630   401.4    4710  397.45    4757   411.2
    4776   414.1    4796   432.2    4837   434.7    4850   448.8    6850   448.8
#Mann= 5 ,-1,0
    -100    .075       0    1000     .15       0    2223    .185       0
    4556     .05       0    4776    .075       0
Bank Sta=4556,4776
XS Rating Curve= 0 ,0
Exp/Cntr=0.3,0.1

Type RM Length L Ch R = 1 ,36129   ,438,703,547
BEGIN DESCRIPTION:
This cross section corresponds to cross section 36107 of the non-georeferenced CDC model which was the source of this model.
END DESCRIPTION:
XS GIS Cut Line= 6
2455052.236909517005056.261624722454752.938951677002941.94269063
2454491.786914917000670.694936542453845.071016766998646.27214813
2453850.06280467 6998440.25549982453898.508629526996440.84233538
#Sta/Elev= 30
 -2146.1     430 -1780.4     428  -290.3     432  -271.1     428  -257.6     432
  -217.2     436  -161.4     454   -66.1     456     -41     454   22.95     434
  127.31     428  775.63  430.42  1005.5     426  1845.3     422  1920.6     418
  2340.7     416    2550     416    2550     440    3650   442.8    3650     418
  4406.9     414  4449.1     412  4463.7     408    4475   399.6    4485   397.1
    4535     396  4565.1     414    4599     438  4606.8     440  6606.8     440
#Mann= 5 ,-1,0
 -2146.1     .07       0  1005.5     .15       0  2340.7    .185       0
  4406.9     .05       0  4565.1    .075       0
#XS Ineff= 2 , 0
       0    1.03     450               0
Permanent Ineff=
       F       F
Bank Sta=4406.9,4565.1
XS Rating Curve= 0 ,0
Exp/Cntr=0.3,0.1

Type RM Length L Ch R = 1 ,35426   ,314,1050,195
BEGIN DESCRIPTION:
This cross section corresponds to cross section 35400 of the non-georeferenced CDC model which was the source of this model.
STA 354+00  New X-section
---------------------------------------------------------------------
CDC IRV082109-1 NORTHWEST LEVEE SEEPAGE CONTROL
CROSS-SECTION 13293 - 55400
UPSTREAM END
---------------------------------------------------------------------
END DESCRIPTION:
XS GIS Cut Line= 6
 2454794.62948517002909.716705222454637.936885097001911.17605138
2454633.30369225 7001849.90616082454572.889114927000012.10799913
2454201.420369686997699.429553632454236.189985196996065.33177197
#Sta/Elev= 30
   -18.7     440     5.4     432    65.4     428   440.1   430.4   440.1     440
   507.6     440   507.6   430.6   844.5     430    1000   424.9  1656.8     424
    1874     422  2021.1     416    2813     416    2813     440  3471.3     440
  3471.3   417.5  3817.6     420  3868.4     416  3911.5     414  3930.4     408
    4027  395.05  4070.2   413.9  4768.9     416  4907.2     410  4952.9     416
  5430.1     412    5636     416 5693.44     429 6749.83     434 6869.23     440
#Mann= 5 ,-1,0
   -18.7     .07       0    1000    .185       0  3868.4     .05       0
  4070.2     .08       0 5693.44    .035       0
#XS Ineff= 2 , 0
       0                    6520       0     450
Permanent Ineff=
       F       F
Bank Sta=3868.4,4070.2
XS Rating Curve= 0 ,0
Exp/Cntr=0.3,0.1

Type RM Length L Ch R = 1 ,34376   ,15,34,43
BEGIN DESCRIPTION:
This cross section corresponds to cross section 34430 of the non-georeferenced CDC model which was the source of this model.
STA 344+30  New X-section
END DESCRIPTION:
XS GIS Cut Line= 6
    2454898.32587002890.412609962454651.234102587001975.48563404
2454640.112733757001901.505467042454684.47156891 6999091.0475053
2454690.305874826996401.708067722454698.22777501 6995778.5521618
#Sta/Elev= 30
   -14.1     440    11.1     432    40.9     430   413.3   430.1   413.3     440
   538.3     440   538.3   430.7   848.6     430     969     428   975.7     426
  1907.1     422  2025.8     416  3394.6     416  4044.7     418  4713.2     414
 4743.91     412    4806  394.24    4831  393.74  4866.7     412  4929.3     414
    4981     416 5155.58     417 5202.36     409 5394.21     409 5453.74     417
  5554.8     417  5740.8     418  5800.8     429 6602.11     433 7131.39     440
#Mann= 7 ,-1,0
   -14.1     .07       0   975.7    .185       0  4713.2     .05       0
  4929.3     .08       0 5155.58     .05       0  5554.8     .08       0
  5800.8    .035       0
Bank Sta=4713.2,4929.3
XS Rating Curve= 0 ,0
Exp/Cntr=0.3,0.1