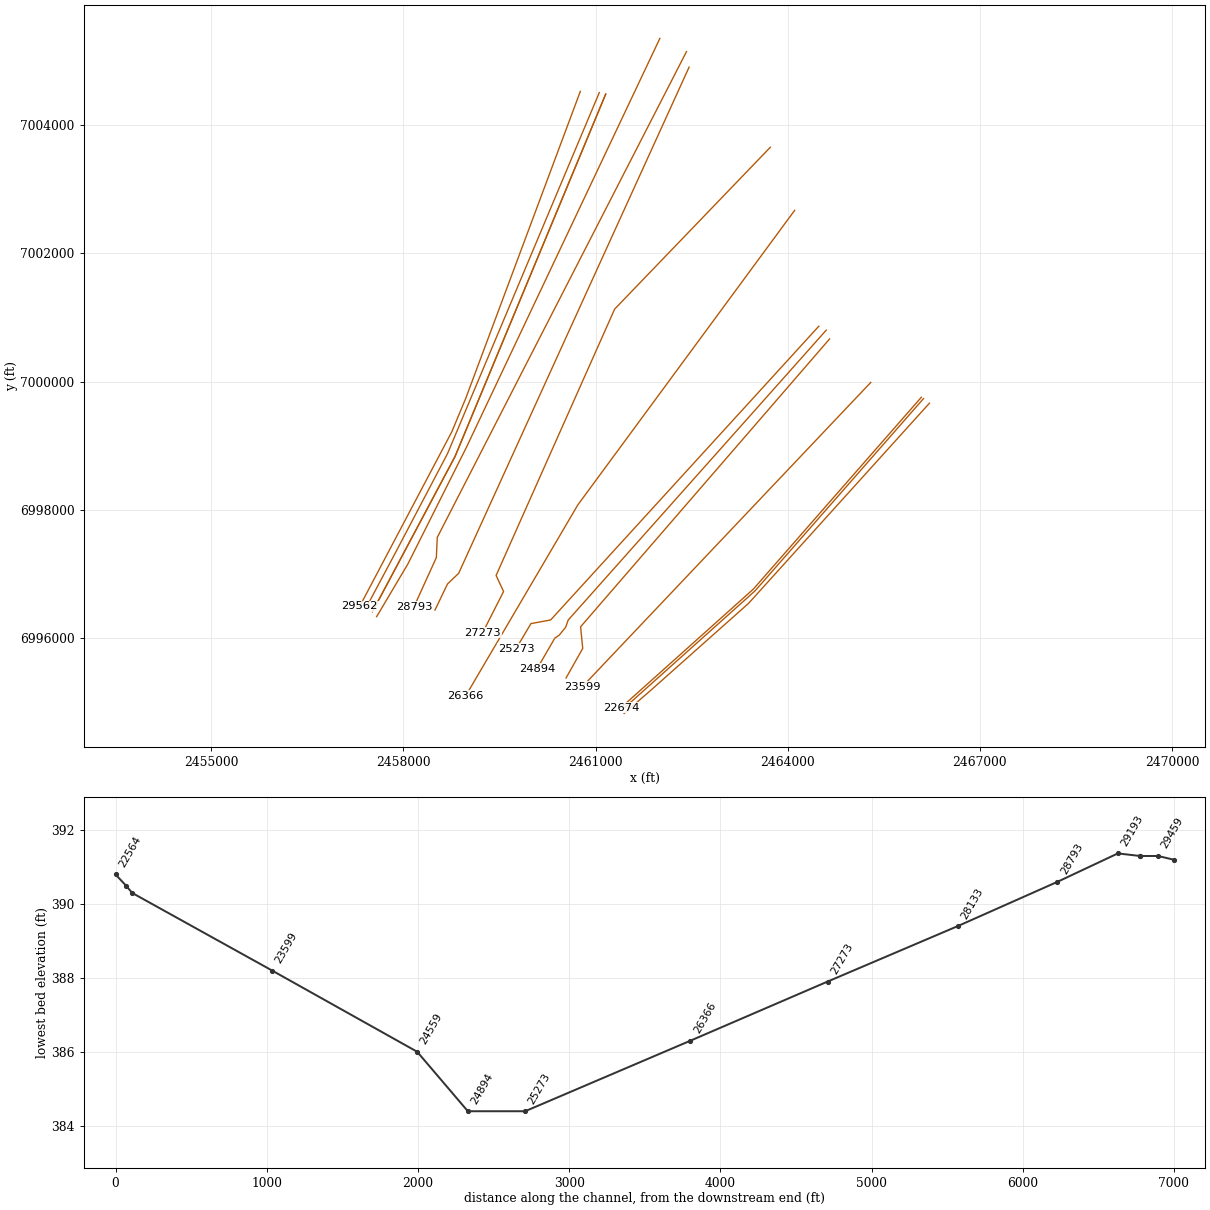
HEC-RAS study CDC_Consolidated_Model.prj: Upper Trinity CDC Consolidated Model

--- CDC_Consolidated_Model.g02 (geometry) --- (continued)

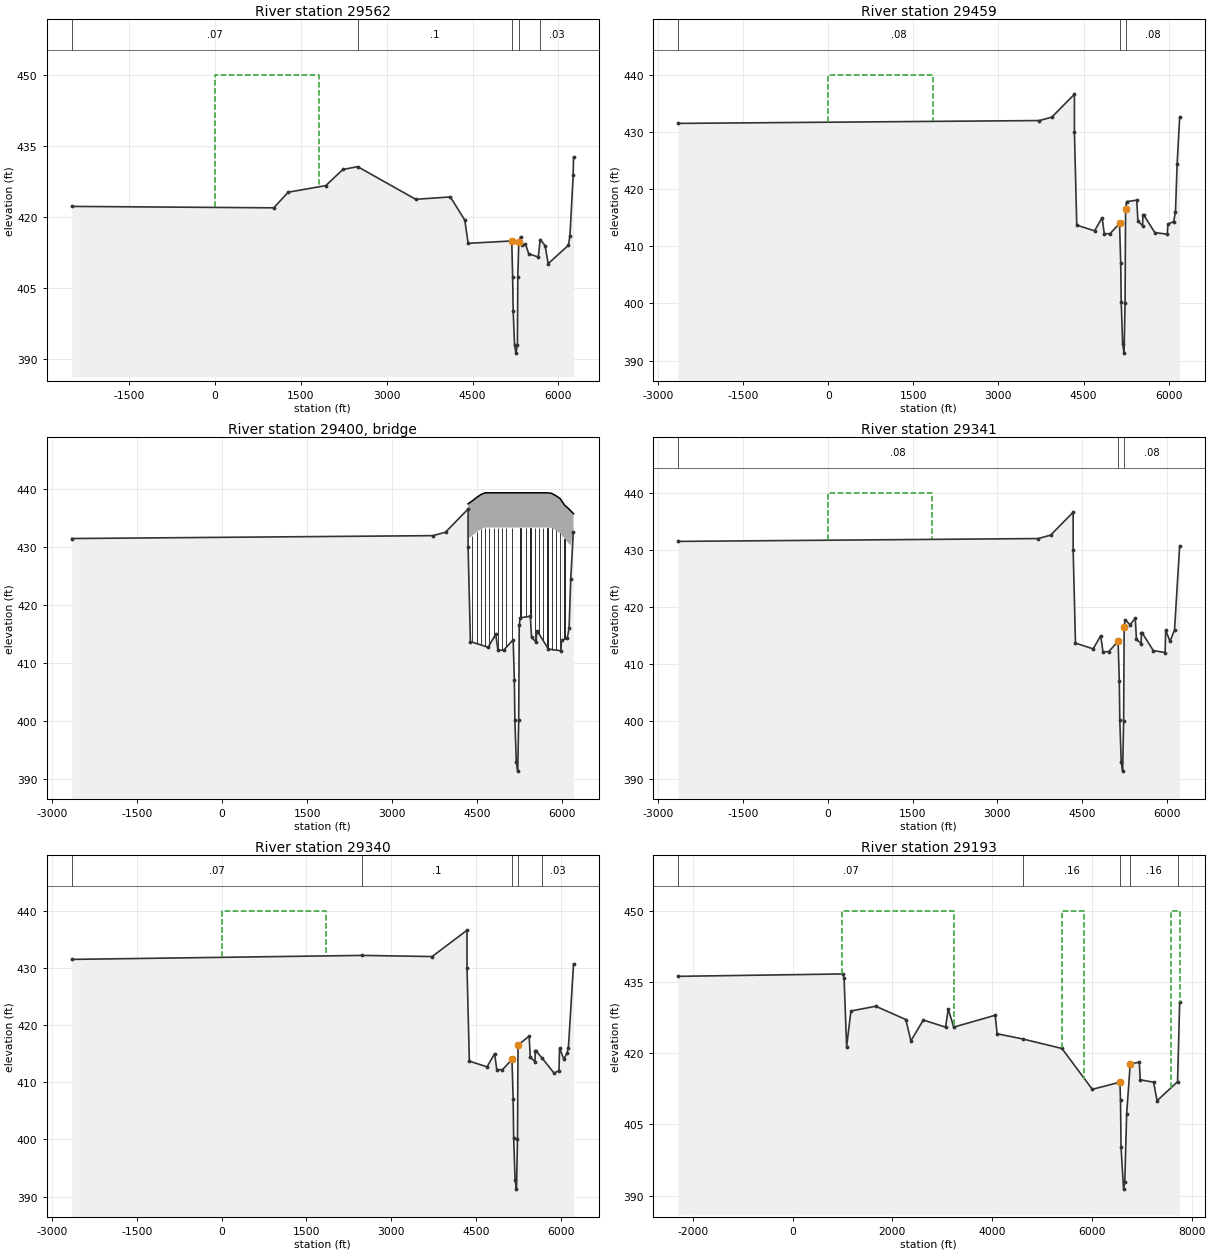
Type RM Length L Ch R = 1 ,29562   ,103,103,103
BEGIN DESCRIPTION:
This cross section corresponds to cross section 29539 of the non-georeferenced CDC model which was the source of this model.
Right Overbank updated with 2007 levee topo.
END DESCRIPTION:
XS GIS Cut Line= 5
2460761.552754427004531.063646032459537.779775687001251.98150364
2458974.645075176999743.070151392458755.869922166999217.50099255
2457317.215975346996490.42869081
#Sta/Elev= 30
   -2500   422.2    1028   421.9    1280   425.2    1937   426.6    2235     430
    2493   430.6    3507   423.7    4112   424.2    4364   419.3    4423   414.4
    5184   414.9    5200   407.3    5209   400.2    5233   392.9    5258   391.2
    5283   392.9    5290   407.3    5307   414.6    5339   415.8    5357     414
    5422   414.3    5481   412.2    5647   411.5    5682   415.2    5767   413.9
    5820   410.1 6174.93     414 6200.25     416 6257.05  428.77 6263.14   432.6
#Mann= 5 ,-1,0
   -2500     .07       0    2493      .1       0    5184     .05       0
    5307      .1       0    5682     .03       0
#XS Ineff= 2 , 0
       0    1820     450               0
Permanent Ineff=
       F       F
Bank Sta=5184,5307
XS Rating Curve= 0 ,0
Exp/Cntr=0.3,0.1

Type RM Length L Ch R = 1 ,29459   ,118,118,118
BEGIN DESCRIPTION:
This cross section corresponds to cross section 29438 of the non-georeferenced CDC model which was the source of this model.
Right Overbank updated with 2007 levee topo.
END DESCRIPTION:
XS GIS Cut Line= 5
2461057.618049797004512.107408382459313.870774697000363.69259781
2458687.587250356998873.749711542457872.600035166997323.13339022
2457413.172804426996460.78668971
#Sta/Elev= 30
   -2650   431.5    3723     432    3942   432.6    4340   436.6    4340     430
    4381   413.7    4694   412.7    4828     415  4866.5   412.2    4967   412.2
    5135     414    5156   407.1    5165   400.2    5190   392.9    5215   391.3
 5232.66  400.08    5242   416.5    5259   417.8  5438.5  418.07    5459   414.4
    5542   413.6    5547   415.4    5560   415.5    5757   412.4    5977   412.1
  5988.1   413.9 6089.21  414.31 6121.02     416 6150.63  424.47 6195.06   432.6
#Mann= 3 ,0,0
   -2650     .08       0    5135     .05       0    5242     .08       0
#XS Ineff= 2 , 0
       0    1850     440               0
Permanent Ineff=
       F       F
Bank Sta=5135,5242
XS Rating Curve= 0 ,0
Exp/Cntr=0.5,0.3

Type RM Length L Ch R = 3 ,29400   ,,,
BEGIN DESCRIPTION:
Loop 12/Walton Walker Boulevard
END DESCRIPTION:
Node Name=Loop 12
Bridge Culvert--1,0,-1,-1, 0
Deck Dist Width WeirC Skew NumUp NumDn MinLoCord MaxHiCord MaxSubmerge Is_Ogee
2,115,2.6,0, 45, 45, , , 0.95, 0, ,,,
    4340 4413.75 4416.25 4488.75 4491.25  4563.5  4566.5  4638.5  4641.5  4713.5
  4716.5  4788.5  4791.5  4863.5  4866.5  4938.5  4941.5  5013.5  5016.5  5113.5
  5116.5  5263.5  5266.5  5363.5  5366.5  5438.5  5441.5  5513.5  5516.5  5588.5
  5591.5  5663.5  5666.5 5738.75 5741.25 5813.75 5816.25 5888.75 5891.25 5963.75
 5966.25 6038.75 6041.25    6120 6199.69
   437.5     438  438.01  438.59 438.608  439.09 439.106 439.394   439.4   439.4
   439.4   439.4   439.4   439.4   439.4   439.4   439.4   439.4   439.4   439.4
   439.4   439.4   439.4   439.4   439.4   439.4   439.4   439.4   439.4   439.4
   439.4   439.4   439.4   439.4   439.4 439.302 439.293 438.907 438.892 438.408
 438.387 437.318 437.288   436.6  435.79
   431.5     432  432.01  432.59 432.608  433.09 433.106 433.394   433.4   433.4
   433.4   433.4   433.4   433.4   433.4   433.4   433.4   433.4   433.4   433.4
   433.4   433.4   433.4   433.4   433.4   433.4   433.4   433.4   433.4   433.4
   433.4   433.4   433.4   433.4   433.4 433.302 433.293 432.907 432.892 432.408
 432.387 431.521 431.491   430.6  429.79
    4340 4413.75 4416.25 4488.75 4491.25  4563.5  4566.5  4638.5  4641.5  4713.5
  4716.5  4788.5  4791.5  4863.5  4866.5  4938.5  4941.5  5013.5  5016.5  5113.5
  5116.5  5263.5  5266.5  5363.5  5366.5  5438.5  5441.5  5513.5  5516.5  5588.5
  5591.5  5663.5  5666.5 5738.75 5741.25 5813.75 5816.25 5888.75 5891.25 5963.75
 5966.25 6038.75 6041.25    6120 6225.87
   437.5     438  438.01  438.59 438.608  439.09 439.106 439.394   439.4   439.4
   439.4   439.4   439.4   439.4   439.4   439.4   439.4   439.4   439.4   439.4
   439.4   439.4   439.4   439.4   439.4   439.4   439.4   439.4   439.4   439.4
   439.4   439.4   439.4   439.4   439.4 439.302 439.293 438.907 438.892 438.408
 438.387 437.318 437.288   436.6  435.79
   431.5     432  432.01  432.59 432.608  433.09 433.106 433.394   433.4   433.4
   433.4   433.4   433.4   433.4   433.4   433.4   433.4   433.4   433.4   433.4
   433.4   433.4   433.4   433.4   433.4   433.4   433.4   433.4   433.4   433.4
   433.4   433.4   433.4   433.4   433.4 433.302 433.293 432.907 432.892 432.408
 432.387 431.521 431.491   430.6  429.79
Pier Skew, UpSta & Num, DnSta & Num=  ,4415, 2 ,4415, 2 , 0 , 0 , 0 ,,
     2.5     2.5
     390     444
     2.5     2.5
     390     444
Pier Skew, UpSta & Num, DnSta & Num=  ,4490, 2 ,4490, 2 , 0 , 0 , 0 ,,
     2.5     2.5
     390     444
     2.5     2.5
     390     444
Pier Skew, UpSta & Num, DnSta & Num=  ,4565, 2 ,4565, 2 , 0 , 0 , 0 ,,
       3       3
     390     444
       3       3
     390     444
Pier Skew, UpSta & Num, DnSta & Num=  ,4641, 2 ,4641, 2 , 0 , 0 , 0 ,,
       3       3
     390     444
       3       3
     390     444
Pier Skew, UpSta & Num, DnSta & Num=  ,4715, 2 ,4715, 2 , 0 , 0 , 0 ,,
       3       3
     390     444
       3       3
     390     444
Pier Skew, UpSta & Num, DnSta & Num=  ,4790, 2 ,4790, 2 , 0 , 0 , 0 ,,
       3       3
     390     444
       3       3
     390     444
Pier Skew, UpSta & Num, DnSta & Num=  ,4865, 2 ,4865, 2 , 0 , 0 , 0 ,,
       3       3
     390     444
       3       3
     390     444
Pier Skew, UpSta & Num, DnSta & Num=  ,4940, 2 ,4940, 2 , 0 , 0 , 0 ,,
       3       3
     390     444
       3       3
     390     444
Pier Skew, UpSta & Num, DnSta & Num=  ,5015, 2 ,5015, 2 , 0 , 0 , 0 ,,
       3       3
     390     444
       3       3
     390     444
Pier Skew, UpSta & Num, DnSta & Num=  ,5115, 2 ,5115, 2 , 0 , 0 , 0 ,,
       3       3
     390     444
       3       3
     390     444
Pier Skew, UpSta & Num, DnSta & Num=  ,5265, 2 ,5265, 2 , 0 , 0 , 0 ,,
       3       3
     390     444
       3       3
     390     444
Pier Skew, UpSta & Num, DnSta & Num=  ,5365, 2 ,5365, 2 , 0 , 0 , 0 ,,
       3       3
     390     444
       3       3
     390     444
Pier Skew, UpSta & Num, DnSta & Num=  ,5440, 2 ,5440, 2 , 0 , 0 , 0 ,,
       3       3
     390     444
       3       3
     390     444
Pier Skew, UpSta & Num, DnSta & Num=  ,5515, 2 ,5515, 2 , 0 , 0 , 0 ,,
       3       3
     390     444
       3       3
     390     444
Pier Skew, UpSta & Num, DnSta & Num=  ,5590, 2 ,5590, 2 , 0 , 0 , 0 ,,
       3       3
     390     444
       3       3
     390     444
Pier Skew, UpSta & Num, DnSta & Num=  ,5665, 2 ,5665, 2 , 0 , 0 , 0 ,,
       3       3
     390     444
       3       3
     390     444
Pier Skew, UpSta & Num, DnSta & Num=  ,5740, 2 ,5740, 2 , 0 , 0 , 0 ,,
     2.5     2.5
     390     444
     2.5     2.5
     390     444
Pier Skew, UpSta & Num, DnSta & Num=  ,5815, 2 ,5815, 2 , 0 , 0 , 0 ,,
     2.5     2.5
     390     444
     2.5     2.5
     390     444
Pier Skew, UpSta & Num, DnSta & Num=  ,5890, 2 ,5890, 2 , 0 , 0 , 0 ,,
     2.5     2.5
     390     444
     2.5     2.5
     390     444
Pier Skew, UpSta & Num, DnSta & Num=  ,5965, 2 ,5965, 2 , 0 , 0 , 0 ,,
     2.5     2.5
     390     444
     2.5     2.5
     390     444
Pier Skew, UpSta & Num, DnSta & Num=  ,6040, 2 ,6040, 2 , 0 , 0 , 0 ,,
     2.5     2.5
     390     444
     2.5     2.5
     390     444
BR Coef= 1 , 0 , 0 ,1.05, 0 ,,,0.8,-1,0.5,1,
WSPro=,,,, 1 ,,,, 0 ,,,, 0 ,,,,-1 ,-1 ,-1 , 0 , 0 , 0 , 0 , 0
BC Design=,, 0 ,, 0 ,,,,,,
BC HTab HWMax=436.6
BC Use User HTab Curves=0
BC User HTab FreeFlow(D)= 0

Type RM Length L Ch R = 1 ,29341   ,1,1,1
BEGIN DESCRIPTION:
This cross section corresponds to cross section 29320 of the non-georeferenced CDC model which was the source of this model.
Right Overbank updated with 2007 levee topo.
END DESCRIPTION:
XS GIS Cut Line= 4
2461157.621579477004488.838138672459429.567721757000333.86162071
2458803.524354436998828.587072222457515.645368526996406.39703472
#Sta/Elev= 30
   -2650   431.5    3723     432    3942   432.6    4340   436.6    4340     430
    4381   413.7    4694   412.7    4828     415  4866.5   412.2    4967   412.2
    5135     414    5156   407.1    5165   400.2    5190   392.9    5215   391.3
 5232.66  400.08    5242   416.5    5259   417.8    5347   416.9  5438.5  418.07
    5459   414.4    5542   413.6    5547   415.4    5560   415.5    5757   412.4
 5966.25  412.05 5976.57  415.98 6053.09     414 6132.41     416 6223.56   430.7
#Mann= 3 ,0,0
   -2650     .08       0    5135     .05       0    5242     .08       0
#XS Ineff= 2 , 0
       0    1850     440               0
Permanent Ineff=
       F       F
Bank Sta=5135,5242
XS Rating Curve= 0 ,0
Exp/Cntr=0.5,0.3

Type RM Length L Ch R = 1 ,29340   ,147,147,147
BEGIN DESCRIPTION:
This cross section corresponds to cross section 29319 of the non-georeferenced CDC model which was the source of this model.
Right Overbank updated with 2007 levee topo.
END DESCRIPTION:
XS GIS Cut Line= 4
2461158.115553377004488.565110742459431.03294191 7000333.1847848
2458805.454468676998828.035892222457516.453437756996406.10897756
#Sta/Elev= 30
   -2650   431.5    2484   432.2    3723     432    4340   436.6    4340     430
    4381   413.7    4694   412.7    4828     415  4866.5   412.2    4967   412.2
    5135     414    5156   407.1    5165   400.2    5190   392.9    5215   391.3
 5232.66  400.08    5242   416.5  5438.5  418.07    5459   414.4    5542   413.6
    5547   415.4    5560   415.5  5666.5  414.24    5880   411.6 5966.25  412.05
 5976.57  415.98 6053.09     414 6108.63  415.14 6132.41     416 6223.56   430.7
#Mann= 5 ,-1,0
   -2650     .07       0    2484      .1       0    5135     .05       0
    5242      .1       0  5666.5     .03       0
#XS Ineff= 2 , 0
       0    1850     440               0
Permanent Ineff=
       F       F
Bank Sta=5135,5242
XS Rating Curve= 0 ,0
Exp/Cntr=0.3,0.1

Type RM Length L Ch R = 1 ,29193   ,230,400,390
BEGIN DESCRIPTION:
This cross section corresponds to cross section 29170 of the non-georeferenced CDC model which was the source of this model.
Right Overbank updated with 2007 levee topo.
END DESCRIPTION:
XS GIS Cut Line= 5
2462004.206311227005359.590957272460593.016182247002376.54848021
  2458981.7388936998970.552011392458068.408042526997150.21805364
 2457580.91131416996328.34961863
#Sta/Elev= 30
   -2300   436.2    1010   436.7    1032   435.8    1083   421.4    1169   428.9
    1667   429.9    2270   427.1    2371   422.6    2621     427    3066   425.5
    3121   429.3    3230   425.5    4062     428    4100   424.1    4615     423
    5400     421    6009   412.4    6563   413.9    6574   410.1    6585   400.2
    6635  391.37    6660   392.9    6697   407.2    6769   417.8    6951   418.1
    6969   414.4    7237   413.9 7307.77     410 7717.67     414 7760.08   430.7
#Mann= 5 ,-1,0
   -2300     .07       0    4615     .16       0    6563     .05       0
    6769     .16       0 7717.67     .03       0
#XS Ineff= 3 ,-1
    1000    3230     450    5400    5850     450    7580 7760.08     450
Permanent Ineff=
       F       F       F
Bank Sta=6563,6769
XS Rating Curve= 0 ,0
Exp/Cntr=0.3,0.1

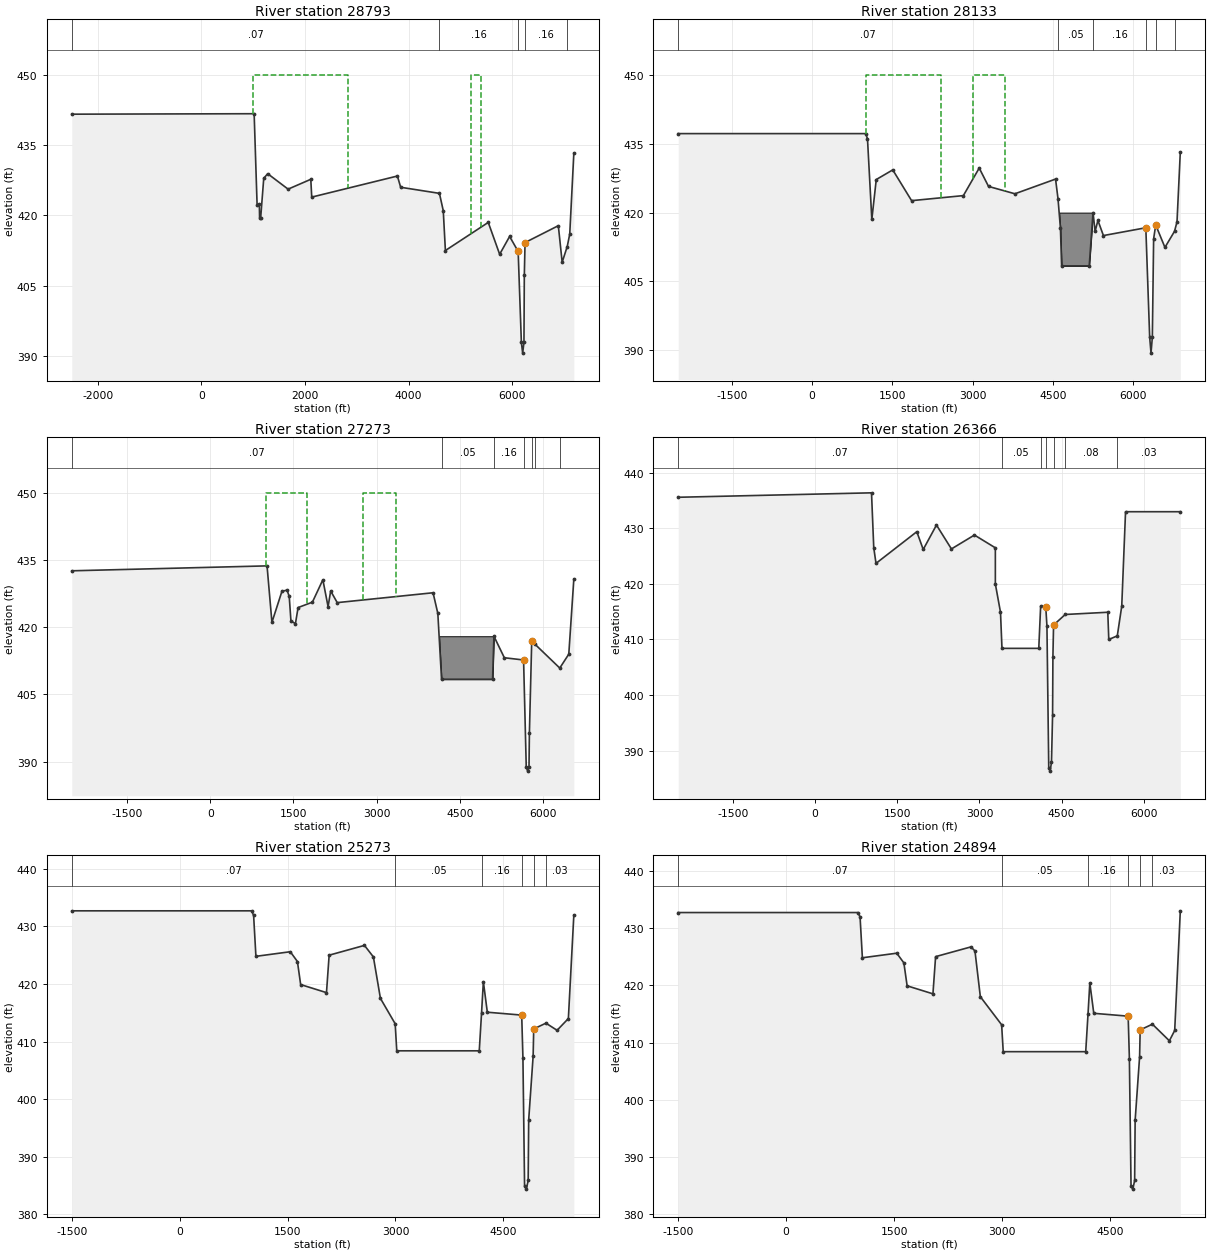
Type RM Length L Ch R = 1 ,28793   ,529,660,339
BEGIN DESCRIPTION:
This cross section corresponds to cross section 28770 of the non-georeferenced CDC model which was the source of this model.
Right Overbank updated with 2007 levee topo.
END DESCRIPTION:
XS GIS Cut Line= 5
2462419.249360357005151.46204691 2460821.65483267002037.35033971
2458527.822149936997566.09615888  2458512.9760516997250.61516255
2458162.704113756996480.13179538
#Sta/Elev= 30
   -2500   441.6    1019   441.7    1076   422.2    1119   422.4    1124   419.5
    1145   419.5    1204   427.9    1280   428.9    1674   425.6    2112   427.7
    2130   423.9    3783   428.4    3846     426    4594   424.7    4668     421
    4709   412.5    5536   418.5    5756   411.7    5948   415.5    6113   412.3
    6175   392.9    6200   390.6    6225   392.9    6232   407.2    6246   414.2
    6888   417.8 6962.14     410 7059.91  413.35 7108.28     416 7187.51   433.3
#Mann= 5 ,-1,0
   -2500     .07       0    4594     .16       0    6113     .05       0
    6246     .16       0 7059.91     .03       0
#XS Ineff= 2 ,-1
    1000    2830     450    5200    5400     450
Permanent Ineff=
       F       F
Bank Sta=6113,6246
XS Rating Curve= 0 ,0
Exp/Cntr=0.3,0.1

Type RM Length L Ch R = 1 ,28133   ,550,860,840
BEGIN DESCRIPTION:
This cross section corresponds to cross section 28109 of the non-georeferenced CDC model which was the source of this model.
Right Overbank updated with 2007 levee topo.
END DESCRIPTION:
XS GIS Cut Line= 5
 2462460.44887437004910.22740512 2461010.26830057001724.79551864
2458861.859867666997005.653054042458687.417959336996838.63403113
2458491.851749426996431.53838864
#Sta/Elev= 30
   -2500   437.2    1000   437.2    1035   436.1    1116   418.5    1199   427.2
    1507   429.3    1859   422.6    2826   423.7    3122   429.7    3296   425.7
    3789   424.1    4548   427.3    4594     423    4639   416.6    4661   408.4
    5177   408.4    5248     420    5287   415.9    5339   418.3    5442     415
    6234   416.7    6306   392.9    6331   389.4    6356   392.9    6380   414.3
    6419   417.3  6591.2  412.42 6770.37  415.93 6816.63     418 6878.35   433.2
#Mann= 6 ,-1,0
   -2500     .07       0    4594     .05       0    5248     .16       0
    6234     .05       0    6419     .16       0 6770.37     .03       0
#XS Ineff= 2 ,-1
    1000    2400     450    3000    3600     450
Permanent Ineff=
       F       F
#Block Obstruct= 2 ,-1
                            4607    5248     420
Bank Sta=6234,6419
XS Rating Curve= 0 ,0
Exp/Cntr=0.3,0.1

Type RM Length L Ch R = 1 ,27273   ,700,907,400
BEGIN DESCRIPTION:
This cross section corresponds to cross section 27249 of the non-georeferenced CDC model which was the source of this model.
Right Overbank updated with 2007 levee topo.
END DESCRIPTION:
XS GIS Cut Line= 6
 2463729.0261799 7003658.81911182461302.577755247001136.44958247
2461297.64797509 7001131.32492082459446.397084426996971.78402729
2459563.31089258 6996721.25500082459236.204919526996078.32124729
#Sta/Elev= 30
   -2500   432.6    1023   433.7    1111   421.1    1291     428    1383   428.3
    1423   426.9    1454   421.4    1535   420.8    1583   424.4    1841   425.6
    2030   430.6    2124   424.6    2171   428.1    2289   425.5    4018   427.7
    4104   423.1    4171   408.4    5092   408.4    5116     418    5304   413.2
    5651   412.7    5699   388.9    5724   387.9    5749   388.9    5756   396.4
    5798     417    5858   416.2 6303.86   410.9 6466.67     414 6557.84   430.8
#Mann= 7 ,-1,0
   -2500     .07       0    4171     .05       0    5116     .16       0
    5651     .05       0    5798     .16       0    5858     .08       0
 6303.86     .03       0
#XS Ineff= 2 ,-1
    2750    3350     450    1000    1750     450
Permanent Ineff=
       F       F
#Block Obstruct= 2 ,-1
                            4104    5116     418
Bank Sta=5651,5798
XS Rating Curve= 0 ,0
Exp/Cntr=0.3,0.1

Type RM Length L Ch R = 1 ,26366   ,859,1093,450
BEGIN DESCRIPTION:
This cross section corresponds to cross section 26342 of the non-georeferenced CDC model which was the source of this model.
Right Overbank updated with 2007 levee topo.
---------------------------------------------------------------------
CDC Dallas 050901-1 B&B Lakes Office Site
Located in LOB.
Cross-sections 26342 - 27249
---------------------------------------------------------------------
END DESCRIPTION:
XS GIS Cut Line= 5
2464108.811545847002673.554848022462033.922093096999854.89669938
2460723.404044846998074.607937132459479.393737586995956.42746222
2458972.972018566995094.14152211
#Sta/Elev= 30
   -2500   435.6    1029   436.4    1070   426.5    1111   423.7    1856   429.4
    1973   426.2    2215   430.6    2488   426.3    2908   428.8    3290   426.5
    3290     420    3384   414.9    3411   408.4    4083   408.4    4117     416
    4211   415.8    4232   412.4    4265   386.9    4290   386.3    4315   387.9
    4335   396.4    4341   406.9    4353   412.6    4566   414.5    5343   414.9
 5361.11     410 5516.57  410.65 5597.79     416 5667.13     433 6667.13     433
#Mann= 7 ,-1,0
   -2500     .07       0    3411     .05       0    4117     .16       0
    4211     .05       0    4353     .16       0    4566     .08       0
 5516.57     .03       0
#Block Obstruct= 2 , 0
            4117     416
Bank Sta=4211,4353
XS Rating Curve= 0 ,0
Exp/Cntr=0.3,0.1

Type RM Length L Ch R = 1 ,25273   ,207,379,483
BEGIN DESCRIPTION:
This cross section corresponds to cross section 25248 of the non-georeferenced CDC model which was the source of this model.
Right Overbank updated with 2007 levee topo.
END DESCRIPTION:
XS GIS Cut Line= 5
2464485.704832587000863.586858992462800.08821169 6999017.3212748
2460298.195905756996276.984235792459990.87991935 6996220.1969478
2459757.472249696995827.64720796
#Sta/Elev= 30
   -1500   432.7    1000   432.7    1028   431.9    1060   424.8    1538   425.6
    1637   423.9    1682   419.9    2041   418.5    2078     425    2569   426.7
    2693   424.7    2791   417.5    2996   413.1    3018   408.4    4165   408.4
    4197     415    4222   420.4    4277   415.1    4755   414.6    4772   407.2
    4795   384.9    4820  384.39    4845   385.9    4852   396.4    4914   407.5
    4922   412.2    5092   413.2 5246.85  411.96 5403.73     414 5479.87     432
#Mann= 6 ,-1,0
   -1500     .07       0    2996     .05       0    4197     .16       0
    4755     .05       0    4922     .16       0    5092     .03       0
#Block Obstruct= 2 , 0
            4197     415
Bank Sta=4755,4922
XS Rating Curve= 0 ,0
Exp/Cntr=0.3,0.1

Type RM Length L Ch R = 1 ,24894   ,219,335,370
BEGIN DESCRIPTION:
This cross section corresponds to cross section 24900 of the non-georeferenced CDC model which was the source of this model.
END DESCRIPTION:
XS GIS Cut Line= 6
2464602.615385677000803.267097522460572.26064634 6996275.4212468
2460532.298784026996162.557627382460432.175952766996040.07952589
2460363.263032856995992.982179142460084.030323596995511.23478305
#Sta/Elev= 30
   -1500   432.7    1000   432.7    1028   431.9    1060   424.8    1538   425.6
    1637   423.9    1682   419.9    2041   418.5    2078     425    2569   426.7
    2625     426    2700     418    2996   413.1    3018   408.4    4165   408.4
    4197     415    4222   420.4    4277   415.1    4755   414.6    4772   407.2
    4795   384.9    4820  384.39    4845   385.9    4852   396.4    4914   407.5
    4922   412.2    5092   413.2    5328   410.3    5402   412.1    5480     433
#Mann= 6 ,-1,0
   -1500     .07       0    2996     .05       0    4197     .16       0
    4755     .05       0    4922     .16       0    5092     .03       0
Bank Sta=4755,4922
XS Rating Curve= 0 ,0
Exp/Cntr=0.3,0.1

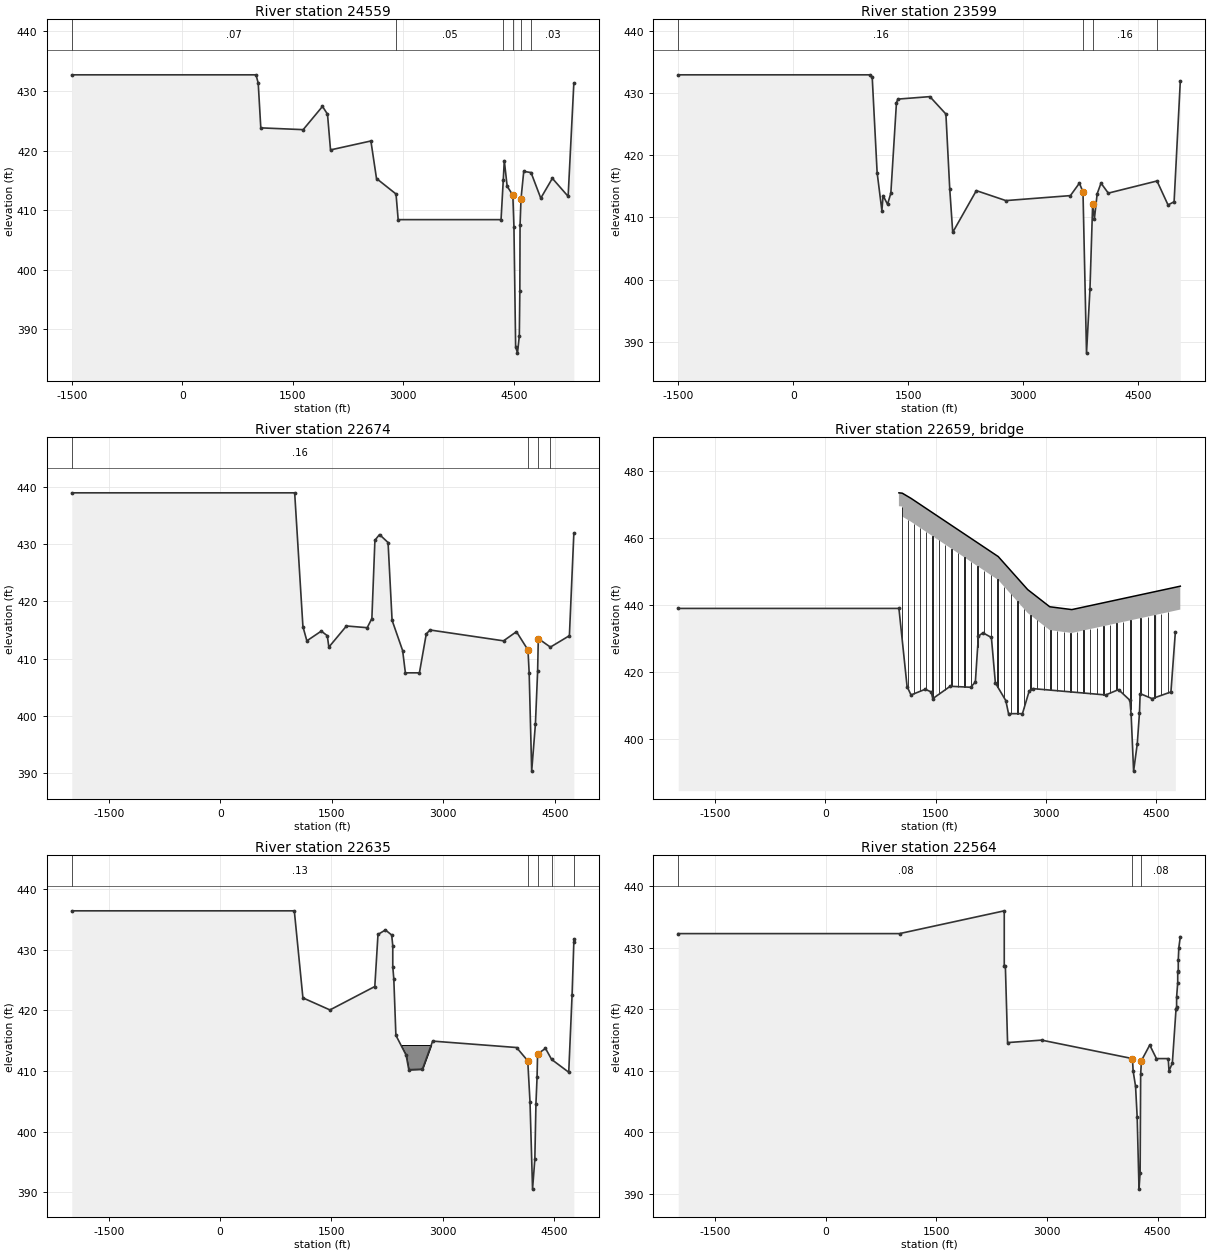
Type RM Length L Ch R = 1 ,24559   ,740,960,400
BEGIN DESCRIPTION:
This cross section corresponds to cross section 24534 of the non-georeferenced CDC model which was the source of this model.
Right Overbank updated with 2007 levee topo.
---------------------------------------------------------------------
CDC Dallas 021800-1 DEA Laboratory
Located in LOB.
Cross-sections 24534 - 25248
---------------------------------------------------------------------
END DESCRIPTION:
XS GIS Cut Line= 5
2464654.130596817000665.476740062463018.658968756998774.64820372
2460765.848841856996170.092061132460799.252974516995832.71314272
2460538.997917596995370.85087746
#Sta/Elev= 30
   -1500   432.7    1000   432.7    1030   431.3    1065   423.8    1640   423.5
    1902   427.4    1970   426.1    2011   420.1    2559   421.6    2635   415.3
    2900   412.7    2929   408.4    4325   408.4    4355     415    4369   418.3
    4408     414    4485   412.5    4500   407.2    4523   387.1    4548     386
    4573   388.9    4580   396.4    4583   407.5    4596   411.9    4633   416.5
    4732   416.3    4864     412 5021.38  415.33 5235.34   412.3 5312.84  431.32
#Mann= 6 ,-1,0
   -1500     .07       0    2900     .05       0    4355     .16       0
    4485     .05       0    4596     .16       0    4732     .03       0
#Block Obstruct= 2 , 0
            4355     415
Bank Sta=4485,4596
XS Rating Curve= 0 ,0
Exp/Cntr=0.3,0.1

Type RM Length L Ch R = 1 ,23599   ,840,925,700
BEGIN DESCRIPTION:
This cross section corresponds to cross section 23574 of the non-georeferenced CDC model which was the source of this model.
Right Overbank updated with 2007 levee topo.
END DESCRIPTION:
XS GIS Cut Line= 3
2465297.408271936999986.549689572463577.522352346998172.16482863
2460792.483631076995234.10246331
#Sta/Elev= 30
   -1500   432.9    1000   432.9    1030   432.5    1094   417.2    1156   411.1
    1172   413.5    1230   412.1    1273   413.9    1346   428.4    1364     429
    1782   429.4    1991   426.6    2041   414.6    2080   407.6    2388   414.3
    2773   412.7    3615   413.5    3732   415.5    3779   414.1    3825   388.2
    3870   398.5    3905   412.1    3928   409.8    3964   413.8    4014   415.5
    4109   413.9  4744.3  415.85 4888.25     412 4967.28  412.51 5048.29   431.9
#Mann= 4 ,-1,0
   -1500     .16       0    3779     .05       0    3905     .16       0
  4744.3     .03       0
Bank Sta=3779,3905
XS Rating Curve= 0 ,0
Exp/Cntr=0.3,0.1

Type RM Length L Ch R = 1 ,22674   ,39,39,39
BEGIN DESCRIPTION:
This cross section corresponds to cross section 22649 of the non-georeferenced CDC model which was the source of this model.
Right Overbank updated with 2007 levee topo.
END DESCRIPTION:
XS GIS Cut Line= 5
2466086.676240926999754.437743742465757.277602466999378.27748935
2464110.284410186997497.476217392463461.233871016996756.28609872
2461396.079208676994906.93809138
#Sta/Elev= 30
   -2000     439    1000     439    1111   415.6    1164   413.1    1358   414.8
    1439     414    1460     412    1697   415.7    1976   415.4    2039     417
    2080   430.7    2142   431.7    2257   430.3    2311   416.7    2453   411.4
    2490   407.5    2679   407.5    2771   414.3    2821     415    3811   413.1
    3985   414.7    4140   411.5    4156   407.5    4190   390.3    4240   398.5
    4270   407.8    4279   413.5 4441.62     412 4697.54     414 4757.38   431.9
#Mann= 4 ,-1,0
   -2000     .16       0    4140     .05       0    4279     .16       0
 4441.62     .03       0
#Block Obstruct= 2 , 0
            2771   414.3
Bank Sta=4140,4279
XS Rating Curve= 0 ,0
Exp/Cntr=0.3,0.1

Type RM Length L Ch R = 3 ,22659   ,,,
BEGIN DESCRIPTION:
DART Northwest Transit Line
END DESCRIPTION:
Node Name=DART
Bridge Culvert--1,0,-1,-1, 0
Deck Dist Width WeirC Skew NumUp NumDn MinLoCord MaxHiCord MaxSubmerge Is_Ogee
3,25,2.6,0, 13, 13, , , 0.98, 0, 0,0,,
    1000    1045    1045    1165    1980    2250    2350    2450    2750    3050
    3350    4750    4825
   473.6   473.5   473.5  471.94  459.96  455.99  454.52  452.05  444.64   439.5
  438.65   445.3  445.66
   469.6   469.5   466.5  464.94  452.96  448.99  447.52  445.05  437.64   432.5
  431.65   438.3  438.66
    1000    1045    1045    1165    1980    2250    2350    2450    2750    3050
    3350    4750    4825
   473.6   473.5   473.5  471.94  459.96  455.99  454.52  452.05  444.64   439.5
  438.65   445.3  445.66
   469.6   469.5   466.5  464.94  452.96  448.99  447.52  445.05  437.64   432.5
  431.65   438.3  438.66
Pier Skew, UpSta & Num, DnSta & Num=  ,1045, 2 ,1045, 2 , 0 , 0 , 0 ,,
       5       5
     400     470
       5       5
     400     470
Pier Skew, UpSta & Num, DnSta & Num=  ,1125, 2 ,1125, 2 , 0 , 0 , 0 ,,
       5       5
     400     470
       5       5
     400     470
Pier Skew, UpSta & Num, DnSta & Num=  ,1205, 2 ,1205, 2 , 0 , 0 , 0 ,,
       5       5
     400     465
       5       5
     400     465
Pier Skew, UpSta & Num, DnSta & Num=  ,1285, 2 ,1285, 2 , 0 , 0 , 0 ,,
       5       5
     400     465
       5       5
     400     465
Pier Skew, UpSta & Num, DnSta & Num=  ,1365, 2 ,1365, 2 , 0 , 0 , 0 ,,
       5       5
     400     465
       5       5
     400     465
Pier Skew, UpSta & Num, DnSta & Num=  ,1455, 2 ,1455, 2 , 0 , 0 , 0 ,,
       5       5
     400     465
       5       5
     400     465
Pier Skew, UpSta & Num, DnSta & Num=  ,1545, 2 ,1545, 2 , 0 , 0 , 0 ,,
       5       5
     400     463
       5       5
     400     463
Pier Skew, UpSta & Num, DnSta & Num=  ,1630, 2 ,1630, 2 , 0 , 0 , 0 ,,
       5       5
     400     460
       5       5
     400     460
Pier Skew, UpSta & Num, DnSta & Num=  ,1715, 2 ,1715, 2 , 0 , 0 , 0 ,,
       5       5
     400     460
       5       5
     400     460
Pier Skew, UpSta & Num, DnSta & Num=  ,1800, 2 ,1800, 2 , 0 , 0 , 0 ,,
       5       5
     400     460
       5       5
     400     460
Pier Skew, UpSta & Num, DnSta & Num=  ,1890, 2 ,1890, 2 , 0 , 0 , 0 ,,
       5       5
     400     458
       5       5
     400     458
Pier Skew, UpSta & Num, DnSta & Num=  ,1980, 2 ,1980, 2 , 0 , 0 , 0 ,,
       5       5
     400     455
       5       5
     400     455
Pier Skew, UpSta & Num, DnSta & Num=  ,2070, 2 ,2070, 2 , 0 , 0 , 0 ,,
       5       5
     400     455
       5       5
     400     455
Pier Skew, UpSta & Num, DnSta & Num=  ,2160, 2 ,2160, 2 , 0 , 0 , 0 ,,
       5       5
     400   454.3
       5       5
     400   454.3
Pier Skew, UpSta & Num, DnSta & Num=  ,2250, 2 ,2250, 2 , 0 , 0 , 0 ,,
       5       5
     400   454.3
       5       5
     400   454.3
Pier Skew, UpSta & Num, DnSta & Num=  ,2340, 2 ,2340, 2 , 0 , 0 , 0 ,,
       5       5
     400   454.3
       5       5
     400   454.3
Pier Skew, UpSta & Num, DnSta & Num=  ,2430, 2 ,2430, 2 , 0 , 0 , 0 ,,
       5       5
     400   454.3
       5       5
     400   454.3
Pier Skew, UpSta & Num, DnSta & Num=  ,2520, 2 ,2520, 2 , 0 , 0 , 0 ,,
       5       5
     400   454.3
       5       5
     400   454.3
Pier Skew, UpSta & Num, DnSta & Num=  ,2610, 2 ,2610, 2 , 0 , 0 , 0 ,,
       5       5
     400   454.3
       5       5
     400   454.3
Pier Skew, UpSta & Num, DnSta & Num=  ,2700, 2 ,2700, 2 , 0 , 0 , 0 ,,
       5       5
     400   454.3
       5       5
     400   454.3
Pier Skew, UpSta & Num, DnSta & Num=  ,2790, 2 ,2790, 2 , 0 , 0 , 0 ,,
       5       5
     400   454.3
       5       5
     400   454.3
Pier Skew, UpSta & Num, DnSta & Num=  ,2880, 2 ,2880, 2 , 0 , 0 , 0 ,,
       5       5
     400   454.3
       5       5
     400   454.3
Pier Skew, UpSta & Num, DnSta & Num=  ,2970, 2 ,2970, 2 , 0 , 0 , 0 ,,
       5       5
     400   454.3
       5       5
     400   454.3
Pier Skew, UpSta & Num, DnSta & Num=  ,3060, 2 ,3060, 2 , 0 , 0 , 0 ,,
       5       5
     400   454.3
       5       5
     400   454.3
Pier Skew, UpSta & Num, DnSta & Num=  ,3150, 2 ,3150, 2 , 0 , 0 , 0 ,,
       5       5
     400   454.3
       5       5
     400   454.3
Pier Skew, UpSta & Num, DnSta & Num=  ,3240, 2 ,3240, 2 , 0 , 0 , 0 ,,
       5       5
     400   454.3
       5       5
     400   454.3
Pier Skew, UpSta & Num, DnSta & Num=  ,3330, 2 ,3330, 2 , 0 , 0 , 0 ,,
       5       5
     400   454.3
       5       5
     400   454.3
Pier Skew, UpSta & Num, DnSta & Num=  ,3420, 2 ,3420, 2 , 0 , 0 , 0 ,,
       5       5
     400   454.3
       5       5
     400   454.3
Pier Skew, UpSta & Num, DnSta & Num=  ,3510, 2 ,3510, 2 , 0 , 0 , 0 ,,
       5       5
     400   454.3
       5       5
     400   454.3
Pier Skew, UpSta & Num, DnSta & Num=  ,3600, 2 ,3600, 2 , 0 , 0 , 0 ,,
       5       5
     400   454.3
       5       5
     400   454.3
Pier Skew, UpSta & Num, DnSta & Num=  ,3690, 2 ,3690, 2 , 0 , 0 , 0 ,,
       5       5
     400   454.3
       5       5
     400   454.3
Pier Skew, UpSta & Num, DnSta & Num=  ,3780, 2 ,3780, 2 , 0 , 0 , 0 ,,
       5       5
     400   454.3
       5       5
     400   454.3
Pier Skew, UpSta & Num, DnSta & Num=  ,3870, 2 ,3870, 2 , 0 , 0 , 0 ,,
       5       5
     400   454.3
       5       5
     400   454.3
Pier Skew, UpSta & Num, DnSta & Num=  ,3960, 2 ,3960, 2 , 0 , 0 , 0 ,,
       5       5
     400   454.3
       5       5
     400   454.3
Pier Skew, UpSta & Num, DnSta & Num=  ,4050, 2 ,4050, 2 , 0 , 0 , 0 ,,
       5       5
     400   454.3
       5       5
     400   454.3
Pier Skew, UpSta & Num, DnSta & Num=  ,4150, 2 ,4150, 2 , 0 , 0 , 0 ,,
       5       5
     400   454.3
       5       5
     400   454.3
Pier Skew, UpSta & Num, DnSta & Num=  ,4285, 2 ,4285, 2 , 0 , 0 , 0 ,,
       5       5
     400   454.3
       5       5
     400   454.3
Pier Skew, UpSta & Num, DnSta & Num=  ,4385, 2 ,4385, 2 , 0 , 0 , 0 ,,
       5       5
     400   454.3
       5       5
     400   454.3
Pier Skew, UpSta & Num, DnSta & Num=  ,4475, 2 ,4475, 2 , 0 , 0 , 0 ,,
       5       5
     400   454.3
       5       5
     400   454.3
Pier Skew, UpSta & Num, DnSta & Num=  ,4565, 2 ,4565, 2 , 0 , 0 , 0 ,,
       5       5
     400   454.3
       5       5
     400   454.3
Pier Skew, UpSta & Num, DnSta & Num=  ,4655, 2 ,4655, 2 , 0 , 0 , 0 ,,
       6       6
     400   454.3
       6       6
     400   454.3
BR Coef=-1 , 0 , 0 ,1.05, 0 ,,,0.8,-1,0.5,0,
WSPro=,,,, 1 ,,,, 0 ,,,, 0 ,,,,-1 ,-1 ,-1 , 0 , 0 , 0 , 0 , 0
BC Design=,, 0 ,, 0 ,,,,,,
BC Use User HTab Curves=0
BC User HTab FreeFlow(D)= 0

Type RM Length L Ch R = 1 ,22635   ,71,71,71
BEGIN DESCRIPTION:
This cross section corresponds to cross section 22610 of the non-georeferenced CDC model which was the source of this model.
---------------------------------------------------------------------
CDC Irving 110308-01 DART Northwest Corridor Light Rail Transit Line
Cross-sections 22610 - 22649
---------------------------------------------------------------------
Interpolated cross-section
END DESCRIPTION:
XS GIS Cut Line= 5
2466120.054379636999733.089409342465790.594566196999356.98273388
  2464143.2954996997476.449356562463492.124229166996733.08142072
2461421.602779696994877.96209946
#Sta/Elev= 30
   -2000  436.46    1000  436.46 1115.94  422.08 1480.46  420.09 2085.21  423.96
 2128.04  432.56 2228.31   433.3 2312.91  432.46 2327.25  430.67 2327.25  427.26
 2341.27  425.21 2369.31   415.9 2507.31  412.62 2543.27  410.22 2726.95   410.3
 2864.95  414.94 3996.18  413.88 4146.82  411.69 4177.38  404.88 4211.58  390.49
 4242.44  395.43 4257.43  404.61 4272.51  409.01 4279.36  412.81 4386.06  413.74
 4468.68  411.91 4699.39   409.8 4744.46  422.56 4768.27  431.37 4768.27  431.82
#Mann= 5 ,-1,0
   -2000     .13       0 4146.82     .05       0 4279.36     .13       0
 4468.68    .049       0 4768.27    .049       0
#Block Obstruct= 2 , 0
       0    2900   414.3               0
Bank Sta=4146.82,4279.36
XS Rating Curve= 0 ,0
Exp/Cntr=0.3,0.1

Type RM Length L Ch R = 1 ,22564   ,89,89,89
BEGIN DESCRIPTION:
This cross section corresponds to cross section 22546 of the non-georeferenced CDC model which was the source of this model.
Right Overbank updated with 2007 levee topo.
END DESCRIPTION:
XS GIS Cut Line= 6
2466213.721526016999662.195220132465878.501442316999291.21342073
2464202.401023836997436.304423722463389.522072176996536.70648538
2461876.051345836995191.109439052461446.075827846994818.12560497
#Sta/Elev= 30
   -2000   432.3    1000   432.3    2420     436    2420     427    2435     427
    2465   414.6  2926.5     415    4158     412    4167     410    4200   407.5
    4222   402.5    4247   390.8    4262   393.5 4269.29 409.451 4279.95  411.68
  4392.5   414.2    4483     412 4643.02     412 4653.38     410 4698.89  411.28
  4748.5     420 4754.97     420 4756.57  420.43 4756.78     422 4771.52  424.33
  4771.8     426 4779.01  426.21 4779.25     428 4786.48     430 4806.81   431.8
#Mann= 3 ,0,0
   -2000     .08       0    4158     .05       0 4279.95     .08       0
Bank Sta=4158,4279.95
XS Rating Curve= 0 ,0
Exp/Cntr=0.5,0.3