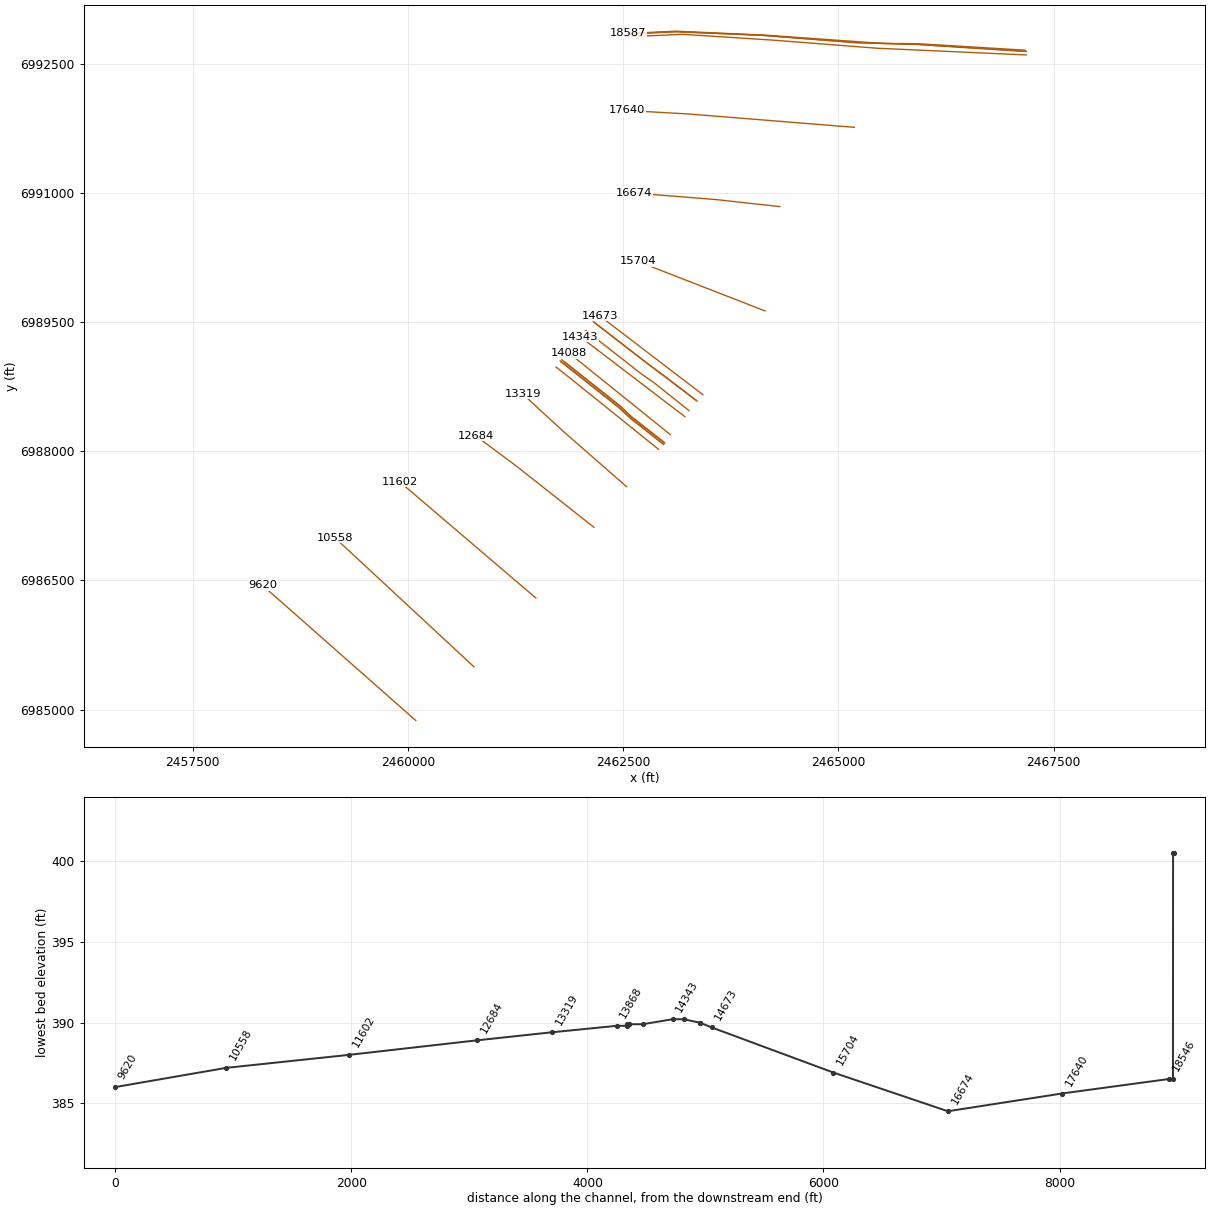
HEC-RAS study CDC_Consolidated_Model.prj: Upper Trinity CDC Consolidated Model

--- CDC_Consolidated_Model.g02 (geometry) --- (continued)

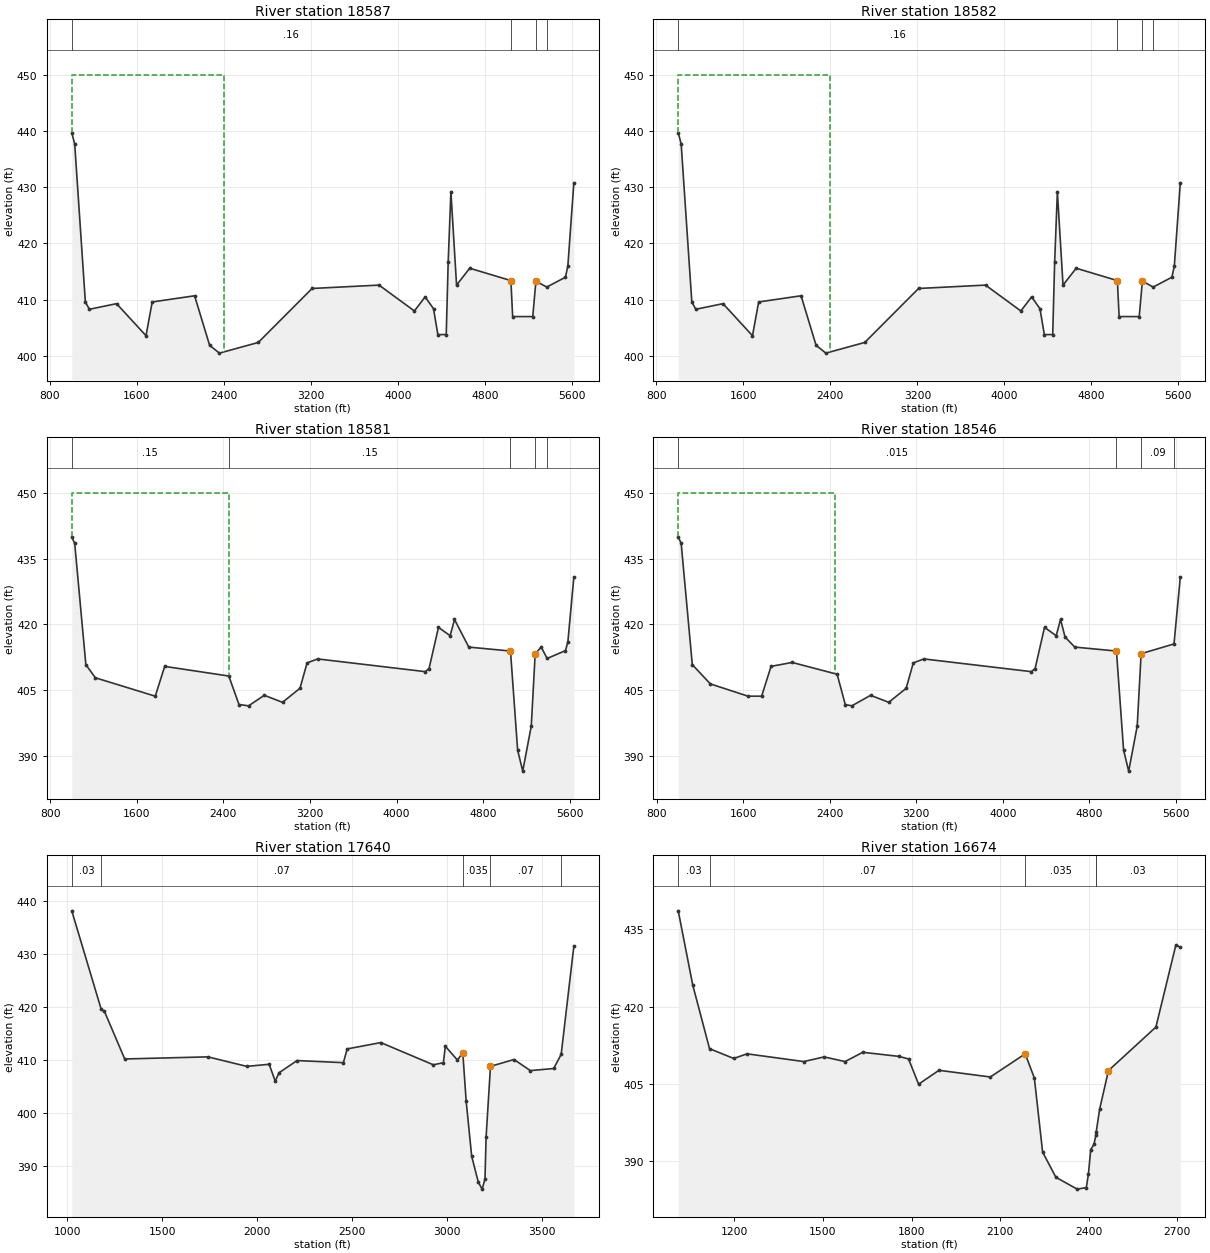
Type RM Length L Ch R = 1 ,18587   ,5,5,5
BEGIN DESCRIPTION:
This cross section corresponds to cross section 18576 of the non-georeferenced CDC model which was the source of this model.
END DESCRIPTION:
XS GIS Cut Line= 6
2467168.62967142 6992658.07218232465924.089509586992733.17308196
2465511.603129836992736.290201722464129.732205936992833.94879904
 2463115.28016666992878.409996212462557.091322336992852.88708138
#Sta/Elev= 30
    1000   439.7    1027   437.7    1125   409.6    1162   408.3    1412   409.3
    1683   403.6    1740   409.6    2130   410.7    2268   401.9    2358   400.5
    2716   402.4    3211     412    3827   412.6    4152     408    4251   410.5
    4328   408.4    4368   403.8    4445   403.8    4463   416.7    4488   429.2
    4540   412.6    4661   415.6    5040   413.4    5056     407    5241     407
    5270   413.3 5369.71  412.25 5541.63     414 5563.96     416 5619.03   430.8
#Mann= 4 ,-1,0
    1000     .16       0    5040     .02       0    5270     .07       0
 5369.71     .03       0
#XS Ineff= 2 , 0
       0    2400     450               0
Permanent Ineff=
       F       F
Bank Sta=5040,5270
XS Rating Curve= 0 ,0
Exp/Cntr=0.3,0.1

Type RM Length L Ch R = 1 ,18582   ,1,1,1
BEGIN DESCRIPTION:
This cross section corresponds to cross section 18571 of the non-georeferenced CDC model which was the source of this model.
Frasier Dam
---------------------------------------------------------------------
CDC DAL021201-1 Frasier Dam Modifications
Cross-section 18571 - 18576
---------------------------------------------------------------------
END DESCRIPTION:
Node Name=Frasier Dam
XS GIS Cut Line= 6
       2467169.3     6992644.849     2465917.426     6992725.511
     2465206.977     6992746.233     2464113.071     6992831.255
     2463114.446     6992873.398     2462558.268     6992848.167
#Sta/Elev= 30
    1000   439.7    1027   437.7    1125   409.6    1162   408.3    1412   409.3
    1683   403.6    1740   409.6    2130   410.7    2268   401.9    2358   400.5
    2716   402.4    3211     412    3827   412.6    4152     408    4251   410.5
    4328   408.4    4368   403.8    4445   403.8    4463   416.7    4488   429.2
    4540   412.6    4661   415.6    5040   413.4    5056     407    5241     407
    5270   413.3 5369.71  412.25 5541.63     414 5563.96     416 5619.03   430.8
#Mann= 4 ,-1,0
    1000     .16       0    5040     .02       0    5270     .07       0
 5369.71     .03       0
#XS Ineff= 2 , 0
       0    2400     450               0
Permanent Ineff=
       F       F
Bank Sta=5040,5270
XS Rating Curve= 0 ,0
Exp/Cntr=0.3,0.1

Type RM Length L Ch R = 1 ,18581   ,35,35,35
BEGIN DESCRIPTION:
This cross section corresponds to cross section 18570 of the non-georeferenced CDC model which was the source of this model.
END DESCRIPTION:
XS GIS Cut Line= 6
2467183.315665666992643.066634882465917.463210496992724.50774497
2465207.013844016992745.230144472464113.108223416992830.25162797
2463114.483580266992872.394916392462555.309501776992847.00914039
#Sta/Elev= 30
    1000   439.9    1027   438.5    1130   410.8    1218   407.8    1771   403.6
    1858   410.4    2450   408.2    2544   401.7    2632   401.4    2778   403.8
    2946   402.2    3107   405.4    3173   411.2    3271   412.1    4264   409.2
    4299   409.9    4386   419.3    4494   417.4    4534   421.1    4666   414.8
    5051   413.9    5117   391.3    5164   386.5    5243   396.8    5279   413.3
    5335   414.8 5389.22   412.2 5558.63     414 5580.96     416 5636.03   430.8
#Mann= 5 ,-1,0
    1000     .15       0    2450     .15       0    5051    .035       0
    5279     .09       0 5389.22     .03       0
#XS Ineff= 2 , 0
       0    2450     450               0
Permanent Ineff=
       F       F
Bank Sta=5051,5279
XS Rating Curve= 0 ,0
Exp/Cntr=0.3,0.1

Type RM Length L Ch R = 1 ,18546   ,960,906,906
BEGIN DESCRIPTION:
This cross section corresponds to cross section 18521 of the non-georeferenced CDC model which was the source of this model.
Right Overbank updated with 2007 levee topo.
END DESCRIPTION:
XS GIS Cut Line= 6
2467182.491848416992602.669405972465445.249259926992680.86642805
2464236.476415016992774.954494462463214.511923496992840.84182988
2463187.191112016992842.053113552462549.376114676992813.51970606
#Sta/Elev= 30
    1000   439.9    1027   438.5    1130   410.8    1297   406.4    1645   403.6
    1771   403.6    1858   410.4    2053   411.3    2469   408.6    2544   401.7
    2605   401.4    2778   403.8    2946   402.2    3107   405.4    3173   411.2
    3271   412.1    4264   409.2    4299   409.9    4386   419.3    4494   417.4
    4534   421.1    4576   417.1    4666   414.8    5051   413.9    5117   391.3
    5164   386.5    5243   396.8    5279   413.3 5582.95  415.52 5641.32  430.78
#Mann= 4 ,-1,0
    1000    .015       0    5051    .035       0    5279     .09       0
 5582.95     .03       0
#XS Ineff= 2 , 0
       0    2450     450               0
Permanent Ineff=
       F       F
Bank Sta=5051,5279
XS Rating Curve= 0 ,0
Exp/Cntr=0.3,0.1

Type RM Length L Ch R = 1 ,17640   ,1000,966,950
BEGIN DESCRIPTION:
This cross section corresponds to cross section 17615 of the non-georeferenced CDC model which was the source of this model.
Right Overbank updated with 2007 levee topo.
END DESCRIPTION:
XS GIS Cut Line= 3
2465185.311131516991762.060850962463278.727346246991915.61730239
 2462547.4738875 6991957.5086228
#Sta/Elev= 30
    1023   438.2    1178   419.6    1195   419.2    1302   410.2    1740   410.6
    1945   408.8    2063   409.2    2095     406    2115   407.6    2210   409.9
    2454   409.5    2474   412.1    2651   413.3    2928   409.1    2981   409.5
    2991   412.6    3055     410    3083   411.4    3101   402.2    3130   391.8
    3165   386.9    3185   385.6    3200   387.5    3206   395.5    3229   408.8
    3353   410.1    3439     408    3562   408.4  3601.4  411.06 3668.21  431.52
#Mann= 5 ,-1,0
    1023     .03       0    1178     .07       0    3083    .035       0
    3229     .07       0  3601.4     .03       0
Bank Sta=3083,3229
XS Rating Curve= 0 ,0
Exp/Cntr=0.3,0.1

Type RM Length L Ch R = 1 ,16674   ,1049,970,849
BEGIN DESCRIPTION:
This cross section corresponds to cross section 16649 of the non-georeferenced CDC model which was the source of this model.
Proposed grading for levee overbank.
Right Overbank updated with 2007 levee topo.
END DESCRIPTION:
XS GIS Cut Line= 3
2464321.024146176990841.184739962463571.845526436990923.54153064
2462628.231600026990998.89964764
#Sta/Elev= 30
    1010   438.6    1059   424.2    1116   411.8    1198   409.9    1243   410.8
    1435   409.3    1504   410.2    1575   409.3    1635   411.1    1758   410.3
    1790   409.8    1824   404.9    1893   407.6    2067   406.3    2185   410.8
    2216   406.1    2244   391.7    2289   386.8    2361   384.5    2392   384.8
    2399   387.4    2407   392.2    2418   393.2  2424.2  394.96 2425.34  395.54
 2436.94     400    2467  407.55 2627.64     416 2695.44     432 2710.31  431.49
#Mann= 5 ,-1,0
    1010     .03       0    1116     .07       0    2185    .035       0
  2424.2     .07       0 2425.34     .03       0
Bank Sta=2185,2467
XS Rating Curve= 0 ,0
Exp/Cntr=0.3,0.1

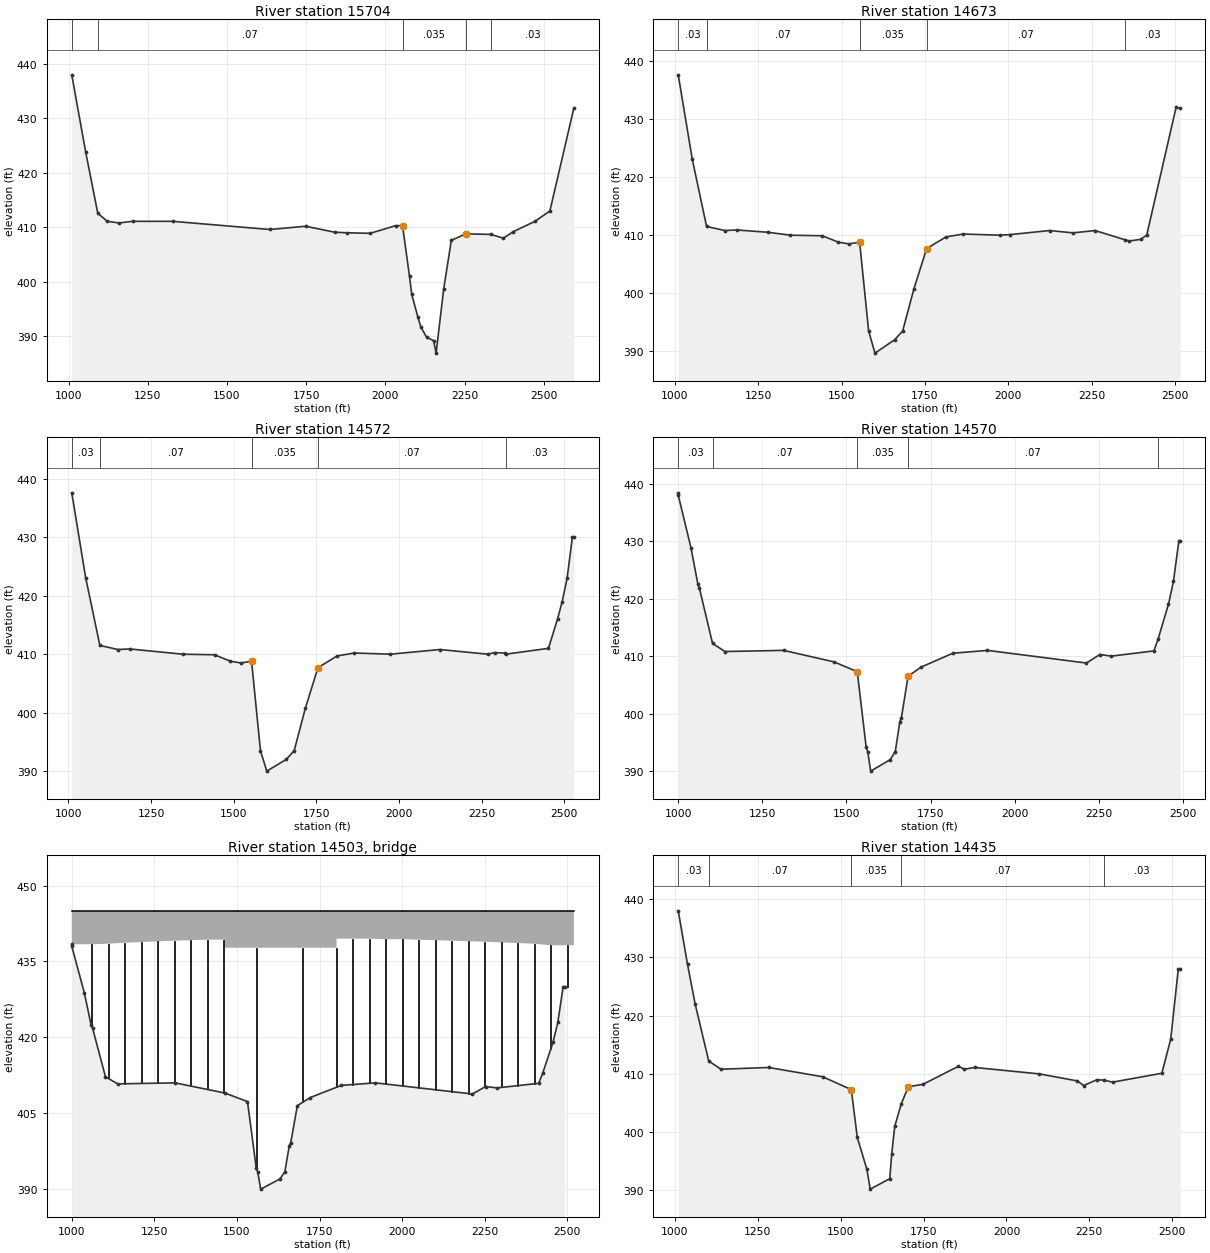
Type RM Length L Ch R = 1 ,15704   ,1061,1031,851
BEGIN DESCRIPTION:
This cross section corresponds to cross section 15678 of the non-georeferenced CDC model which was the source of this model.
Proposed grading for levee overbank.
Right Overbank updated with 2007 levee topo.
END DESCRIPTION:
XS GIS Cut Line= 2
2464147.013667436989630.166492722462670.037946856990204.54624946
#Sta/Elev= 30
    1010     438    1054   423.8    1092   412.6    1122   411.1    1159   410.8
    1202   411.1    1329   411.1    1635   409.6    1748   410.2    1840   409.1
    1878     409    1952   408.9    2032   410.3    2054   410.3    2076     401
    2083   397.7    2102   393.6    2112   391.7    2130   389.8    2152   389.2
    2160   386.9    2184   398.7    2208   407.6    2253   408.8    2333   408.7
 2372.06     408 2404.04  409.22 2471.15  411.07 2519.11     413 2594.73  431.89
#Mann= 5 ,-1,0
    1010     .03       0    1092     .07       0    2054    .035       0
    2253     .07       0    2333     .03       0
Bank Sta=2054,2253
XS Rating Curve= 0 ,0
Exp/Cntr=0.3,0.1

Type RM Length L Ch R = 1 ,14673   ,101,101,101
BEGIN DESCRIPTION:
This cross section corresponds to cross section 14648 of the non-georeferenced CDC model which was the source of this model.
Proposed grading for levee overbank.
Right Overbank updated with 2007 levee topo.
END DESCRIPTION:
XS GIS Cut Line= 2
 2463425.48033366988657.478477462462228.986007426989571.50453655
#Sta/Elev= 30
    1010   437.6    1052   423.1    1095   411.5    1150   410.8    1185   410.9
    1279   410.5    1346     410    1442   409.9    1490   408.8    1522   408.5
    1554   408.8    1581   393.5    1600   389.7    1659     392    1683   393.5
    1717   400.8    1755   407.7    1813   409.7    1865   410.2    1974     410
    2005   410.1    2124   410.8    2194   410.4 2259.93   410.8  2349.7  409.21
 2362.59     409 2396.68  409.28 2414.94     410 2502.98     432 2515.67  431.83
#Mann= 5 ,-1,0
    1010     .03       0    1095     .07       0    1554    .035       0
    1755     .07       0  2349.7     .03       0
Bank Sta=1554,1755
XS Rating Curve= 0 ,0
Exp/Cntr=0.3,0.1

Type RM Length L Ch R = 1 ,14572   ,2,2,2
BEGIN DESCRIPTION:
This cross section corresponds to cross section 14545 of the non-georeferenced CDC model which was the source of this model.
Proposed grading for levee overbank.
Right Overbank updated with 2007 levee topo.
END DESCRIPTION:
XS GIS Cut Line= 4
2463360.138600776988582.560976392462954.787377336988893.08528972
2462792.263096096989011.351457392462153.760764186989505.91542888
#Sta/Elev= 30
    1010   437.6    1052   423.1    1095   411.5    1150   410.8    1185   410.9
    1346     410    1442   409.9    1490   408.8    1522   408.5    1554   408.8
    1581   393.5    1600     390    1659     392    1683   393.5    1717   400.8
    1755   407.7    1813   409.7    1865   410.2    1974     410    2124   410.8
    2269     410 2290.21  410.28 2321.22  410.18 2324.22  410.01 2452.44     411
 2479.83     416 2494.05     419 2508.87     423 2524.81     430 2529.26     430
#Mann= 5 ,-1,0
    1010     .03       0    1095     .07       0    1554    .035       0
    1755     .07       0 2324.22     .03       0
Bank Sta=1554,1755
XS Rating Curve= 0 ,0
Exp/Cntr=0.5,0.3

Type RM Length L Ch R = 1 ,14570   ,135,135,135
BEGIN DESCRIPTION:
This cross section corresponds to cross section 14544 of the non-georeferenced CDC model which was the source of this model.
Proposed grading for levee overbank.
Right Overbank updated with 2007 levee topo.
END DESCRIPTION:
XS GIS Cut Line= 3
2463350.542163256988588.547184882462811.876245836988996.14610721
2462165.39886427 6989494.9682723
#Sta/Elev= 30
    1000   438.4    1000     438    1038   428.8  1058.5 422.464    1063   421.8
    1102   412.2    1139   410.8    1313     411    1463     409    1532   407.3
  1558.5  394.15    1563   393.4    1572     390    1630     392    1645   393.4
  1658.5  398.57    1663   399.2    1683   406.5    1722   408.1    1816   410.5
    1919     411    2213   408.8    2253  410.28 2287.25     410 2413.57  410.91
 2426.17     413 2456.84     419 2471.66     423  2487.6     430 2492.05     430
#Mann= 5 ,-1,0
    1000     .03       0    1102     .07       0    1532    .035       0
    1683     .07       0 2426.17     .03       0
Bank Sta=1532,1683
XS Rating Curve= 0 ,0
Exp/Cntr=0.5,0.3

Type RM Length L Ch R = 3 ,14503   ,,,
BEGIN DESCRIPTION:
SH 183/John W. Carpenter Freeway
Data from bridge planns 1977.
END DESCRIPTION:
Node Name=SH 183
Bridge Culvert--1,0,-1,-1, 0
Deck Dist Width WeirC Skew NumUp NumDn MinLoCord MaxHiCord MaxSubmerge Is_Ogee
1,132,2.6,0, 52, 52, , , 0.95, 0, ,,,
    1000  1058.5  1061.5  1108.5  1111.5  1158.5  1161.5    1207    1213  1308.5
  1311.5  1358.5  1361.5  1408.5  1411.5  1458.5  1461.5  1461.5  1558.5  1561.5
  1698.5  1701.5  1798.5  1801.5  1801.5  1848.5  1851.5  1898.5  1901.5  1948.5
  1951.5  1998.5  2001.5  2048.5  2051.5  2098.5  2101.5  2148.5  2151.5  2198.5
  2201.5  2248.5  2251.5    2297    2303  2398.5  2401.5  2448.5  2451.5  2498.5
  2501.5    2520
     445     445     445     445     445     445     445     445     445     445
     445     445     445     445     445     445     445     445     445     445
     445     445     445     445     445     445     445     445     445     445
     445     445     445     445     445     445     445     445     445     445
     445     445     445     445     445     445     445     445     445     445
     445     445
   438.4   438.4 438.403 438.497 438.506 438.694 438.703 438.825 438.841 439.097
 439.103 439.197 439.203 439.297   439.3   439.3   439.3   437.7   437.7   437.7
   437.7   437.7   437.7   437.7   439.5   439.5   439.5   439.5 439.497 439.403
   439.4   439.4 439.397 439.303 439.297 439.203 439.197 439.103 439.097 439.003
 438.997 438.903 438.897 438.775 438.759 438.503 438.491 438.209   438.2   438.2
   438.2   438.2
    1000  1058.5  1061.5  1108.5  1111.5  1158.5  1161.5    1207    1213  1308.5
  1311.5  1358.5  1361.5  1408.5  1411.5  1458.5  1461.5  1461.5  1558.5  1561.5
  1698.5  1701.5  1798.5  1801.5  1801.5  1848.5  1851.5  1898.5  1901.5  1948.5
  1951.5  1998.5  2001.5  2048.5  2051.5  2098.5  2101.5  2148.5  2151.5  2198.5
  2201.5  2248.5  2251.5    2297    2303  2398.5  2401.5  2448.5  2451.5  2498.5
  2501.5    2520
     445     445     445     445     445     445     445     445     445     445
     445     445     445     445     445     445     445     445     445     445
     445     445     445     445     445     445     445     445     445     445
     445     445     445     445     445     445     445     445     445     445
     445     445     445     445     445     445     445     445     445     445
     445     445
   438.4   438.4 438.403 438.497 438.506 438.694 438.703 438.825 438.841 439.097
 439.103 439.197 439.203 439.297   439.3   439.3   439.3   437.7   437.7   437.7
   437.7   437.7   437.7   437.7   439.5   439.5   439.5   439.5 439.497 439.403
   439.4   439.4 439.397 439.303 439.297 439.203 439.197 439.103 439.097 439.003
 438.997 438.903 438.897 438.775 438.759 438.503 438.491 438.209   438.2   438.2
   438.2   438.2
Pier Skew, UpSta & Num, DnSta & Num=  ,1060, 2 ,1060, 2 , 0 , 0 , 0 ,,
       3       3
     390     442
       3       3
     390     442
Pier Skew, UpSta & Num, DnSta & Num=  ,1110, 2 ,1110, 2 , 0 , 0 , 0 ,,
       3       3
     390     442
       3       3
     390     442
Pier Skew, UpSta & Num, DnSta & Num=  ,1160, 2 ,1160, 2 , 0 , 0 , 0 ,,
       3       3
     390     442
       3       3
     390     442
Pier Skew, UpSta & Num, DnSta & Num=  ,1210, 2 ,1210, 2 , 0 , 0 , 0 ,,
       3       3
     390     442
       3       3
     390     442
Pier Skew, UpSta & Num, DnSta & Num=  ,1260, 2 ,1260, 2 , 0 , 0 , 0 ,,
       3       3
     390     442
       3       3
     390     442
Pier Skew, UpSta & Num, DnSta & Num=  ,1310, 2 ,1310, 2 , 0 , 0 , 0 ,,
       3       3
     390     442
       3       3
     390     442
Pier Skew, UpSta & Num, DnSta & Num=  ,1360, 2 ,1360, 2 , 0 , 0 , 0 ,,
       3       3
     390     442
       3       3
     390     442
Pier Skew, UpSta & Num, DnSta & Num=  ,1410, 2 ,1410, 2 , 0 , 0 , 0 ,,
       3       3
     390     442
       3       3
     390     442
Pier Skew, UpSta & Num, DnSta & Num=  ,1460, 2 ,1460, 2 , 0 , 0 , 0 ,,
       3       3
     390     442
       3       3
     390     442
Pier Skew, UpSta & Num, DnSta & Num=  ,1560, 2 ,1560, 2 , 0 , 0 , 0 ,,
       3       3
     390     442
       3       3
     390     442
Pier Skew, UpSta & Num, DnSta & Num=  ,1700, 2 ,1700, 2 , 0 , 0 , 0 ,,
       3       3
     390     442
       3       3
     390     442
Pier Skew, UpSta & Num, DnSta & Num=  ,1800, 2 ,1800, 2 , 0 , 0 , 0 ,,
       3       3
     390     442
       3       3
     390     442
Pier Skew, UpSta & Num, DnSta & Num=  ,1850, 2 ,1850, 2 , 0 , 0 , 0 ,,
       3       3
     390     442
       3       3
     390     442
Pier Skew, UpSta & Num, DnSta & Num=  ,1900, 2 ,1900, 2 , 0 , 0 , 0 ,,
       3       3
     390     442
       3       3
     390     442
Pier Skew, UpSta & Num, DnSta & Num=  ,1950, 2 ,1950, 2 , 0 , 0 , 0 ,,
       3       3
     390     442
       3       3
     390     442
Pier Skew, UpSta & Num, DnSta & Num=  ,2000, 2 ,2000, 2 , 0 , 0 , 0 ,,
       3       3
     390     442
       3       3
     390     442
Pier Skew, UpSta & Num, DnSta & Num=  ,2050, 2 ,2050, 2 , 0 , 0 , 0 ,,
       3       3
     390     442
       3       3
     390     442
Pier Skew, UpSta & Num, DnSta & Num=  ,2100, 2 ,2100, 2 , 0 , 0 , 0 ,,
       3       3
     390     442
       3       3
     390     442
Pier Skew, UpSta & Num, DnSta & Num=  ,2150, 2 ,2150, 2 , 0 , 0 , 0 ,,
       3       3
     390     442
       3       3
     390     442
Pier Skew, UpSta & Num, DnSta & Num=  ,2200, 2 ,2200, 2 , 0 , 0 , 0 ,,
       3       3
     390     442
       3       3
     390     442
Pier Skew, UpSta & Num, DnSta & Num=  ,2250, 2 ,2250, 2 , 0 , 0 , 0 ,,
       3       3
     390     442
       3       3
     390     442
Pier Skew, UpSta & Num, DnSta & Num=  ,2300, 2 ,2300, 2 , 0 , 0 , 0 ,,
       3       3
     390     442
       3       3
     390     442
Pier Skew, UpSta & Num, DnSta & Num=  ,2350, 2 ,2350, 2 , 0 , 0 , 0 ,,
       3       3
     390     442
       3       3
     390     442
Pier Skew, UpSta & Num, DnSta & Num=  ,2400, 2 ,2400, 2 , 0 , 0 , 0 ,,
       3       3
     390     442
       3       3
     390     442
Pier Skew, UpSta & Num, DnSta & Num=  ,2450, 2 ,2450, 2 , 0 , 0 , 0 ,,
       3       3
     390     442
       3       3
     390     442
Pier Skew, UpSta & Num, DnSta & Num=  ,2500, 2 ,2500, 2 , 0 , 0 , 0 ,,
       3       3
     390     442
       3       3
     390     442
BR Coef= 1 , 0 , 0 ,1.05, 0 ,,,0.8,-1,0.5,1,
WSPro=,,,, 1 ,,,, 0 ,,,, 0 ,,,,-1 ,-1 ,-1 , 0 , 0 , 0 , 0 , 0
BC Design=,, 0 ,, 0 ,,,,,,
BC HTab HWMax=438.4
BC Use User HTab Curves=0
BC User HTab FreeFlow(D)= 0

Type RM Length L Ch R = 1 ,14435   ,92,92,92
BEGIN DESCRIPTION:
This cross section corresponds to cross section 14411 of the non-georeferenced CDC model which was the source of this model.
Proposed grading for levee overbank.
Right Overbank updated with 2007 levee topo.
END DESCRIPTION:
XS GIS Cut Line= 4
2463265.036428756988471.588757382462859.100560846988795.77282029
2462717.625450076988893.593162722462069.660538676989400.73420879
#Sta/Elev= 30
    1010     438    1038   428.8    1061     422    1102   412.2    1139   410.8
    1283   411.1    1446   409.5    1532   407.3    1550   399.1    1579   393.6
    1589  390.21    1648     392    1654   396.3    1663     401    1683   404.9
    1704   407.8    1748   408.2    1855   411.3    1873   410.8    1904   411.1
    2099     410    2213   408.8    2233     408 2272.88     409 2294.92  408.92
 2319.94  408.58 2468.66  410.11 2495.52     416 2518.23     428 2524.33     428
#Mann= 5 ,-1,0
    1010     .03       0    1102     .07       0    1532    .035       0
    1683     .07       0 2294.92     .03       0
Bank Sta=1532,1704
XS Rating Curve= 0 ,0
Exp/Cntr=0.3,0.1

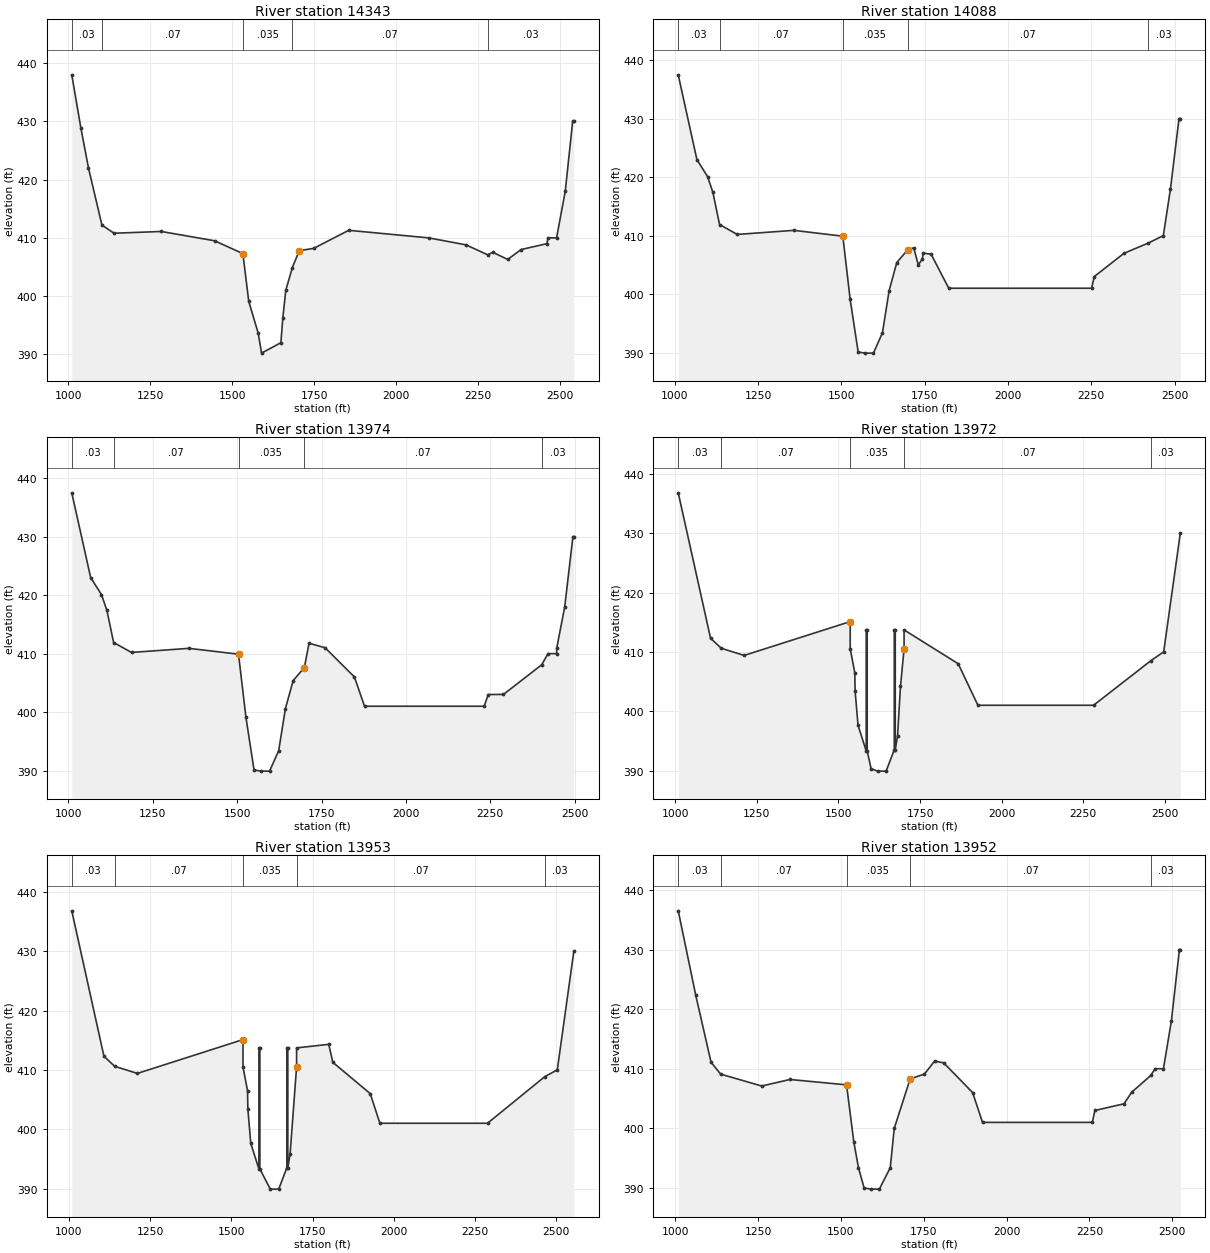
Type RM Length L Ch R = 1 ,14343   ,255,255,255
BEGIN DESCRIPTION:
This cross section corresponds to cross section 14317 of the non-georeferenced CDC model which was the source of this model.
Proposed grading for levee overbank.
Right Overbank updated with 2007 levee topo.
END DESCRIPTION:
XS GIS Cut Line= 2
2463216.977469746988401.485551132461999.679051346989331.40429497
#Sta/Elev= 30
    1010     438    1038   428.8    1061     422    1102   412.2    1139   410.8
    1283   411.1    1446   409.5    1532   407.3    1550   399.1    1579   393.6
    1589  390.21    1648     392    1654   396.3    1663     401    1683   404.9
    1704   407.8    1748   408.2    1855   411.3    2099     410    2213   408.8
    2279  407.09 2294.24  407.53 2340.04   406.3 2380.98     408 2459.29     409
  2463.3     410 2489.18     410 2515.63     418 2538.26     430 2541.85     430
#Mann= 5 ,-1,0
    1010     .03       0    1102     .07       0    1532    .035       0
    1683     .07       0    2279     .03       0
Bank Sta=1532,1704
XS Rating Curve= 0 ,0
Exp/Cntr=0.3,0.1

Type RM Length L Ch R = 1 ,14088   ,114,114,114
BEGIN DESCRIPTION:
This cross section corresponds to cross section 14062 of the non-georeferenced CDC model which was the source of this model.
Proposed grading for borrow pit and levee overbank.
END DESCRIPTION:
XS GIS Cut Line= 2
2463047.122166436988193.733998132461873.421757946989138.87712097
#Sta/Elev= 30
    1010   437.5    1066     423    1098   420.1    1114   417.4    1134   411.9
    1187   410.2    1357   410.9    1504   409.9    1526   399.1    1550   390.1
    1570   389.9    1596   389.9    1623   393.4    1643   400.6    1666   405.4
    1699   407.6    1717   407.9 1730.33     405 1743.02     406 1744.38     407
 1768.99  406.82  1821.9     401 2250.75     401 2258.75     403 2348.05  406.98
 2419.59  408.69    2466     410 2487.41     418 2513.01     430 2516.94     430
#Mann= 5 ,-1,0
    1010     .03       0    1134     .07       0    1504    .035       0
    1699     .07       0 2419.59     .03       0
Bank Sta=1504,1699
XS Rating Curve= 0 ,0
Exp/Cntr=0.3,0.1

Type RM Length L Ch R = 1 ,13974   ,2,2,2
BEGIN DESCRIPTION:
This cross section corresponds to cross section 13962 of the non-georeferenced CDC model which was the source of this model.
Proposed grading for borrow pit and levee overbank.
Right Overbank updated with 2007 levee topo and borrow pit topography
END DESCRIPTION:
XS GIS Cut Line= 4
2462969.44351602 6988108.49860432462600.548912586988397.58332796
2462459.242436686988530.428206642461812.814267586989042.76871738
#Sta/Elev= 30
    1010   437.5    1066     423    1098   420.1    1114   417.4    1134   411.9
    1187   410.2    1357   410.9    1504   409.9    1526   399.1    1550   390.1
    1570   389.9    1596   389.9    1623   393.4    1643   400.6    1666   405.4
    1699   407.6 1713.01  411.78 1760.53     411 1847.45     406 1877.26     401
  2231.7     401 2243.95     403 2289.02  403.02 2402.17  408.09  2421.1     410
 2446.52     410 2446.68  410.92 2470.46     418 2494.68     430 2497.46     430
#Mann= 5 ,-1,0
    1010     .03       0    1134     .07       0    1504    .035       0
    1699     .07       0 2402.17     .03       0
Bank Sta=1504,1699
XS Rating Curve= 0 ,0
Exp/Cntr=0.3,0.1

Type RM Length L Ch R = 1 ,13972   ,19,19,19
BEGIN DESCRIPTION:
This cross section corresponds to cross section 13961 of the non-georeferenced CDC model which was the source of this model.
Proposed grading for borrow pit and levee overbank.
Right Overbank updated with 2007 levee topo and borrow pit topo
END DESCRIPTION:
XS GIS Cut Line= 4
2462984.652475096988094.885770632462599.451801936988396.62565272
2462457.15484244 6988529.85209232461788.142729016989060.98652871
#Sta/Elev= 30
    1009   436.8    1108   412.3    1141   410.6    1211   409.4    1536   415.1
    1536   410.5    1550   406.5    1551   403.4    1560   397.6    1585   393.3
    1585   413.7    1588   413.7    1588   393.3    1600   390.3    1620   389.9
    1646   389.9    1671   393.5    1671   413.7    1674   413.7    1674   393.5
    1681   395.8    1690   404.2    1701   410.5    1701   413.7 1866.84     408
 1927.26     401  2281.7     401 2456.52  408.48 2496.52     410 2547.46     430
#Mann= 5 ,-1,0
    1009     .03       0    1141     .07       0    1536    .035       0
    1701     .07       0 2456.52     .03       0
Bank Sta=1536,1701
XS Rating Curve= 0 ,0
Exp/Cntr=0.3,0.1

Type RM Length L Ch R = 1 ,13953   ,1,1,1
BEGIN DESCRIPTION:
This cross section corresponds to cross section 13941 of the non-georeferenced CDC model which was the source of this model.
Proposed grading for borrow pit and levee overbank.
Right Overbank updated with 2007 levee topo and borrow pit topo
END DESCRIPTION:
XS GIS Cut Line= 4
2462972.107224586988079.919265142462585.26515052 6988384.1063208
 2462444.83268866988514.452516792461769.316979266989049.42093505
#Sta/Elev= 30
    1009   436.8    1108   412.3    1141   410.6    1211   409.4    1536   415.1
    1536   410.5    1550   406.5    1551   403.4    1560   397.6    1585   393.3
    1585   413.7    1588   413.7    1588   393.3    1620   389.9    1646   389.9
    1671   393.5    1671   413.7    1674   413.7    1674   393.5    1681   395.8
    1701   410.5    1701   413.7    1800   414.3 1812.52  411.27  1927.6     406
 1957.41     401  2288.7     401 2465.25  408.87 2503.47     410 2554.41     430
#Mann= 5 ,-1,0
    1009     .03       0    1141     .07       0    1536    .035       0
    1701     .07       0 2465.25     .03       0
Bank Sta=1536,1701
XS Rating Curve= 0 ,0
Exp/Cntr=0.3,0.1

Type RM Length L Ch R = 1 ,13952   ,84,84,84
BEGIN DESCRIPTION:
This cross section corresponds to cross section 13940 of the non-georeferenced CDC model which was the source of this model.
Proposed grading for borrow pit and levee overbank.
Right Overbank updated with 2007 levee topo and borrow pit topo.
END DESCRIPTION:
XS GIS Cut Line= 5
2462962.927124836988085.442219972462584.427881846988383.21065331
2462443.641089926988513.475812722461812.113809686989013.52960263
2461781.766757526989033.76118946
#Sta/Elev= 30
    1009   436.5    1062   422.3    1108   411.1    1137   409.1    1261   407.1
    1346   408.2    1517   407.3    1539   397.7    1553   393.4    1570     390
    1590   389.8    1616   389.8    1649   393.4    1661     400    1709   408.3
    1752   409.1 1782.51  411.27 1810.06     411 1897.59     406  1927.4     401
 2258.69     401 2266.69     403 2354.58  404.12 2377.12  406.03 2435.24  408.87
 2448.09     410 2473.46     410 2497.41     418 2521.67     430  2524.4     430
#Mann= 5 ,-1,0
    1009     .03       0    1137     .07       0    1517    .035       0
    1709     .07       0 2435.24     .03       0
Bank Sta=1517,1709
XS Rating Curve= 0 ,0
Exp/Cntr=0.3,0.1

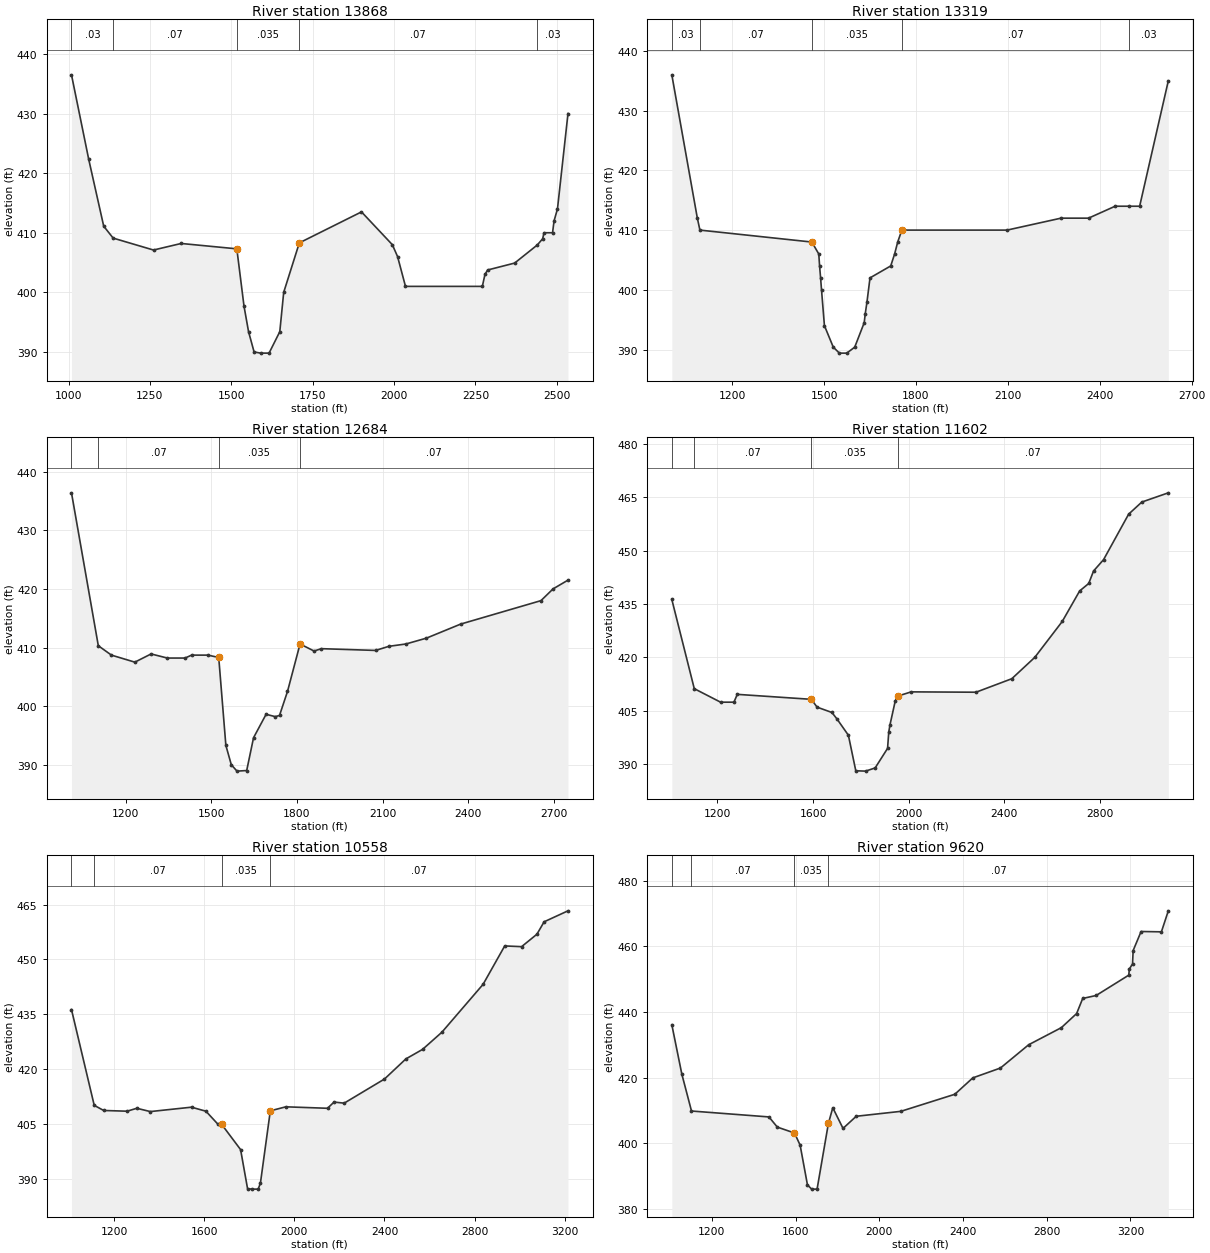
Type RM Length L Ch R = 1 ,13868   ,549,549,549
BEGIN DESCRIPTION:
This cross section corresponds to cross section 13842 of the non-georeferenced CDC model which was the source of this model.
Proposed grading for borrow pit and levee overbank.
Right Overbank updated with 2007 levee topo and borrow pit topography.
END DESCRIPTION:
XS GIS Cut Line= 3
2462910.786153026988022.569970382461838.411001186988885.75492381
2461721.155330186988977.40172213
#Sta/Elev= 30
    1009   436.5    1062   422.3    1108   411.1    1137   409.1    1261   407.1
    1346   408.2    1517   407.3    1539   397.7    1553   393.4    1570     390
    1590   389.8    1616   389.8    1649   393.4    1661     400    1709   408.3
    1900   413.5 1994.69     408 2010.86     406 2035.18     401 2271.31     401
 2279.31     403 2287.52  403.75 2370.51  404.91 2439.99  407.94 2456.71     409
 2460.72     410    2487     410 2491.72     412 2502.14     414 2534.44     430
#Mann= 5 ,-1,0
    1009     .03       0    1137     .07       0    1517    .035       0
    1709     .07       0 2439.99     .03       0
Bank Sta=1517,1709
XS Rating Curve= 0 ,0
Exp/Cntr=0.3,0.1

Type RM Length L Ch R = 1 ,13319   ,600,635,650
BEGIN DESCRIPTION:
This cross section corresponds to cross section 13293 of the non-georeferenced CDC model which was the source of this model.
Proposed grading  levee tie-in overbank
Right Overbank updated with 2007 levee topo
---------------------------------------------------------------------
CDC IRVING 082109-1 NORTHWEST LEVEE SEEPAGE CONTROL
CROSS-SECTION 13293 - 55400
DOWNSTREAM END
---------------------------------------------------------------------
END DESCRIPTION:
XS GIS Cut Line= 4
2462540.637615086987587.919592962461807.831009846988228.12894246
 2461524.97199556988488.02901322  2461332.8680496988668.20056888
#Sta/Elev= 28
    1003     436  1086.3     412  1094.7     410    1460     408  1482.7     406
  1485.3     404  1488.6     402  1491.6     400  1501.1     394    1530   390.4
    1550   389.4    1574   389.4    1600   390.4    1631   394.5  1634.4     396
  1640.1     398  1649.9     402  1717.5     404  1730.2     406  1740.3     408
  1753.8     410  2097.3     410  2273.3     412  2363.2     412    2450     414
  2495.3     414 2530.02     414 2623.58     435
#Mann= 5 ,-1,0
    1003     .03       0  1094.7     .07       0    1460    .035       0
  1753.8     .07       0  2495.3     .03       0
Bank Sta=1460,1753.8
XS Rating Curve= 0 ,0
Exp/Cntr=0.3,0.1

Type RM Length L Ch R = 1 ,12684   ,1050,1082,1010
BEGIN DESCRIPTION:
This cross section corresponds to cross section 12658 of the non-georeferenced CDC model which was the source of this model.
END DESCRIPTION:
XS GIS Cut Line= 3
2462161.249594336987116.51174313  2461254.5060016987831.98898672
2460785.060417596988181.00370863
#Sta/Elev= 30
    1010   436.4    1104   410.3    1150   408.7    1232   407.5    1289   408.9
    1346   408.2    1408   408.2    1431   408.7    1488   408.7    1526   408.3
    1551   393.3    1570     390    1590   388.9    1624     389    1648   394.6
    1692   398.6    1724   398.2    1739   398.4    1767   402.5    1811   410.6
    1860   409.4    1886   409.8    2076   409.5    2122   410.2    2182   410.6
    2254   411.6  2374.1     414  2655.3     418  2697.6     420    2750   421.5
#Mann= 4 ,-1,0
    1010     .03       0    1104     .07       0    1526    .035       0
    1811     .07       0
Bank Sta=1526,1811
XS Rating Curve= 0 ,0
Exp/Cntr=0.3,0.1

Type RM Length L Ch R = 1 ,11602   ,1050,1044,1030
BEGIN DESCRIPTION:
This cross section corresponds to cross section 11576 of the non-georeferenced CDC model which was the source of this model.
END DESCRIPTION:
XS GIS Cut Line= 2
2461487.142018686986294.703347382459906.435206326987643.57335305
#Sta/Elev= 30
    1009   436.3    1103   411.2    1213   407.4    1269   407.4    1283   409.6
    1593   408.2    1617     406    1679   404.5    1700   402.7    1748   398.1
    1779   388.1    1820     388    1860   388.9    1912   394.4    1917     399
    1922     401    1944   407.7    1954   409.1    2011   410.3    2282   410.2
    2432     414    2528     420    2643   430.1    2716   438.7    2754   440.8
    2774   444.3    2816   447.5    2921   460.3    2976   463.7    3087   466.3
#Mann= 4 ,-1,0
    1009     .03       0    1103     .07       0    1593    .035       0
    1954     .07       0
Bank Sta=1593,1954
XS Rating Curve= 0 ,0
Exp/Cntr=0.3,0.1

Type RM Length L Ch R = 1 ,10558   ,920,938,940
BEGIN DESCRIPTION:
This cross section corresponds to cross section 10532 of the non-georeferenced CDC model which was the source of this model.
END DESCRIPTION:
XS GIS Cut Line= 2
2460767.921344256985495.784669642459151.808106666986995.85253564
#Sta/Elev= 30
    1010   436.3    1111   410.1    1153   408.7    1257   408.5    1300   409.3
    1360   408.4    1543   409.6    1607   408.5    1661   404.9    1677   404.9
    1761     398    1792   387.3    1812  387.19    1839  387.19    1849   388.8
    1893   408.6    1962   409.7    2147   409.3    2176     411    2221   410.7
    2400   417.3    2495   422.8    2569   425.4    2655   430.1    2838   443.2
    2934   453.7    3009   453.5    3077   456.9    3109   460.3    3215   463.3
#Mann= 4 ,-1,0
    1010     .03       0    1111     .07       0    1677    .035       0
    1893     .07       0
Bank Sta=1677,1893
XS Rating Curve= 0 ,0
Exp/Cntr=0.3,0.1

Type RM Length L Ch R = 1 ,9620    ,960,995,1010
BEGIN DESCRIPTION:
This cross section corresponds to cross section 9594 of the non-georeferenced CDC model which was the source of this model.
END DESCRIPTION:
XS GIS Cut Line= 2
2460092.000123926984872.393856052458312.975794856986441.29688622
#Sta/Elev= 30
    1009   436.1    1057     421    1103   409.8    1473     408    1513   404.9
    1595   403.1    1622   399.4    1657   387.3    1677     386    1703     386
    1757     406    1778   410.8    1827   404.5    1890   408.2    2103   409.7
    2361   414.9    2447   419.9    2579   422.9    2714     430    2870   435.2
    2943   439.5    2972   444.1    3036     445    3192   451.2    3195   453.1
    3210   454.6    3213   458.7    3251   464.5    3348   464.4    3381   470.8
#Mann= 4 ,-1,0
    1009     .03       0    1103     .07       0    1595    .035       0
    1757     .07       0
Bank Sta=1595,1757
XS Rating Curve= 0 ,0
Exp/Cntr=0.3,0.1