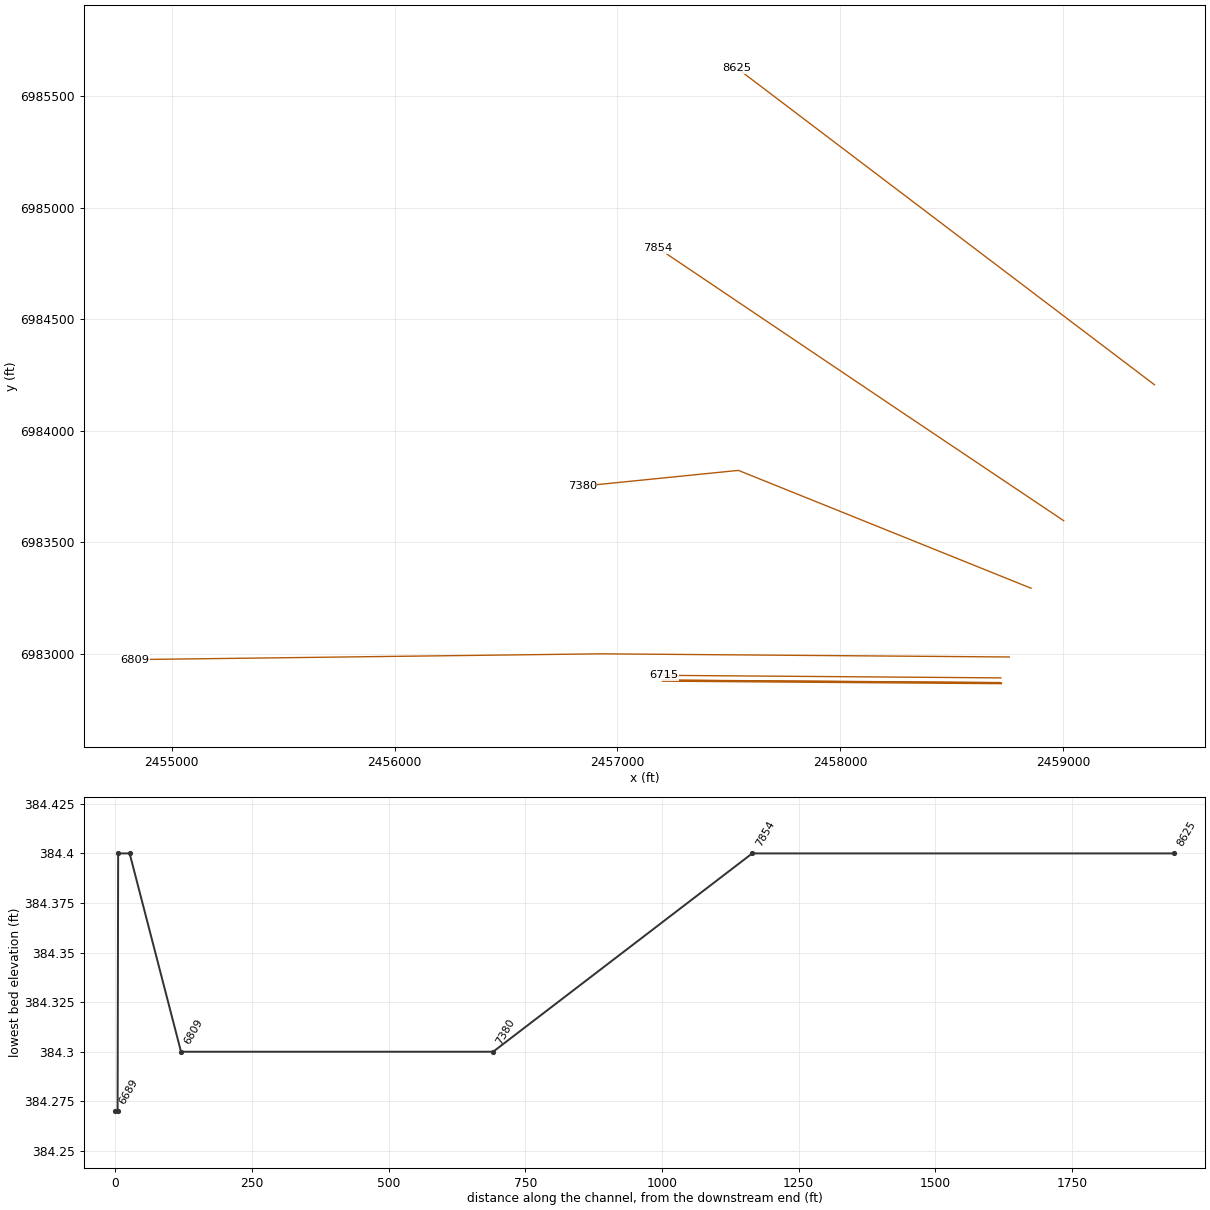
HEC-RAS study CDC_Consolidated_Model.prj: Upper Trinity CDC Consolidated Model

--- CDC_Consolidated_Model.g02 (geometry) --- (continued)

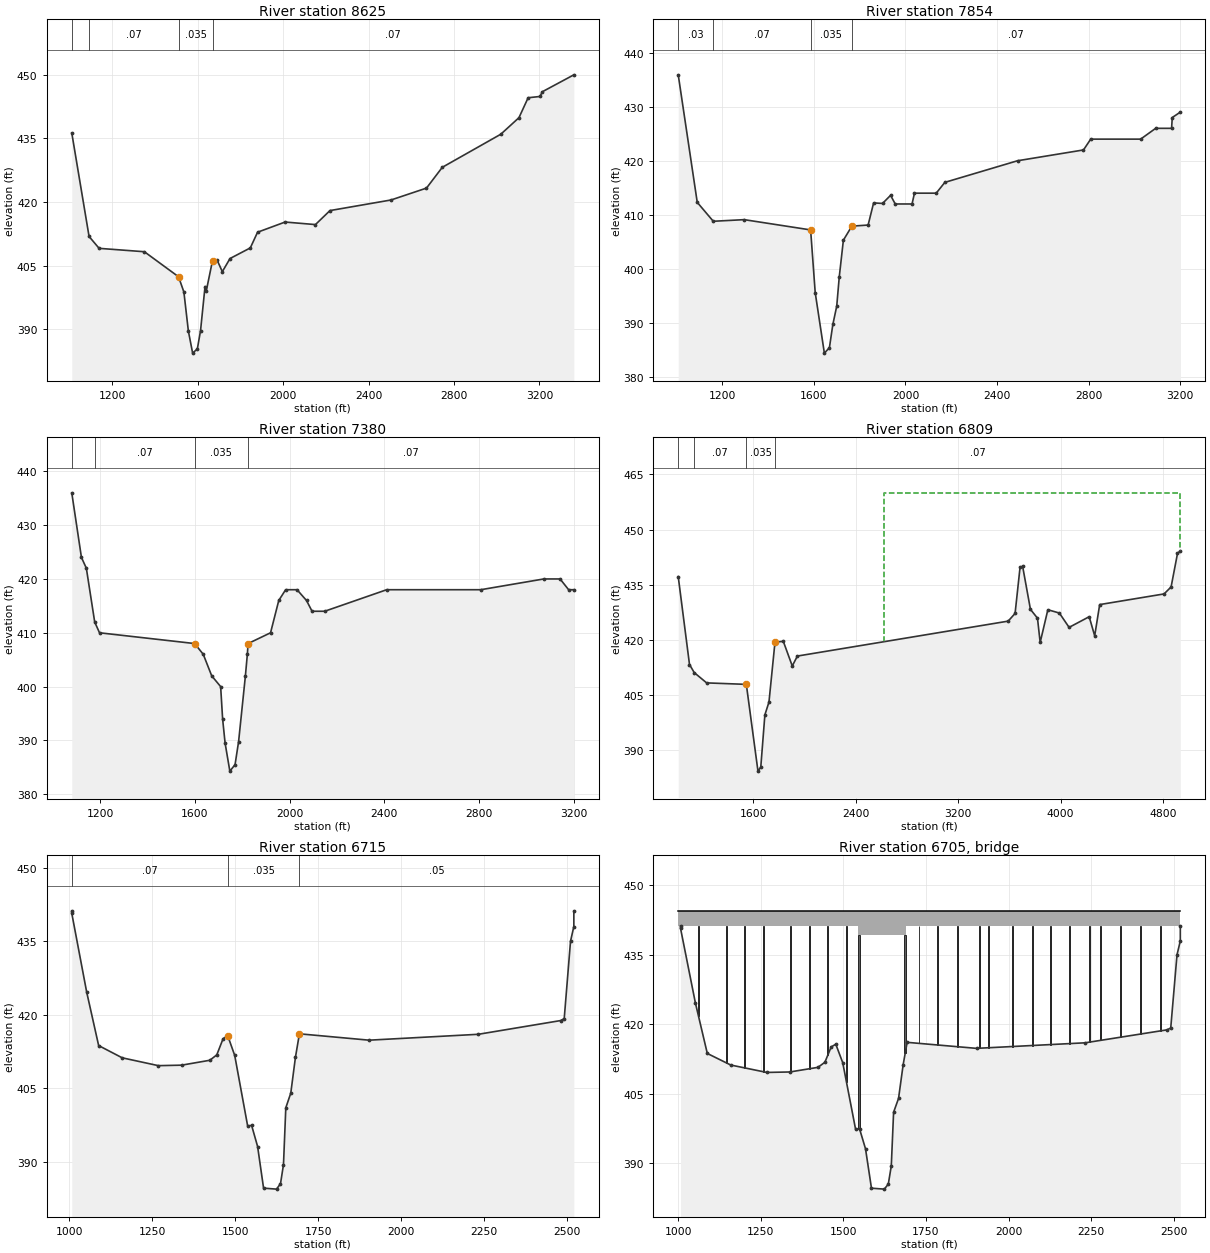
Type RM Length L Ch R = 1 ,8625    ,771,771,781
BEGIN DESCRIPTION:
This cross section corresponds to cross section 8599 of the non-georeferenced CDC model which was the source of this model.
END DESCRIPTION:
XS GIS Cut Line= 2
2459408.411924186984205.746239222457535.091851926985626.25914621
#Sta/Elev= 30
    1010   436.3    1091   411.9    1138   409.1    1350   408.3    1510   402.4
    1535   398.8    1556   389.6    1576   384.4    1598   385.4    1613   389.7
    1634   400.1    1640   399.1    1669   406.2    1690   406.4    1715   403.6
    1751   406.7    1846   409.2    1880   412.9    2009   415.3    2151   414.7
    2219     418    2505   420.5    2671   423.3    2745   428.2    3019     436
    3104   439.9    3147   444.6    3203   444.9    3213     446    3361     450
#Mann= 4 ,-1,0
    1010     .03       0    1091     .07       0    1510    .035       0
    1669     .07       0
Bank Sta=1510,1669
XS Rating Curve= 0 ,0
Exp/Cntr=0.3,0.1

Type RM Length L Ch R = 1 ,7854    ,400,474,550
BEGIN DESCRIPTION:
This cross section corresponds to cross section 7829 of the non-georeferenced CDC model which was the source of this model.
END DESCRIPTION:
XS GIS Cut Line= 3
 2459001.38485116983596.003364222458263.860079416984090.38918647
2457182.069592096984818.68530205
#Sta/Elev= 30
    1008   435.9    1091   412.3    1161   408.8    1296   409.1    1586   407.2
    1606   395.6    1646   384.4    1668   385.4    1683   389.7    1700   393.1
    1711   398.5    1729   405.3    1766   407.9    1837   408.1    1861   412.2
    1900   412.1    1935   413.6  1955.4     412  2028.8     412  2039.3     414
  2134.3     414    2172     416  2489.4     420  2777.3     422  2808.8     424
  3026.8     424  3092.4     426  3161.9     426  3164.9     428    3200     429
#Mann= 4 ,-1,0
    1008     .03       0    1161     .07       0    1586    .035       0
    1766     .07       0
Bank Sta=1586,1766
XS Rating Curve= 0 ,0
Exp/Cntr=0.3,0.1

Type RM Length L Ch R = 1 ,7380    ,459,571,659
BEGIN DESCRIPTION:
This cross section corresponds to cross section 7355 of the non-georeferenced CDC model which was the source of this model.
END DESCRIPTION:
XS GIS Cut Line= 3
2458855.041311746983293.112237722457542.564934076983821.59313613
2456841.794025936983750.99124321
#Sta/Elev= 30
  1080.8     436  1121.6     424  1142.3     422  1177.6     412  1197.9     410
  1599.4     408  1635.8     406  1671.5     402  1709.2     400  1717.5     394
    1728   389.5    1748   384.3    1770   385.5    1785   389.8  1813.7     402
  1821.9     406  1825.1     408  1919.8     410  1954.5     416  1983.5     418
  2031.6     418  2071.6     416    2095     414  2148.4     414    2410     418
    2807     418  3073.2     420  3141.9     420    3178     418    3200     418
#Mann= 4 ,-1,0
  1080.8     .03       0  1177.6     .07       0  1599.4    .035       0
  1825.1     .07       0
Bank Sta=1599.4,1825.1
XS Rating Curve= 0 ,0
Exp/Cntr=0.3,0.1

Type RM Length L Ch R = 1 ,6809    ,94,94,94
BEGIN DESCRIPTION:
This cross section corresponds to cross section 6783 of the non-georeferenced CDC model which was the source of this model.
END DESCRIPTION:
XS GIS Cut Line= 3
   2458757.294466982984.653865132456925.549107766982998.84707822
2454834.508670426982973.04332405
#Sta/Elev= 30
    1012   437.2    1100   413.3    1137   411.1    1234   408.3    1544   407.9
    1635   384.3    1657   385.4    1689   399.6    1721   403.1    1768   419.4
    1833   419.6    1903   412.9    1943   415.6    3590   425.1    3644   427.2
    3683   439.8    3703     440    3764   428.3    3819   425.9    3840   419.3
    3900   428.2    3990   427.3    4066   423.4    4223   426.3    4266   421.1
    4305   429.6    4808   432.5    4863   434.4    4913   443.5    4935   444.2
#Mann= 4 ,-1,0
    1012     .03       0    1137     .07       0    1544    .035       0
    1768     .07       0
#XS Ineff= 2 , 0
       0                    2620       0     460
Permanent Ineff=
       F       F
Bank Sta=1544,1768
XS Rating Curve= 0 ,0
Exp/Cntr=0.3,0.1

Type RM Length L Ch R = 1 ,6715    ,21,21,21
BEGIN DESCRIPTION:
This cross section corresponds to cross section 6689 of the non-georeferenced CDC model which was the source of this model.
END DESCRIPTION:
XS GIS Cut Line= 2
2458719.499916176982890.94670346 2457206.54756156982902.34070955
#Sta/Elev= 30
    1007   441.2    1007   440.7    1052  424.59    1088   413.7    1159   411.2
    1268   409.6    1338   409.7    1423   410.7    1444   411.8    1463   415.1
    1477   415.7    1498   411.7    1537   397.3    1549   397.4    1567   393.1
    1585   384.6    1624   384.4    1636   385.5    1645   389.4    1652     401
    1667     404    1681   411.3    1693   416.1    1903   414.8    2232     416
    2480   418.8    2491   419.2    2510     435    2520     438    2520   441.2
#Mann= 3 ,0,0
    1007     .07       0    1477    .035       0    1693     .05       0
Bank Sta=1477,1693
XS Rating Curve= 0 ,0
Exp/Cntr=0.5,0.3

Type RM Length L Ch R = 3 ,6705    ,,,
BEGIN DESCRIPTION:
Burlington Northen Sante Fe Railroad
END DESCRIPTION:
Node Name=BNSF RR
Bridge Culvert--1,0,-1,-1, 0
Deck Dist Width WeirC Skew NumUp NumDn MinLoCord MaxHiCord MaxSubmerge Is_Ogee
1,19,2.6,0, 53, 53, , , 0.95, 0, 0,0,,
    1000    1007    1048    1052    1146    1154    1296    1304    1348    1352
    1398    1402    1448    1452  1489.5  1490.5  1519.5  1520.5  1526.5    1544
    1544    1617    1690    1690  1724.5  1725.5  1739.5  1740.5    1788    1792
    1848    1852    1898    1902    1958    1962    1998    2002    2048    2052
    2148    2152    2256    2264    2298    2302    2426    2434    2468    2472
    2489    2491    2520
   444.5   444.5   444.5   444.5   444.5   444.5   444.5   444.5   444.5   444.5
   444.5   444.5   444.5   444.5   444.5   444.5   444.5   444.5   444.5   444.5
   444.5   444.5   444.5   444.5   444.5   444.5   444.5   444.5   444.5   444.5
   444.5   444.5   444.5   444.5   444.5   444.5   444.5   444.5   444.5   444.5
   444.5   444.5   444.5   444.5   444.5   444.5   444.5   444.5   444.5   444.5
   444.5   444.5   444.5
   441.2   441.2   441.2   441.2   441.2   441.2   441.2   441.2   441.2   441.2
   441.2   441.2   441.2   441.2   441.2   441.2   441.2   441.2   441.2   441.2
   439.3   439.3   439.3   441.2   441.2   441.2   441.2   441.2   441.2   441.2
   441.2   441.2   441.2   441.2   441.2   441.2   441.2   441.2   441.2   441.2
   441.2   441.2   441.2   441.2   441.2   441.2   441.2   441.2   441.2   441.2
   441.2   441.2   441.2
    1000    1007    1048    1052    1146    1154    1296    1304    1348    1352
    1398    1402    1448    1452  1489.5  1490.5  1519.5  1520.5  1526.5    1544
    1544    1617    1690    1690  1724.5  1725.5  1739.5  1740.5    1788    1792
    1848    1852    1898    1902    1958    1962    1998    2002    2048    2052
    2148    2152    2256    2264    2298    2302    2426    2434    2468    2472
    2489    2491    2520
   444.5   444.5   444.5   444.5   444.5   444.5   444.5   444.5   444.5   444.5
   444.5   444.5   444.5   444.5   444.5   444.5   444.5   444.5   444.5   444.5
   444.5   444.5   444.5   444.5   444.5   444.5   444.5   444.5   444.5   444.5
   444.5   444.5   444.5   444.5   444.5   444.5   444.5   444.5   444.5   444.5
   444.5   444.5   444.5   444.5   444.5   444.5   444.5   444.5   444.5   444.5
   444.5   444.5   444.5
   441.2   441.2   441.2   441.2   441.2   441.2   441.2   441.2   441.2   441.2
   441.2   441.2   441.2   441.2   441.2   441.2   441.2   441.2   441.2   441.2
   439.3   439.3   439.3   441.2   441.2   441.2   441.2   441.2   441.2   441.2
   441.2   441.2   441.2   441.2   441.2   441.2   441.2   441.2   441.2   441.2
   441.2   441.2   441.2   441.2   441.2   441.2   441.2   441.2   441.2   441.2
   441.2   441.2   441.2
Pier Skew, UpSta & Num, DnSta & Num=  ,1061, 2 ,10613.5, 2 , 0 , 0 , 0 ,,
     3.5     3.5
       0     442
     3.5     3.5
       0     442
Pier Skew, UpSta & Num, DnSta & Num=  ,1145, 2 ,1145, 2 , 0 , 0 , 0 ,,
     3.5     3.5
       0     442
     3.5     3.5
       0     442
Pier Skew, UpSta & Num, DnSta & Num=  ,1201, 2 ,1201, 2 , 0 , 0 , 0 ,,
    2.34    2.34
       0     442
    2.34    2.34
       0     442
Pier Skew, UpSta & Num, DnSta & Num=  ,1257, 2 ,1257, 2 , 0 , 0 , 0 ,,
     3.5     3.5
       0     442
     3.5     3.5
       0     442
Pier Skew, UpSta & Num, DnSta & Num=  ,1341, 2 ,1341, 2 , 0 , 0 , 0 ,,
     3.5     3.5
       0     442
     3.5     3.5
       0     442
Pier Skew, UpSta & Num, DnSta & Num=  ,1397, 2 ,1397, 2 , 0 , 0 , 0 ,,
    2.34    2.34
       0     442
    2.34    2.34
       0     442
Pier Skew, UpSta & Num, DnSta & Num=  ,1453, 2 ,1453, 2 , 0 , 0 , 0 ,,
     3.5     3.5
       0     442
     3.5     3.5
       0     442
Pier Skew, UpSta & Num, DnSta & Num=  ,1509, 2 ,1509, 2 , 0 , 0 , 0 ,,
    1.17    1.17
       0     442
    1.17    1.17
       0     442
Pier Skew, UpSta & Num, DnSta & Num=  ,1547, 2 ,1547, 2 , 0 , 0 , 0 ,,
       6       6
       0     442
       6       6
       0     442
Pier Skew, UpSta & Num, DnSta & Num=  ,1687, 2 ,1687, 2 , 0 , 0 , 0 ,,
       6       6
       0     442
       6       6
       0     442
Pier Skew, UpSta & Num, DnSta & Num=  ,1728, 2 ,1728, 2 , 0 , 0 , 0 ,,
    1.17    1.17
       0     442
    1.17    1.17
       0     442
Pier Skew, UpSta & Num, DnSta & Num=  ,1784, 2 ,1784, 2 , 0 , 0 , 0 ,,
     3.5     3.5
       0     442
     3.5     3.5
       0     442
Pier Skew, UpSta & Num, DnSta & Num=  ,1845, 2 ,1845, 2 , 0 , 0 , 0 ,,
    2.34    2.34
       0     442
    2.34    2.34
       0     442
Pier Skew, UpSta & Num, DnSta & Num=  ,1911, 2 ,1911, 2 , 0 , 0 , 0 ,,
    2.34    2.34
       0     442
    2.34    2.34
       0     442
Pier Skew, UpSta & Num, DnSta & Num=  ,1939, 2 ,1939, 2 , 0 , 0 , 0 ,,
    2.34    2.34
       0     442
    2.34    2.34
       0     442
Pier Skew, UpSta & Num, DnSta & Num=  ,2011, 2 ,2011, 2 , 0 , 0 , 0 ,,
    2.34    2.34
       0     442
    2.34    2.34
       0     442
Pier Skew, UpSta & Num, DnSta & Num=  ,2072, 2 ,2072, 2 , 0 , 0 , 0 ,,
     3.5     3.5
       0     442
     3.5     3.5
       0     442
Pier Skew, UpSta & Num, DnSta & Num=  ,2128, 2 ,2128, 2 , 0 , 0 , 0 ,,
    2.34    2.34
       4     442
    2.34    2.34
       4     442
Pier Skew, UpSta & Num, DnSta & Num=  ,2184, 2 ,2184, 2 , 0 , 0 , 0 ,,
    2.34    2.34
       4     442
    2.34    2.34
       4     442
Pier Skew, UpSta & Num, DnSta & Num=  ,2245, 2 ,2245, 2 , 0 , 0 , 0 ,,
    2.34    2.34
       4     442
    2.34    2.34
       4     442
Pier Skew, UpSta & Num, DnSta & Num=  ,2278, 2 ,2278, 2 , 0 , 0 , 0 ,,
    2.34    2.34
       4     442
    2.34    2.34
       4     442
Pier Skew, UpSta & Num, DnSta & Num=  ,2339, 2 ,2339, 2 , 0 , 0 , 0 ,,
    2.34    2.34
       4     442
    2.34    2.34
       4     442
Pier Skew, UpSta & Num, DnSta & Num=  ,2400, 2 ,2400, 2 , 0 , 0 , 0 ,,
    2.34    2.34
       4     442
    2.34    2.34
       4     442
Pier Skew, UpSta & Num, DnSta & Num=  ,2461, 2 ,24613.54, 2 , 0 , 0 , 0 ,,
     3.5     3.5
       4     442
     3.5     3.5
       4     442
BR Coef=-1 , 0 , 0 ,1.05, 0 ,,,0.8,-1,0.5,0,
WSPro=,,,, 1 ,,,, 0 ,,,, 0 ,,,,-1 ,-1 ,-1 , 0 , 0 , 0 , 0 , 0
BC Design=,, 0 ,, 0 ,,,,,,
BC Use User HTab Curves=0
BC User HTab FreeFlow(D)= 0

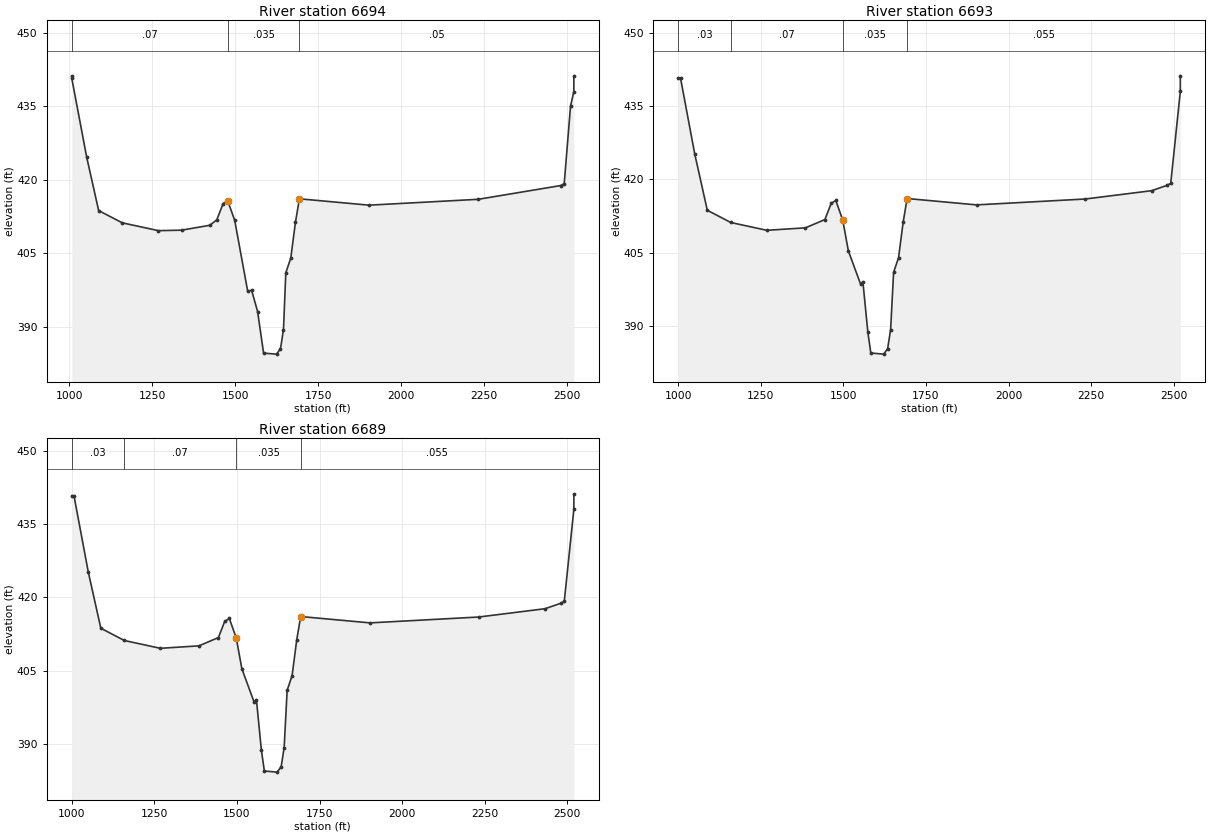
Type RM Length L Ch R = 1 ,6694    ,1,1,1
BEGIN DESCRIPTION:
This cross section corresponds to cross section 6668 of the non-georeferenced CDC model which was the source of this model.
END DESCRIPTION:
XS GIS Cut Line= 2
      2458714.85     6982869.982     2457201.766       6982881.3
#Sta/Elev= 30
    1007   441.2    1007   440.7    1052  424.59    1088   413.7    1159   411.2
    1268   409.6    1338   409.7    1423   410.7    1444   411.8    1463   415.1
    1477   415.7    1498   411.7    1537   397.3    1549   397.4    1567   393.1
    1585   384.6    1624   384.4    1636   385.5    1645   389.4    1652     401
    1667     404    1681   411.3    1693   416.1    1903   414.8    2232     416
    2480   418.8    2491   419.2    2510     435    2520     438    2520   441.2
#Mann= 3 ,0,0
    1007     .07       0    1477    .035       0    1693     .05       0
Bank Sta=1477,1693
XS Rating Curve= 0 ,0
Exp/Cntr=0.5,0.3

Type RM Length L Ch R = 1 ,6693    ,4,4,4
BEGIN DESCRIPTION:
This cross section corresponds to cross section 6663 of the non-georeferenced CDC model which was the source of this model.
END DESCRIPTION:
XS GIS Cut Line= 2
 2458721.95791656982868.929030972457201.95144209 6982880.2807143
#Sta/Elev= 30
    1000   440.8    1007   440.7    1050   425.2    1088   413.7    1159   411.2
    1268   409.6    1385   410.1    1444   411.8    1463   415.1    1477   415.7
    1498   411.7    1515   405.4    1552   398.6    1559   399.1    1574   388.8
    1583   384.5    1622  384.27    1634   385.4    1643   389.3    1652     401
    1667     404    1681   411.3    1693   416.1    1903   414.8    2232     416
    2433   417.7    2480   418.8    2491   419.2    2520     438    2520   441.2
#Mann= 4 ,-1,0
    1000     .03       0    1159     .07       0    1498    .035       0
    1693    .055       0
Bank Sta=1498,1693
XS Rating Curve= 0 ,0
Exp/Cntr=0.3,0.1

Type RM Length L Ch R = 1 ,6689    ,20,20,20
BEGIN DESCRIPTION:
This cross section corresponds to cross section 6663 of the non-georeferenced CDC model which was the source of this model.
END DESCRIPTION:
XS GIS Cut Line= 2
2458721.842103096982864.93166363 2457201.89435566982876.24299271
#Sta/Elev= 30
    1000   440.8    1007   440.7    1050   425.2    1088   413.7    1159   411.2
    1268   409.6    1385   410.1    1444   411.8    1463   415.1    1477   415.7
    1498   411.7    1515   405.4    1552   398.6    1559   399.1    1574   388.8
    1583   384.5    1622  384.27    1634   385.4    1643   389.3    1652     401
    1667     404    1681   411.3    1693   416.1    1903   414.8    2232     416
    2433   417.7    2480   418.8    2491   419.2    2520     438    2520   441.2
#Mann= 4 ,-1,0
    1000     .03       0    1159     .07       0    1498    .035       0
    1693    .055       0
Bank Sta=1498,1693
XS Rating Curve= 0 ,0
Exp/Cntr=0.5,0.3