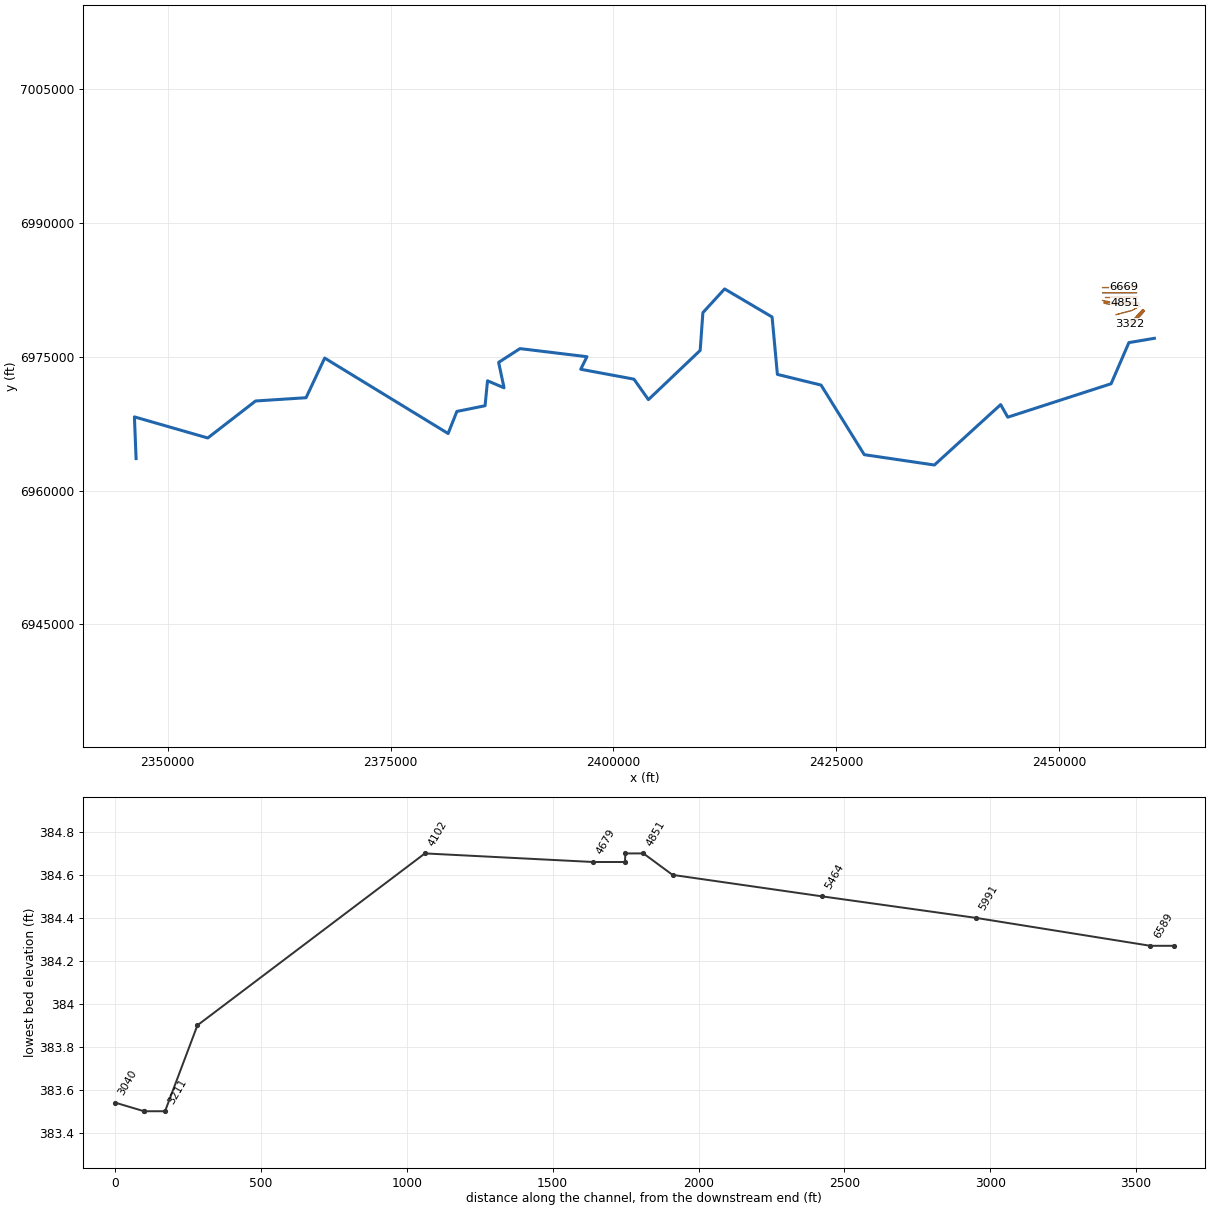
HEC-RAS study CDC_Consolidated_Model.prj: Upper Trinity CDC Consolidated Model

--- CDC_Consolidated_Model.g02 (geometry) --- (continued)

Type RM Length L Ch R = 3 ,6679    ,,,
BEGIN DESCRIPTION:
Burlington Northern Sante Fe Railroad
END DESCRIPTION:
Node Name=BNSF RR
Bridge Culvert--1,0,-1,-1, 0
Deck Dist Width WeirC Skew NumUp NumDn MinLoCord MaxHiCord MaxSubmerge Is_Ogee
0.5,19,2.6,0, 52, 52, , , 0.95, 0, 0,0,,
    1000    1048    1052    1146    1154    1296    1304    1348    1352    1398
    1402    1448    1452  1489.5  1490.5  1519.5  1520.5  1526.5    1547    1547
    1617    1687    1687  1724.5  1725.5  1739.5  1740.5    1788    1792    1848
    1852    1898    1902    1958    1962    1998    2002    2048    2052    2148
    2152    2256    2264    2298    2302    2426    2434    2468    2472    2489
    2491    2520
   444.5   444.5   444.5   444.5   444.5   444.5   444.5   444.5   444.5   444.5
   444.5   444.5   444.5   444.5   444.5   444.5   444.5   444.5   444.5   444.5
   444.5   444.5   444.5   444.5   444.5   444.5   444.5   444.5   444.5   444.5
   444.5   444.5   444.5   444.5   444.5   444.5   444.5   444.5   444.5   444.5
   444.5   444.5   444.5   444.5   444.5   444.5   444.5   444.5   444.5   444.5
   444.5   444.5
   441.2   441.2   441.2   441.2   441.2   441.2   441.2   441.2   441.2   441.2
   441.2   441.2   441.2   441.2   441.2   441.2   441.2   441.2   441.2   439.3
   439.3   439.3   441.2   441.2   441.2   441.2   441.2   441.2   441.2   441.2
   441.2   441.2   441.2   441.2   441.2   441.2   441.2   441.2   441.2   441.2
   441.2   441.2   441.2   441.2   441.2   441.2   441.2   441.2   441.2   441.2
   441.2   441.2
    1000    1048    1052    1146    1154    1296    1304    1348    1352    1398
    1402    1448    1452  1489.5  1490.5  1519.5  1520.5  1526.5    1547    1547
    1617    1687    1687  1724.5  1725.5  1739.5  1740.5    1788    1792    1848
    1852    1898    1902    1958    1962    1998    2002    2048    2052    2148
    2152    2256    2264    2298    2302    2426    2434    2468    2472    2489
    2491    2520
   444.5   444.5   444.5   444.5   444.5   444.5   444.5   444.5   444.5   444.5
   444.5   444.5   444.5   444.5   444.5   444.5   444.5   444.5   444.5   444.5
   444.5   444.5   444.5   444.5   444.5   444.5   444.5   444.5   444.5   444.5
   444.5   444.5   444.5   444.5   444.5   444.5   444.5   444.5   444.5   444.5
   444.5   444.5   444.5   444.5   444.5   444.5   444.5   444.5   444.5   444.5
   444.5   444.5
   441.2   441.2   441.2   441.2   441.2   441.2   441.2   441.2   441.2   441.2
   441.2   441.2   441.2   441.2   441.2   441.2   441.2   441.2   441.2   439.3
   439.3   439.3   441.2   441.2   441.2   441.2   441.2   441.2   441.2   441.2
   441.2   441.2   441.2   441.2   441.2   441.2   441.2   441.2   441.2   441.2
   441.2   441.2   441.2   441.2   441.2   441.2   441.2   441.2   441.2   441.2
   441.2   441.2
Pier Skew, UpSta & Num, DnSta & Num=  ,1061, 2 ,1061, 2 , 0 , 0 , 0 ,,
     3.5     3.5
       0     442
     3.5     3.5
       0     442
Pier Skew, UpSta & Num, DnSta & Num=  ,1145, 2 ,1145, 2 , 0 , 0 , 0 ,,
     3.5     3.5
       0     442
     3.5     3.5
       0     442
Pier Skew, UpSta & Num, DnSta & Num=  ,1201, 2 ,1201, 2 , 0 , 0 , 0 ,,
    2.34    2.34
       0     442
    2.34    2.34
       0     442
Pier Skew, UpSta & Num, DnSta & Num=  ,1257, 2 ,12573.5, 2 , 0 , 0 , 0 ,,
     3.5     3.5
       0     442
     3.5     3.5
       0     442
Pier Skew, UpSta & Num, DnSta & Num=  ,1341, 2 ,1341, 2 , 0 , 0 , 0 ,,
     3.5     3.5
       0     442
     3.5     3.5
       0     442
Pier Skew, UpSta & Num, DnSta & Num=  ,1397, 2 ,1397, 2 , 0 , 0 , 0 ,,
    2.34    2.34
       0     442
    2.34    2.34
       0     442
Pier Skew, UpSta & Num, DnSta & Num=  ,1453, 2 ,1453, 2 , 0 , 0 , 0 ,,
     3.5     3.5
       0     442
     3.5     3.5
       0     442
Pier Skew, UpSta & Num, DnSta & Num=  ,1509, 2 ,1509, 2 , 0 , 0 , 0 ,,
    1.17    1.17
       0     442
    1.17    1.17
       0     442
Pier Skew, UpSta & Num, DnSta & Num=  ,1547, 2 ,1547, 2 , 0 , 0 , 0 ,,
       6       6
       0     442
       6       6
       0     442
Pier Skew, UpSta & Num, DnSta & Num=  ,1687, 2 ,1687, 2 , 0 , 0 , 0 ,,
       6       6
       0     442
       6       6
       0     442
Pier Skew, UpSta & Num, DnSta & Num=  ,1728, 2 ,1728, 2 , 0 , 0 , 0 ,,
    1.17    1.17
       0     442
    1.17    1.17
       0     442
Pier Skew, UpSta & Num, DnSta & Num=  ,1784, 2 ,1784, 2 , 0 , 0 , 0 ,,
     3.5     3.5
       0     442
     3.5     3.5
       0     442
Pier Skew, UpSta & Num, DnSta & Num=  ,1845, 2 ,1845, 2 , 0 , 0 , 0 ,,
    2.34    2.34
       0     442
    2.34    2.34
       0     442
Pier Skew, UpSta & Num, DnSta & Num=  ,1911, 2 ,1911, 2 , 0 , 0 , 0 ,,
    2.34    2.34
       0     442
    2.34    2.34
       0     442
Pier Skew, UpSta & Num, DnSta & Num=  ,1939, 2 ,1939, 2 , 0 , 0 , 0 ,,
    2.34    2.34
       0     442
    2.34    2.34
       0     442
Pier Skew, UpSta & Num, DnSta & Num=  ,2011, 2 ,2011, 2 , 0 , 0 , 0 ,,
    2.34    2.34
       0     442
    2.34    2.34
       0     442
Pier Skew, UpSta & Num, DnSta & Num=  ,2072, 2 ,2072, 2 , 0 , 0 , 0 ,,
     3.5     3.5
       0     442
     3.5     3.5
       0     442
Pier Skew, UpSta & Num, DnSta & Num=  ,2128, 2 ,2128, 2 , 0 , 0 , 0 ,,
    2.34    2.34
       0     442
    2.34    2.34
       0     442
Pier Skew, UpSta & Num, DnSta & Num=  ,2184, 2 ,2184, 2 , 0 , 0 , 0 ,,
    2.34    2.34
       0     442
    2.34    2.34
       0     442
Pier Skew, UpSta & Num, DnSta & Num=  ,2245, 2 ,2245, 2 , 0 , 0 , 0 ,,
    2.34    2.34
       0     442
    2.34    2.34
       0     442
Pier Skew, UpSta & Num, DnSta & Num=  ,2278, 2 ,2278, 2 , 0 , 0 , 0 ,,
    2.34    2.34
       0     442
    2.34    2.34
       0     442
Pier Skew, UpSta & Num, DnSta & Num=  ,2339, 2 ,2339, 2 , 0 , 0 , 0 ,,
    2.34    2.34
       0     442
    2.34    2.34
       0     442
Pier Skew, UpSta & Num, DnSta & Num=  ,2400, 2 ,2400, 2 , 0 , 0 , 0 ,,
    2.34    2.34
       0     442
    2.34    2.34
       0     442
Pier Skew, UpSta & Num, DnSta & Num=  ,2461, 2 ,2461, 2 , 0 , 0 , 0 ,,
     3.5     3.5
       0     442
     3.5     3.5
       0     442
BR Coef=-1 , 0 , 0 ,1.05, 0 ,,,0.8,-1,0.5,0,
WSPro=,,,, 1 ,,,, 0 ,,,, 0 ,,,,-1 ,-1 ,-1 , 0 , 0 , 0 , 0 , 0
BC Design=,, 0 ,, 0 ,,,,,,
BC Use User HTab Curves=0
BC User HTab FreeFlow(D)= 0

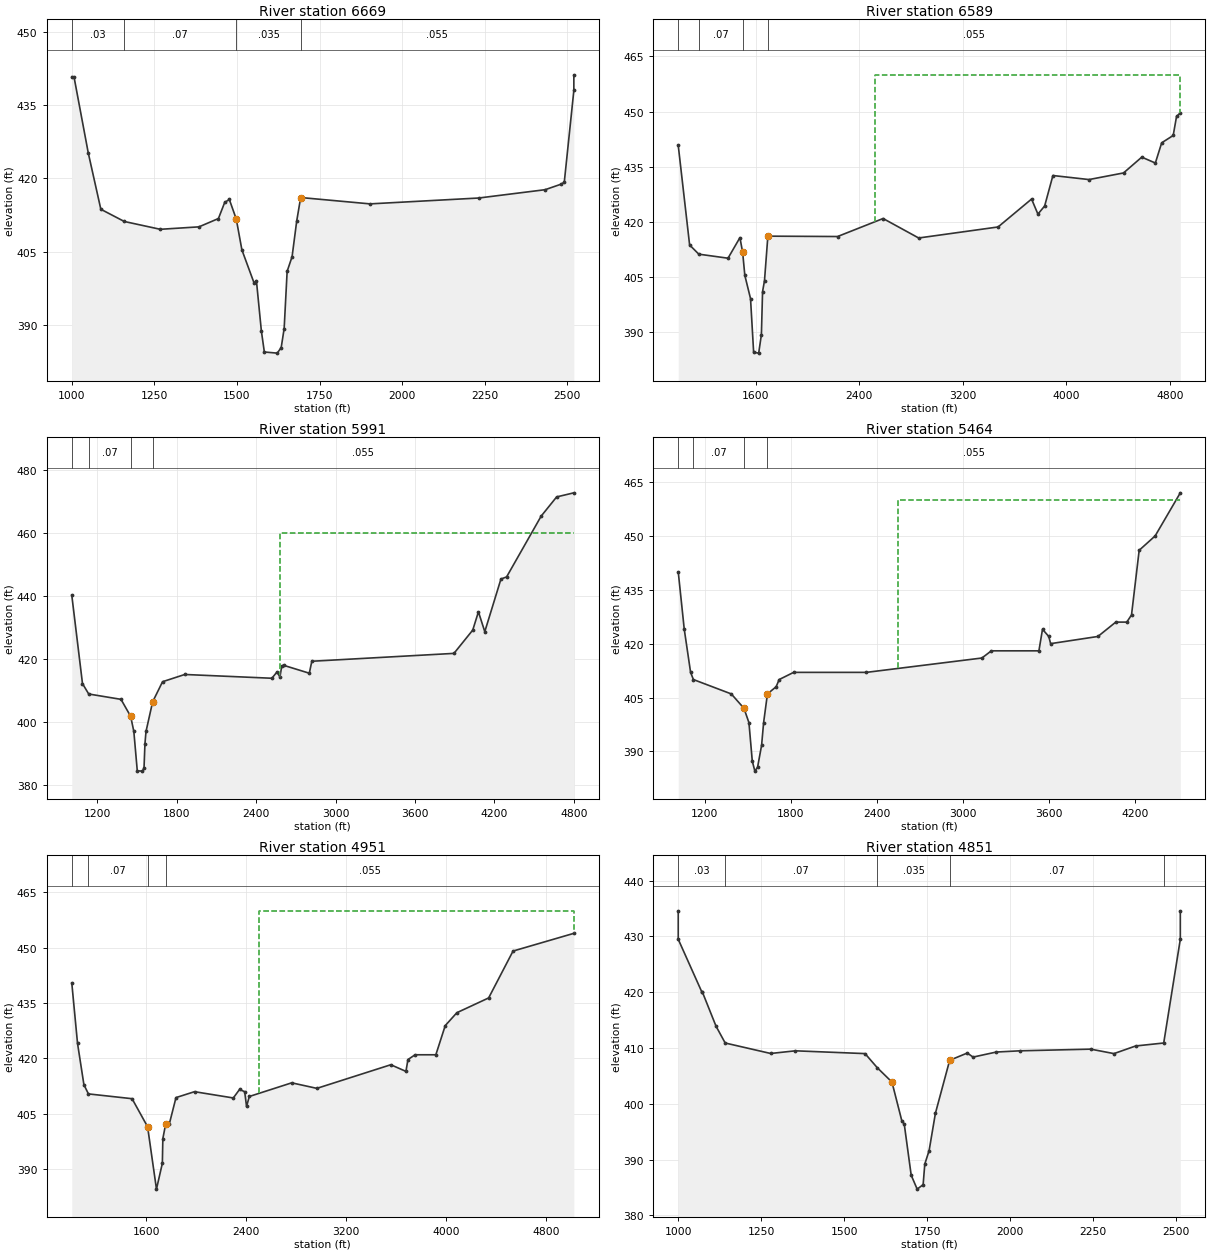
Type RM Length L Ch R = 1 ,6669    ,80,80,80
BEGIN DESCRIPTION:
This cross section corresponds to cross section 6643 of the non-georeferenced CDC model which was the source of this model.
---------------------------------------------------------------------
CDC IRV092399-1 BNSF Bridge
CROSS-SECTION 6643 - 6689
---------------------------------------------------------------------
END DESCRIPTION:
XS GIS Cut Line= 2
2458733.769572686982844.843121132457213.812966916982856.12689121
#Sta/Elev= 30
    1000   440.8    1007   440.7    1050   425.2    1088   413.7    1159   411.2
    1268   409.6    1385   410.1    1444   411.8    1463   415.1    1477   415.7
    1498   411.7    1515   405.4    1552   398.6    1559   399.1    1574   388.8
    1583   384.5    1622  384.27    1634   385.4    1643   389.3    1652     401
    1667     404    1681   411.3    1693   416.1    1903   414.8    2232     416
    2433   417.7    2480   418.8    2491   419.2    2520     438    2520   441.2
#Mann= 4 ,-1,0
    1000     .03       0    1159     .07       0    1498    .035       0
    1693    .055       0
Bank Sta=1498,1693
XS Rating Curve= 0 ,0
Exp/Cntr=0.5,0.3

Type RM Length L Ch R = 1 ,6589    ,598,598,598
BEGIN DESCRIPTION:
This cross section corresponds to cross section 6563 of the non-georeferenced CDC model which was the source of this model.
END DESCRIPTION:
XS GIS Cut Line= 3
2458720.327014276982764.951220562456926.186901756982777.93413422
2454838.522770026982753.02407905
#Sta/Elev= 30
    1000   440.8    1088   413.7    1159   411.2    1385   410.1    1477   415.7
    1498   411.7    1515   405.4    1559   399.1    1583   384.5    1622  384.27
    1643   389.3    1652     401    1667     404    1693   416.1    2232     416
    2584   420.9    2859   415.6    3473   418.6    3732   426.2    3781   422.1
    3833   424.3    3897   432.6    4176   431.5    4443   433.3    4584   437.6
    4689     436    4738   441.5    4827   443.5    4853   448.7    4882   449.6
#Mann= 4 ,-1,0
    1000     .03       0    1159     .07       0    1498    .035       0
    1693    .055       0
#XS Ineff= 2 , 0
       0                    2520       0     460
Permanent Ineff=
       F       F
Bank Sta=1498,1693
XS Rating Curve= 0 ,0
Exp/Cntr=0.3,0.1

Type RM Length L Ch R = 1 ,5991    ,527,527,527
BEGIN DESCRIPTION:
This cross section corresponds to cross section 5965 of the non-georeferenced CDC model which was the source of this model.
END DESCRIPTION:
XS GIS Cut Line= 2
2458645.244159166982174.781797222454851.314083016982151.77790621
#Sta/Elev= 30
    1007   440.3    1088   412.2    1135   408.9    1379   407.2    1452   401.8
    1476     397    1502   384.5    1541   384.4    1553   385.4    1560   393.1
    1568     397    1618   406.4    1693   412.8    1861   415.1    2519   413.9
    2558   415.9    2580   414.3    2594   417.8    2609     418    2802   415.5
    2821   419.3    3895   421.8    4037   429.2    4080     435    4128   428.7
    4250   445.4    4293   446.1    4554   465.4    4671   471.5    4801   472.8
#Mann= 4 ,-1,0
    1007     .03       0    1135     .07       0    1452    .035       0
    1618    .055       0
#XS Ineff= 2 , 0
       0                    2580       0     460
Permanent Ineff=
       F       F
Bank Sta=1452,1618
XS Rating Curve= 0 ,0
Exp/Cntr=0.3,0.1

Type RM Length L Ch R = 1 ,5464    ,513,513,513
BEGIN DESCRIPTION:
This cross section corresponds to cross section 5438 of the non-georeferenced CDC model which was the source of this model.
END DESCRIPTION:
XS GIS Cut Line= 3
2458680.768366346981645.731346132457814.093918596981643.43902788
2455179.271432346981644.76120372
#Sta/Elev= 30
  1016.6     440  1058.6     424  1102.8     412  1122.4     410  1386.6     406
  1474.9     402  1509.7     398    1533   387.3    1551   384.5    1570   385.6
    1598   391.7    1612     398  1638.7     406  1699.4     408  1720.4     410
  1821.3     412  2328.6     412  3134.5     416  3200.3     418    3532     418
    3557     424  3600.7     422  3613.6     420  3943.5     422    4068     426
  4144.9     426  4177.8     428  4231.2     446  4342.6     450  4518.1     462
#Mann= 4 ,-1,0
  1016.6     .03       0  1122.4     .07       0  1474.9    .035       0
  1638.7    .055       0
#XS Ineff= 2 , 0
       0                    2550       0     460
Permanent Ineff=
       F       F
Bank Sta=1474.9,1638.7
XS Rating Curve= 0 ,0
Exp/Cntr=0.3,0.1

Type RM Length L Ch R = 1 ,4951    ,100,100,100
BEGIN DESCRIPTION:
This cross section corresponds to cross section 4925 of the non-georeferenced CDC model which was the source of this model.
END DESCRIPTION:
XS GIS Cut Line= 6
2458826.461316446981096.603179312456870.079074356981199.42416789
2456286.012985266981126.415127552455964.778063426981111.81410688
2455701.947880426981141.01713246 2454838.2396341 6981305.8271703
#Sta/Elev= 30
    1006   440.5    1052   424.1    1103   412.9    1139   410.4    1488   409.1
    1612   401.5    1683   384.6    1730   391.6    1734   398.3    1757   402.3
    1786   402.3    1839   409.4    1987     411    2297   409.3    2347   411.6
    2388     411    2403     407    2425   409.7    2764   413.4    2965   411.9
    3556   418.3    3677   416.5    3693   419.7    3750     421    3916     421
    3991   428.9    4084   432.4    4338   436.4    4533   449.1    5019   453.9
#Mann= 4 ,-1,0
    1006     .03       0    1139     .07       0    1612    .035       0
    1757    .055       0
#XS Ineff= 2 , 0
       0                    2500       0     460
Permanent Ineff=
       F       F
Bank Sta=1612,1757
XS Rating Curve= 0 ,0
Exp/Cntr=0.3,0.1

Type RM Length L Ch R = 1 ,4851    ,62,62,62
BEGIN DESCRIPTION:
This cross section corresponds to cross section 4826 of the non-georeferenced CDC model which was the source of this model.
END DESCRIPTION:
XS GIS Cut Line= 3
2458880.24992275 6980991.97149882458152.950196276981032.34608996
2457369.44356117 6981073.3768478
#Sta/Elev= 30
    1000   434.6    1000   429.5  1071.5     420    1073     420    1114   413.9
  1141.5   410.9  1278.5 409.022    1353   409.5    1563     409 1599.77 406.469
    1644   403.9    1674   396.9    1681   396.4    1702   387.2    1720   384.7
    1738   385.5    1743   389.2    1756   391.6    1775   398.3    1818   407.8
    1871   409.1  1888.5 408.375  1958.5  409.28  2028.5 409.496    2243   409.8
    2313     409  2378.5 410.369    2463   410.9    2513   429.5    2513   434.5
#Mann= 5 ,-1,0
    1000     .03       0  1141.5     .07       0 1599.77    .035       0
    1818     .07       0    2463     .03       0
Bank Sta=1644,1818
XS Rating Curve= 0 ,0
Exp/Cntr=0.5,0.3

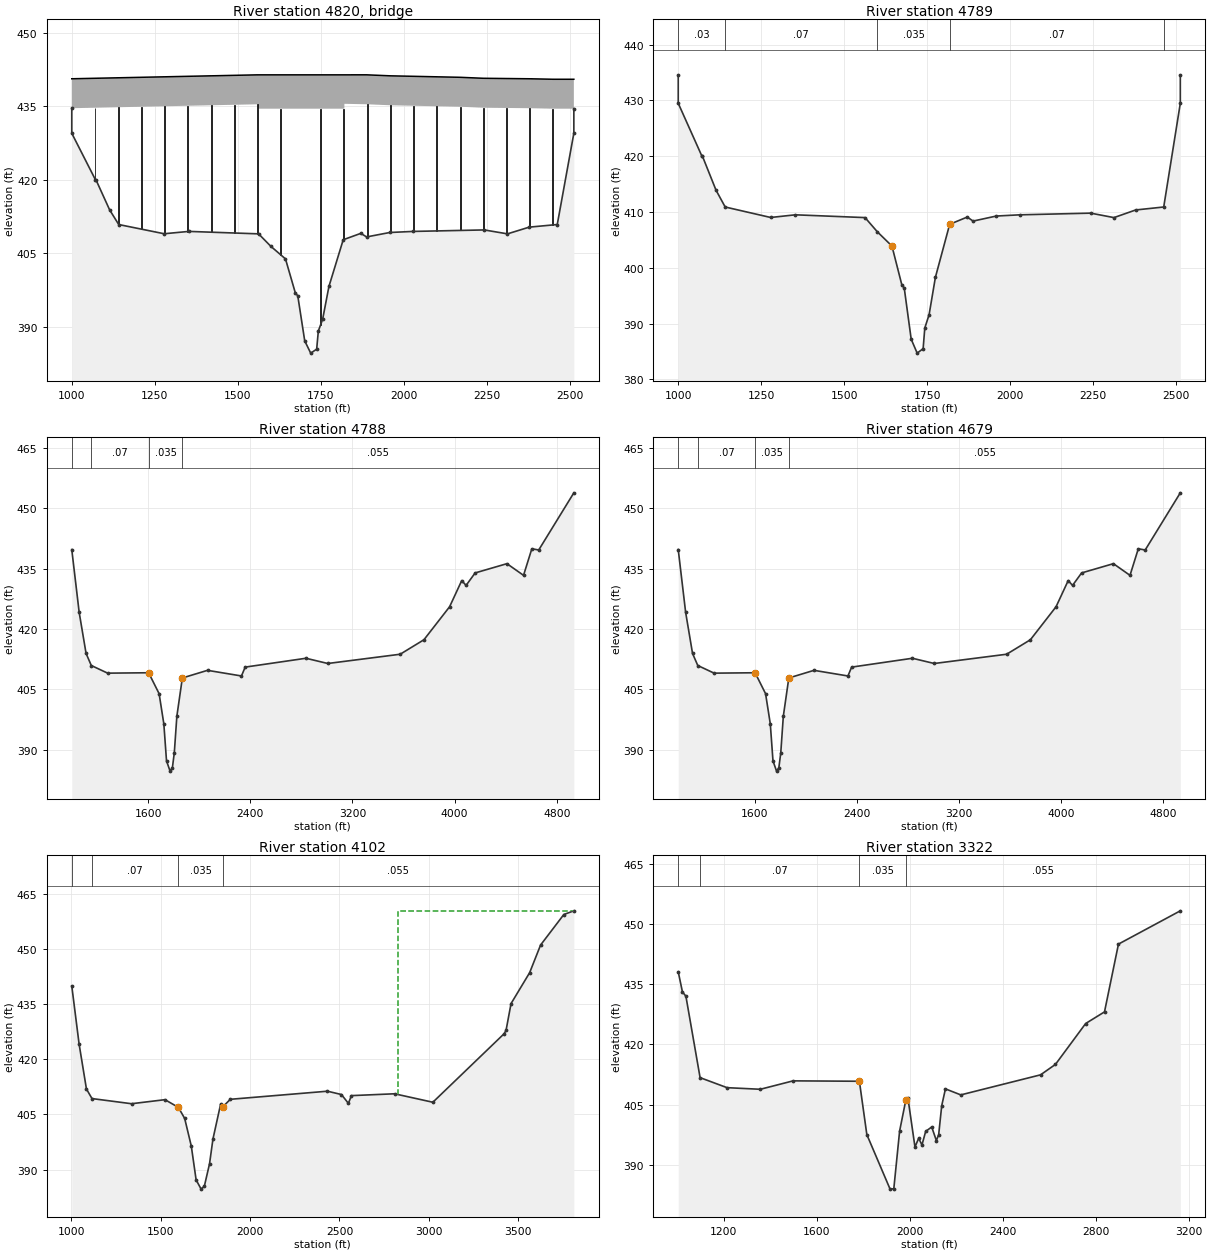
Type RM Length L Ch R = 3 ,4820    ,,,
BEGIN DESCRIPTION:
SH 356/Irving Boulevard
END DESCRIPTION:
Node Name=SH 356/Irving Bl
Bridge Culvert--1,0,-1,-1, 0
Deck Dist Width WeirC Skew NumUp NumDn MinLoCord MaxHiCord MaxSubmerge Is_Ogee
2,59,2.6,0, 44, 44, , , 0.95, 0, ,,,
    1000  1068.5  1071.5  1138.5  1141.5  1208.5  1211.5  1278.5  1281.5  1348.5
  1351.5  1418.5  1421.5  1488.5  1491.5  1558.5  1561.5  1561.5 1628.25 1631.75
 1748.25 1751.75  1818.5  1821.5  1821.5  1888.5  1891.5  1958.5  1961.5  2028.5
  2031.5  2098.5  2101.5  2168.5  2171.5  2238.5  2241.5  2308.5  2311.5  2378.5
  2381.5  2448.5  2451.5    2513
   440.6 440.698 440.702 440.798 440.802 440.898 440.902 440.998 441.002 441.098
 441.102 441.198 441.202 441.298 441.302 441.398   441.4   441.4   441.4   441.4
   441.4   441.4   441.4   441.4   441.4 441.402 441.396 441.204 441.198 441.102
 441.098 441.002 440.998 440.902 440.896 440.704 440.699 440.651 440.649 440.601
 440.598 440.502   440.5   440.5
   434.6 434.698 434.702 434.798 434.802 434.898 434.902 434.998 435.002 435.098
 435.102 435.198 435.202 435.298 435.302 435.398   435.4   434.5   434.5   434.5
   434.5   434.5   434.5  434.52   435.5 435.402 435.396 435.204 435.198 435.102
 435.098 435.002 434.998 434.902 434.896 434.704 434.699 434.651 434.649 434.601
 434.598 434.502   434.5   434.5
    1000  1068.5  1071.5  1138.5  1141.5  1208.5  1211.5  1278.5  1281.5  1348.5
  1351.5  1418.5  1421.5  1488.5  1491.5  1558.5  1561.5  1561.5 1628.25 1631.75
 1748.25 1751.75  1818.5  1821.5  1821.5  1888.5  1891.5  1958.5  1961.5  2028.5
  2031.5  2098.5  2101.5  2168.5  2171.5  2238.5  2241.5  2308.5  2311.5  2378.5
  2381.5  2448.5  2451.5    2513
   440.6 440.698 440.702 440.798 440.802 440.898 440.902 440.998 441.002 441.098
 441.102 441.198 441.202 441.298 441.302 441.398   441.4   441.4   441.4   441.4
   441.4   441.4   441.4   441.4   441.4 441.402 441.396 441.204 441.198 441.102
 441.098 441.002 440.998 440.902 440.896 440.704 440.699 440.651 440.649 440.601
 440.598 440.502   440.5   440.5
   434.6 434.698 434.702 434.798 434.802 434.898 434.902 434.998 435.002 435.098
 435.102 435.198 435.202 435.298 435.302 435.398   435.4   434.5   434.5   434.5
   434.5   434.5   434.5  434.52   435.5 435.402 435.396 435.204 435.198 435.102
 435.098 435.002 434.998 434.902 434.896 434.704 434.699 434.651 434.649 434.601
 434.598 434.502   434.5   434.5
Pier Skew, UpSta & Num, DnSta & Num=  ,1070, 2 ,1070, 2 , 0 , 0 , 0 ,,
       3       3
       0     440
       3       3
       0     440
Pier Skew, UpSta & Num, DnSta & Num=  ,1140, 2 ,1140, 2 , 0 , 0 , 0 ,,
       3       3
       0     440
       3       3
       0     440
Pier Skew, UpSta & Num, DnSta & Num=  ,1210, 2 ,1210, 2 , 0 , 0 , 0 ,,
       3       3
       0     440
       3       3
       0     440
Pier Skew, UpSta & Num, DnSta & Num=  ,1280, 2 ,1280, 2 , 0 , 0 , 0 ,,
       3       3
       0     440
       3       3
       0     440
Pier Skew, UpSta & Num, DnSta & Num=  ,1350, 2 ,1350, 2 , 0 , 0 , 0 ,,
       3       3
       0     440
       3       3
       0     440
Pier Skew, UpSta & Num, DnSta & Num=  ,1420, 2 ,1420, 2 , 0 , 0 , 0 ,,
       3       3
       0     440
       3       3
       0     440
Pier Skew, UpSta & Num, DnSta & Num=  ,1490, 2 ,1490, 2 , 0 , 0 , 0 ,,
       3       3
       0     440
       3       3
       0     440
Pier Skew, UpSta & Num, DnSta & Num=  ,1560, 2 ,1560, 2 , 0 , 0 , 0 ,,
       3       3
       0     440
       3       3
       0     440
Pier Skew, UpSta & Num, DnSta & Num=  ,1630, 2 ,1630, 2 , 0 , 0 , 0 ,,
       3       3
       0     440
       3       3
       0     440
Pier Skew, UpSta & Num, DnSta & Num=  ,1750, 2 ,1750, 2 , 0 , 0 , 0 ,,
       3       3
       0     440
       3       3
       0     440
Pier Skew, UpSta & Num, DnSta & Num=  ,1820, 2 ,1820, 2 , 0 , 0 , 0 ,,
       3       3
       0     440
       3       3
       0     440
Pier Skew, UpSta & Num, DnSta & Num=  ,1890, 2 ,1890, 2 , 0 , 0 , 0 ,,
       3       3
       0     440
       3       3
       0     440
Pier Skew, UpSta & Num, DnSta & Num=  ,1960, 2 ,1960, 2 , 0 , 0 , 0 ,,
       3       3
       0     440
       3       3
       0     440
Pier Skew, UpSta & Num, DnSta & Num=  ,2030, 2 ,2030, 2 , 0 , 0 , 0 ,,
       3       3
       0     440
       3       3
       0     440
Pier Skew, UpSta & Num, DnSta & Num=  ,2100, 2 ,2100, 2 , 0 , 0 , 0 ,,
       3       3
       0     440
       3       3
       0     440
Pier Skew, UpSta & Num, DnSta & Num=  ,2170, 2 ,2170, 2 , 0 , 0 , 0 ,,
       3       3
       0     440
       3       3
       0     440
Pier Skew, UpSta & Num, DnSta & Num=  ,2240, 2 ,2240, 2 , 0 , 0 , 0 ,,
       3       3
       0     440
       3       3
       0     440
Pier Skew, UpSta & Num, DnSta & Num=  ,2310, 2 ,2310, 2 , 0 , 0 , 0 ,,
       3       3
       0     440
       3       3
       0     440
Pier Skew, UpSta & Num, DnSta & Num=  ,2380, 2 ,2380, 2 , 0 , 0 , 0 ,,
       3       3
       3     440
       3       3
       3     440
Pier Skew, UpSta & Num, DnSta & Num=  ,2450, 2 ,2450, 2 , 0 , 0 , 0 ,,
       3       3
       3     440
       3       3
       3     440
BR Coef= 1 , 0 , 0 ,1.05, 0 ,,,0.8,-1,0.5,1,
WSPro=,,,, 1 ,,,, 0 ,,,, 0 ,,,,-1 ,-1 ,-1 , 0 , 0 , 0 , 0 , 0
BC Design=,, 0 ,, 0 ,,,,,,
BC HTab HWMax=434.6
BC Use User HTab Curves=0
BC User HTab FreeFlow(D)= 0

Type RM Length L Ch R = 1 ,4789    ,1,1,1
BEGIN DESCRIPTION:
This cross section corresponds to cross section 4760 of the non-georeferenced CDC model which was the source of this model.
END DESCRIPTION:
XS GIS Cut Line= 3
  2458876.860493 6980928.6740532  2458155.764167  6980970.027317
 2457366.0223082 6981009.3195612
#Sta/Elev= 30
    1000   434.6    1000   429.5  1071.5     420    1073     420    1114   413.9
  1141.5   410.9  1278.5 409.022    1353   409.5    1563     409 1599.77 406.469
    1644   403.9    1674   396.9    1681   396.4    1702   387.2    1720   384.7
    1738   385.5    1743   389.2    1756   391.6    1775   398.3    1818   407.8
    1871   409.1  1888.5 408.375  1958.5  409.28  2028.5 409.496    2243   409.8
    2313     409  2378.5 410.369    2463   410.9    2513   429.5    2513   434.5
#Mann= 5 ,-1,0
    1000     .03       0  1141.5     .07       0 1599.77    .035       0
    1818     .07       0    2463     .03       0
Bank Sta=1644,1818
XS Rating Curve= 0 ,0
Exp/Cntr=0.5,0.3

Type RM Length L Ch R = 1 ,4788    ,109,109,109
BEGIN DESCRIPTION:
This cross section corresponds to cross section 4759 of the non-georeferenced CDC model which was the source of this model.
END DESCRIPTION:
XS GIS Cut Line= 4
2458926.217350516980923.890270132458155.827815186980969.03191213
2457350.472470496981007.818908052454999.197799566981121.05945667
#Sta/Elev= 30
    1002   439.7    1060   424.1    1114   413.9    1155   410.9    1283     409
    1604   409.1    1686   403.9    1723   396.4    1744   387.2    1772  384.66
    1790   385.5    1805   389.2    1825   398.3    1868   407.8    2065   409.7
    2331   408.3    2360   410.5    2836   412.7    3007   411.4    3574   413.7
    3760   417.3    3961   425.5    4056     432    4090   430.8    4161   433.9
    4410   436.2    4540   433.3    4605   439.9    4659   439.6    4934   453.8
#Mann= 4 ,-1,0
    1002     .03       0    1155     .07       0    1604    .035       0
    1868    .055       0
Bank Sta=1604,1868
XS Rating Curve= 0 ,0
Exp/Cntr=0.3,0.1

Type RM Length L Ch R = 1 ,4679    ,400,577,750
BEGIN DESCRIPTION:
This cross section corresponds to cross section 4653 of the non-georeferenced CDC model which was the source of this model.
END DESCRIPTION:
XS GIS Cut Line= 6
  2458949.899717 6980819.7608852 2456986.8918328 6980921.9929642
 2456359.0220256 6980863.5859288  2455993.981089 6980834.3832313
 2455716.5498853 6980863.5859288 2455038.4892336 6980994.4856014
#Sta/Elev= 30
    1002   439.7    1060   424.1    1114   413.9    1155   410.9    1283     409
    1604   409.1    1686   403.9    1723   396.4    1744   387.2    1772  384.66
    1790   385.5    1805   389.2    1825   398.3    1868   407.8    2065   409.7
    2331   408.3    2360   410.5    2836   412.7    3007   411.4    3574   413.7
    3760   417.3    3961   425.5    4056     432    4090   430.8    4161   433.9
    4410   436.2    4540   433.3    4605   439.9    4659   439.6    4934   453.8
#Mann= 4 ,-1,0
    1002     .03       0    1155     .07       0    1604    .035       0
    1868    .055       0
Bank Sta=1604,1868
XS Rating Curve= 0 ,0
Exp/Cntr=0.3,0.1

Type RM Length L Ch R = 1 ,4102    ,649,780,899
BEGIN DESCRIPTION:
This cross section corresponds to cross section 4076 of the non-georeferenced CDC model which was the source of this model.
END DESCRIPTION:
XS GIS Cut Line= 3
     2458989.484      6980666.39     2458129.345     6980192.919
     2456366.582     6979723.647
#Sta/Elev= 30
    1004   439.9    1045   424.1    1086   411.9    1117   409.3    1338   407.9
    1525     409    1600   406.9    1635   403.9    1672   396.4    1699   387.2
    1727   384.7    1745   385.5    1774   391.6    1793   398.3    1836   407.8
    1849   407.1    1890   409.1    2433   411.3    2511   410.4    2550     408
    2567   410.1    2808   410.6    3022   408.3    3420   426.9    3431   427.8
    3459   435.1    3563   443.5    3624     451    3754   459.3    3810   460.3
#Mann= 4 ,-1,0
    1004     .03       0    1117     .07       0    1600    .035       0
    1849    .055       0
#XS Ineff= 3 ,-1
    1004    1600   406.9    1849    2830   407.1    2830    3810   460.3
Permanent Ineff=
       F       F       F
Bank Sta=1600,1849
XS Rating Curve= 0 ,0
Exp/Cntr=0.3,0.1

Type RM Length L Ch R = 1 ,3322    ,111,111,111
BEGIN DESCRIPTION:
This cross section corresponds to cross section 3295 of the non-georeferenced CDC model which was the source of this model.
END DESCRIPTION:
XS GIS Cut Line= 3
  2459323.422264 6980282.2186532 2458096.3180917 6978935.6580261
  2457835.823862 6978721.5636381
#Sta/Elev= 30
    1005   438.1    1023   433.1    1038     432    1099   411.7    1215   409.2
    1358   408.8    1499   410.9    1784   410.8    1816   397.5    1916   383.9
    1932     384    1957   398.4    1984   406.2    1993   406.5    2023   394.4
    2039   396.6    2053   394.9    2069   398.3    2095   399.4    2115     396
    2125   397.5    2138   404.7    2154   408.9    2220   407.4    2563   412.4
    2627     415    2757   425.2    2838   428.1    2898     445    3164   453.3
#Mann= 4 ,-1,0
    1005     .03       0    1099     .07       0    1784    .035       0
    1984    .055       0
#Block Obstruct= 2 , 0
                            1993           406.5
Bank Sta=1784,1984
XS Rating Curve= 0 ,0
Exp/Cntr=0.3,0.1

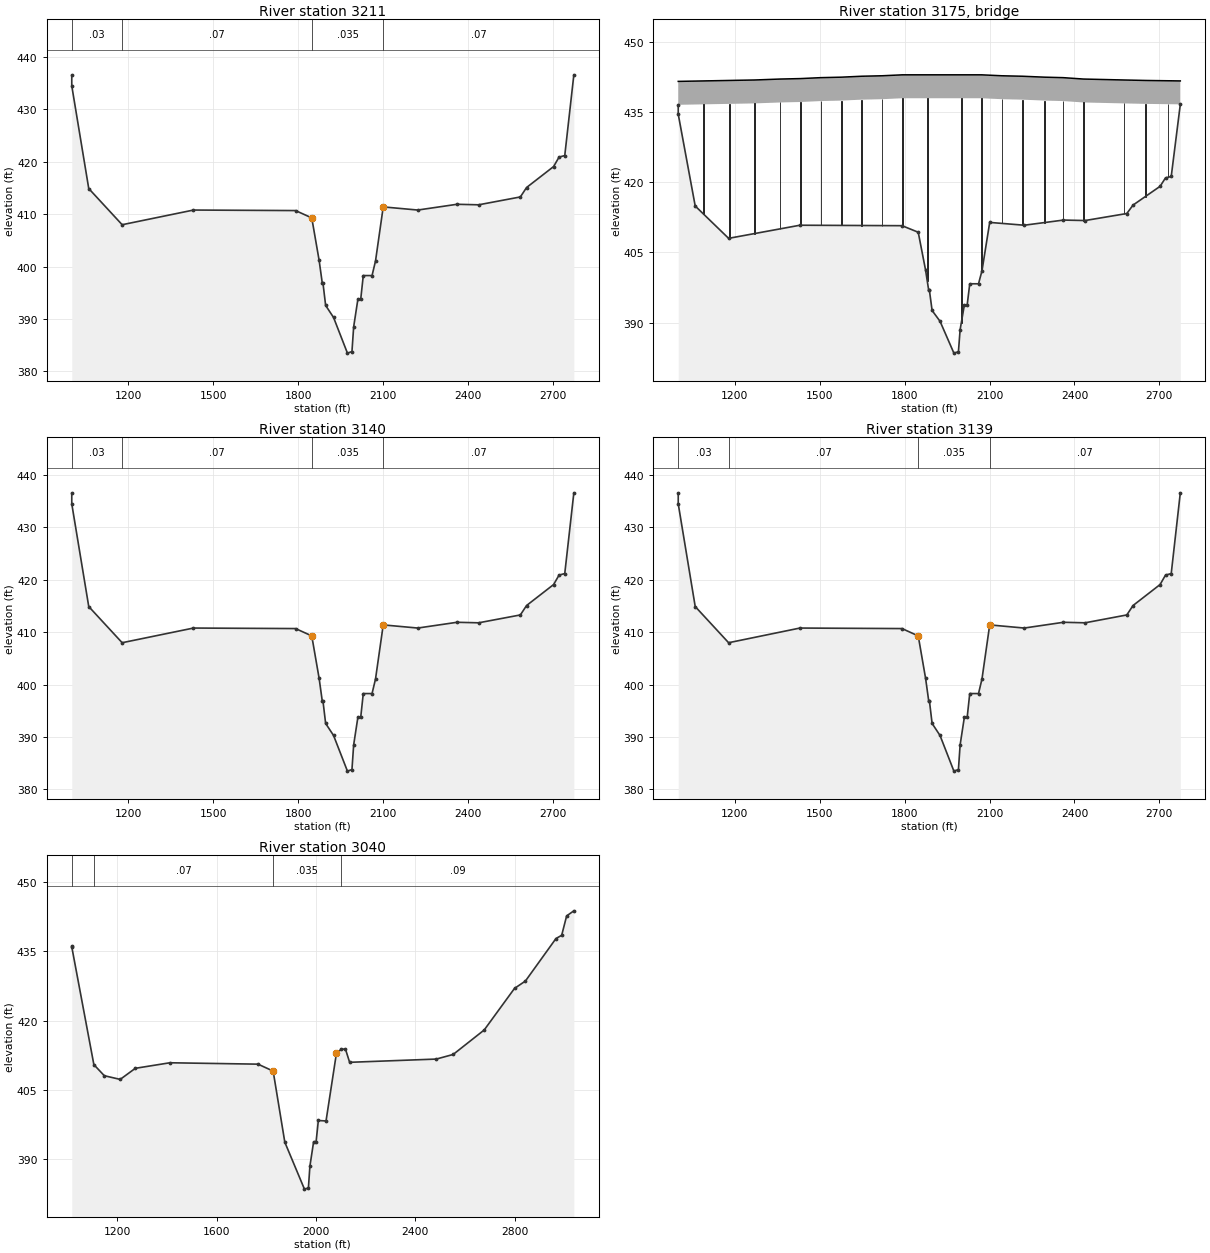
Type RM Length L Ch R = 1 ,3211    ,71,71,71
BEGIN DESCRIPTION:
This cross section corresponds to cross section 3190 of the non-georeferenced CDC model which was the source of this model.
END DESCRIPTION:
XS GIS Cut Line= 3
2459425.753424916980231.53830838 2458789.85541856979535.99278347
2458230.308309266978920.82012931
#Sta/Elev= 30
    1000   436.5    1000   434.5    1060   414.9    1178     408    1430   410.8
 1790.75   410.7    1848   409.3    1874   401.2    1885   396.9  1887.5   396.9
    1897   392.6    1925   390.3    1974   383.5    1990   383.8    1996   388.5
    2011   393.8    2021   393.8    2030   398.3    2061   398.3 2073.25 401.084
  2100.5   411.4  2222.5   410.8 2361.25   411.9  2437.5   411.8    2585   413.3
    2607   415.1  2702.5   419.1  2721.7   420.9  2741.9   421.2    2774   436.6
#Mann= 4 ,-1,0
    1000     .03       0    1178     .07       0    1848    .035       0
  2100.5     .07       0
Bank Sta=1848,2100.5
XS Rating Curve= 0 ,0
Exp/Cntr=0.5,0.3

Type RM Length L Ch R = 3 ,3175    ,,,
BEGIN DESCRIPTION:
Shady Grove Road
END DESCRIPTION:
Node Name=Shady Grove Road
Bridge Culvert--1,0,-1,-1, 0
Deck Dist Width WeirC Skew NumUp NumDn MinLoCord MaxHiCord MaxSubmerge Is_Ogee
2,68,2.6,0, 46, 46, , , 0.95, 0, ,,,
    1000  1088.5 1088.75 1091.25  1091.5 1178.75 1181.25 1268.75 1271.25 1358.75
 1361.25 1430.75 1433.25 1502.75 1505.25 1574.75 1577.25 1646.75 1649.25 1718.75
 1721.25 1790.75 1793.25 1878.75 1881.25 1998.75 2001.25 2070.75 2073.25 2142.75
 2145.25 2214.75 2217.25 2293.75 2296.25 2358.75 2361.25 2430.75 2433.25 2573.75
 2576.25 2648.75 2651.25 2728.75 2731.25    2774
   441.5 441.598 441.599 441.601 441.602 441.699 441.701 441.799 441.803 441.997
 442.002 442.098 442.103 442.297 442.302 442.398 442.404 442.596 442.602 442.698
 442.703 442.897   442.9   442.9   442.9   442.9   442.9   442.9 442.897 442.703
 442.698 442.602 442.597 442.403 442.398 442.302 442.295 442.005 441.998 441.802
 441.798 441.702 441.698 441.636 441.634   441.6
   436.5 436.598 436.599 436.601 436.602 436.699 436.701 436.799 436.803 436.997
 437.002 437.098 437.103 437.297 437.302 437.398 437.404 437.596 437.602 437.698
 437.703 437.897   437.9   437.9   437.9   437.9   437.9   437.9 437.897 437.703
 437.698 437.602 437.597 437.403 437.398 437.302 437.295 437.005 436.998 436.802
 436.798 436.702 436.698 436.636 436.634   436.6
    1000  1088.5 1088.75 1091.25  1091.5 1178.75 1181.25 1268.75 1271.25 1358.75
 1361.25 1430.75 1433.25 1502.75 1505.25 1574.75 1577.25 1646.75 1649.25 1718.75
 1721.25 1790.75 1793.25 1878.75 1881.25 1998.75 2001.25 2070.75 2073.25 2142.75
 2145.25 2214.75 2217.25 2293.75 2296.25 2358.75 2361.25 2430.75 2433.25 2573.75
 2576.25 2648.75 2651.25 2728.75 2731.25    2774
   441.5 441.598 441.599 441.601 441.602 441.699 441.701 441.799 441.803 441.997
 442.002 442.098 442.103 442.297 442.302 442.398 442.404 442.596 442.602 442.698
 442.703 442.897   442.9   442.9   442.9   442.9   442.9   442.9 442.897 442.703
 442.698 442.602 442.597 442.403 442.398 442.302 442.295 442.005 441.998 441.802
 441.798 441.702 441.698 441.636 441.634   441.6
   436.5 436.598 436.599 436.601 436.602 436.699 436.701 436.799 436.803 436.997
 437.002 437.098 437.103 437.297 437.302 437.398 437.404 437.596 437.602 437.698
 437.703 437.897   437.9   437.9   437.9   437.9   437.9   437.9 437.897 437.703
 437.698 437.602 437.597 437.403 437.398 437.302 437.295 437.005 436.998 436.802
 436.798 436.702 436.698 436.636 436.634   436.6
Pier Skew, UpSta & Num, DnSta & Num=  ,1090, 2 ,1090, 2 , 0 , 0 , 0 ,,
     2.5     2.5
       0     440
     2.5     2.5
       0     440
Pier Skew, UpSta & Num, DnSta & Num=  ,1180, 2 ,1180, 2 , 0 , 0 , 0 ,,
     2.5     2.5
       0     440
     2.5     2.5
       0     440
Pier Skew, UpSta & Num, DnSta & Num=  ,1270, 2 ,1270, 2 , 0 , 0 , 0 ,,
     2.5     2.5
       0     440
     2.5     2.5
       0     440
Pier Skew, UpSta & Num, DnSta & Num=  ,1360, 2 ,1360, 2 , 0 , 0 , 0 ,,
     2.5     2.5
       0     440
     2.5     2.5
       0     440
Pier Skew, UpSta & Num, DnSta & Num=  ,1432, 2 ,1432, 2 , 0 , 0 , 0 ,,
     2.5     2.5
       0     440
     2.5     2.5
       0     440
Pier Skew, UpSta & Num, DnSta & Num=  ,1504, 2 ,1504, 2 , 0 , 0 , 0 ,,
     2.5     2.5
       0     440
     2.5     2.5
       0     440
Pier Skew, UpSta & Num, DnSta & Num=  ,1576, 2 ,1576, 2 , 0 , 0 , 0 ,,
     2.5     2.5
       0     440
     2.5     2.5
       0     440
Pier Skew, UpSta & Num, DnSta & Num=  ,1648, 2 ,1648, 2 , 0 , 0 , 0 ,,
     2.5     2.5
       0     440
     2.5     2.5
       0     440
Pier Skew, UpSta & Num, DnSta & Num=  ,1720, 2 ,1720, 2 , 0 , 0 , 0 ,,
     2.5     2.5
       0     440
     2.5     2.5
       0     440
Pier Skew, UpSta & Num, DnSta & Num=  ,1792, 2 ,1792, 2 , 0 , 0 , 0 ,,
     2.5     2.5
       0     440
     2.5     2.5
       0     440
Pier Skew, UpSta & Num, DnSta & Num=  ,1880, 2 ,1880, 2 , 0 , 0 , 0 ,,
     2.5     2.5
       0     440
     2.5     2.5
       0     440
Pier Skew, UpSta & Num, DnSta & Num=  ,2000, 2 ,2000, 2 , 0 , 0 , 0 ,,
     2.5     2.5
       0     440
     2.5     2.5
       0     440
Pier Skew, UpSta & Num, DnSta & Num=  ,2072, 2 ,2072, 2 , 0 , 0 , 0 ,,
     2.5     2.5
       0     440
     2.5     2.5
       0     440
Pier Skew, UpSta & Num, DnSta & Num=  ,2144, 2 ,2144, 2 , 0 , 0 , 0 ,,
     2.5     2.5
       0     440
     2.5     2.5
       0     440
Pier Skew, UpSta & Num, DnSta & Num=  ,2216, 2 ,2216, 2 , 0 , 0 , 0 ,,
     2.5     2.5
       0     440
     2.5     2.5
       0     440
Pier Skew, UpSta & Num, DnSta & Num=  ,2295, 2 ,2295, 2 , 0 , 0 , 0 ,,
     2.5     2.5
       0     440
     2.5     2.5
       0     440
Pier Skew, UpSta & Num, DnSta & Num=  ,2360, 2 ,2360, 2 , 0 , 0 , 0 ,,
     2.5     2.5
       0     440
     2.5     2.5
       0     440
Pier Skew, UpSta & Num, DnSta & Num=  ,2432, 2 ,2432, 2 , 0 , 0 , 0 ,,
     2.5     2.5
       0     440
     2.5     2.5
       0     440
Pier Skew, UpSta & Num, DnSta & Num=  ,2575, 2 ,2575, 2 , 0 , 0 , 0 ,,
     2.5     2.5
       0     440
     2.5     2.5
       0     440
Pier Skew, UpSta & Num, DnSta & Num=  ,2650, 2 ,2650, 2 , 0 , 0 , 0 ,,
     2.5     2.5
       0     440
     2.5     2.5
       0     440
Pier Skew, UpSta & Num, DnSta & Num=  ,2730, 2 ,2730, 2 , 0 , 0 , 0 ,,
     2.5     2.5
       0     440
     2.5     2.5
       0     440
BR Coef= 1 , 0 , 0 ,1.05, 0 ,,,0.8,-1,0.5,1,
WSPro=,,,, 1 ,,,, 0 ,,,, 0 ,,,,-1 ,-1 ,-1 , 0 , 0 , 0 , 0 , 0
BC Design=,, 0 ,, 0 ,,,,,,
BC HTab HWMax=436.6
BC Use User HTab Curves=0
BC User HTab FreeFlow(D)= 0

Type RM Length L Ch R = 1 ,3140    ,1,1,1
BEGIN DESCRIPTION:
This cross section corresponds to cross section 3119 of the non-georeferenced CDC model which was the source of this model.
END DESCRIPTION:
XS GIS Cut Line= 3
2459466.637857596980178.474438132458826.652588996979475.10839079
2458275.535909096978863.81269738
#Sta/Elev= 30
    1000   436.5    1000   434.5    1060   414.9    1178     408    1430   410.8
 1790.75   410.7    1848   409.3    1874   401.2    1885   396.9  1887.5   396.9
    1897   392.6    1925   390.3    1974   383.5    1990   383.8    1996   388.5
    2011   393.8    2021   393.8    2030   398.3    2061   398.3 2073.25 401.084
  2100.5   411.4  2222.5   410.8 2361.25   411.9  2437.5   411.8    2585   413.3
    2607   415.1  2702.5   419.1  2721.7   420.9  2741.9   421.2    2774   436.6
#Mann= 4 ,-1,0
    1000     .03       0    1178     .07       0    1848    .035       0
  2100.5     .07       0
Bank Sta=1848,2100.5
XS Rating Curve= 0 ,0
Exp/Cntr=0.5,0.3

Type RM Length L Ch R = 1 ,3139    ,99,99,99
BEGIN DESCRIPTION:
This cross section corresponds to cross section 3118 of the non-georeferenced CDC model which was the source of this model.
END DESCRIPTION:
XS GIS Cut Line= 3
2459467.939364176980177.220831722458827.149635266979474.23831379
2458276.238335526978863.11223947
#Sta/Elev= 30
    1000   436.5    1000   434.5    1060   414.9    1178     408    1430   410.8
 1790.75   410.7    1848   409.3    1874   401.2    1885   396.9  1887.5   396.9
    1897   392.6    1925   390.3    1974   383.5    1990   383.8    1996   388.5
    2011   393.8    2021   393.8    2030   398.3    2061   398.3 2073.25 401.084
  2100.5   411.4  2222.5   410.8 2361.25   411.9  2437.5   411.8    2585   413.3
    2607   415.1  2702.5   419.1  2721.7   420.9  2741.9   421.2    2774   436.6
#Mann= 4 ,-1,0
    1000     .03       0    1178     .07       0    1848    .035       0
  2100.5     .07       0
Bank Sta=1848,2100.5
XS Rating Curve= 0 ,0
Exp/Cntr=0.3,0.1

Type RM Length L Ch R = 1 ,3040    ,0,0,0
BEGIN DESCRIPTION:
This cross section corresponds to cross section 3013 of the non-georeferenced CDC model which was the source of this model.
END DESCRIPTION:
XS GIS Cut Line= 3
  2459501.030505 6980073.9300278 2458285.6090517 6978741.9130068
 2458116.6218568 6978602.9234554
#Sta/Elev= 30
    1017   436.1    1017     436    1106   410.5    1148   408.1    1212   407.3
    1273   409.7    1412   410.9    1767   410.6    1828   409.1    1875   393.7
    1954  383.54    1970   383.8    1976   388.5    1991   393.8    2001   393.8
    2010   398.4    2041   398.3    2083     413    2102   413.8    2119   413.9
    2136     411    2485   411.7    2553   412.7    2678     418    2800     427
    2844   428.6    2967   437.8    2990   438.5    3010   442.7    3039   443.8
#Mann= 4 ,-1,0
    1017     .03       0    1106     .07       0    1828    .035       0
    2102     .09       0
Bank Sta=1828,2083
XS Rating Curve= 0 ,0
Exp/Cntr=0.3,0.1

River Reach=West Fork       ,wf
Reach XY= 30
       2346473.9        6963584.      2346286.59      6968259.29
       2354512.4      6965894.36      2359871.65      6970041.49
      2365532.14      6970407.58      2367619.48       6974853.9
      2381458.46      6966394.67      2382440.84      6968870.18
       2385600.2      6969508.62      2385877.69      6972305.46
      2387730.11       6971519.9      2387123.85      6974369.92
      2389517.29      6975915.22      2397024.23      6975004.71
      2396328.62      6973598.51      2402295.53       6972489.5
       2403920.5      6970193.02      2409720.17      6975714.25
      2410027.07      6979946.39      2412459.53      6982607.21
      2417785.24      6979460.17       2418378.9      6973023.19
      2423274.88      6971824.69      2428119.37      6964022.21
      2435982.11      6962862.51      2443411.24      6969635.42
      2444209.34      6968225.94      2455794.74      6971975.24
       2457790.9      6976586.85       2460651.9      6977070.51