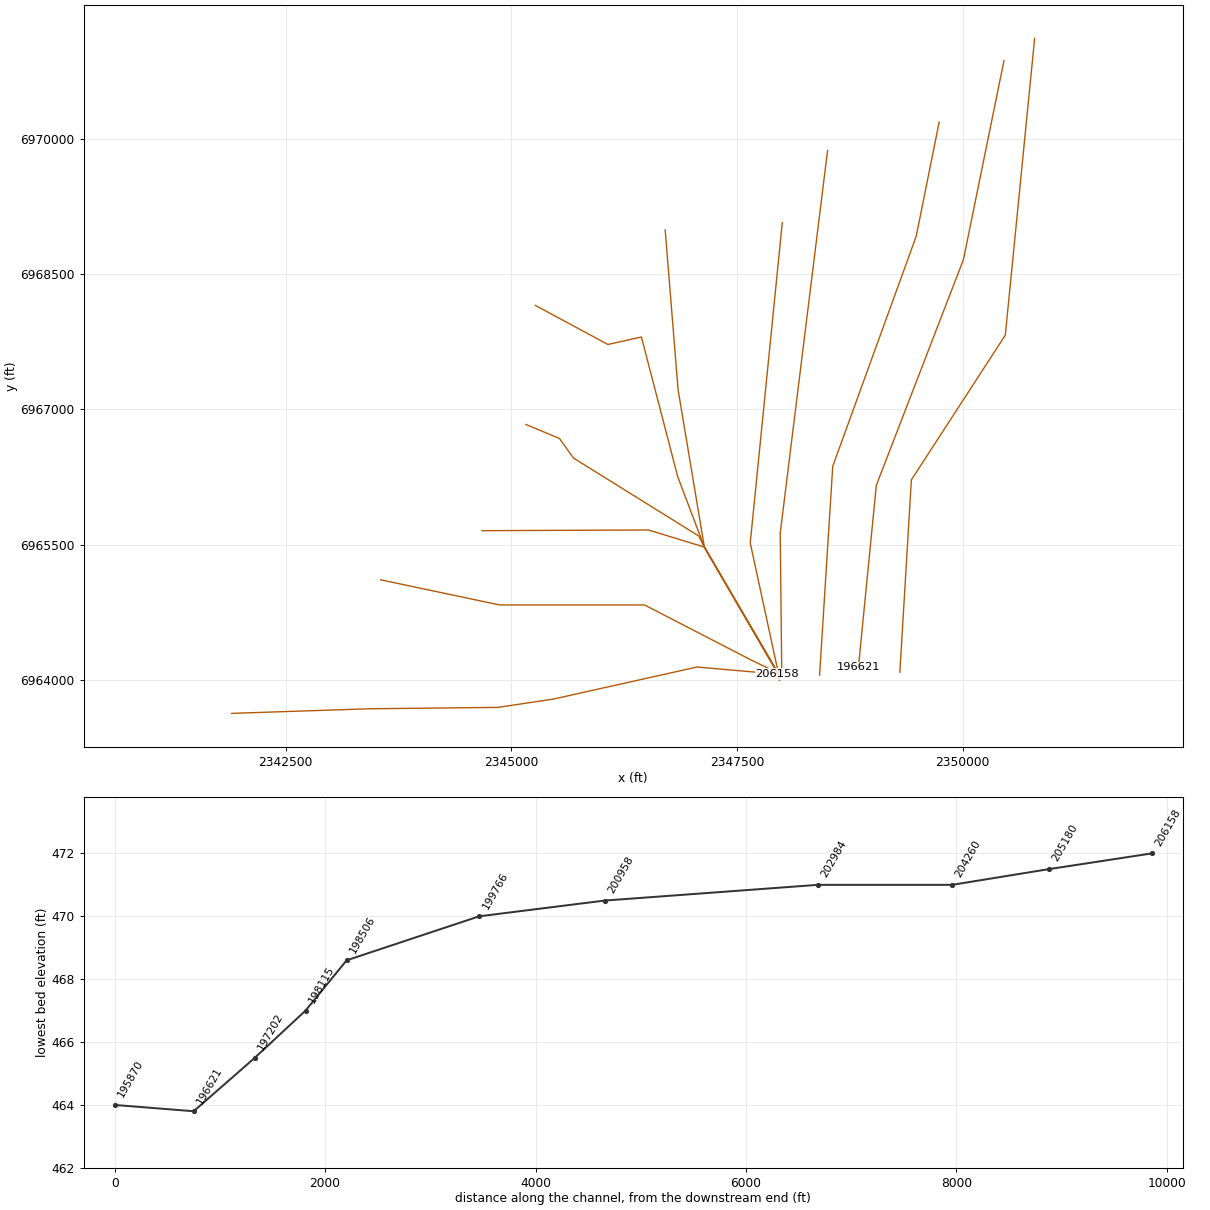
HEC-RAS study CDC_Consolidated_Model.prj: Upper Trinity CDC Consolidated Model

--- CDC_Consolidated_Model.g02 (geometry) --- (continued)

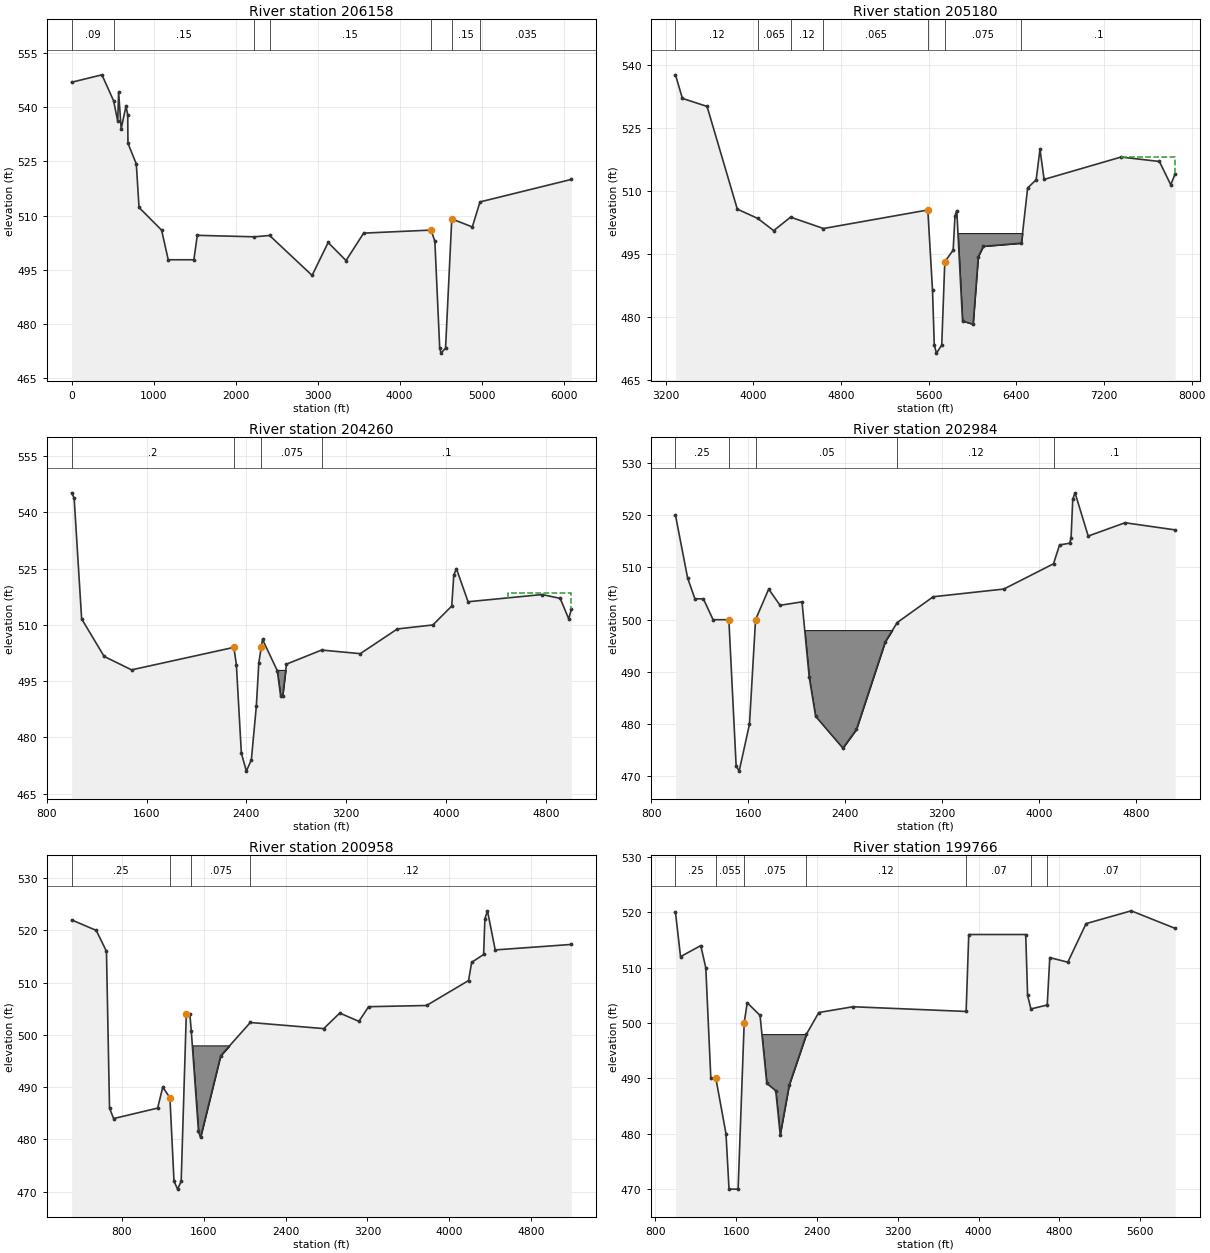
Type RM Length L Ch R = 1 ,206158  ,1071,978,460
BEGIN DESCRIPTION:
This cross section corresponds to cross section 206218 of the non-georeferenced CDC model which was the source of this model.
Downstream of East 1st Street.
END DESCRIPTION:
XS GIS Cut Line= 6
  2341904.095961 6963632.5437376   2343430.68391   6963683.60684
     2344852.789   6963698.88109   2345465.41508   6963790.52001
   2347058.22685   6964146.11608      2347944.51      6964068.28
#Sta/Elev= 30
       0  546.85  369.23   548.9  512.04  541.71  562.18  536.03  572.53  544.23
  603.81  533.98  663.08  540.28  684.12  537.77  686.41     530  788.51  524.26
  821.63  512.25 1096.67     506  1177.8   497.8 1490.48   497.8  1532.1  504.55
 2227.97  504.14 2413.28  504.51 2932.16  493.48 3128.06  502.57 3345.99  497.58
 3560.99  505.16 4383.29     506 4429.29  502.89 4488.22  473.47 4503.96     472
 4559.71  473.37 4635.51  509.09 4886.06  506.87 4979.55  513.78  6093.5     520
#Mann= 7 ,-1,0
       0     .09       0  512.04     .15       0 2227.97     .06       0
 2413.28     .15       0 4383.29    .066       0 4635.51     .15       0
 4979.55    .035       0
Bank Sta=4383.29,4635.51
XS Rating Curve= 0 ,0
Exp/Cntr=0.3,0.1

Type RM Length L Ch R = 1 ,205180  ,800,920,900
BEGIN DESCRIPTION:
This cross section corresponds to cross section 205240 of the non-georeferenced CDC model which was the source of this model.
ROB updated with 2009 TNRIS LiDAR
END DESCRIPTION:
XS GIS Cut Line= 6
2343553.770143826965112.22718057   2344871.03011      6964833.93
   2346477.14501      6964833.93 2347670.1078499 6964217.5993343
     2347947.246     6964085.0922347968.191686126964001.06927625
#Sta/Elev= 30
    3291   537.6    3354     532    3579   530.1    3855   505.7    4041   503.5
    4187   500.6    4341   503.8    4641   501.1    5593   505.5    5636   486.4
    5652   473.4    5672   471.5    5720   473.4    5748   493.2 5824.32  495.96
 5840.89  504.11  5857.3  505.35 5909.68  479.13 6006.13  478.36  6053.3  494.42
  6099.2  496.87 6447.21  497.62 6503.68  510.73 6581.57  512.68 6616.27  519.92
 6653.93  512.76  7355.7  518.07 7705.91  517.02 7809.26  511.48 7849.67  514.11
#Mann= 7 ,-1,0
    3291     .12       0    4041    .065       0    4341     .12       0
    4641    .065       0    5593    .055       0    5748    .075       0
 6447.21      .1       0
#XS Ineff= 3 ,-1
    3291    5593   505.5    5748 7358.97   493.2 7358.97 7849.67  518.05
Permanent Ineff=
       F       F       F
#Block Obstruct= 1 ,-1
 5861.35 6480.54     500
Bank Sta=5593,5748
XS Rating Curve= 0 ,0
Exp/Cntr=0.3,0.1

Type RM Length L Ch R = 1 ,204260  ,1000,1276,200
BEGIN DESCRIPTION:
This cross section corresponds to cross section 204336 of the non-georeferenced CDC model which was the source of this model.
ROB updated with Halff Survey & 2009 TNRIS LiDAR
END DESCRIPTION:
XS GIS Cut Line= 6
     2344675.495     6965656.765     2344766.751     6965657.144
     2346520.754     6965664.422     2347139.385     6965475.194
 2347946.74364766964085.956933832347946.994879386964085.52463464
#Sta/Elev= 30
    1000   545.2    1020   543.8    1080   511.6    1260   501.6    1480     498
    2300     504    2320   499.4    2360   475.8    2400     471    2440     474
    2480   488.3    2500   499.9    2520   504.1 2529.47  506.11 2647.55  497.81
  2674.9     491 2690.71     491 2721.35  499.52 3002.93  503.28 3313.06  502.32
 3610.27  508.91 3894.45  509.97 4045.89  515.01 4062.53  523.31 4083.48  524.97
 4176.83  516.16 4770.05  518.08 4914.96  517.06 4983.21  511.61 5004.37   514.1
#Mann= 4 ,-1,0
    1000      .2       0    2300    .055       0    2520    .075       0
 3002.93      .1       0
#XS Ineff= 3 ,-1
    1000    2300     504    2520 4494.78   504.1 4494.78 5004.37  518.51
Permanent Ineff=
       F       F       F
#Block Obstruct= 1 ,-1
 2628.13 2742.16     498
Bank Sta=2300,2520
XS Rating Curve= 0 ,0
Exp/Cntr=0.3,0.1

Type RM Length L Ch R = 1 ,202984  ,1688,2026,226
BEGIN DESCRIPTION:
This cross section corresponds to cross section 203180 of the non-georeferenced CDC model which was the source of this model.
New XS from 99 topo, interpolated FL, ROB updated with Halff Survey & 2009 TNRIS LiDAR
END DESCRIPTION:
XS GIS Cut Line= 6
      2345163.49      6966832.88      2345534.79      6966678.18
      2345689.49      6966461.59      2347077.94      6965597.59
       2347139.5     6965475.2162347948.487997476964084.05120195
#Sta/Elev= 30
    1000     520    1100     508    1160     504    1230     504    1310     500
    1440     500    1500     472    1525     471    1610     480    1660     500
 1768.15  505.86 1861.89  502.76 2043.01  503.42 2102.64  488.94 2155.16   481.5
 2379.83  475.41 2491.72     479 2729.01  495.77 2828.13  499.46 3124.91   504.4
 3706.36  505.87 4116.31  510.71 4166.18  514.32 4248.99  514.65 4260.97  515.57
 4274.86  523.08 4293.79   524.3 4402.38  516.02 4705.99  518.57 5119.25   517.2
#Mann= 5 ,-1,0
    1000     .25       0    1440    .055       0    1660     .05       0
 2828.13     .12       0 4116.31      .1       0
#XS Ineff= 2 , 0
       0    1440     500 1768.15       0  505.86
Permanent Ineff=
       F       F
#Block Obstruct= 1 ,-1
    2040    2840     498
Bank Sta=1440,1660
XS Rating Curve= 0 ,0
Exp/Cntr=0.3,0.1

Type RM Length L Ch R = 1 ,200958  ,930,1192,380
BEGIN DESCRIPTION:
This cross section corresponds to cross section 201380 of the non-georeferenced CDC model which was the source of this model.
New XS from 99 topo, ROB updated with Halff Survey & 2009 TNRIS LiDAR
END DESCRIPTION:
XS GIS Cut Line= 6
      2345266.63      6968153.05       2346071.1      6967719.87
       2346442.4      6967802.38      2346844.64      6966255.32
      2347139.74      6965475.342347945.940442246964095.00547947
#Sta/Elev= 30
     310     522     550     520     650     516     680     486     720     484
    1150     486    1200     490    1270     488    1310     472    1345   470.5
    1380     472    1430     504 1464.58  504.03 1478.78  500.75  1549.1  481.54
 1568.96  480.38 1765.56     496 2055.38  502.38 2772.55  501.21 2929.15  504.18
 3116.13   502.6 3211.09   505.4 3777.11  505.63 4187.32   510.4 4217.82  513.88
 4334.55  515.39 4347.11  522.23 4372.27  523.74 4447.89  516.26 5191.53  517.31
#Mann= 4 ,-1,0
     310     .25       0    1270    .055       0 1478.78    .075       0
 2055.38     .12       0
#XS Ineff= 2 , 0
       0    1270     488    1430       0     504
Permanent Ineff=
       F       F
#Block Obstruct= 1 ,-1
    1450    1850     498
Bank Sta=1270,1430
XS Rating Curve= 0 ,0
Exp/Cntr=0.3,0.1

Type RM Length L Ch R = 1 ,199766  ,1454,1260,582
BEGIN DESCRIPTION:
This cross section corresponds to cross section 199650 of the non-georeferenced CDC model which was the source of this model.
New XS from 99 topo, ROB updated with Halff Survey & 2009 TNRIS LiDAR
END DESCRIPTION:
XS GIS Cut Line= 6
2346705.969551196968989.37062247     2346709.982     6968939.532
     2346848.265     6967221.919      2347139.86      6965475.38
     2347900.201     6964175.2772347925.442715766964132.11632553
#Sta/Elev= 30
    1000     520    1050     512    1250     514    1300     510    1350     490
    1400     490    1500     480    1530     470    1620     470    1680     500
 1710.03  503.67 1837.22  501.39 1903.67  489.13 1992.62  487.77 2036.58  479.85
 2125.81   488.8 2296.56     498 2419.07  501.91  2756.9  502.95 3877.32   502.1
 3903.31     516 4467.21     516 4485.82     505 4518.55  502.55 4680.23  503.27
 4705.46  511.83 4884.01     511  5064.8  517.97  5511.5  520.28 5946.79  517.11
#Mann= 7 ,-1,0
    1000     .25       0    1400    .055       0    1680    .075       0
 2296.56     .12       0 3877.32     .07       0 4518.55     .12       0
 4680.23     .07       0
#XS Ineff= 2 , 0
       0    1400     490 1710.03       0  503.67
Permanent Ineff=
       F       F
#Block Obstruct= 1 ,-1
 1837.06 2346.15     498
Bank Sta=1400,1680
XS Rating Curve= 0 ,0
Exp/Cntr=0.3,0.1

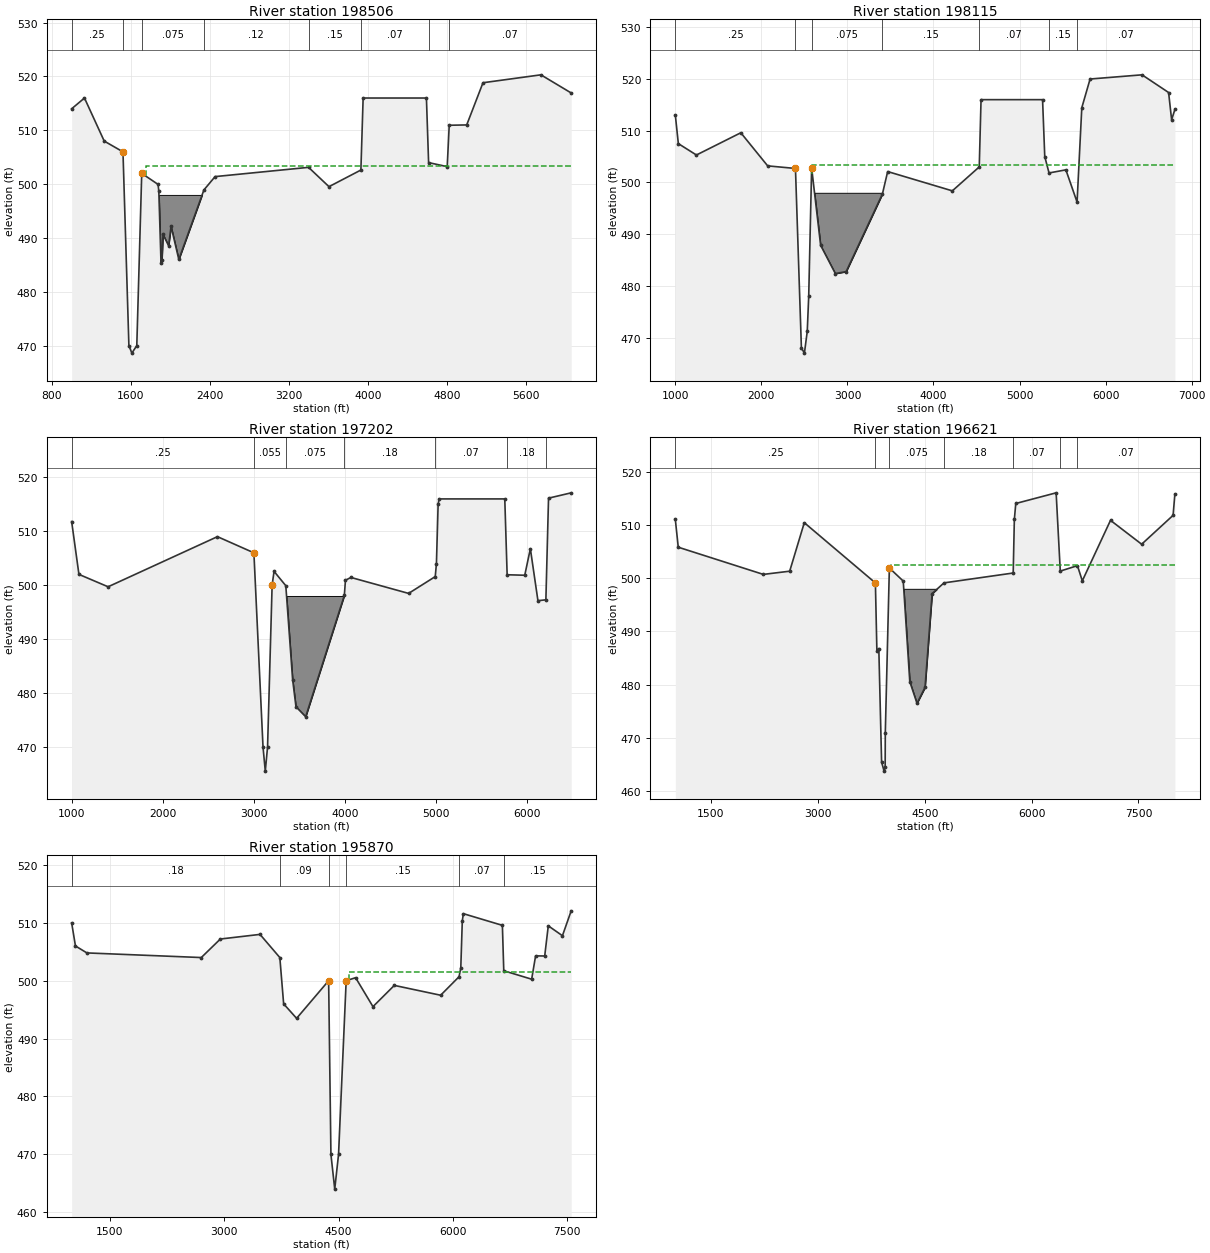
Type RM Length L Ch R = 1 ,198506  ,349,391,368
BEGIN DESCRIPTION:
This cross section corresponds to cross section 199000 of the non-georeferenced CDC model which was the source of this model.
ROB updated with Halff Survey & 2009 TNRIS LiDAR
END DESCRIPTION:
XS GIS Cut Line= 4
     2348003.085     6969069.651     2347648.191     6965520.706
     2347906.296     6964326.969     2347976.465     6964002.435
#Sta/Elev= 30
    1000     514    1130     516    1330     508    1520     506    1580     470
    1610   468.6    1660     470    1710     502 1875.43  499.95 1883.11  498.64
 1905.52   485.3 1914.73  485.94 1925.51  490.66 1982.34  488.55 2007.16  492.15
 2085.73     486 2339.86  498.92 2453.16   501.4  3399.9  503.12 3606.91  499.53
 3930.15  502.62 3952.88     516    4594     516 4616.11     504 4804.64  503.25
 4824.95  510.94  5002.2     511 5167.04  518.84 5753.77  520.31 6060.59  516.94
#Mann= 8 ,-1,0
    1000     .25       0    1520    .055       0    1710    .075       0
 2339.86     .12       0  3399.9     .15       0 3930.15     .07       0
 4616.11     .15       0 4824.95     .07       0
#XS Ineff= 2 , 0
       0    1520     506 1749.35       0  503.34
Permanent Ineff=
       F       F
#Block Obstruct= 1 ,-1
 1840.91 2392.05     498
Bank Sta=1520,1710
XS Rating Curve= 0 ,0
Exp/Cntr=0.3,0.1

Type RM Length L Ch R = 1 ,198115  ,536,482,386
BEGIN DESCRIPTION:
This cross section corresponds to cross section 198174 of the non-georeferenced CDC model which was the source of this model.
ROB updated with Halff Survey & 2009 TNRIS LiDAR
END DESCRIPTION:
XS GIS Cut Line= 4
      2348504.95     6969868.623     2348502.254     6969846.832
      2347980.22      6965626.85      2347997.38      6964089.91
#Sta/Elev= 30
    1000     513    1035   507.5    1245   505.3    1761   509.6    2073   503.2
    2396   502.7    2465     468    2500     467    2533   471.2    2550     478
    2584   502.8 2688.58  487.83 2859.56  482.38 2985.18  482.76 3406.38  497.76
 3467.49   502.1 4218.93  498.37 4531.75     503 4552.65     516 5267.57     516
    5293     505 5342.63  501.83 5538.47  502.43 5668.55   496.2 5723.42  514.44
 5819.85  519.99 6423.42   520.8 6732.17  517.38 6767.22  512.11 6805.11   514.1
#Mann= 7 ,-1,0
    1000     .25       0    2396    .055       0    2584    .075       0
 3406.38     .15       0 4531.75     .07       0 5342.63     .15       0
 5668.55     .07       0
#XS Ineff= 2 , 0
       0    2396   502.7 2592.56       0  503.36
Permanent Ineff=
       F       F
#Block Obstruct= 1 ,-1
 2602.27 3460.23     498
Bank Sta=2396,2584
XS Rating Curve= 0 ,0
Exp/Cntr=0.3,0.1

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
Type RM Length L Ch R = 1 ,197202  ,645,581,488
BEGIN DESCRIPTION:
This cross section corresponds to cross section 197450 of the non-georeferenced CDC model which was the source of this model.
New XS from 99 topo, interpolated FL, ROB updated with Halff Survey & 2009 TNRIS LiDAR
END DESCRIPTION:
XS GIS Cut Line= 5
   2349741.33176 6970183.8905078 2349487.1895125 6968919.0894779
 2348562.3127533 6966370.3012684 2348476.2778204 6965004.4949449
 2348416.5537532 6964056.3741531
#Sta/Elev= 30
    1000   511.8    1080     502    1400   499.7    2600     509    3000     506
    3100     470    3125   465.5    3150     470    3200     500  3221.2  502.56
 3350.16   499.9 3424.87  482.49 3461.66  477.45 3568.31   475.6 3992.64  498.11
 4004.66  500.91 4064.85  501.43  4697.8  498.47  4990.1  501.59 5003.08     504
 5021.71     515 5032.14     516 5753.18     516 5779.05  501.93 5972.35  501.84
 6033.88  506.77 6117.03  497.12 6204.19  497.28 6233.31  516.14 6481.95  517.13
#Mann= 7 ,-1,0
    1000     .25       0    3000    .055       0 3350.16    .075       0
 3992.64     .18       0  4990.1     .07       0 5779.05     .18       0
 6204.19     .07       0
#XS Ineff= 3 ,-1
    1000    3000     506  3221.2 6033.82  502.56 6033.82 6222.04  506.74
Permanent Ineff=
       F       F       T
#Block Obstruct= 1 ,-1
 3335.23 4034.09     498
Bank Sta=3000,3200
XS Rating Curve= 0 ,0
Exp/Cntr=0.3,0.1

Type RM Length L Ch R = 1 ,196621  ,551,751,451
BEGIN DESCRIPTION:
This cross section corresponds to cross section 196680 of the non-georeferenced CDC model which was the source of this model.
ROB updated with Halff Survey & 2009 TNRIS LiDAR
END DESCRIPTION:
XS GIS Cut Line= 4
   2350459.27714   6970863.80901   2350010.07593   6968659.57294
   2349045.13003   6966159.15996 2348846.7584696 6964144.5914655
#Sta/Elev= 30
    1000     511    1041   505.8    2235   500.7    2605   501.3    2810   510.4
    3808   499.1    3829   486.3    3856   486.8    3895   465.5    3930   463.8
    3945   464.5    3947     471    4004   501.9 4198.79  499.45 4290.71  480.59
 4391.66  476.52 4504.75  479.51 4604.34  497.11 4770.88  499.11 5742.08  500.96
 5758.21     511 5778.32     514 6344.68     516 6402.86  501.32 6643.71  502.34
 6712.02  499.49 7107.86  510.84 7544.96  506.36 7986.24  511.78  8011.3  515.76
#Mann= 7 ,-1,0
    1000     .25       0    3808    .055       0    4004    .075       0
 4770.88     .18       0 5742.08     .07       0 6402.86     .18       0
 6643.71     .07       0
#XS Ineff= 2 , 0
       0    3808   499.1 4030.27       0  502.37
Permanent Ineff=
       F       F
#Block Obstruct= 1 ,-1
 4166.67 4666.67     498
Bank Sta=3808,4004
XS Rating Curve= 0 ,0
Exp/Cntr=0.3,0.1

Type RM Length L Ch R = 1 ,195870  ,250,404,400
BEGIN DESCRIPTION:
This cross section corresponds to cross section 195930 of the non-georeferenced CDC model which was the source of this model.
ROB updated with Halff Survey & 2009 TNRIS LiDAR
END DESCRIPTION:
XS GIS Cut Line= 6
  2350799.201946 6971111.4184422 2350474.2049269 6967822.7110932
 2349433.4176384 6966219.7402178 2349358.1369491 6964961.4776425
 2349325.0781095 6964408.9229156 2349305.9669784 6964089.4941056
#Sta/Elev= 30
    1000     510    1050     506    1200   504.8    2700     504    2950   507.2
    3470     508    3730     504    3780     496    3950   493.5    4370     500
    4400     470    4450     464    4500     470    4600     500 4723.58  500.52
 4951.34  495.52 5231.25  499.19  5838.8  497.49 6080.13  500.69 6102.97  502.21
 6122.73  510.33 6136.62  511.58  6648.4  509.56 6666.56  501.72 7032.26  500.26
 7083.97  504.29  7203.4  504.27 7250.21  509.48 7435.83  507.77  7550.7  512.07
#Mann= 6 ,-1,0
    1000     .18       0    3730     .09       0    4370    .055       0
    4600     .15       0 6080.13     .07       0 6666.56     .15       0
#XS Ineff= 2 , 0
       0    4370     500 4643.21       0  501.49
Permanent Ineff=
       F       F
#Block Obstruct= 2 , 0
                            6100             508
Bank Sta=4370,4600
XS Rating Curve= 0 ,0
Exp/Cntr=0.3,0.1