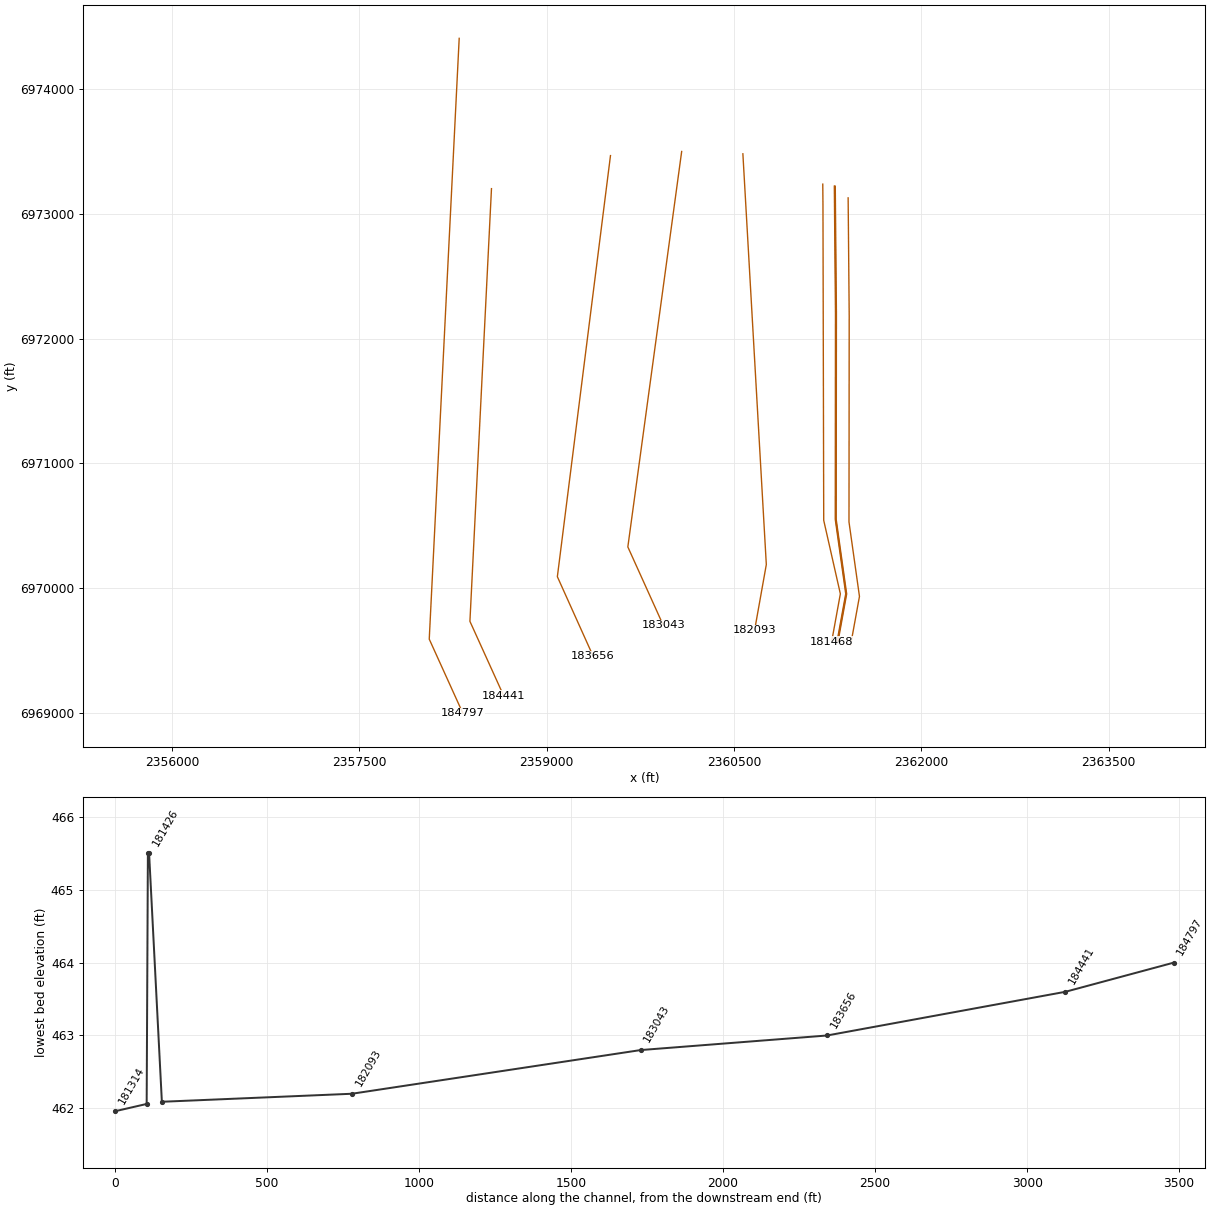
HEC-RAS study CDC_Consolidated_Model.prj: Upper Trinity CDC Consolidated Model

--- CDC_Consolidated_Model.g02 (geometry) --- (continued)

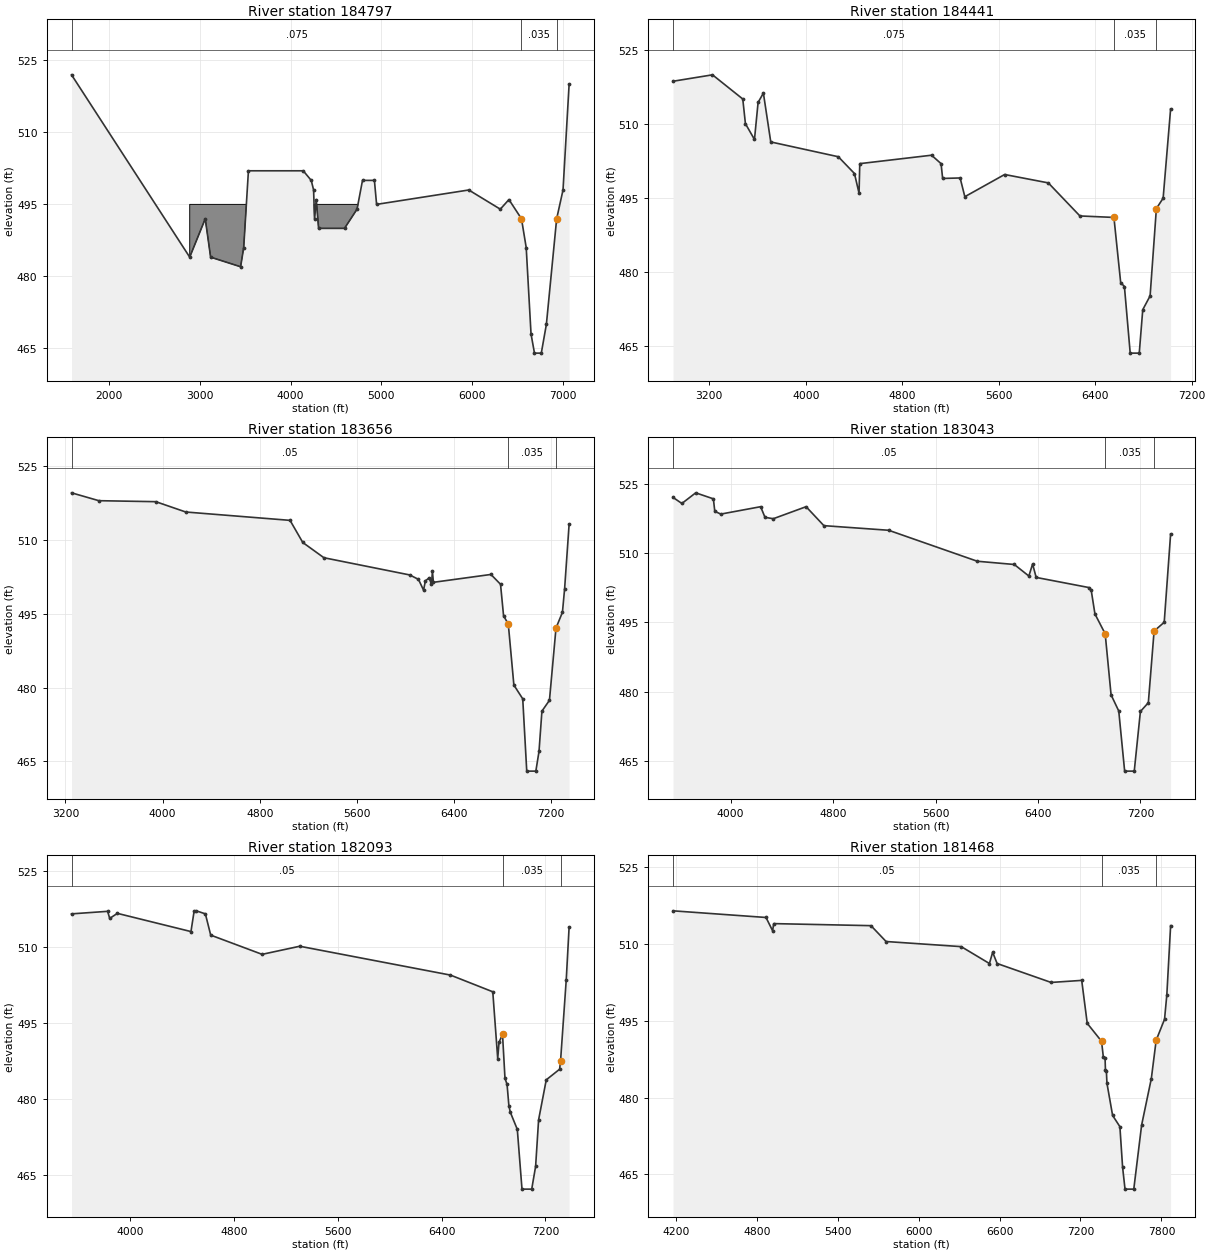
Type RM Length L Ch R = 1 ,184797  ,356,356,356
BEGIN DESCRIPTION:
This cross section corresponds to cross section 184850 of the non-georeferenced CDC model which was the source of this model.
END DESCRIPTION:
XS GIS Cut Line= 4
2358299.041962376974406.54958828  2358234.391604 6973108.1581484
 2358059.2944155  6969591.631768 2358328.8555562 6968996.7379447
#Sta/Elev= 30
    1591     522    2891     484    3062     492    3121     484    3451     482
    3485     486    3537     502    4140     502    4228     500    4254     498
    4264     492    4283     496    4309     490    4594     490    4732     494
    4792     500    4923     500    4947     495    5961     498    6308     494
    6403     496    6541     492    6593     486    6646     468    6684     464
    6759     464    6815     470    6928     492    6998     498    7065     520
#Mann= 3 ,0,0
    1591    .075       0    6541    .035       0    6928     .05       0
#Block Obstruct= 2 ,-1
                         2891.01    6180     495
Bank Sta=6541,6928
XS Rating Curve= 0 ,0
Exp/Cntr=0.3,0.1

Type RM Length L Ch R = 1 ,184441  ,784,784,784
BEGIN DESCRIPTION:
This cross section corresponds to cross section 184495 of the non-georeferenced CDC model which was the source of this model.
END DESCRIPTION:
XS GIS Cut Line= 3
  2358557.588317  6973201.966854   2358384.92795   6969734.37984
   2358654.48909   6969139.48602
#Sta/Elev= 30
    2900   518.7    3227     520    3478   515.1    3500   510.1    3575   506.9
    3605   514.4    3649   516.3    3710   506.4    4270   503.4    4404     500
    4442     496    4448     502    5043  503.71    5122     502    5135     499
    5280   499.1    5319   495.3    5649   499.8    6011   498.1    6273   491.4
    6555   491.1    6611   477.9    6642   477.1    6690   463.6    6765   463.6
    6794   472.4    6855   475.2    6907   492.9    6963     495    7025   513.1
#Mann= 3 ,0,0
    2900    .075       0    6555    .035       0    6907     .05       0
Bank Sta=6555,6907
XS Rating Curve= 0 ,0
Exp/Cntr=0.3,0.1

Type RM Length L Ch R = 1 ,183656  ,613,613,613
BEGIN DESCRIPTION:
This cross section corresponds to cross section 183709 of the non-georeferenced CDC model which was the source of this model.
---------------------------------------------------------------------
CDC FW050103-01 Riverbend West Trussway Site
Cross-section 183709 - 185387
---------------------------------------------------------------------
END DESCRIPTION:
XS GIS Cut Line= 3
  2359510.333965 6973466.7569936     2359085.044   6970092.03694
   2359371.13201   6969455.81216
#Sta/Elev= 30
    3250   519.6    3475     518    3944   517.8    4191   515.7    5050     514
    5155   509.5    5329   506.4    6036   502.9    6108     502    6150   499.8
    6165   501.7    6196   502.3    6215     501    6223   503.6    6231   501.4
    6705     503    6784     501    6809   494.6    6848   492.9    6894   480.5
    6967   477.7    7000     463    7075     463    7101     467    7125   475.2
    7187   477.4    7241   492.1    7294   495.3    7312   500.1    7349   513.2
#Mann= 3 ,0,0
    3250     .05       0    6848    .035       0    7241     .05       0
Bank Sta=6848,7241
XS Rating Curve= 0 ,0
Exp/Cntr=0.3,0.1

Type RM Length L Ch R = 1 ,183043  ,1050,950,900
BEGIN DESCRIPTION:
This cross section corresponds to cross section 183096 of the non-georeferenced CDC model which was the source of this model.
END DESCRIPTION:
XS GIS Cut Line= 3
  2360080.302205 6973499.7483181   2359649.32404   6970330.62602
   2359932.37499   6969703.87006
#Sta/Elev= 30
    3550     522    3619   520.7    3727     523    3865   521.7    3876     519
    3923   518.4    4234     520    4268   517.7    4333   517.4    4589     520
    4728   515.9    5234   514.9    5926   508.2    6215   507.5    6329     505
    6358   507.6    6386   504.7    6800   502.5    6816   501.9    6845   496.8
    6925   492.5    6971   479.3    7031   475.8    7077   462.8    7152   462.8
    7200   475.7    7262   477.6    7307   493.1    7386     495    7436   514.1
#Mann= 3 ,0,0
    3550     .05       0    6925    .035       0    7307     .05       0
Bank Sta=6925,7307
XS Rating Curve= 0 ,0
Exp/Cntr=0.3,0.1

Type RM Length L Ch R = 1 ,182093  ,610,625,625
BEGIN DESCRIPTION:
This cross section corresponds to cross section 182146 of the non-georeferenced CDC model which was the source of this model.
END DESCRIPTION:
XS GIS Cut Line= 3
   2360570.38532  6973481.139121   2360758.00785   6970189.29297
   2360664.02707   6969661.78812
#Sta/Elev= 30
    3550   516.6    3828   517.1    3844   515.7    3903   516.7    4470   513.1
    4494   517.1    4511   517.2    4581   516.6    4622   512.4    5018   508.6
    5308   510.2    6469   504.5    6795   501.2    6833     488    6843   491.2
    6870   492.8    6889   484.1    6905   482.9    6919   478.7    6930   477.4
    6984     474    7020   462.2    7095   462.2    7125   466.7    7148   475.9
    7207   483.8    7310   485.9    7317   487.5    7361   503.6    7383     514
#Mann= 3 ,0,0
    3550     .05       0    6870    .035       0    7317     .05       0
Bank Sta=6870,7317
XS Rating Curve= 0 ,0
Exp/Cntr=0.3,0.1

Type RM Length L Ch R = 1 ,181468  ,42,42,42
BEGIN DESCRIPTION:
This cross section corresponds to cross section 181521 of the non-georeferenced CDC model which was the source of this model.
END DESCRIPTION:
XS GIS Cut Line= 6
  2361210.029294 6973237.9957154  2361210.029294 6973237.9957154
   2361211.53516   6973077.56016   2361217.59715   6970543.71713
   2361350.82294   6969954.61497   2361281.10589   6969571.17315
#Sta/Elev= 30
    4180   516.5    4869   515.2    4918   512.6    4926     514    5647   513.6
    5759   510.5    6316   509.5    6525   506.2    6549   508.4    6582   506.2
    6982   502.5    7209   502.9    7250   494.5    7356     491    7369     488
    7382   487.8    7385   485.3    7392   485.1    7396   482.8    7438   476.5
    7492   474.3    7512   466.4    7530  462.09    7595  462.09    7653   474.6
    7725   483.7    7761   491.2    7823   495.3    7840   500.1    7868   513.6
#Mann= 3 ,0,0
    4180     .05       0    7356    .035       0    7761     .05       0
Bank Sta=7356,7761
XS Rating Curve= 0 ,0
Exp/Cntr=0.3,0.1

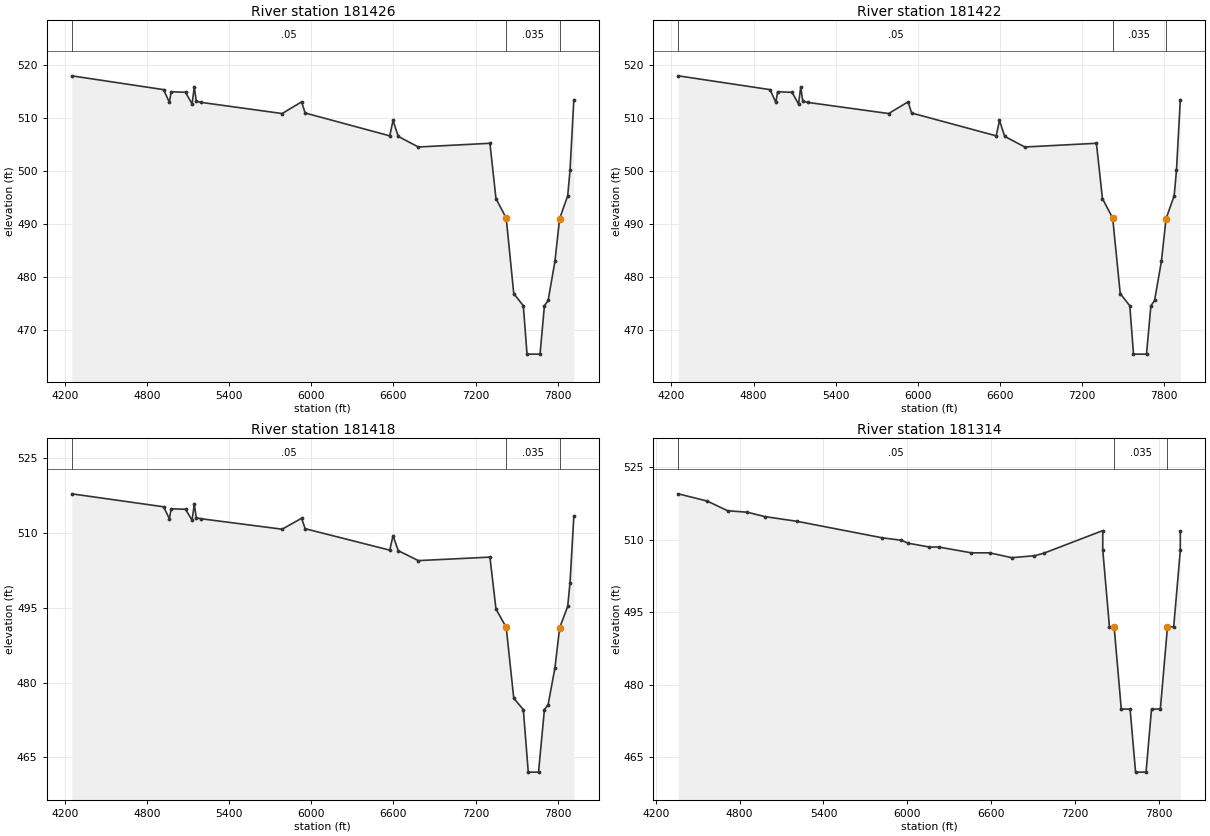
Type RM Length L Ch R = 1 ,181426  ,4,4,4
BEGIN DESCRIPTION:
This cross section corresponds to cross section 181479 of the non-georeferenced CDC model which was the source of this model.
END DESCRIPTION:
XS GIS Cut Line= 5
  2361302.493278 6973221.8763323 2361311.6129613 6972207.4595381
 2361309.9459713 6970552.1327981 2361393.7978313 6969955.0716581
 2361323.0847213 6969566.1537981
#Sta/Elev= 30
    4250   517.9    4921   515.3    4963   512.9    4976   514.9    5081   514.8
    5129   512.6    5145   515.8    5160   513.1    5195   512.9    5787   510.8
    5929     513    5955   510.9    6573   506.6    6597   509.5    6635   506.5
    6782   504.5    7305   505.2    7349   494.8    7424   491.1    7479   476.9
    7549   474.6    7576   465.5    7671   465.5    7703   474.6    7730   475.6
    7780     483    7814     491    7873   495.3    7890   500.1    7918   513.4
#Mann= 3 ,0,0
    4250     .05       0    7424    .035       0    7814     .05       0
Bank Sta=7424,7814
XS Rating Curve= 0 ,0
Exp/Cntr=0.3,0.1

Type RM Length L Ch R = 1 ,181422  ,4,4,4
BEGIN DESCRIPTION:
This cross section corresponds to cross section 181475 of the non-georeferenced CDC model which was the source of this model.
END DESCRIPTION:
XS GIS Cut Line= 5
  2361306.421067 6973221.1185436 2361315.5407504 6972206.7017494
 2361313.8737604 6970551.3750094 2361397.7256204 6969954.3138694
 2361327.0125104 6969565.3960094
#Sta/Elev= 30
    4250   517.9    4921   515.3    4963   512.9    4976   514.9    5081   514.8
    5129   512.6    5145   515.8    5160   513.1    5195   512.9    5787   510.8
    5929     513    5955   510.9    6573   506.6    6597   509.5    6635   506.5
    6782   504.5    7305   505.2    7349   494.8    7424   491.1    7479   476.9
    7549   474.6    7576   465.5    7671   465.5    7703   474.6    7730   475.6
    7780     483    7814     491    7873   495.3    7890   500.1    7918   513.4
#Mann= 3 ,0,0
    4250     .05       0    7424    .035       0    7814     .05       0
Bank Sta=7424,7814
XS Rating Curve= 0 ,0
Exp/Cntr=0.3,0.1

Type RM Length L Ch R = 1 ,181418  ,104,104,104
BEGIN DESCRIPTION:
This cross section corresponds to cross section 181471 of the non-georeferenced CDC model which was the source of this model.
END DESCRIPTION:
XS GIS Cut Line= 5
  2361310.152467 6973220.3986442   2361319.27215   6972205.98185
   2361317.60516   6970550.65511   2361401.45702   6969953.59397
   2361330.74391   6969564.67611
#Sta/Elev= 30
    4250   517.9    4921   515.3    4963   512.9    4976   514.9    5081   514.8
    5129   512.6    5145   515.8    5160   513.1    5195   512.9    5787   510.8
    5929     513    5955   510.9    6573   506.6    6597   509.5    6635   506.5
    6782   504.5    7305   505.2    7349   494.8    7424   491.1    7479   476.9
    7549   474.6    7585  462.06    7660  462.06    7703   474.6    7730   475.6
    7780     483    7814     491    7873   495.3    7890   500.1    7918   513.4
#Mann= 3 ,0,0
    4250     .05       0    7424    .035       0    7814     .05       0
Bank Sta=7424,7814
XS Rating Curve= 0 ,0
Exp/Cntr=0.3,0.1

Type RM Length L Ch R = 1 ,181314  ,82,82,82
BEGIN DESCRIPTION:
This cross section corresponds to cross section 181367 of the non-georeferenced CDC model which was the source of this model.
END DESCRIPTION:
XS GIS Cut Line= 5
  2361413.135029 6973127.9692752 2361421.6012506 6972186.2394851
 2361419.9342606 6970530.9127451 2361503.7861206 6969933.8516051
 2361433.0730106 6969544.9337451
#Sta/Elev= 30
    4360   519.5    4568     518    4714     516    4854   515.7    4979   514.8
    5214   513.8    5822   510.4    5958   509.9    6005   509.3    6158   508.5
    6225   508.5    6459   507.3    6590   507.3    6748   506.3    6911   506.7
    6976   507.2    7400   511.9    7400   507.9  7447.7     492 7481.43     492
 7532.43     475 7595.81     475 7634.93  461.96 7709.93  461.96 7749.05     475
 7812.43     475 7863.43     492 7907.91     492 7955.31   507.8 7955.31   511.8
#Mann= 3 ,0,0
    4360     .05       0 7481.43    .035       0 7863.43     .05       0
Bank Sta=7481.43,7863.43
XS Rating Curve= 0 ,0
Exp/Cntr=0.5,0.3