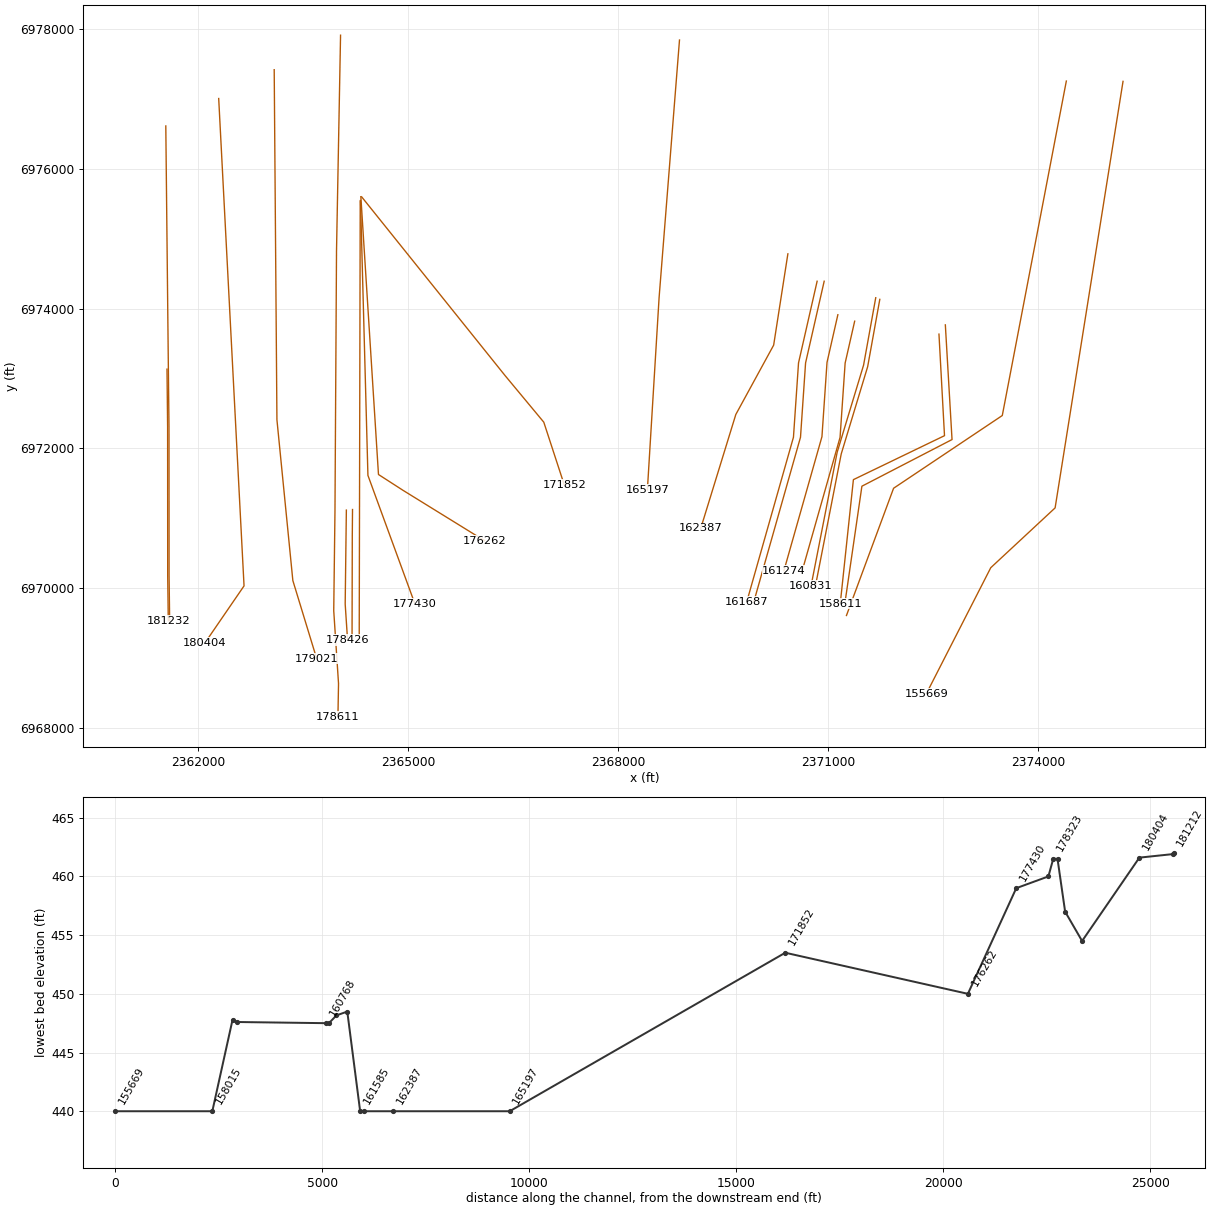
HEC-RAS study CDC_Consolidated_Model.prj: Upper Trinity CDC Consolidated Model

--- CDC_Consolidated_Model.g02 (geometry) --- (continued)

Type RM Length L Ch R = 3 ,181272  ,,,
BEGIN DESCRIPTION:
Handley-Ederville Road
END DESCRIPTION:
Node Name=Handley-Edervill
Bridge Culvert--1,0,-1,-1, 0
Deck Dist Width WeirC Skew NumUp NumDn MinLoCord MaxHiCord MaxSubmerge Is_Ogee
1,80,2.6,0, 18, 18, , , 0.95, 0, ,,,
    7400 7469.53 7472.03 7538.75 7541.25  7606.1  7608.6 7671.18 7673.68  7733.8
  7736.3 7793.67 7796.17 7850.51 7853.01 7903.99 7906.49 7955.31
   511.9   512.3   512.3   512.6   512.6   512.9   512.9     513     513     513
     513   512.8   512.8   512.6   512.6   512.2   512.2   511.8
   507.9   508.3   508.3   508.6   508.6   508.9   508.9     509     509     509
     509   508.8   508.8   508.6   508.6   508.2   508.2   507.8
    7400 7469.53 7472.03 7538.75 7541.25  7606.1  7608.6 7671.18 7673.68  7733.8
  7736.3 7793.67 7796.17 7850.51 7853.01 7903.99 7906.49 7955.31
   511.9   512.3   512.3   512.6   512.6   512.9   512.9     513     513     513
     513   512.8   512.8   512.6   512.6   512.2   512.2   511.8
   507.9   508.3   508.3   508.6   508.6   508.9   508.9     509     509     509
     509   508.8   508.8   508.6   508.6   508.2   508.2   507.8
Pier Skew, UpSta & Num, DnSta & Num=  ,7470.78, 2 ,7470.78, 2 , 0 , 0 , 0 ,,
     2.5     2.5
     450     510
     2.5     2.5
     450     510
Pier Skew, UpSta & Num, DnSta & Num=  ,7540, 2 ,7540, 2 , 0 , 0 , 0 ,,
     2.5     2.5
     450     510
     2.5     2.5
     450     510
Pier Skew, UpSta & Num, DnSta & Num=  ,7607.35, 2 ,7607.35, 2 , 0 , 0 , 0 ,,
     2.5     2.5
     450     510
     2.5     2.5
     450     510
Pier Skew, UpSta & Num, DnSta & Num=  ,7672.43, 2 ,7672.43, 2 , 0 , 0 , 0 ,,
     2.5     2.5
     450     510
     2.5     2.5
     450     510
Pier Skew, UpSta & Num, DnSta & Num=  ,7735.05, 2 ,7735.05, 2 , 0 , 0 , 0 ,,
     2.5     2.5
     450     510
     2.5     2.5
     450     510
Pier Skew, UpSta & Num, DnSta & Num=  ,7794.92, 2 ,7794.92, 2 , 0 , 0 , 0 ,,
     2.5     2.5
     450     510
     2.5     2.5
     450     510
Pier Skew, UpSta & Num, DnSta & Num=  ,7851.76, 2 ,7851.76, 2 , 0 , 0 , 0 ,,
     2.5     2.5
     450     510
     2.5     2.5
     450     510
Pier Skew, UpSta & Num, DnSta & Num=  ,7905.24, 2 ,7905.24, 2 , 0 , 0 , 0 ,,
     2.5     2.5
     450     510
     2.5     2.5
     450     510
BR Coef= 1 , 0 , 0 ,1.05, 0 ,,,0.8,-1,0.5,1,
WSPro=,,,, 1 ,,,, 0 ,,,, 0 ,,,,-1 ,-1 ,-1 , 0 , 0 , 0 , 0 , 0
BC Design=,, 0 ,, 0 ,,,,,,
BC HTab HWMax=519.5
BC Use User HTab Curves=0
BC User HTab FreeFlow(D)= 0

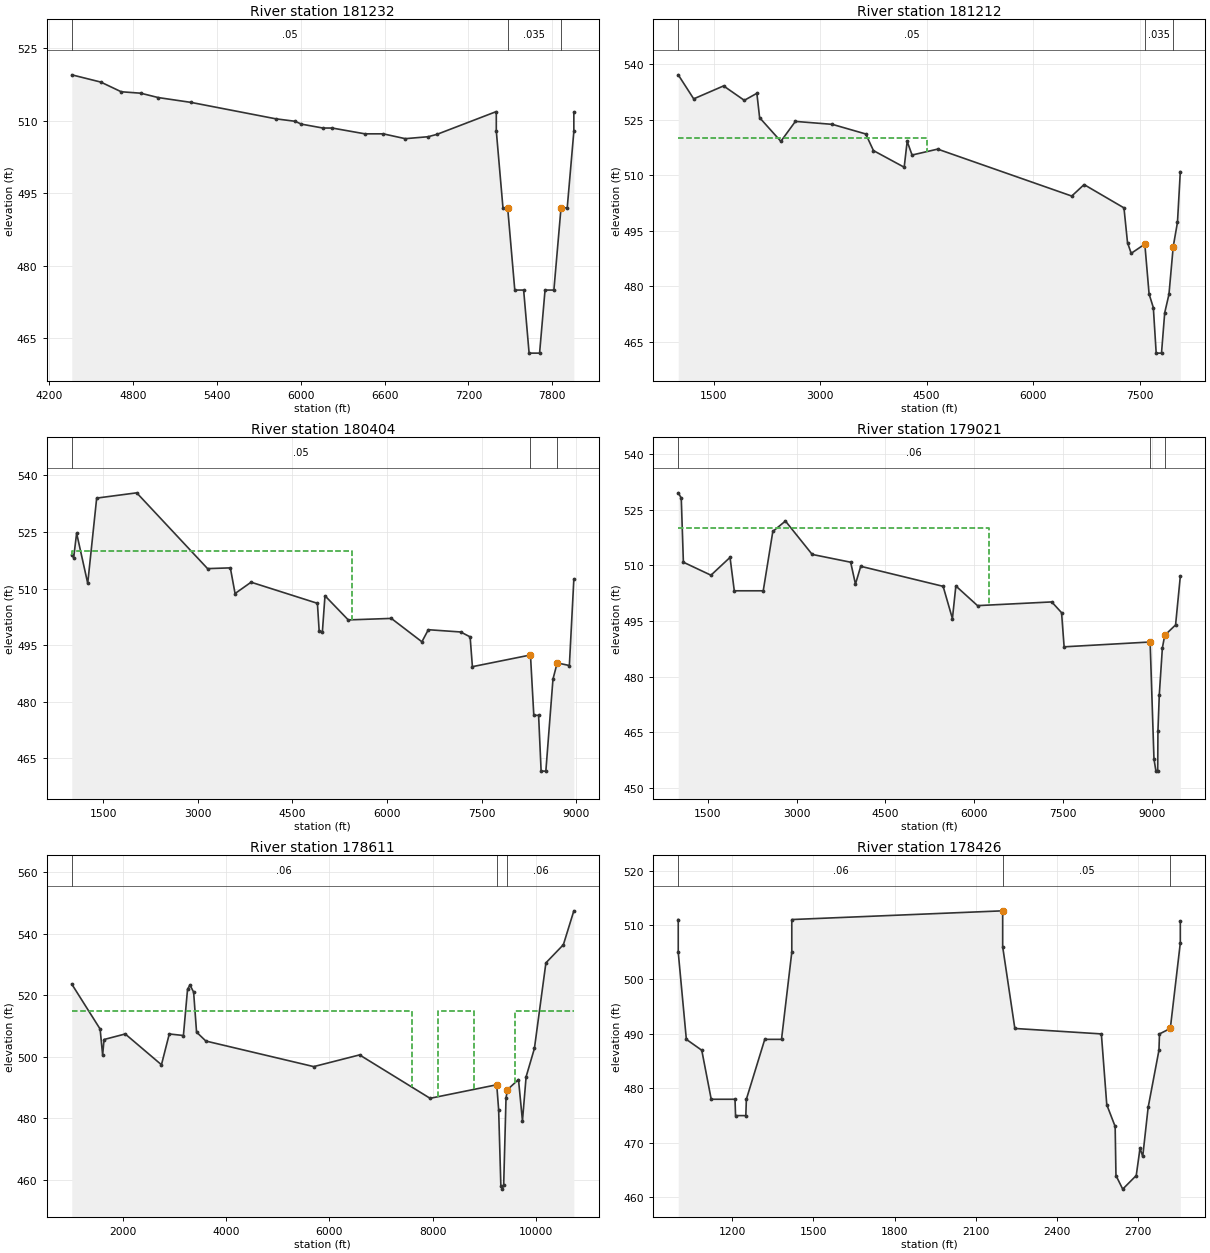
Type RM Length L Ch R = 1 ,181232  ,20,20,20
BEGIN DESCRIPTION:
This cross section corresponds to cross section 181285 of the non-georeferenced CDC model which was the source of this model.
END DESCRIPTION:
XS GIS Cut Line= 5
  2361552.884858 6973134.1526615 2361561.6402378 6972306.8421715
 2361562.8780978 6970179.9373115 2361564.3869478 6970066.7462615
 2361571.1129878 6969538.9422015
#Sta/Elev= 30
    4360   519.5    4568     518    4714     516    4854   515.7    4979   514.8
    5214   513.8    5822   510.4    5958   509.9    6005   509.3    6158   508.5
    6225   508.5    6459   507.3    6590   507.3    6748   506.3    6911   506.7
    6976   507.2    7400   511.9    7400   507.9  7447.7     492 7481.43     492
 7532.43     475 7595.81     475 7634.93  461.96 7709.93  461.96 7749.05     475
 7812.43     475 7863.43     492 7907.91     492 7955.31   507.8 7955.31   511.8
#Mann= 3 ,0,0
    4360     .05       0 7481.43    .035       0 7863.43     .05       0
Bank Sta=7481.43,7863.43
XS Rating Curve= 0 ,0
Exp/Cntr=0.3,0.1

Type RM Length L Ch R = 1 ,181212  ,928,808,728
BEGIN DESCRIPTION:
This cross section corresponds to cross section 181265 of the non-georeferenced CDC model which was the source of this model.
END DESCRIPTION:
XS GIS Cut Line= 6
  2361535.702464 6976609.8584375   2361535.70413   6976609.70107
   2361581.28114   6972303.05285     2361582.519   6970176.14799
   2361584.02785   6970062.95694   2361590.75389   6969535.15288
#Sta/Elev= 30
    1000   537.2    1218   530.7    1639   534.2    1931   530.3    2108   532.2
    2147   525.6    2446   519.2    2651   524.6    3171   523.8    3642   521.2
    3751   516.7    4184   512.2    4226   519.2    4295   515.5    4656   517.1
    6545   504.4    6719   507.5    7281   501.2    7331   491.8    7383   488.9
    7575   491.4    7635   477.9    7695   474.2    7735   461.9    7810   461.9
    7855   472.8    7915   477.8    7975   490.7    8035   497.3    8075     511
#Mann= 3 ,0,0
    1000     .05       0    7575    .035       0    7975     .05       0
#XS Ineff= 2 , 0
       0    4500     520               0
Permanent Ineff=
       F       F
Bank Sta=7575,7975
XS Rating Curve= 0 ,0
Exp/Cntr=0.3,0.1

Type RM Length L Ch R = 1 ,180404  ,852,1383,1553
BEGIN DESCRIPTION:
This cross section corresponds to cross section 180455 of the non-georeferenced CDC model which was the source of this model.
END DESCRIPTION:
XS GIS Cut Line= 3
   2362291.77906   6977002.08906   2362653.95485   6970036.21093
 2362095.2733342 6969221.6854017
#Sta/Elev= 30
    1000     519    1030   518.2    1077   524.7    1253   511.4    1395     534
    2030   535.4    3154   515.3    3515   515.5    3590   508.7    3844   511.7
    4896   506.1    4924   498.7    4975   498.6    5016   508.1    5385   501.7
    6068   502.1    6553   495.9    6655   499.1    7168   498.5    7318   497.2
    7354   489.3    8275   492.4    8328   476.4    8404   476.4    8444   461.6
    8519   461.6    8632     486    8699   490.3    8892   489.6    8963   512.5
#Mann= 3 ,0,0
    1000     .05       0    8275    .035       0    8699     .08       0
#XS Ineff= 2 , 0
       0    5450     520               0
Permanent Ineff=
       F       F
Bank Sta=8275,8699
XS Rating Curve= 0 ,0
Exp/Cntr=0.3,0.1

Type RM Length L Ch R = 1 ,179021  ,499,410,399
BEGIN DESCRIPTION:
This cross section corresponds to cross section 179075 of the non-georeferenced CDC model which was the source of this model.
END DESCRIPTION:
XS GIS Cut Line= 4
   2363085.04585     6977414.061   2363124.02904   6972410.30002
   2363351.58403   6970112.34989 2363692.7487769 6968994.3479177
#Sta/Elev= 30
    1000   529.5    1051   528.1    1087   510.8    1553   507.3    1875   512.1
    1947   503.1    2436   503.1    2598   519.1    2811   521.9    3263   512.9
    3913   510.8    3994   504.9    4083   509.7    5475   504.3    5632   495.6
    5690   504.4    6056   499.1    7310   500.1    7476   497.2    7519     488
    8972   489.3    9037   457.8    9070   454.5    9100   454.5    9104   465.3
    9127   475.1    9179   487.7    9219   491.1    9402   493.9    9482     507
#Mann= 3 ,0,0
    1000     .06       0    8972     .05       0    9219     .08       0
#XS Ineff= 2 , 0
       0    6250     520               0
Permanent Ineff=
       F       F
Bank Sta=8972,9219
XS Rating Curve= 0 ,0
Exp/Cntr=0.3,0.1

Type RM Length L Ch R = 1 ,178611  ,184,184,184
BEGIN DESCRIPTION:
This cross section corresponds to cross section 178664 of the non-georeferenced CDC model which was the source of this model.
END DESCRIPTION:
XS GIS Cut Line= 6
   2364033.43601   6977907.19585   2363975.63396    6974825.7299
   2363953.58414   6971103.01195   2363935.88207   6969681.06794
   2364004.40195   6968639.90204   2363996.04402    6968169.2081
#Sta/Elev= 30
    1000   523.6    1550     509    1599   500.5    1626   505.6    2037   507.4
    2740   497.4    2892   507.4    3166   506.9    3246   521.9    3293   523.3
    3364     521    3421     508    3602   505.1    5694   496.8    6584   500.6
    7952   486.5    9245   490.9    9282   482.8    9325     458    9355     457
    9380   458.5    9425   486.5    9452   489.3    9667   492.6    9744   479.2
    9815   493.5    9976   502.7   10199   530.5   10538   536.4   10741   547.4
#Mann= 3 ,0,0
    1000     .06       0    9245     .05       0    9452     .06       0
#XS Ineff= 3 ,-1
    1000    7600     515    8100    8800     515    9600   10741     515
Permanent Ineff=
       F       F       F
Bank Sta=9245,9452
XS Rating Curve= 0 ,0
Exp/Cntr=0.3,0.1

Type RM Length L Ch R = 1 ,178426  ,103,103,103
BEGIN DESCRIPTION:
This cross section corresponds to cross section 178479 of the non-georeferenced CDC model which was the source of this model.
END DESCRIPTION:
XS GIS Cut Line= 3
  2364116.307598 6971119.6475117     2364099.592     6969776.937
 2364133.3579617 6969263.8614388
#Sta/Elev= 30
    1000     511    1000     505    1030     489    1087     487    1122     478
    1210     478    1212     475    1250     475    1252     478    1320     489
    1382     489    1420     505    1420     511    2200   512.6    2200     506
    2245     491    2565     490    2585     477    2616     473    2619     464
    2644   461.5    2694     464    2708     469    2718   467.5    2738   476.5
    2778     487    2780     490    2820     491    2857   506.7    2857   510.7
#Mann= 3 ,0,0
    1000     .06       0    2200     .05       0    2820     .06       0
Bank Sta=2200,2820
XS Rating Curve= 0 ,0
Exp/Cntr=0.5,0.3

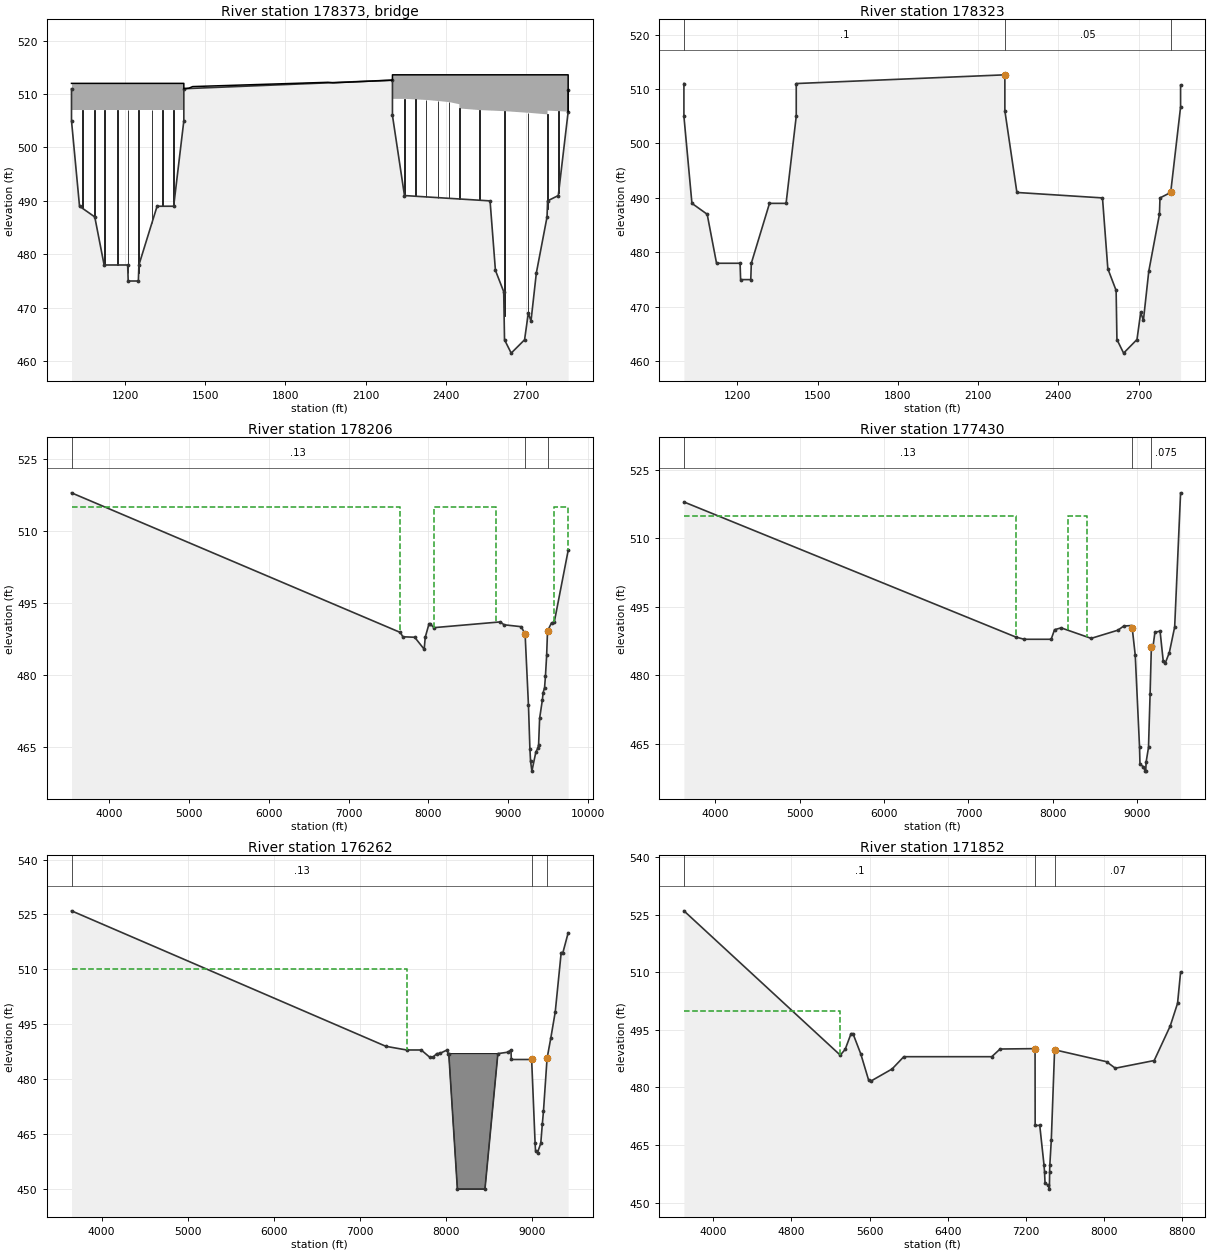
Type RM Length L Ch R = 3 ,178373  ,,,
BEGIN DESCRIPTION:
I.H. 820
END DESCRIPTION:
Node Name=IH 820
Bridge Culvert--1,0,-1,-1, 0
Deck Dist Width WeirC Skew NumUp NumDn MinLoCord MaxHiCord MaxSubmerge Is_Ogee
1,100,2.6,0, 36, 36, , , 0.95, 0, ,,,
    1000    1420    1420    1439    1453    1959    1978    2200    2200    2245
    2247    2285    2287    2325    2327    2370    2372    2410    2412    2450
    2450    2452    2525    2528    2616    2619    2705    2708    2778    2780
    2780    2820    2820    2822    2857    2857
     512     512     511   511.1   511.4   512.2   512.1   512.6   513.6   513.6
   513.6   513.6   513.6   513.6   513.6   513.6   513.6   513.6   513.6   513.6
   513.6   513.6   513.6   513.6   513.6   513.6   513.6   513.6   513.6   513.6
   513.6   513.6   513.6   513.6   513.6   506.7
     507     507     511   511.1   511.4   512.2   512.1   512.6   509.1   509.1
   509.1     509     509   508.9   508.9   508.7   508.7   508.5   508.5   508.1
   507.3   507.3     507     507   506.8   506.8   506.5   506.5   506.2   506.2
   506.9   506.8   506.8   506.8   506.7   506.7
    1000    1420    1420    1439    1453    1959    1978    2200    2200    2245
    2247    2285    2287    2325    2327    2370    2372    2410    2412    2450
    2450    2452    2525    2528    2616    2619    2705    2708    2778    2780
    2780    2820    2820    2822    2857    2857
     512     512     511   511.1   511.4   512.2   512.1   512.6   513.6   513.6
   513.6   513.6   513.6   513.6   513.6   513.6   513.6   513.6   513.6   513.6
   513.6   513.6   513.6   513.6   513.6   513.6   513.6   513.6   513.6   513.6
   513.6   513.6   513.6   513.6   513.6   506.7
     507     507     511   511.1   511.4   512.2   512.1   512.6   509.1   509.1
   509.1     509     509   508.9   508.9   508.7   508.7   508.5   508.5   508.1
   507.3   507.3     507     507   506.8   506.8   506.5   506.5   506.2   506.2
   506.9   506.8   506.8   506.8   506.7   506.7
Pier Skew, UpSta & Num, DnSta & Num=  ,1041, 2 ,1041, 2 , 0 , 0 , 0 ,,
       2       2
     475     510
       2       2
     475     510
Pier Skew, UpSta & Num, DnSta & Num=  ,1086, 2 ,1086, 2 , 0 , 0 , 0 ,,
       2       2
     475     510
       2       2
     475     510
Pier Skew, UpSta & Num, DnSta & Num=  ,1123, 2 ,1123, 2 , 0 , 0 , 0 ,,
       2       2
     475     510
       2       2
     475     510
Pier Skew, UpSta & Num, DnSta & Num=  ,1171, 2 ,1171, 2 , 0 , 0 , 0 ,,
       2       2
     475     510
       2       2
     475     510
Pier Skew, UpSta & Num, DnSta & Num=  ,1211, 2 ,1211, 2 , 0 , 0 , 0 ,,
       2       2
     475     510
       2       2
     475     510
Pier Skew, UpSta & Num, DnSta & Num=  ,1251, 2 ,1251, 2 , 0 , 0 , 0 ,,
       2       2
     475     510
       2       2
     475     510
Pier Skew, UpSta & Num, DnSta & Num=  ,1301, 2 ,1301, 2 , 0 , 0 , 0 ,,
       2       2
     475     510
       2       2
     475     510
Pier Skew, UpSta & Num, DnSta & Num=  ,1341, 2 ,1341, 2 , 0 , 0 , 0 ,,
       2       2
     475     510
       2       2
     475     510
Pier Skew, UpSta & Num, DnSta & Num=  ,1381, 2 ,1381, 2 , 0 , 0 , 0 ,,
       2       2
     475     510
       2       2
     475     510
Pier Skew, UpSta & Num, DnSta & Num=  ,2246, 2 ,2246, 2 , 0 , 0 , 0 ,,
       2       2
     465     510
       2       2
     465     510
Pier Skew, UpSta & Num, DnSta & Num=  ,2286, 2 ,2286, 2 , 0 , 0 , 0 ,,
       2       2
     465     510
       2       2
     465     510
Pier Skew, UpSta & Num, DnSta & Num=  ,2326, 2 ,2326, 2 , 0 , 0 , 0 ,,
       2       2
     465     510
       2       2
     465     510
Pier Skew, UpSta & Num, DnSta & Num=  ,2371, 2 ,2371, 2 , 0 , 0 , 0 ,,
       2       2
     465     510
       2       2
     465     510
Pier Skew, UpSta & Num, DnSta & Num=  ,2411, 2 ,2411, 2 , 0 , 0 , 0 ,,
       2       2
     465     510
       2       2
     465     510
Pier Skew, UpSta & Num, DnSta & Num=  ,2451, 2 ,2451, 2 , 0 , 0 , 0 ,,
       2       2
     465     510
       2       2
     465     510
Pier Skew, UpSta & Num, DnSta & Num=  ,2526.5, 2 ,2526.5, 2 , 0 , 0 , 0 ,,
       3       3
     465     510
       3       3
     465     510
Pier Skew, UpSta & Num, DnSta & Num=  ,2617.5, 2 ,2617.5, 2 , 0 , 0 , 0 ,,
       3       3
     465     510
       3       3
     465     510
Pier Skew, UpSta & Num, DnSta & Num=  ,2706.5, 2 ,2706.5, 2 , 0 , 0 , 0 ,,
       3       3
     465     510
       3       3
     465     510
Pier Skew, UpSta & Num, DnSta & Num=  ,2779, 2 ,2779, 2 , 0 , 0 , 0 ,,
       2       2
     465     510
       2       2
     465     510
Pier Skew, UpSta & Num, DnSta & Num=  ,2821, 2 ,2821, 2 , 0 , 0 , 0 ,,
       2       2
     465     510
       2       2
     465     510
BR Coef= 1 , 0 , 0 ,1.05, 0 ,,,0.8,-1,0.5,1,
WSPro=,,,, 1 ,,,, 0 ,,,, 0 ,,,,-1 ,-1 ,-1 , 0 , 0 , 0 , 0 , 0
BC Design=,, 0 ,, 0 ,,,,,,
BC HTab HWMax=512.6
BC Use User HTab Curves=0
BC User HTab FreeFlow(D)= 0

Type RM Length L Ch R = 1 ,178323  ,117,117,117
BEGIN DESCRIPTION:
This cross section corresponds to cross section 178377 of the non-georeferenced CDC model which was the source of this model.
END DESCRIPTION:
XS GIS Cut Line= 3
  2364204.325923 6971127.7267668      2364201.01     6970750.951
 2364197.5843205  6969270.745322
#Sta/Elev= 30
    1000     511    1000     505    1030     489    1087     487    1122     478
    1210     478    1212     475    1250     475    1252     478    1320     489
    1382     489    1420     505    1420     511    2200   512.6    2200     506
    2245     491    2565     490    2585     477    2616     473    2619     464
    2644   461.5    2694     464    2708     469    2718   467.5    2738   476.5
    2778     487    2780     490    2820     491    2857   506.7    2857   510.7
#Mann= 3 ,0,0
    1000      .1       0    2200     .05       0    2820     .08       0
Bank Sta=2200,2820
XS Rating Curve= 0 ,0
Exp/Cntr=0.3,0.1

Type RM Length L Ch R = 1 ,178206  ,748,776,848
BEGIN DESCRIPTION:
This cross section corresponds to cross section 178263 of the non-georeferenced CDC model which was the source of this model.
END DESCRIPTION:
XS GIS Cut Line= 6
     2364314.499     6975536.584       2364313.4     6975061.585
     2364311.085     6974061.588     2364304.952     6971411.595
     2364302.291     6970261.598      2364300.08     6969306.601
#Sta/Elev= 30
    3525     518    7650   488.9    7681     488    7830   487.9    7949   485.4
    7962   487.9    8008   490.6    8024   490.7    8070   489.9    8904   491.1
    8950   490.5    9167   490.1    9215   488.5    9257   473.7    9275   464.7
    9283   462.1    9300     460    9350     464    9376   464.8    9384   465.5
    9397     471    9432   474.9    9440   476.3    9459   477.4    9470   479.8
    9485   484.1    9496   489.2    9546   490.9    9580     491    9755     506
#Mann= 3 ,0,0
    3525     .13       0    9215     .05       0    9496     .08       0
#XS Ineff= 3 ,-1
    8070    8850     515    9580    9755     515    3525    7650     515
Permanent Ineff=
       F       F       F
Bank Sta=9215,9496
XS Rating Curve= 0 ,0
Exp/Cntr=0.3,0.1

Type RM Length L Ch R = 1 ,177430  ,698,1168,1246
BEGIN DESCRIPTION:
This cross section corresponds to cross section 177485 of the non-georeferenced CDC model which was the source of this model.
END DESCRIPTION:
XS GIS Cut Line= 4
     2364318.534     6975544.511     2364424.556     6971615.942
     2364615.612     6971093.029     2365095.148      6969781.68
#Sta/Elev= 30
    3630     518    7560   488.4    7660   487.9    7980   487.9    8020     490
    8098   490.4    8454   488.1    8772   489.9    8839   490.8    8922   490.9
    8931   490.2    8940   490.4    8976   484.4    9027   464.2    9032   460.5
    9070     460    9095     459    9100     459    9105     461    9133   464.2
    9152     476    9167   486.3    9187   486.4    9209   489.4    9270   489.7
    9307   483.2    9334   482.8    9380     485    9443   490.6    9513     520
#Mann= 3 ,0,0
    3630     .13       0    8940     .05       0    9167    .075       0
#XS Ineff= 2 ,-1
    8180    8400     515    3630    7560     515
Permanent Ineff=
       F       F
#Block Obstruct= 2 , 0
       0                    9270       0   489.7
Bank Sta=8940,9167
XS Rating Curve= 0 ,0
Exp/Cntr=0.3,0.1

Type RM Length L Ch R = 1 ,176262  ,2498,4410,1799
BEGIN DESCRIPTION:
This cross section corresponds to cross section 176313 of the non-georeferenced CDC model which was the source of this model.
END DESCRIPTION:
XS GIS Cut Line= 5
     2364323.523      6975598.92      2364324.42      6975584.78
      2364575.42      6971628.24     2364925.289     6971402.707
     2366091.574     6970682.309
#Sta/Elev= 30
 3650.24     526    7300     489    7540     488    7710     488    7810     486
    7850   486.1    7890     487    7930   487.1    8010     488    8023   486.9
    8030     487    8130     450    8450     450    8600     487    8716   487.4
    8752     488    8756   485.4    8992   485.4    9032   462.6    9037   460.5
    9060     460    9098   462.5    9116   467.8    9129   471.2    9171   485.7
    9214   491.2    9266   498.4    9335   514.6    9355   514.6    9416     520
#Mann= 3 ,0,0
 3650.24     .13       0    8992    .065       0    9171    .075       0
#XS Ineff= 2 , 0
       0    7540     510               0
Permanent Ineff=
       F       F
#Block Obstruct= 2 ,-1
                            8010    8600     487
Bank Sta=8992,9171
XS Rating Curve= 0 ,0
Exp/Cntr=0.3,0.1

Type RM Length L Ch R = 1 ,171852  ,3799,6655,1500
BEGIN DESCRIPTION:
This cross section corresponds to cross section 171900 of the non-georeferenced CDC model which was the source of this model.
END DESCRIPTION:
XS GIS Cut Line= 6
      2364335.62     6975595.769     2365304.911     6974387.828
      2366385.73     6973040.899     2366385.835     6973040.772
     2366938.192     6972375.978     2367230.553     6971480.706
#Sta/Elev= 30
    3700     526    5300   488.4    5350   489.9    5410     494    5430     494
    5510   488.7    5590   481.9    5610   481.6    5830   484.8    5950     488
    6850     488    6935     490    7293   490.1    7294   470.1    7341   470.1
    7385   459.7    7390     458    7395     455    7430   454.5    7440   453.5
    7442     458    7444   459.7    7459   466.2    7493   489.8    8024   486.7
    8114     485    8512     487    8676     496    8751   501.9    8782     510
#Mann= 3 ,0,0
    3700      .1       0    7293    .065       0    7493     .07       0
#XS Ineff= 2 , 0
       0    5300     500               0
Permanent Ineff=
       F       F
Bank Sta=7293,7493
XS Rating Curve= 0 ,0
Exp/Cntr=0.3,0.1

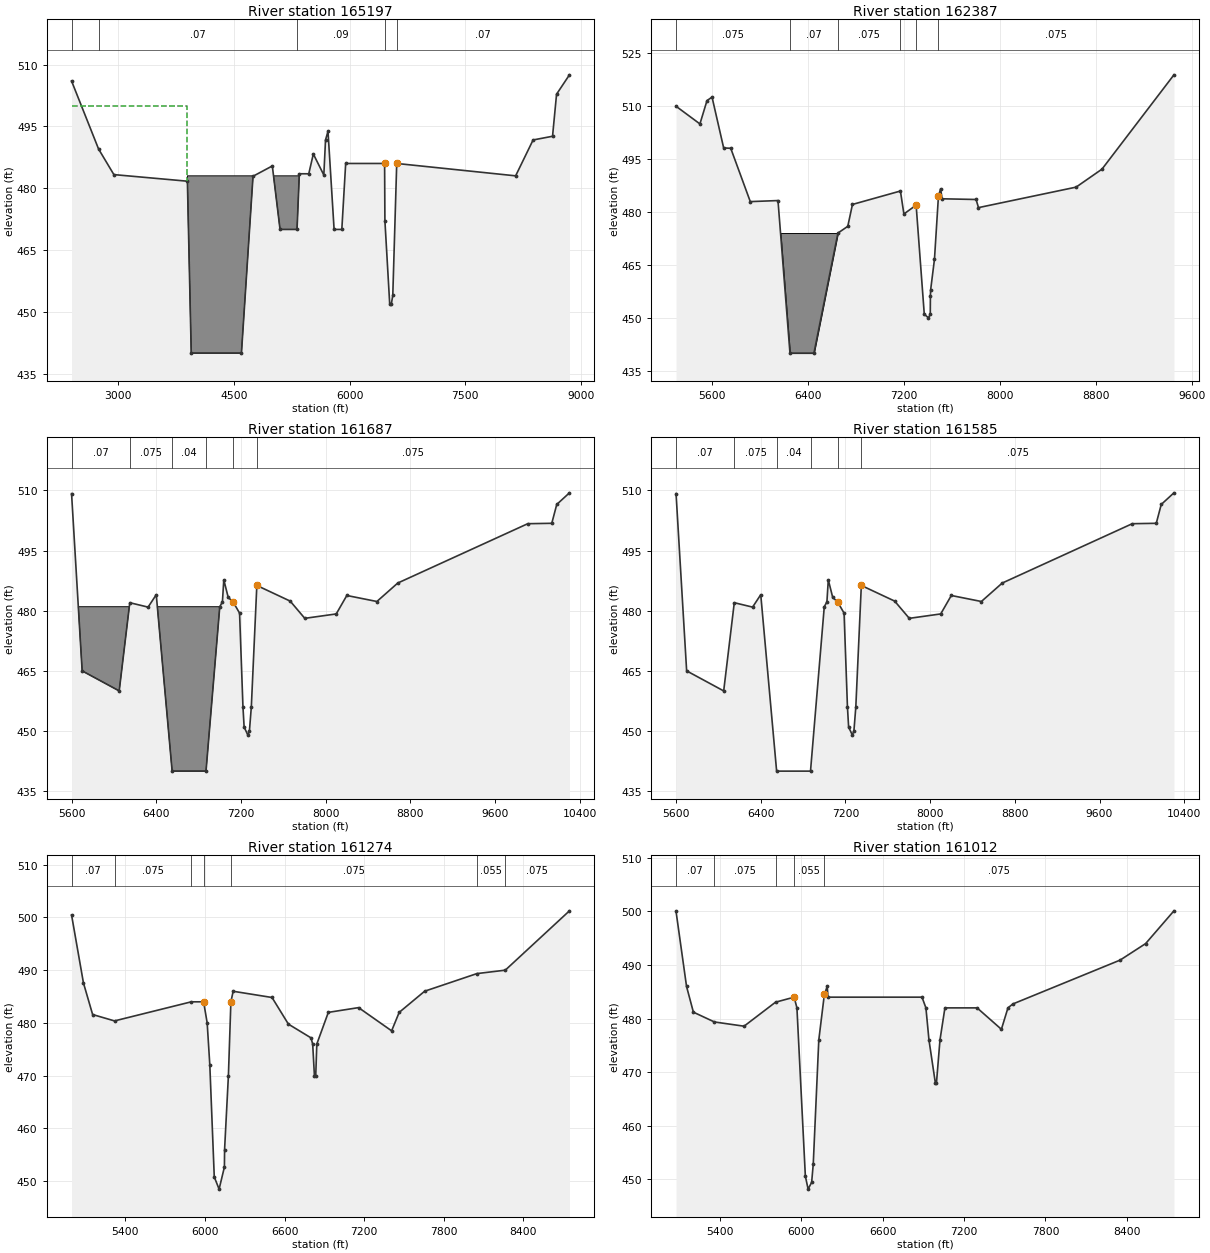
Type RM Length L Ch R = 1 ,165197  ,2402,2810,1151
BEGIN DESCRIPTION:
This cross section corresponds to cross section 165243 of the non-georeferenced CDC model which was the source of this model.
END DESCRIPTION:
XS GIS Cut Line= 5
 2368877.65286136977838.04796955  2368850.022491 6977489.1402989
  2368841.654436 6977383.4711187   2368586.11687   6974156.62297
 2368418.6193932  6971406.669799
#Sta/Elev= 30
    2400     506    2750   489.5    2948   483.3    3900   481.7    3950     440
    4600     440    4750   482.9    5000   485.4    5100     470    5320     470
    5350   483.5    5472   483.5    5531   488.3    5667   483.2    5689   491.7
    5721   493.8    5800     470    5900     470    5950     486    6454     486
    6458   472.1    6520     452    6540   451.8    6560     454    6611     486
    8151     483    8377   491.7    8629   492.6    8681   502.8    8848   507.5
#Mann= 5 ,-1,0
    2400     .07       0    2750     .07       0    5320     .09       0
    6454    .055       0    6611     .07       0
#XS Ineff= 2 , 0
       0    3900     500               0
Permanent Ineff=
       F       F
#Block Obstruct= 2 ,-1
                         3900.01    5350     483
Bank Sta=6454,6611
XS Rating Curve= 0 ,0
Exp/Cntr=0.3,0.1

Type RM Length L Ch R = 1 ,162387  ,409,699,898
BEGIN DESCRIPTION:
This cross section corresponds to cross section 162435 of the non-georeferenced CDC model which was the source of this model.
END DESCRIPTION:
XS GIS Cut Line= 5
  2370426.727748 6974782.1451209  2370394.404979 6974574.6475581
   2370223.44003    6973477.1299   2369682.57891   6972486.03904
  2369181.567299  6970859.262461
#Sta/Elev= 30
    5300   509.9    5499   504.9    5558   511.5    5600   512.5    5697   498.1
    5756     498    5919   482.9    6150   483.2    6250     440    6450     440
    6650     474    6732   475.9    6771   482.1    7171   485.9    7200   479.4
    7302   481.9    7370     451    7405     450    7420     451    7421   456.2
    7423   457.9    7455   466.6    7488   484.4    7506   486.5    7519   483.7
    7802   483.5    7822   481.2    8636     487    8852   492.1    9452   518.8
#Mann= 6 ,-1,0
    5300    .075       0    6250     .07       0    6650    .075       0
    7171     .12       0    7302    .055       0    7488    .075       0
#Block Obstruct= 2 , 0
       0    6650     474               0
Bank Sta=7302,7488
XS Rating Curve= 0 ,0
Exp/Cntr=0.3,0.1

Type RM Length L Ch R = 1 ,161687  ,102,102,102
BEGIN DESCRIPTION:
This cross section corresponds to cross section 161734 of the non-georeferenced CDC model which was the source of this model.
Copied geometry from XS 161634
END DESCRIPTION:
XS GIS Cut Line= 4
  2370844.741162 6974390.6193323 2370578.9524015 6973223.3172414
 2370506.4023515 6972160.9483014 2369840.2425915 6969812.6291814
#Sta/Elev= 30
    5600   509.2    5700     465    6050     460    6150     482    6323   480.9
    6400     484    6550     440    6870     440    7000     481    7025   482.2
    7038   487.7    7080   483.3    7126   482.2    7187   479.4    7219     456
    7230     451    7265     449    7280     450    7298     456    7350   486.3
    7665   482.4    7803   478.1    8100   479.2    8200   483.8    8484   482.3
    8681   486.9    9909   501.7   10136   501.8   10183   506.5   10303   509.4
#Mann= 6 ,-1,0
    5600     .07       0    6150    .075       0    6550     .04       0
    6870     .12       0    7126    .055       0    7350    .075       0
#Block Obstruct= 2 , 0
       0    7000     481               0
Bank Sta=7126,7350
XS Rating Curve= 0 ,0
Exp/Cntr=0.3,0.1

Type RM Length L Ch R = 1 ,161585  ,294,311,209
BEGIN DESCRIPTION:
This cross section corresponds to cross section 161634 of the non-georeferenced CDC model which was the source of this model.
END DESCRIPTION:
XS GIS Cut Line= 4
  2370945.508721 6974390.7510709   2370679.71996   6973223.44898
   2370607.16991   6972161.08004   2369941.01015   6969812.76092
#Sta/Elev= 30
    5600   509.2    5700     465    6050     460    6150     482    6323   480.9
    6400     484    6550     440    6870     440    7000     481    7025   482.2
    7038   487.7    7080   483.3    7126   482.2    7187   479.4    7219     456
    7230     451    7265     449    7280     450    7298     456    7350   486.3
    7665   482.4    7803   478.1    8100   479.2    8200   483.8    8484   482.3
    8681   486.9    9909   501.7   10136   501.8   10183   506.5   10303   509.4
#Mann= 6 ,-1,0
    5600     .07       0    6150    .075       0    6550     .04       0
    6870     .12       0    7126    .055       0    7350    .075       0
#Block Obstruct= 2 , 0
            7000     481
Bank Sta=7126,7350
XS Rating Curve= 0 ,0
Exp/Cntr=0.3,0.1

Type RM Length L Ch R = 1 ,161274  ,294,263,204
BEGIN DESCRIPTION:
This cross section corresponds to cross section 161322 of the non-georeferenced CDC model which was the source of this model.
XS Added - GeoRas
END DESCRIPTION:
XS GIS Cut Line= 5
  2371141.137944 6973911.8172809  2371041.232307  6973473.047565
 2370986.2134367 6973231.4134114 2370913.6633867 6972169.0444714
  2370370.311757 6970253.6435459
#Sta/Elev= 30
 4994.13  500.46 5083.83  487.57 5152.95  481.59 5317.95  480.38 5896.74     484
 5989.66     484 6016.54     480 6036.48     472 6069.98   450.8 6106.45  448.49
 6146.49  452.69 6147.77     456 6176.58     470 6195.34     484 6212.49     486
 6505.46  484.82 6628.92  479.77 6799.09  477.17 6811.98     476 6825.03     470
 6834.98     470 6843.11     476 6929.92     482 7157.98   482.9 7407.05   478.5
 7464.19     482 7656.11  486.01    8050  489.35    8264     490 8747.77  501.25
#Mann= 7 ,-1,0
 4994.13     .07       0 5317.95    .075       0 5896.74     .13       0
 5989.66    .055       0 6195.34    .075       0    8050    .055       0
    8264    .075       0
#XS Ineff= 2 , 0
       0 5989.66     484 6195.34       0     484
Permanent Ineff=
       F       F
Bank Sta=5989.66,6195.34
XS Rating Curve= 0 ,0
Exp/Cntr=0.3,0.1

Type RM Length L Ch R = 1 ,161012  ,210,180,216
BEGIN DESCRIPTION:
This cross section corresponds to cross section 161058 of the non-georeferenced CDC model which was the source of this model.
XS Added - GeoRas
END DESCRIPTION:
XS GIS Cut Line= 5
  2371381.326327 6973819.5147058 2371281.4206906 6973380.7449899
 2371245.0484877 6973221.0040425 2371172.4984377 6972158.6351025
  2370629.146808  6970243.234177
#Sta/Elev= 30
 5077.54     500 5154.87     486 5205.27   481.2 5360.23  479.37 5578.87  478.58
 5810.58  483.06  5947.8     484 5968.42     482 6030.53  450.58 6050.93  448.16
 6076.94  449.43 6088.79  452.85 6129.57     476 6170.58   484.5 6191.54     486
 6197.76     484 6890.25     484 6919.07     482 6941.59     476 6988.54     468
 6996.87     468 7022.73     476 7059.18     482 7296.28     482 7475.44     478
 7523.71     482 7559.85  482.73 8350.35  490.92 8538.28     494 8747.19  500.12
#Mann= 5 ,-1,0
 5077.54     .07       0 5360.23    .075       0 5810.58     .13       0
  5947.8    .055       0 6170.58    .075       0
Bank Sta=5947.8,6170.58
XS Rating Curve= 0 ,0
Exp/Cntr=0.3,0.1

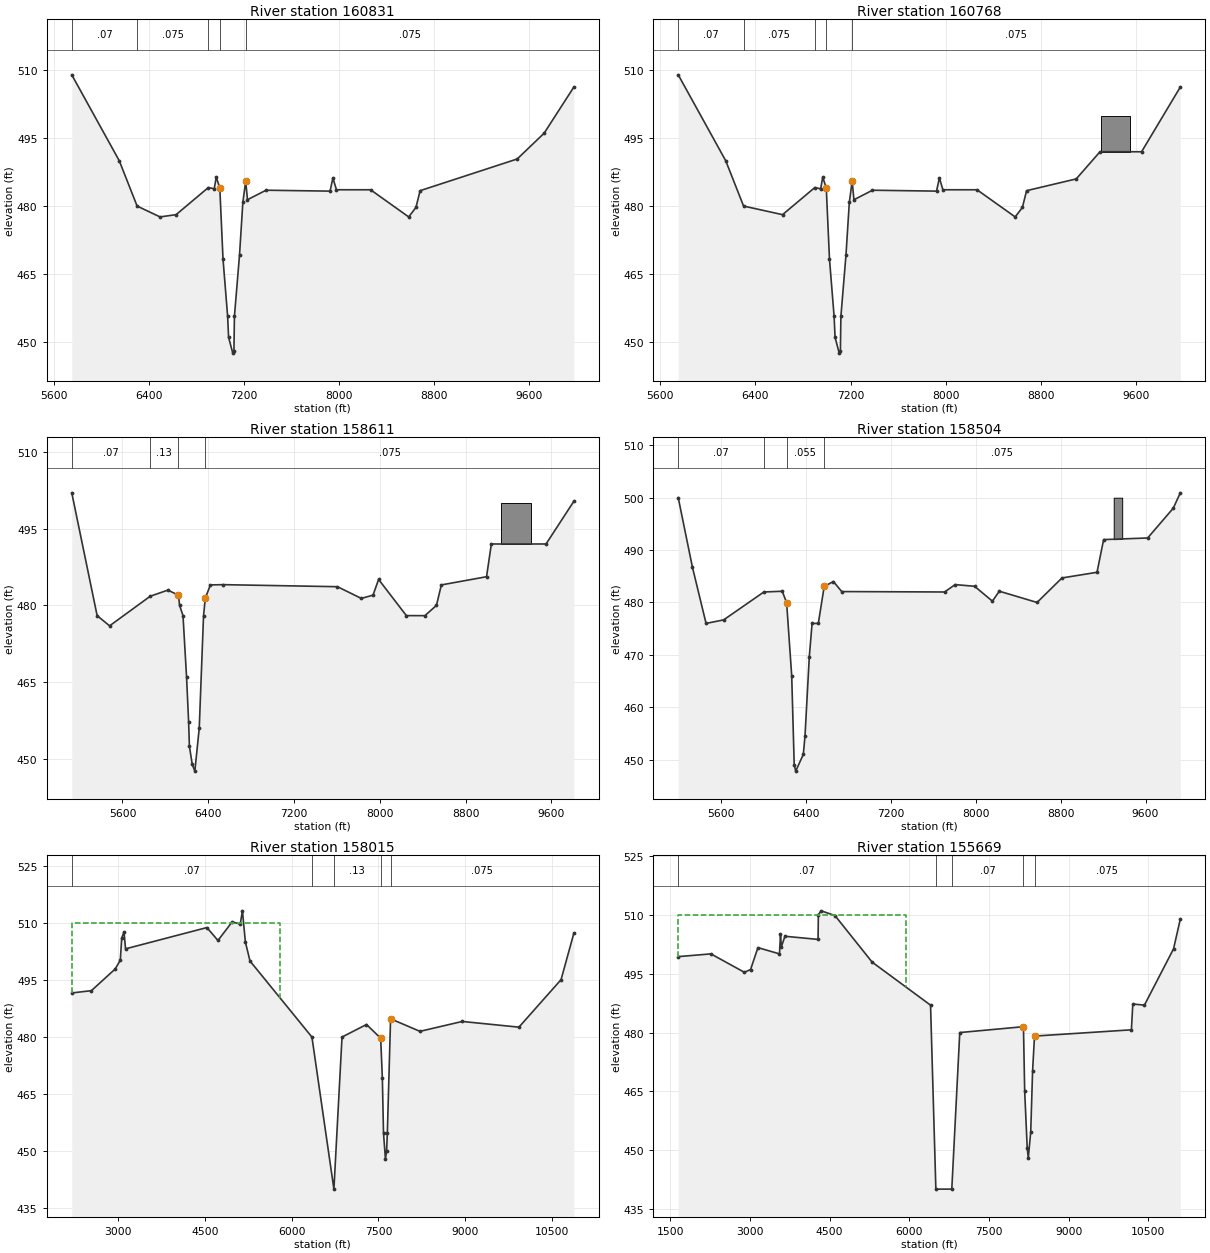
Type RM Length L Ch R = 1 ,160831  ,63,63,69
BEGIN DESCRIPTION:
This cross section corresponds to cross section 160878 of the non-georeferenced CDC model which was the source of this model.
END DESCRIPTION:
XS GIS Cut Line= 5
  2371682.359361 6974154.7699653 2371638.0012066 6973908.7367275
   2371508.76916   6973191.94904    2371131.2499   6971946.14904
 2370758.0835277 6970036.3538995
#Sta/Elev= 30
    5750     509    6150     490    6300     480    6493   477.6    6628   478.1
    6900   484.1    6949   483.8    6966   486.4    6996     484    7023   468.3
    7062   455.6    7070     451    7105   447.5    7115     448    7119   455.6
    7162   469.2    7190   480.8    7214   485.5    7229   481.4    7385   483.5
    7924   483.3    7948   486.2    7978   483.6    8265   483.6    8586   477.6
    8647   479.7    8682   483.4    9499   490.4    9726   496.1    9976   506.3
#Mann= 5 ,-1,0
    5750     .07       0    6300    .075       0    6900     .13       0
    6996    .055       0    7214    .075       0
Bank Sta=6996,7214
XS Rating Curve= 0 ,0
Exp/Cntr=0.3,0.1

Type RM Length L Ch R = 1 ,160768  ,819,2158,215
BEGIN DESCRIPTION:
This cross section corresponds to cross section 160778 of the non-georeferenced CDC model which was the source of this model.
Copied geometry from XS 160878
END DESCRIPTION:
XS GIS Cut Line= 5
  2371740.543566 6974131.6257075 2371696.1854117 6973885.5924697
 2371566.9533651 6973168.8047822 2371189.4341051 6971923.0047822
 2370816.2677328 6970013.2096417
#Sta/Elev= 30
    5750     509    6150     490    6300     480    6628   478.1    6900   484.1
    6949   483.8    6966   486.4    6996     484    7023   468.3    7062   455.6
    7070     451    7105   447.5    7115     448    7119   455.6    7162   469.2
    7190   480.8    7214   485.5    7229   481.4    7385   483.5    7924   483.3
    7948   486.2    7978   483.6    8265   483.6    8586   477.6    8647   479.7
    8682   483.4    9100     486    9300     492    9650     492    9976   506.3
#Mann= 5 ,-1,0
    5750     .07       0    6300    .075       0    6900     .13       0
    6996    .055       0    7214    .075       0
#XS Ineff= 2 , 0
       0    6996     484    7214       0   485.5
Permanent Ineff=
       F       F
#Block Obstruct= 1 ,-1
    9312    9555     500
Bank Sta=6996,7214
XS Rating Curve= 0 ,0
Exp/Cntr=0.3,0.1

Type RM Length L Ch R = 1 ,158611  ,116,106,126
BEGIN DESCRIPTION:
This cross section corresponds to cross section 158671 of the non-georeferenced CDC model which was the source of this model.
XS Added - GeoRas
END DESCRIPTION:
XS GIS Cut Line= 6
  2372586.090192 6973634.5653238  2372593.003609 6973507.8235619
      2372644.42     6972565.221     2372665.254     6972183.277
      2371363.17     6971554.804 2371175.1656432 6969781.7211204
#Sta/Elev= 30
 5126.93     502 5363.42     478 5479.76     476 5858.78  481.79 6022.87  482.98
 6122.02     482 6132.39     480 6164.25     478 6197.42     466 6216.78  457.17
 6223.95  452.45 6250.53  448.91 6274.73   447.6 6315.75     456  6355.8     478
 6372.34   481.4 6419.68     484 6540.09  484.05 7604.86  483.65 7827.09  481.36
 7936.19     482 7988.46  485.07 8247.14     478 8420.19  477.99 8527.93     480
 8573.68     484    8995   485.6    9040     492    9550     492 9809.22  500.35
#Mann= 4 ,-1,0
 5126.93     .07       0 5858.78     .13       0 6122.02    .055       0
 6372.34    .075       0
#XS Ineff= 2 , 0
       0 6122.02     482 6372.34       0   481.4
Permanent Ineff=
       F       F
#Block Obstruct= 1 ,-1
    9130    9405     500
Bank Sta=6122.02,6372.34
XS Rating Curve= 0 ,0
Exp/Cntr=0.3,0.1

Type RM Length L Ch R = 1 ,158504  ,1106,489,372
BEGIN DESCRIPTION:
This cross section corresponds to cross section 158651 of the non-georeferenced CDC model which was the source of this model.
XS Added - GeoRas
END DESCRIPTION:
XS GIS Cut Line= 6
  2372677.284238 6973766.6996845  2372688.846856 6973568.4868423
     2372748.587     6972544.388     2372772.893     6972127.721
     2371484.698     6971461.054 2371249.3614863 6969841.5680821
#Sta/Elev= 30
 5198.55     500 5331.68  486.78 5460.59     476 5626.01  476.67 6005.02     482
 6178.59  482.14 6219.46  479.93 6267.26     466 6290.82     449 6304.96   447.8
 6376.68     451 6392.39   454.5 6433.14  469.68 6459.26     476 6517.93     476
 6573.23  483.05 6659.85     484 6738.42  482.08 7707.49     482 7806.75  483.41
 7989.45  483.09 8157.59  480.25 8222.28  482.15 8578.14     480 8812.84  484.68
 9142.82  485.76    9205     492 9619.74  492.31 9861.11     498 9927.29  500.93
#Mann= 4 ,-1,0
 5198.55     .07       0 6005.02     .13       0 6219.46    .055       0
 6573.23    .075       0
#XS Ineff= 2 , 0
       0 6219.46  479.93 6573.23       0  483.05
Permanent Ineff=
       F       F
#Block Obstruct= 1 ,-1
    9300    9380     500
Bank Sta=6219.46,6573.23
XS Rating Curve= 0 ,0
Exp/Cntr=0.3,0.1

Type RM Length L Ch R = 1 ,158015  ,1000,2346,1699
BEGIN DESCRIPTION:
This cross section corresponds to cross section 158061 of the non-georeferenced CDC model which was the source of this model.
---------------------------------------------------------------------
CDC FW022307-01 Rocking River M Equestrian Center
Cross-section 158061 - 161734
Located in ROB.
---------------------------------------------------------------------
END DESCRIPTION:
XS GIS Cut Line= 5
  2374406.594046 6977251.9090106 2374375.1860997 6977087.8890701
   2373491.15988   6972471.28907   2371937.53995   6971431.67894
 2371264.0377802  6969613.238869
#Sta/Elev= 30
    2200   491.6    2539   492.2    2950   497.9    3039   500.2    3063     506
    3103   507.7    3129   503.2    4535   508.8    4726   505.4    4972   510.3
    5111   509.7    5149   513.2    5200     505    5280     500    6350     480
    6730     440    6870     480    7293   483.3    7538   479.7    7567   469.2
    7587   454.7    7620     448    7640     450    7653   454.7    7709   484.8
    8217   481.5    8947   484.1    9927   482.6   10655   495.1   10876   507.3
#Mann= 5 ,-1,0
    2200     .07       0    6350     .06       0    6730     .13       0
    7538    .055       0    7709    .075       0
#XS Ineff= 2 , 0
       0    5800     510               0
Permanent Ineff=
       F       F
#Block Obstruct= 2 , 0
            6870     480
Bank Sta=7538,7709
XS Rating Curve= 0 ,0
Exp/Cntr=0.3,0.1

Type RM Length L Ch R = 1 ,155669  ,350,1187,1499
BEGIN DESCRIPTION:
This cross section corresponds to cross section 155714 of the non-georeferenced CDC model which was the source of this model.
END DESCRIPTION:
XS GIS Cut Line= 4
  2375216.900499 6977247.5845485   2374246.14885   6971151.04991
   2373326.55916   6970296.25897   2372405.52196   6968494.91907
#Sta/Elev= 30
    1650   499.4    2265   500.1    2895   495.4    3012   496.1    3150   501.7
    3556   500.1    3575   505.1    3591   501.9    3659   504.6    4282   503.8
    4288   510.1    4340   511.1    4600   509.9    5300     498    6400     487
    6500     440    6800     440    6950     480    8149   481.5    8172   465.1
    8220   450.5    8240     448    8286   454.6    8321   470.2    8357   479.1
   10181   480.7   10208   487.3   10426     487   10975   501.4   11102     509
#Mann= 5 ,-1,0
    1650     .07       0    6500     .04       0    6800     .07       0
    8149    .055       0    8357    .075       0
#XS Ineff= 2 , 0
       0    5933     510    8357       0   479.1
Permanent Ineff=
       F       F
#Block Obstruct= 2 , 0
            6950     480
Bank Sta=8149,8357
XS Rating Curve= 0 ,0
Exp/Cntr=0.3,0.1