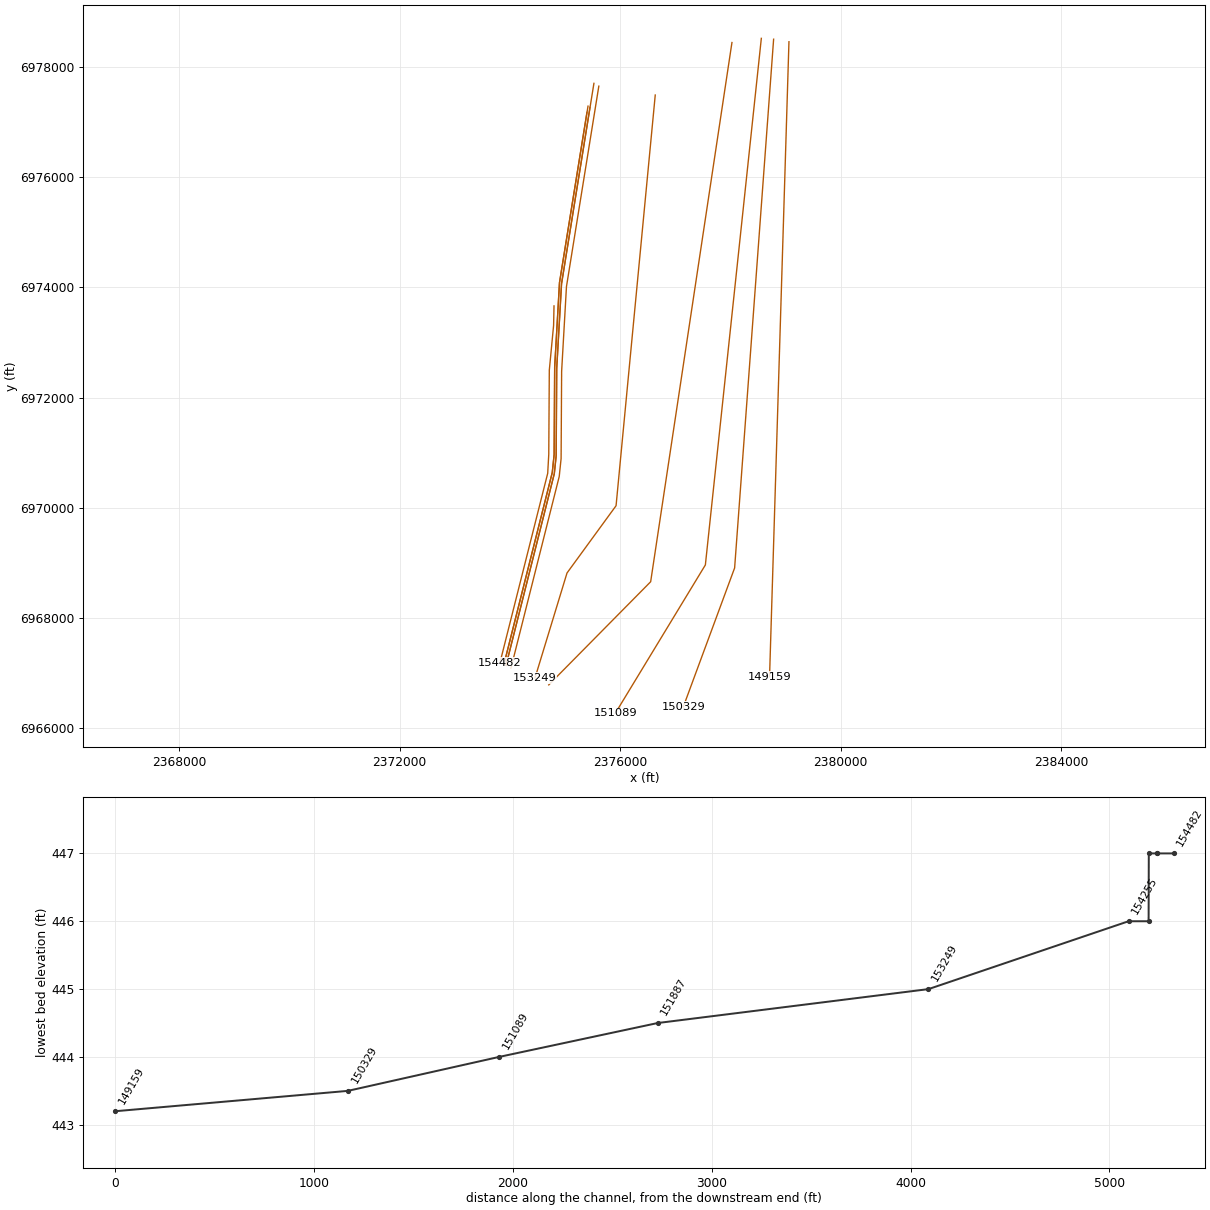
HEC-RAS study CDC_Consolidated_Model.prj: Upper Trinity CDC Consolidated Model

--- CDC_Consolidated_Model.g02 (geometry) --- (continued)

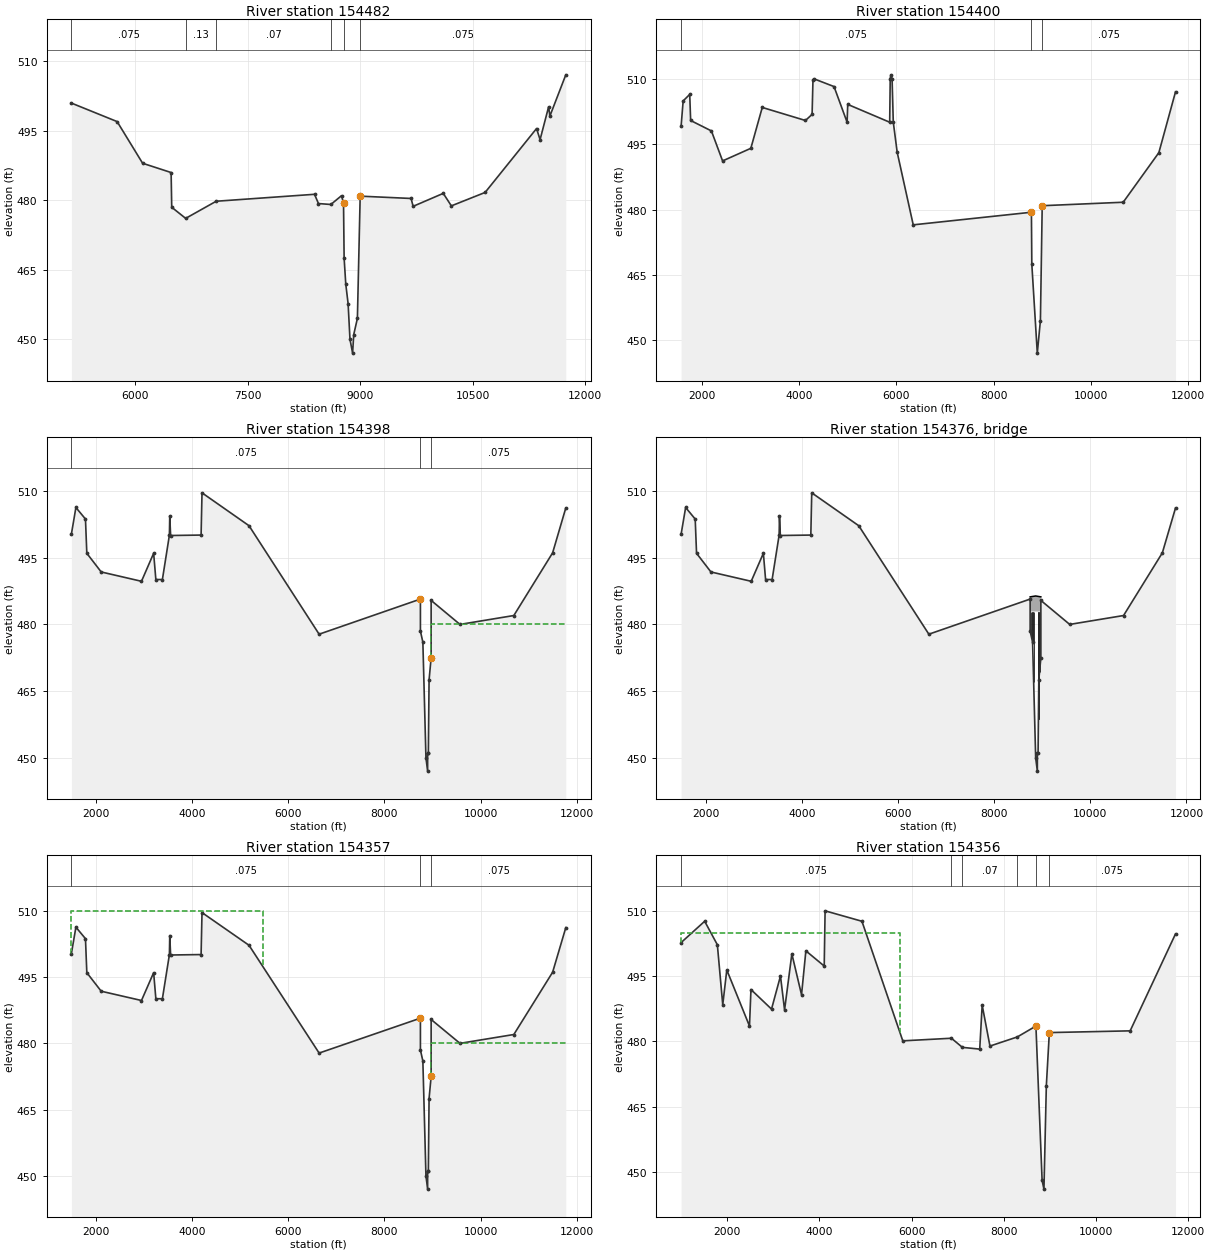
Type RM Length L Ch R = 1 ,154482  ,83,83,83
BEGIN DESCRIPTION:
This cross section corresponds to cross section 154527 of the non-georeferenced CDC model which was the source of this model.
END DESCRIPTION:
XS GIS Cut Line= 6
  2374800.699271 6973662.8791966   2374793.20189    6973308.0141
   2374715.41793     6972496.144   2374705.69485   6970969.63393
   2374686.24902   6970624.46796   2373819.26716     6967181.798
#Sta/Elev= 30
    5150     501    5760     497    6100     488    6480     486    6488   478.5
    6674   476.1    7081   479.8    8392   481.3    8445   479.3    8610   479.1
    8752     481    8779   479.4    8787   467.5    8809   461.9    8840   457.7
    8865     450    8900     447    8915     451    8964   454.5    9001   480.9
    9680   480.4    9707   478.7   10109   481.5   10217   478.8   10667   481.7
   11353   495.5   11400   493.1   11514   500.2   11531   498.2   11743   507.1
#Mann= 6 ,-1,0
    5150    .075       0    6674     .13       0    7081     .07       0
    8610     .13       0    8779    .055       0    9001    .075       0
#XS Ineff= 2 , 0
            8779   479.4    9001           480.9
Permanent Ineff=
       F       F
#Block Obstruct= 2 , 0
       0    5900                       0
Bank Sta=8779,9001
XS Rating Curve= 0 ,0
Exp/Cntr=0.3,0.1

Type RM Length L Ch R = 1 ,154400  ,1,1,1
BEGIN DESCRIPTION:
This cross section corresponds to cross section 154445 of the non-georeferenced CDC model which was the source of this model.
END DESCRIPTION:
XS GIS Cut Line= 6
  2375398.244882 6977175.2932533 2374899.9057473 6974085.5876751
 2374812.3987045 6972549.3545271 2374802.6756268 6970964.5066469
 2374768.6455112 6970638.7868259 2373893.0406351 6967159.7826291
#Sta/Elev= 30
    1574   499.2    1616     505    1751   506.5    1770   500.5    2197   498.1
    2427   491.2    3008   494.1    3243   503.5    4131   500.5    4268   501.9
    4286   509.8    4302   510.1    4719   508.3    4988   500.1    5001   504.2
    5864   500.1    5875   510.1    5888     511    5913   510.1    5938   500.1
    6018   493.2    6348   476.5    8779   479.4    8787   467.5    8900     447
    8964   454.5    9001   480.9   10667   481.7   11400   493.1   11743   507.1
#Mann= 3 ,0,0
    1574    .075       0    8779    .055       0    9001    .075       0
#XS Ineff= 2 , 0
            8779   479.4    9001           480.9
Permanent Ineff=
       F       F
#Block Obstruct= 2 , 0
            5750     511
Bank Sta=8779,9001
XS Rating Curve= 0 ,0
Exp/Cntr=0.3,0.1

Type RM Length L Ch R = 1 ,154398  ,41,41,41
BEGIN DESCRIPTION:
This cross section corresponds to cross section 154444 of the non-georeferenced CDC model which was the source of this model.
END DESCRIPTION:
XS GIS Cut Line= 6
   2375417.43061 6977288.3246735 2374900.7797613 6974085.0863637
 2374813.2727185 6972548.8532157 2374803.5496408 6970964.0053356
 2374769.5195252 6970638.2855146 2373893.9146491 6967159.2813177
#Sta/Elev= 30
    1490   500.3    1584   506.3    1783   503.7    1811     496    2110   491.8
    2948   489.7    3201     496    3247   490.1    3383   490.1    3529   500.1
    3536   504.4    3554     500    4188   500.1    4207   509.6    5185   502.2
    6643   477.8    8750   485.7    8750   478.5    8801     476    8865     450
    8900     447    8900     451    8915     451    8930   467.5    8973   472.5
    8973   485.4    9573     480   10693     482   11500   496.1   11774   506.2
#Mann= 3 ,0,0
    1490    .075       0    8750    .055       0    8973    .075       0
#XS Ineff= 2 , 0
       0    8750   477.8    8973       0     480
Permanent Ineff=
       F       F
#Block Obstruct= 2 , 0
       0    5750                       0
Bank Sta=8750,8973
XS Rating Curve= 0 ,0
Exp/Cntr=0.3,0.1

Type RM Length L Ch R = 3 ,154376  ,,,
BEGIN DESCRIPTION:
Precinct Line Road
END DESCRIPTION:
Node Name=Precinct Line Ro
Bridge Culvert--1,0,-1,-1, 0
Deck Dist Width WeirC Skew NumUp NumDn MinLoCord MaxHiCord MaxSubmerge Is_Ogee
1,38,2.6,0, 3, 3, , , 0.95, 0, ,,,
    8750    8865    8973
   486.2   486.4   486.2
   482.9   482.9   482.9
    8750    8865    8973
   486.2   486.4   486.2
   482.9   482.9   482.9
Pier Skew, UpSta & Num, DnSta & Num=  ,8771, 2 ,8771, 2 , 0 , 0 , 0 ,,
       2       2
     455     485
       2       2
     455     485
Pier Skew, UpSta & Num, DnSta & Num=  ,8799.5, 2 ,8799.5, 2 , 0 , 0 , 0 ,,
       3       3
     455     485
       3       3
     455     485
Pier Skew, UpSta & Num, DnSta & Num=  ,8823, 2 ,8823, 2 , 0 , 0 , 0 ,,
       4       4
     455     485
       4       4
     455     485
Pier Skew, UpSta & Num, DnSta & Num=  ,8922, 2 ,8922, 2 , 0 , 0 , 0 ,,
       4       4
     455     485
       4       4
     455     485
Pier Skew, UpSta & Num, DnSta & Num=  ,8946, 2 ,8946, 2 , 0 , 0 , 0 ,,
       2       2
     455     485
       2       2
     455     485
BR Coef= 1 , 0 , 0 ,1.05, 0 ,,,0.8,-1,0.5,1,
WSPro=,,,, 1 ,,,, 0 ,,,, 0 ,,,,-1 ,-1 ,-1 , 0 , 0 , 0 , 0 , 0
BC Design=,, 0 ,, 0 ,,,,,,
BC HTab HWMax=506.2
BC Use User HTab Curves=0
BC User HTab FreeFlow(D)= 0

Type RM Length L Ch R = 1 ,154357  ,1,1,1
BEGIN DESCRIPTION:
This cross section corresponds to cross section 154404 of the non-georeferenced CDC model which was the source of this model.
END DESCRIPTION:
XS GIS Cut Line= 6
  2375453.266234 6977267.7661527 2374936.6153862 6974064.5278488
 2374849.1083362 6972528.2946988 2374839.3852662 6970943.4468188
 2374805.3551462 6970617.7269988 2373929.7502662 6967138.7227988
#Sta/Elev= 30
    1490   500.3    1584   506.3    1783   503.7    1811     496    2110   491.8
    2948   489.7    3201     496    3247   490.1    3383   490.1    3529   500.1
    3536   504.4    3554     500    4188   500.1    4207   509.6    5185   502.2
    6643   477.8    8750   485.7    8750   478.5    8801     476    8865     450
    8900     447    8900     451    8915     451    8930   467.5    8973   472.5
    8973   485.4    9573     480   10693     482   11500   496.1   11774   506.2
#Mann= 3 ,0,0
    1490    .075       0    8750    .055       0    8973    .075       0
#XS Ineff= 2 , 0
       0    5466     510    8973       0     480
Permanent Ineff=
       F       F
#Block Obstruct= 2 , 0
       0    5750                       0
Bank Sta=8750,8973
XS Rating Curve= 0 ,0
Exp/Cntr=0.3,0.1

Type RM Length L Ch R = 1 ,154356  ,101,101,101
BEGIN DESCRIPTION:
This cross section corresponds to cross section 154403 of the non-georeferenced CDC model which was the source of this model.
END DESCRIPTION:
XS GIS Cut Line= 6
     2375524.327     6977702.037      2374937.62      6974064.48
      2374850.14      6972528.37      2374840.39      6970943.44
      2374806.35      6970617.86      2373930.66      6967138.23
#Sta/Elev= 30
    1000   502.7    1511   507.6    1786   502.2    1903   488.4    1991   496.4
    2483   483.5    2515   491.9    2961   487.4    3155     495    3244   487.2
    3402   500.1    3612   490.7    3706   500.8    4104   497.3    4123     510
    4922   507.6    5808   480.1    6863   480.7    7101   478.6    7477   478.2
    7530   488.3    7699   478.9    8293     481    8696   483.5    8830     448
    8870     446    8922   469.8    8987     482   10740   482.4   11724   504.7
#Mann= 6 ,-1,0
    1000    .075       0    6863     .13       0    7101     .07       0
    8293     .12       0    8696    .055       0    8987    .075       0
#XS Ineff= 3 ,-1
    1000    5750     505    5750    8696   480.1    8987   11724     482
Permanent Ineff=
       F       F       F
Bank Sta=8696,8987
XS Rating Curve= 0 ,0
Exp/Cntr=0.3,0.1

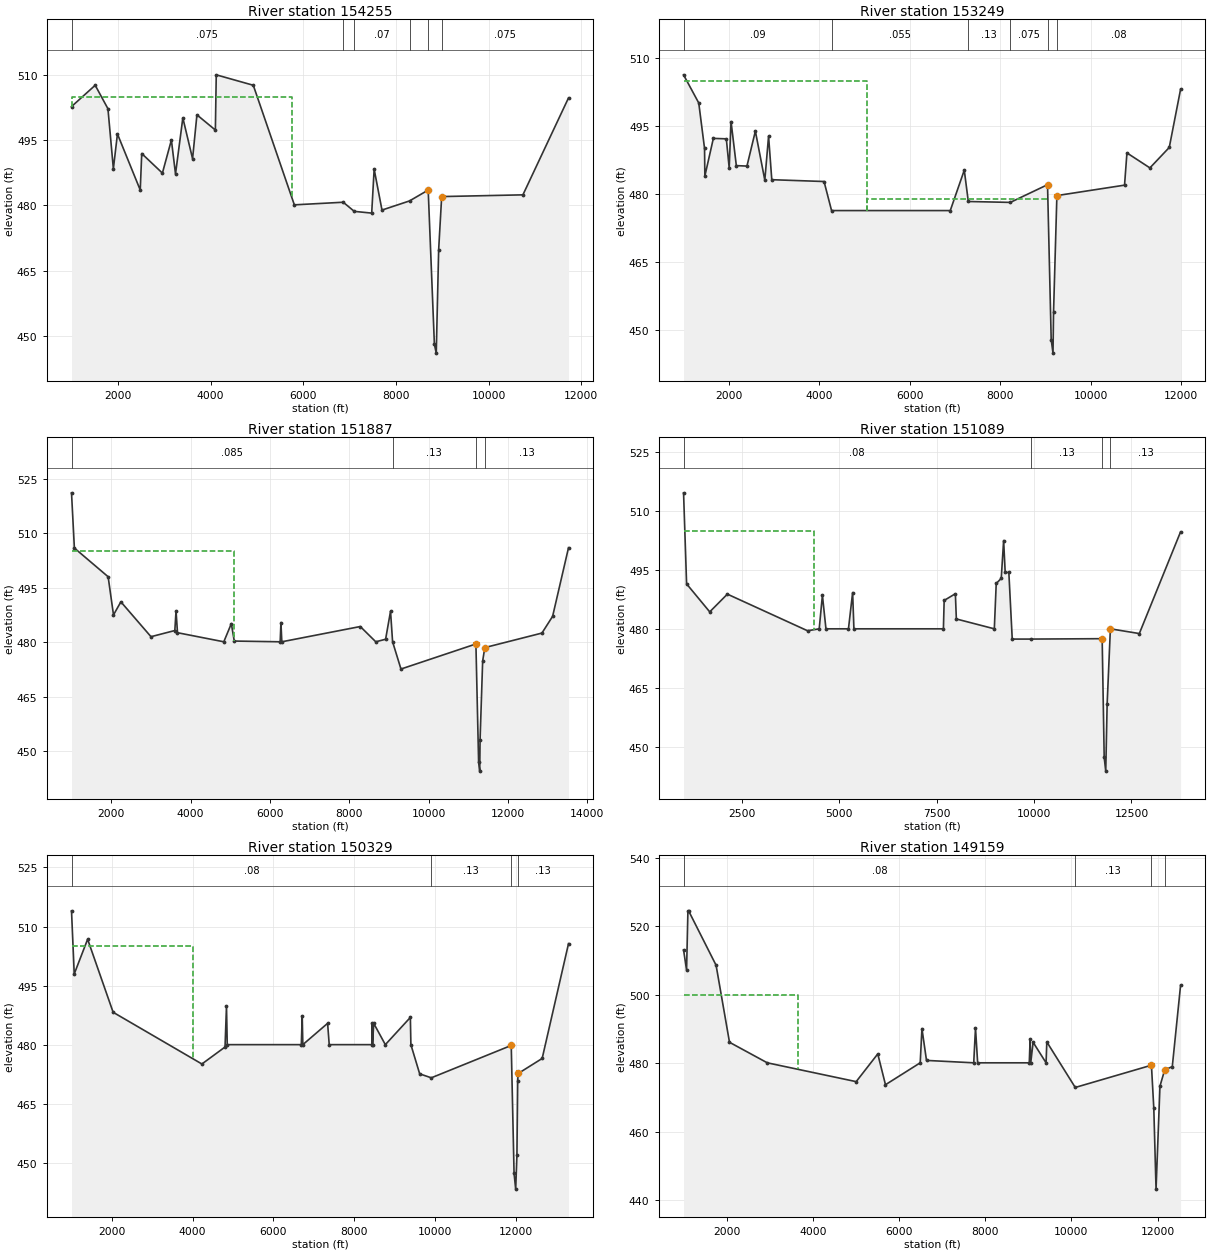
Type RM Length L Ch R = 1 ,154255  ,1198,1006,599
BEGIN DESCRIPTION:
This cross section corresponds to cross section 154301 of the non-georeferenced CDC model which was the source of this model.
END DESCRIPTION:
XS GIS Cut Line= 6
  2375613.267176 6977650.5554074   2375026.55412     6974012.931
   2374939.04707   6972476.69785     2374929.324   6970891.84997
   2374895.29388   6970566.13015     2374019.689   6967087.12595
#Sta/Elev= 30
    1000   502.7    1511   507.6    1786   502.2    1903   488.4    1991   496.4
    2483   483.5    2515   491.9    2961   487.4    3155     495    3244   487.2
    3402   500.1    3612   490.7    3706   500.8    4104   497.3    4123     510
    4922   507.6    5808   480.1    6863   480.7    7101   478.6    7477   478.2
    7530   488.3    7699   478.9    8293     481    8696   483.5    8830     448
    8870     446    8922   469.8    8987     482   10740   482.4   11724   504.7
#Mann= 6 ,-1,0
    1000    .075       0    6863     .13       0    7101     .07       0
    8293     .12       0    8696    .055       0    8987    .075       0
#XS Ineff= 3 ,-1
    1000    5750     505    5750    8696   480.1    8987   11724     482
Permanent Ineff=
       F       F       F
Bank Sta=8696,8987
XS Rating Curve= 0 ,0
Exp/Cntr=0.3,0.1

Type RM Length L Ch R = 1 ,153249  ,860,1362,950
BEGIN DESCRIPTION:
This cross section corresponds to cross section 153293 of the non-georeferenced CDC model which was the source of this model.
END DESCRIPTION:
XS GIS Cut Line= 5
  2376636.239987 6977489.8100756   2376636.19985   6977489.38894
   2375925.88992   6970036.66008    2375036.4291   6968815.61888
   2374455.51884   6966908.72014
#Sta/Elev= 30
    1000   506.3    1336   500.1    1464   490.1    1471     484    1659   492.3
    1946   492.2    2009   485.8    2050     496    2167   486.3    2402   486.2
    2588   493.9    2797   483.1    2880   492.8    2951   483.2    4107   482.8
    4273   476.4    6898   476.4    7208   485.3    7297   478.4    8226   478.2
    9049   482.1    9130     448    9170     445    9182     454    9256   479.7
   10752     482   10805   489.1   11313   485.8   11741   490.3   11991   503.1
#Mann= 6 ,-1,0
    1000     .09       0    4273    .055       0    7297     .13       0
    8226    .075       0    9049    .055       0    9256     .08       0
#XS Ineff= 3 ,-1
    1000    5050     505    5050    9049     479    9256   11991   479.7
Permanent Ineff=
       F       F       F
Bank Sta=9049,9256
XS Rating Curve= 0 ,0
Exp/Cntr=0.3,0.1

Type RM Length L Ch R = 1 ,151887  ,802,798,1053
BEGIN DESCRIPTION:
This cross section corresponds to cross section 151932 of the non-georeferenced CDC model which was the source of this model.
END DESCRIPTION:
XS GIS Cut Line= 3
   2378026.87631 6978442.6383771   2376553.11898   6968657.02012
   2374705.68993   6966785.11015
#Sta/Elev= 30
    1000   521.1    1072   505.9    1923     498    2058   487.5    2244   491.1
    3003   481.5    3604   483.2    3634   488.6    3671   482.6    4838   480.1
    5028   485.1    5102   480.3    6259   480.1    6278   485.4    6300   480.1
    8278   484.3    8668   480.1    8916   480.8    9040   488.5    9092   480.1
    9303   472.6   11192   479.5   11260     447   11288   444.5   11297   453.2
   11362   474.8   11416   478.5   12856   482.5   13125   487.1   13526     506
#Mann= 4 ,-1,0
    1000    .085       0    9092     .13       0   11192     .05       0
   11416     .13       0
#XS Ineff= 3 ,-1
    1000    5100     505    5100   11192   475.6   11416   13526   477.5
Permanent Ineff=
       F       F       F
Bank Sta=11192,11416
XS Rating Curve= 0 ,0
Exp/Cntr=0.3,0.1

Type RM Length L Ch R = 1 ,151089  ,429,760,898
BEGIN DESCRIPTION:
This cross section corresponds to cross section 151136 of the non-georeferenced CDC model which was the source of this model.
END DESCRIPTION:
XS GIS Cut Line= 6
  2378559.604136 6978518.6939663 2378062.9548674 6973839.7476156
 2377819.8549599 6971550.0546884 2377544.9998666 6968961.7101276
 2376505.2814736 6967247.5255638 2375911.1061527 6966268.0068536
#Sta/Elev= 30
    1000   514.6    1078   491.5    1672   484.4    2125   488.9    4185   479.6
    4483   480.1    4565   488.6    4656   480.1    5234   480.1    5341   489.3
    5374   480.1    7672   480.1    7691   487.3    7979     489    8004   482.6
    8979   480.1    9028   491.6    9157   492.9    9218   502.5    9258   494.4
    9352   494.4    9439   477.5    9914   477.5   11748   477.6   11800   447.5
   11840     444   11876   461.1   11959   480.1   12702   478.9   13761   504.7
#Mann= 4 ,-1,0
    1000     .08       0    9914     .13       0   11748     .05       0
   11959     .13       0
#XS Ineff= 3 ,-1
    1000    4350     505    4350   11748     473   11959   13761   478.9
Permanent Ineff=
       F       F       F
Bank Sta=11748,11959
XS Rating Curve= 0 ,0
Exp/Cntr=0.3,0.1

Type RM Length L Ch R = 1 ,150329  ,549,1170,1358
BEGIN DESCRIPTION:
This cross section corresponds to cross section 150374 of the non-georeferenced CDC model which was the source of this model.
END DESCRIPTION:
XS GIS Cut Line= 3
   2378782.41111   6978502.98599   2378075.32886       6968907.1
 2377143.8019386 6966383.4347682
#Sta/Elev= 30
    1000     514    1067     498    1399   506.8    2031   488.3    4230   475.2
    4803   479.5    4839   489.9    4858   480.1    6693   480.1    6715   487.4
    6730   480.1    7344   485.5    7384   480.1    8442   480.1    8451   485.5
    8457   480.1    8486   485.5    8774   480.1    9394     487    9407   480.1
    9625   472.7    9913   471.7   11893   479.9   11963   447.5   12003   443.5
   12034   452.1   12053     471   12066   472.8   12659   476.6   13312   505.7
#Mann= 4 ,-1,0
    1000     .08       0    9913     .13       0   11893     .05       0
   12066     .13       0
#XS Ineff= 3 ,-1
    1000    4000     505    4000   11893     473   12066   13312   472.8
Permanent Ineff=
       F       F       F
Bank Sta=11893,12066
XS Rating Curve= 0 ,0
Exp/Cntr=0.3,0.1

Type RM Length L Ch R = 1 ,149159  ,480,539,550
BEGIN DESCRIPTION:
This cross section corresponds to cross section 149202 of the non-georeferenced CDC model which was the source of this model.
END DESCRIPTION:
XS GIS Cut Line= 2
  2379060.506912 6978457.0551653   2378708.55692   6966928.42614
#Sta/Elev= 30
    1000   513.1    1070   507.2    1101   524.4    1117   524.5    1755   508.6
    2066   486.1    2943   480.1    5006   474.6    5507   482.7    5686   473.7
    6492   480.1    6532   490.1    6638   480.8    7734   480.1    7775   490.3
    7825   480.1    9023   480.1    9043   487.1    9057   480.1    9112   486.1
    9413   480.1    9430   486.2   10090   472.9   11858   479.4   11913   466.8
   11965   443.2   12056   473.3   12165     478   12342     479   12534   502.7
#Mann= 4 ,-1,0
    1000     .08       0   10090     .13       0   11858     .05       0
   12165     .12       0
#XS Ineff= 3 ,-1
    1000    3650     500    3650   11858     473   12165   12534   476.5
Permanent Ineff=
       F       F       F
Bank Sta=11858,12165
XS Rating Curve= 0 ,0
Exp/Cntr=0.3,0.1