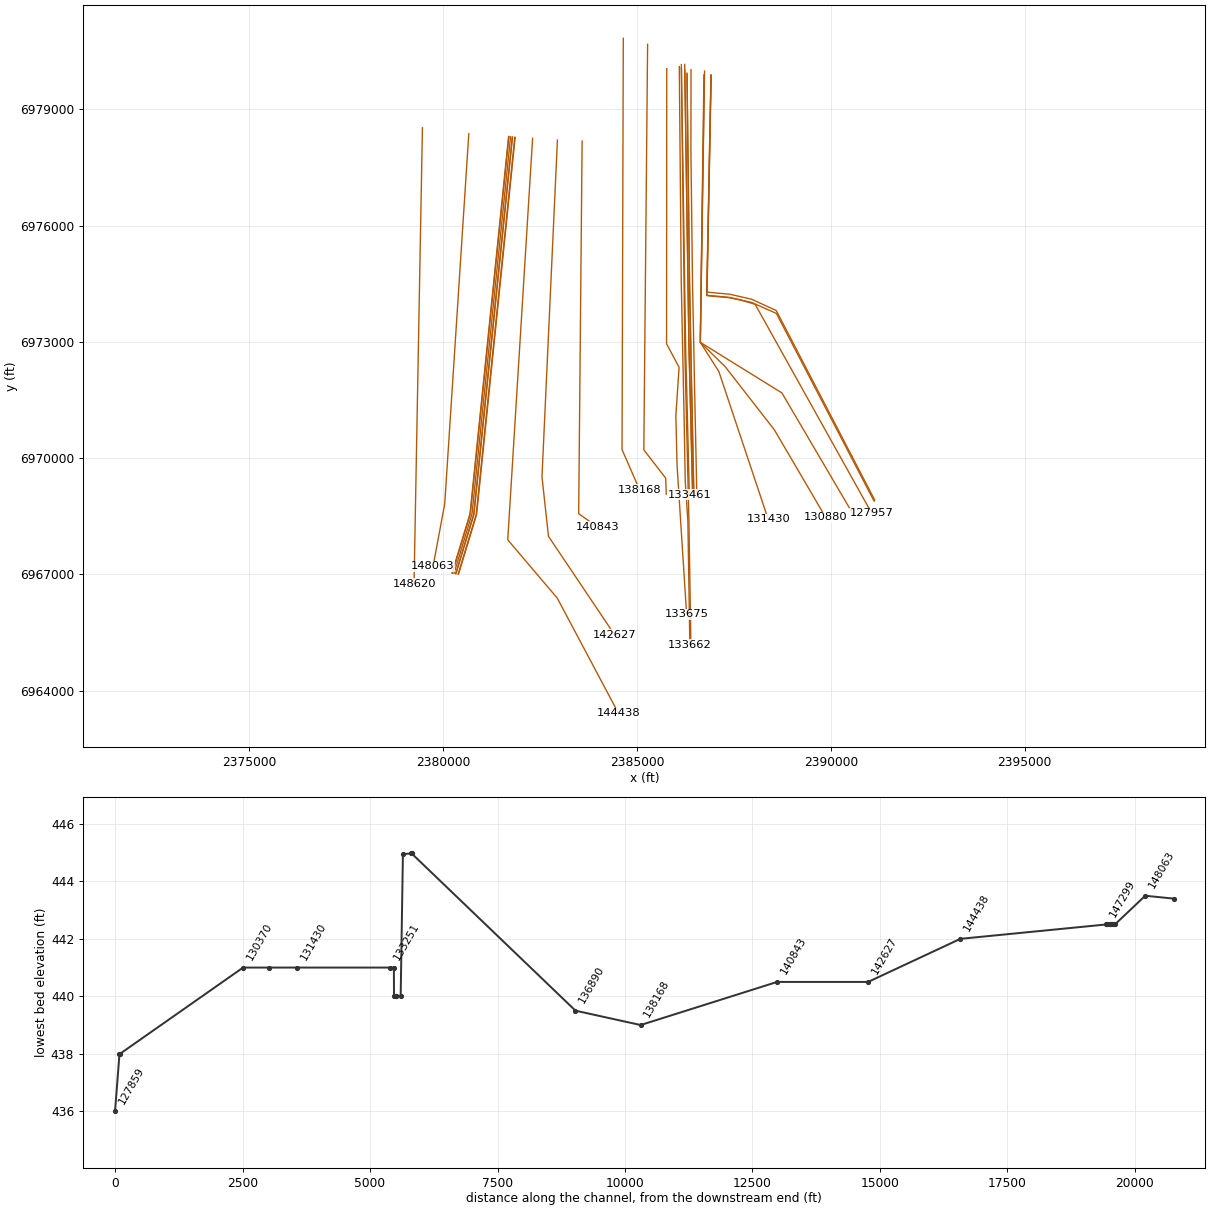
HEC-RAS study CDC_Consolidated_Model.prj: Upper Trinity CDC Consolidated Model

--- CDC_Consolidated_Model.g02 (geometry) --- (continued)

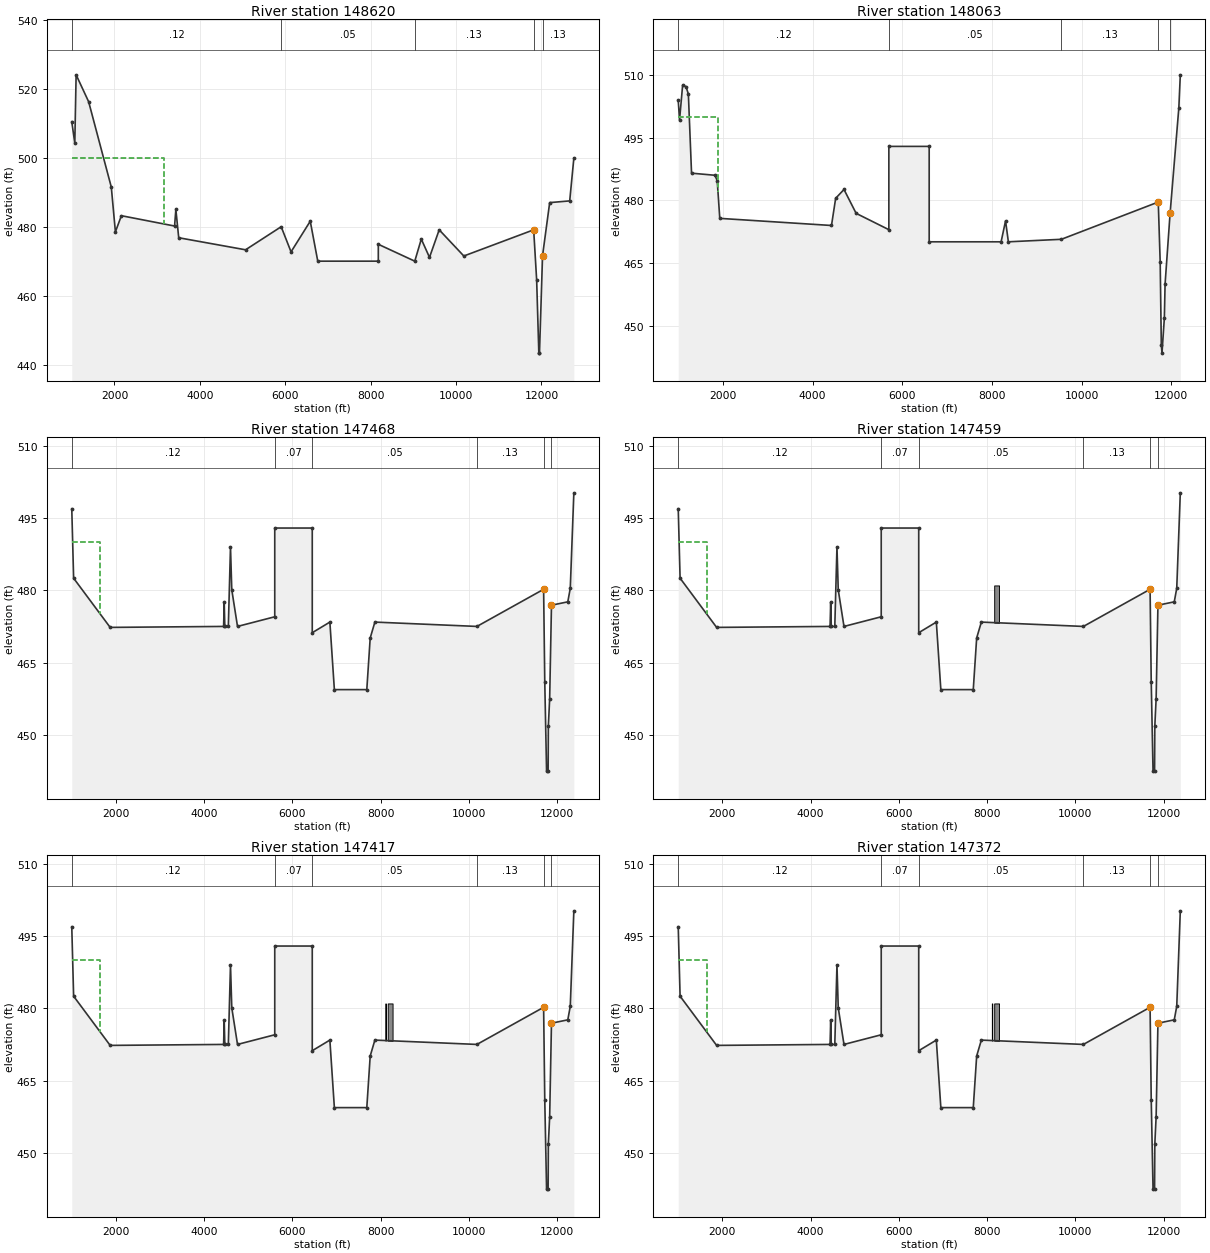
Type RM Length L Ch R = 1 ,148620  ,899,557,500
BEGIN DESCRIPTION:
This cross section corresponds to cross section 148663 of the non-georeferenced CDC model which was the source of this model.
END DESCRIPTION:
XS GIS Cut Line= 3
  2379467.410259 6978522.3299658   2379466.17516   6978455.19901
   2379251.08208   6966764.31984
#Sta/Elev= 30
    1000   510.6    1071   504.4    1102   524.2    1395   516.4    1926   491.6
    2022   478.6    2162   483.3    3408   480.3    3438   485.1    3505   476.9
    5071   473.4    5905   480.1    6136   472.8    6586   481.7    6762   470.1
    8180   470.1    8180     475    9034   470.1    9187   476.5    9379   471.2
    9606   479.2   10183   471.6   11819   479.2   11889   464.6   11940   443.4
   11955   443.4   12027   471.7   12194   487.1   12663   487.6   12760     500
#Mann= 5 ,-1,0
    1000     .12       0    5905     .05       0    9034     .13       0
   11819     .05       0   12027     .13       0
#XS Ineff= 3 ,-1
    1000    3150     500    3150   11819   473.1   12027   12760   471.7
Permanent Ineff=
       F       F       F
Bank Sta=11819,12027
XS Rating Curve= 0 ,0
Exp/Cntr=0.3,0.1

Type RM Length L Ch R = 1 ,148063  ,801,595,551
BEGIN DESCRIPTION:
This cross section corresponds to cross section 148106 of the non-georeferenced CDC model which was the source of this model.
END DESCRIPTION:
XS GIS Cut Line= 3
  2380663.686699 6978368.9249946   2380042.69008   6968821.25011
   2379742.11588   6967212.94492
#Sta/Elev= 30
    1000   503.9    1029   499.2    1098   507.5    1173   507.2    1226   505.4
    1297   486.5    1819     486    1870   484.7    1927   475.7    4420     474
    4513   480.5    4699   482.6    4970   476.9    5700     473    5700   492.9
    6600   492.9    6600   470.1    8205   470.1    8304   475.1    8367   470.1
    9550   470.7   11712   479.6   11755   465.2   11780   445.5   11795   443.5
   11848   451.9   11864     460   11976   476.9   12171   502.1   12204     510
#Mann= 5 ,-1,0
    1000     .12       0    5700     .05       0    9550     .13       0
   11712     .05       0   11976     .13       0
#XS Ineff= 2 , 0
       0    1887     500               0
Permanent Ineff=
       F       F
Bank Sta=11712,11976
XS Rating Curve= 0 ,0
Exp/Cntr=0.3,0.1

Type RM Length L Ch R = 1 ,147468  ,9,9,9
BEGIN DESCRIPTION:
This cross section corresponds to cross section 147512 of the non-georeferenced CDC model which was the source of this model.
END DESCRIPTION:
XS GIS Cut Line= 5
  2381689.690602 6978296.0682551   2381689.67596   6978295.92505
   2380694.93189   6968566.94484   2380231.07586   6967037.73793
  2380231.034075 6967037.6001762
#Sta/Elev= 30
    1000   496.9    1042   482.5    1870   472.3    4441   472.5    4455   477.5
    4468   472.5    4548   472.5    4597     489    4626   480.1    4756   472.5
    5600   474.5    5600   492.9    6450   492.9    6450   471.2    6849   473.4
    6951   459.4    7686   459.4    7763   470.1    7869   473.4   10182   472.5
   11693   480.2   11719     461   11760   442.5   11795   442.5   11800   451.8
   11830   457.5   11871   476.9   12241   477.6   12297   480.4   12378   500.2
#Mann= 6 ,-1,0
    1000     .12       0    5600     .07       0    6450     .05       0
   10182     .13       0   11693    .055       0   11871     .13       0
#XS Ineff= 2 , 0
       0    1650     490               0
Permanent Ineff=
       F       F
Bank Sta=11693,11871
XS Rating Curve= 0 ,0
Exp/Cntr=0.3,0.1

Type RM Length L Ch R = 1 ,147459  ,42,42,42
BEGIN DESCRIPTION:
This cross section corresponds to cross section 147496 of the non-georeferenced CDC model which was the source of this model.
THIS SECTION WAS COPIED FROM 1475+12
1) THE 110' BLOCKED OBSTRUCTION MODELS THE BERM THAT THE TANKS WILL BE ELEVATED ON
END DESCRIPTION:
XS GIS Cut Line= 5
  2381698.477657 6978294.5800697  2381698.463016 6978294.4368689
 2380703.7189428  6968565.456655 2380239.8629152 6967036.2497397
 2380239.8211315 6967036.1119901
#Sta/Elev= 30
    1000   496.9    1042   482.5    1870   472.3    4441   472.5    4455   477.5
    4468   472.5    4548   472.5    4597     489    4626   480.1    4756   472.5
    5600   474.5    5600   492.9    6450   492.9    6450   471.2    6849   473.4
    6951   459.4    7686   459.4    7763   470.1    7869   473.4   10182   472.5
   11693   480.2   11719     461   11760   442.5   11795   442.5   11800   451.8
   11830   457.5   11871   476.9   12241   477.6   12297   480.4   12378   500.2
#Mann= 6 ,-1,0
    1000     .12       0    5600     .07       0    6450     .05       0
   10182     .13       0   11693    .055       0   11871     .13       0
#XS Ineff= 2 , 0
       0    1650     490               0
Permanent Ineff=
       F       F
#Block Obstruct= 2 ,-1
                            8160    8270     481
Bank Sta=11693,11871
XS Rating Curve= 0 ,0
Exp/Cntr=0.3,0.1

Type RM Length L Ch R = 1 ,147417  ,45,45,45
BEGIN DESCRIPTION:
This cross section corresponds to cross section 147424 of the non-georeferenced CDC model which was the source of this model.
THIS SECTION WAS COPIED FROM 1475+12
1) THE 10'  BLOCKED OBSTRUCTION REPRESENTS THE GAS WELL HEAD
2) THE 110' BLOCKED OBSTRUCTION MODELS THE BERM THAT THE TANKS WILL BE ELEVATED ON
END DESCRIPTION:
XS GIS Cut Line= 5
  2381740.376851 6978287.4849395   2381740.36221 6978287.3417387
 2380745.6181372 6968558.3615248 2380281.7621096 6967029.1546095
 2380281.7203258 6967029.0168598
#Sta/Elev= 30
    1000   496.9    1042   482.5    1870   472.3    4441   472.5    4455   477.5
    4468   472.5    4548   472.5    4597     489    4626   480.1    4756   472.5
    5600   474.5    5600   492.9    6450   492.9    6450   471.2    6849   473.4
    6951   459.4    7686   459.4    7763   470.1    7869   473.4   10182   472.5
   11693   480.2   11719     461   11760   442.5   11795   442.5   11800   451.8
   11830   457.5   11871   476.9   12241   477.6   12297   480.4   12378   500.2
#Mann= 6 ,-1,0
    1000     .12       0    5600     .07       0    6450     .05       0
   10182     .13       0   11693    .055       0   11871     .13       0
#XS Ineff= 2 , 0
       0    1650     490               0
Permanent Ineff=
       F       F
#Block Obstruct= 3 ,-1
                            8107    8117     481    8160    8270     481
Bank Sta=11693,11871
XS Rating Curve= 0 ,0
Exp/Cntr=0.3,0.1

Type RM Length L Ch R = 1 ,147372  ,6,6,6
BEGIN DESCRIPTION:
This cross section corresponds to cross section 147414 of the non-georeferenced CDC model which was the source of this model.
THIS SECTION WAS COPIED FROM 1475+12
1) THE 10'  BLOCKED OBSTRUCTION REPRESENTS THE GAS WELL HEAD
2) THE 110' BLOCKED OBSTRUCTION MODELS THE BERM THAT THE TANKS WILL BE ELEVATED ON
END DESCRIPTION:
XS GIS Cut Line= 5
   2381785.09625  6978280.588956  2381785.081609 6978280.4457552
  2380790.337536 6968551.4655412 2380326.4815083 6967022.2586259
 2380326.4397246 6967022.1208763
#Sta/Elev= 30
    1000   496.9    1042   482.5    1870   472.3    4441   472.5    4455   477.5
    4468   472.5    4548   472.5    4597     489    4626   480.1    4756   472.5
    5600   474.5    5600   492.9    6450   492.9    6450   471.2    6849   473.4
    6951   459.4    7686   459.4    7763   470.1    7869   473.4   10182   472.5
   11693   480.2   11719     461   11760   442.5   11795   442.5   11800   451.8
   11830   457.5   11871   476.9   12241   477.6   12297   480.4   12378   500.2
#Mann= 6 ,-1,0
    1000     .12       0    5600     .07       0    6450     .05       0
   10182     .13       0   11693    .055       0   11871     .13       0
#XS Ineff= 2 , 0
       0    1650     490               0
Permanent Ineff=
       F       F
#Block Obstruct= 3 ,-1
                            8107    8117     481    8160    8270     481
Bank Sta=11693,11871
XS Rating Curve= 0 ,0
Exp/Cntr=0.3,0.1

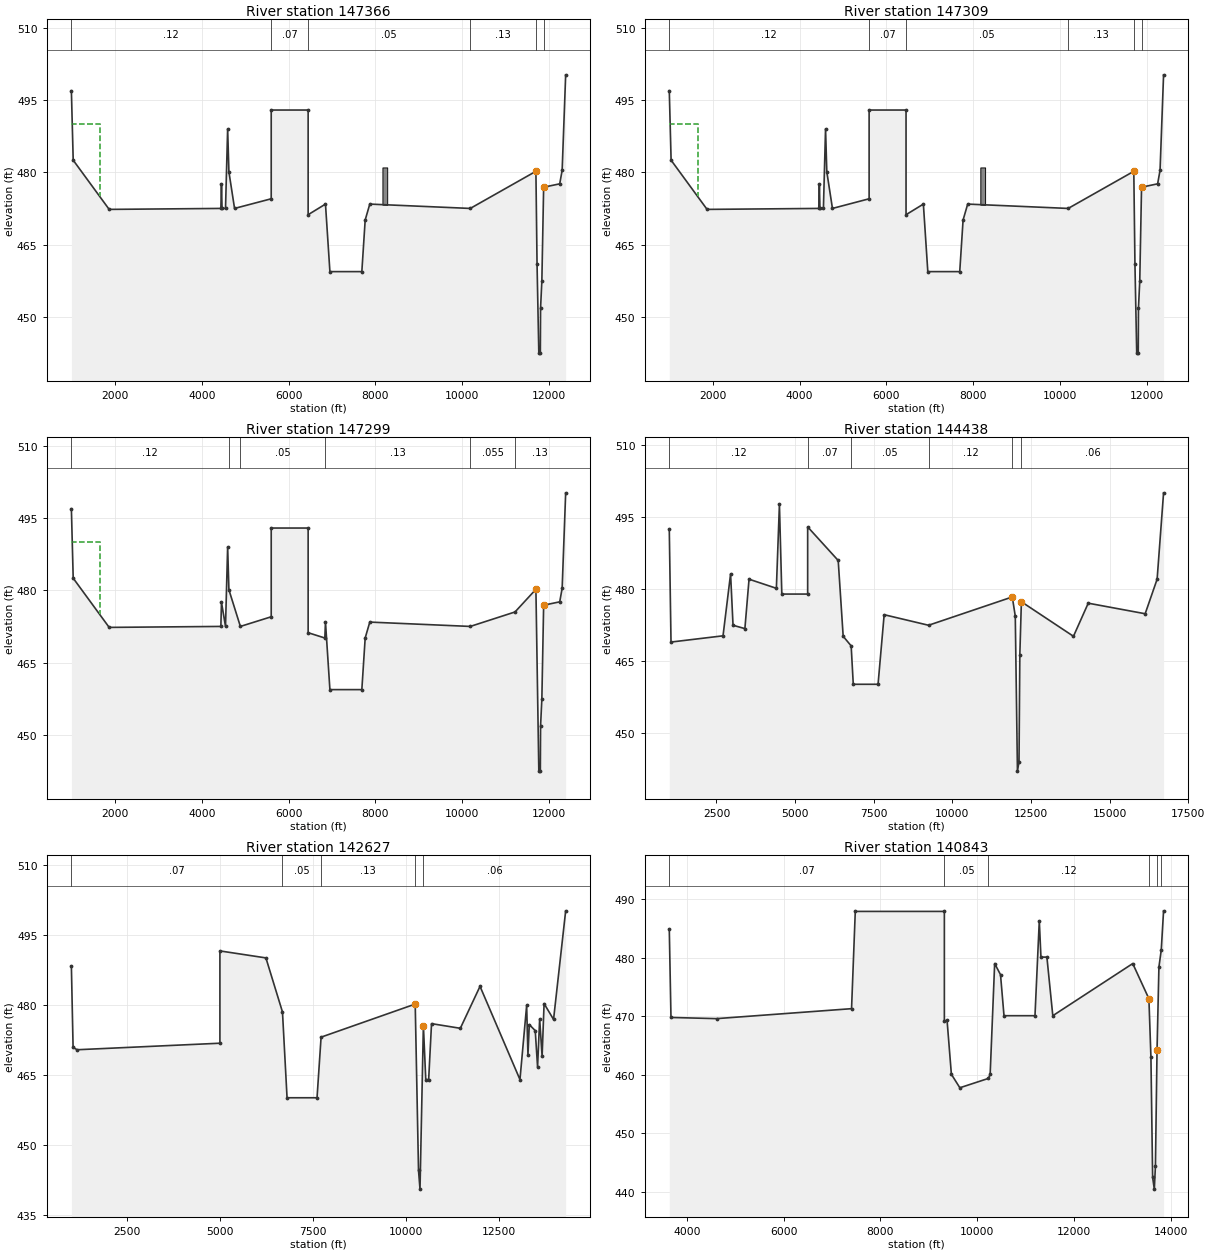
Type RM Length L Ch R = 1 ,147366  ,57,57,57
BEGIN DESCRIPTION:
This cross section corresponds to cross section 147404 of the non-georeferenced CDC model which was the source of this model.
THIS SECTION WAS COPIED FROM 1475+12
1) THE 110' BLOCKED OBSTRUCTION MODELS THE BERM THAT THE TANKS WILL BE ELEVATED ON
END DESCRIPTION:
XS GIS Cut Line= 5
  2381790.800307 6978279.7418448  2381790.785666  6978279.598644
 2380796.0415928 6968550.6184301 2380332.1855652 6967021.4115147
 2380332.1437815 6967021.2737651
#Sta/Elev= 30
    1000   496.9    1042   482.5    1870   472.3    4441   472.5    4455   477.5
    4468   472.5    4548   472.5    4597     489    4626   480.1    4756   472.5
    5600   474.5    5600   492.9    6450   492.9    6450   471.2    6849   473.4
    6951   459.4    7686   459.4    7763   470.1    7869   473.4   10182   472.5
   11693   480.2   11719     461   11760   442.5   11795   442.5   11800   451.8
   11830   457.5   11871   476.9   12241   477.6   12297   480.4   12378   500.2
#Mann= 6 ,-1,0
    1000     .12       0    5600     .07       0    6450     .05       0
   10182     .13       0   11693    .055       0   11871     .13       0
#XS Ineff= 2 , 0
       0    1650     490               0
Permanent Ineff=
       F       F
#Block Obstruct= 2 ,-1
                            8160    8270     481
Bank Sta=11693,11871
XS Rating Curve= 0 ,0
Exp/Cntr=0.3,0.1

Type RM Length L Ch R = 1 ,147309  ,10,10,10
BEGIN DESCRIPTION:
This cross section corresponds to cross section 147346 of the non-georeferenced CDC model which was the source of this model.
THIS SECTION WAS COPIED FROM 1475+12
1) THE 110' BLOCKED OBSTRUCTION MODELS THE BERM THAT THE TANKS WILL BE ELEVATED UPON
END DESCRIPTION:
XS GIS Cut Line= 3
      2381848.81       6978274.3      2380854.37      6968545.83
       2380389.6      6967014.01
#Sta/Elev= 30
    1000   496.9    1042   482.5    1870   472.3    4441   472.5    4455   477.5
    4468   472.5    4548   472.5    4597     489    4626   480.1    4756   472.5
    5600   474.5    5600   492.9    6450   492.9    6450   471.2    6849   473.4
    6951   459.4    7686   459.4    7763   470.1    7869   473.4   10182   472.5
   11693   480.2   11719     461   11760   442.5   11795   442.5   11800   451.8
   11830   457.5   11871   476.9   12241   477.6   12297   480.4   12378   500.2
#Mann= 6 ,-1,0
    1000     .12       0    5600     .07       0    6450     .05       0
   10182     .13       0   11693    .055       0   11871     .13       0
#XS Ineff= 2 , 0
       0    1650     490               0
Permanent Ineff=
       F       F
#Block Obstruct= 2 ,-1
                            8160    8270     481
Bank Sta=11693,11871
XS Rating Curve= 0 ,0
Exp/Cntr=0.3,0.1

Type RM Length L Ch R = 1 ,147299  ,725,2861,2799
BEGIN DESCRIPTION:
This cross section corresponds to cross section 147336 of the non-georeferenced CDC model which was the source of this model.
THIS SECTION WAS COPIED FROM 1475+12 AND IT MODELS THE AREA 10'  DOWNSTREAM OF THE BLOCKED OBSTRUCTION
---------------------------------------------------------------------
CDC FW122804-01 Gas Well Duck Lake No.1
Located in LOB.
Cross-sections 147336 - 147496
---------------------------------------------------------------------
END DESCRIPTION:
XS GIS Cut Line= 3
       2381859.3      6978272.91       2380864.8      6968545.85
      2380399.76      6967012.49
#Sta/Elev= 30
    1000   496.9    1042   482.5    1870   472.3    4441   472.5    4455   477.5
    4548   472.5    4597     489    4626   480.1    4890   472.5    5600   474.5
    5600   492.9    6450   492.9    6450   471.2    6834   470.1    6849   473.4
    6951   459.4    7686   459.4    7763   470.1    7869   473.4   10182   472.5
   11212   475.5   11693   480.2   11760   442.5   11795   442.5   11800   451.8
   11830   457.5   11871   476.9   12241   477.6   12297   480.4   12378   500.2
#Mann= 6 ,-1,0
    1000     .12       0    4626     .07       0    4890     .05       0
    6834     .13       0   10182    .055       0   11212     .13       0
#XS Ineff= 2 , 0
       0    1650     490               0
Permanent Ineff=
       F       F
Bank Sta=11693,11871
XS Rating Curve= 0 ,0
Exp/Cntr=0.3,0.1

Type RM Length L Ch R = 1 ,144438  ,760,1810,760
BEGIN DESCRIPTION:
This cross section corresponds to cross section 144480 of the non-georeferenced CDC model which was the source of this model.
END DESCRIPTION:
XS GIS Cut Line= 5
   2382309.22295   6978250.58689   2381668.19011    6967894.5889
   2382944.88999   6966391.44886 2383077.2418921 6966142.4064883
2384525.465736686963417.32966443
#Sta/Elev= 30
    1000   492.4    1055   468.9    2709   470.2    2949   483.1    3027   472.4
    3404   471.7    3536     482    4405   480.1    4502   497.6    4578   478.9
    5400   478.9    5400   492.9    6371   485.9    6529   470.1    6783   468.1
    6850   460.1    7638   460.1    7832   474.6    9244   472.4   11906   478.3
   12001   474.3   12070     442   12120     444   12146   466.3   12195   477.3
   13851   470.1   14321     477   16131   474.8   16511     482   16716     500
#Mann= 6 ,-1,0
    1000     .12       0    5400     .07       0    6783     .05       0
    9244     .12       0   11906     .05       0   12195     .06       0
Bank Sta=11906,12195
XS Rating Curve= 0 ,0
Exp/Cntr=0.3,0.1

Type RM Length L Ch R = 1 ,142627  ,900,1784,1350
BEGIN DESCRIPTION:
This cross section corresponds to cross section 142669 of the non-georeferenced CDC model which was the source of this model.
---------------------------------------------------------------------
CDC FW070799-01 Links at Waterchase
Cross-section 142669 - 144480
Located in ROB.
---------------------------------------------------------------------
END DESCRIPTION:
XS GIS Cut Line= 5
   2382949.30894      6978204.69   2382551.17916   6969520.17915
   2382718.62994   6967983.55887 2383671.0259506 6966566.1621826
2384426.740487416965441.47532002
#Sta/Elev= 30
    1003   488.3    1049   470.9    1157   470.4    5000   471.8    5000   491.6
    6238   490.1    6684   478.5    6807   460.1    7614   460.1    7723   473.1
   10256   480.2   10345   444.5   10385   440.5   10476   475.6   10540     464
   10618     464   10695     476   11470     475   12000     484   13075     464
   13255   479.9   13290   469.3   13326   475.8   13486   474.5   13549   466.7
   13605     477   13671     469   13724   480.3   13979   476.9   14305   500.2
#Mann= 5 ,-1,0
    1003     .07       0    6684     .05       0    7723     .13       0
   10256    .055       0   10476     .06       0
Bank Sta=10256,10476
XS Rating Curve= 0 ,0
Exp/Cntr=0.3,0.1

Type RM Length L Ch R = 1 ,140843  ,1159,2676,2399
BEGIN DESCRIPTION:
This cross section corresponds to cross section 140885 of the non-georeferenced CDC model which was the source of this model.
---------------------------------------------------------------------
CDC FW121505-1 Bell Station Tract
This project is located between cross-sections 140885 - 147512 and within ineffective flow area, therefore the model was not changed.
---------------------------------------------------------------------
END DESCRIPTION:
XS GIS Cut Line= 4
  2383586.541063 6978179.0099156  2383585.266537 6978041.0158013
   2383497.76388   6968567.02686 2383987.5257072 6968224.5835066
#Sta/Elev= 30
    3638   484.9    3673   469.8    4615   469.6    7403   471.3    7480   487.9
    9320   487.9    9320   469.2    9376   469.3    9465   460.1    9640   457.8
   10231   459.4   10266   460.1   10359     479   10480   477.1   10552   470.1
   11192   470.1   11281   486.3   11315   480.1   11438   480.1   11560   470.1
   13211     479   13545     473   13587     463   13622   442.5   13657   440.5
   13680   444.5   13713   464.2   13752   478.4   13800   481.3   13848     488
#Mann= 6 ,-1,0
    3638     .07       0    9320     .05       0   10231     .12       0
   13545    .055       0   13713     .12       0   13800     .03       0
Bank Sta=13545,13713
XS Rating Curve= 0 ,0
Exp/Cntr=0.3,0.1

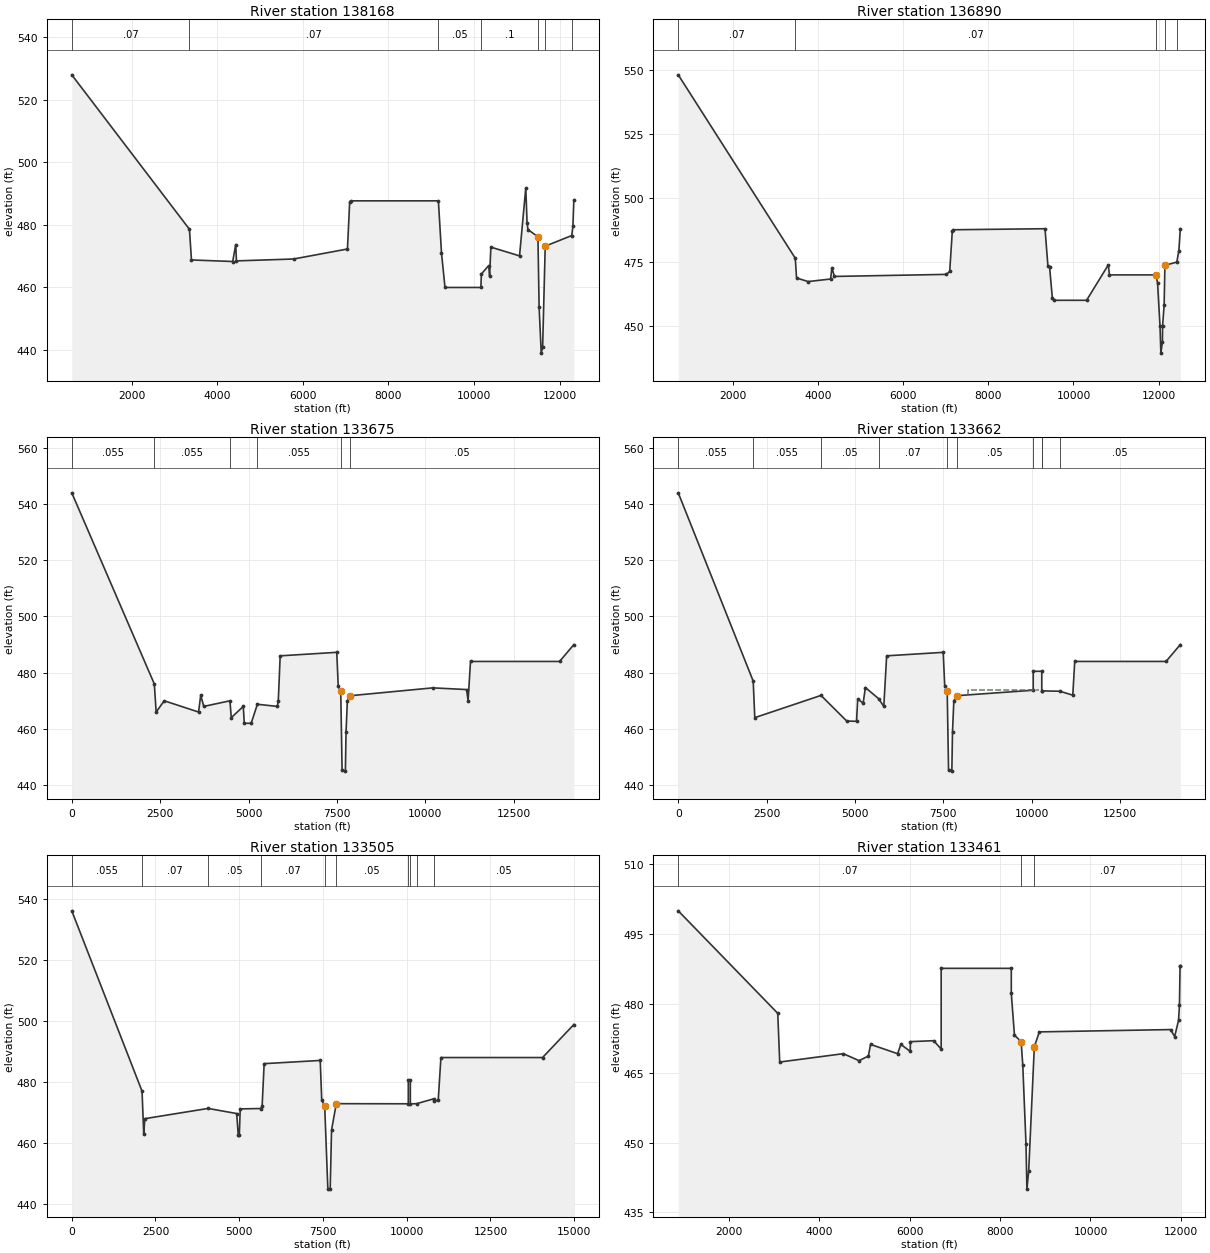
Type RM Length L Ch R = 1 ,138168  ,580,1278,800
BEGIN DESCRIPTION:
This cross section corresponds to cross section 138208 of the non-georeferenced CDC model which was the source of this model.
END DESCRIPTION:
XS GIS Cut Line= 5
2384648.456770356980829.01652966  2384640.097359 6978079.0292351
 2384637.8479174  6977339.032654   2384616.20915   6970220.55013
 2385065.8238786 6969190.9559315
#Sta/Elev= 30
     602     528    3352   478.6    3399   468.8    4363   468.3    4433   473.7
    4450   468.5    5785   469.1    7044   472.3    7096   487.3    7116   487.7
    9169   487.7    9241   471.1    9323     460   10162     460   10173   464.3
   10344     467   10366   463.6   10395   472.9   11065   470.1   11211   491.9
   11241   480.6   11263   478.5   11495   476.2   11522   453.9   11572     439
   11605     441   11665   473.2   12285   476.6   12312   479.6   12334     488
#Mann= 7 ,-1,0
     602     .07       0    3352     .07       0    9169     .05       0
   10173      .1       0   11495     .05       0   11665     .08       0
   12285     .03       0
Bank Sta=11495,11665
XS Rating Curve= 0 ,0
Exp/Cntr=0.3,0.1

Type RM Length L Ch R = 1 ,136890  ,822,3214,163
BEGIN DESCRIPTION:
This cross section corresponds to cross section 136930 of the non-georeferenced CDC model which was the source of this model.
---------------------------------------------------------------------
CDC FW020400-01 Lakeview Addition
Cross-sections 136930 - 138208
---------------------------------------------------------------------
Project located in LOB outside of effective flow limits, therefore not included in model.
END DESCRIPTION:
XS GIS Cut Line= 6
2385275.657724186980676.42565839    2385250.0178 6977926.5451893
 2385249.1693516 6977835.5491447   2385178.10894      6970214.33
   2385741.97002   6969485.02896 2385756.7620401 6969072.7010796
#Sta/Elev= 30
     713     548    3463   476.5    3493   468.8    3765   467.4    4293   468.4
    4324   472.8    4382   469.4    7016   470.2    7092   471.4    7153   487.2
    7177   487.6    9331     488    9400   473.3    9439   472.9    9503   461.1
    9544   460.1   10308   460.1   10818   473.9   10845     470   11932     470
   11975     467   12033   450.1   12053   439.5   12090     444   12093   450.1
   12130   458.2   12148   473.7   12428     475   12476   479.5   12510     488
#Mann= 5 ,-1,0
     713     .07       0    3463     .07       0   11932    .055       0
   12148    .075       0   12428     .03       0
Bank Sta=11932,12148
XS Rating Curve= 0 ,0
Exp/Cntr=0.3,0.1

Type RM Length L Ch R = 1 ,133675  ,13,13,51
BEGIN DESCRIPTION:
This cross section corresponds to cross section 133780 of the non-georeferenced CDC model which was the source of this model.
END DESCRIPTION:
XS GIS Cut Line= 6
2385769.793706786980045.92876009     2385764.762     6972948.171
     2386087.679     6972344.004     2386004.346     6971094.004
     2386035.596     6969812.754 2386281.8520441 6965971.1535652
#Sta/Elev= 30
    .415     5442334.997     4762386.968     4662616.108     4703586.739     466
3647.913     4723733.838     4684474.462     4704511.788     4644851.551     468
4880.327     462 5074.39     462    5250 468.7645814.548     4685841.647     470
5895.139     486 7495.41 487.245 7537.46  475.13 7607.93 473.446 7645.97 445.307
 7739.03 444.973 7757.61  458.89 7795.31 469.982 7883.29 471.817 10210.8   474.6
 11167.2     47411209.74     470 11278.1     48413796.99     48414200.95     490
#Mann= 6 ,-1,0
    .415    .055       02334.997    .055       04474.462     .07       0
    5250    .055       0 7607.93     .05       0 7883.29     .05       0
Bank Sta=7607.93,7883.29
XS Rating Curve= 0 ,0
Exp/Cntr=0.3,0.1

Type RM Length L Ch R = 1 ,133662  ,150,157,245
BEGIN DESCRIPTION:
This cross section corresponds to cross section 133770 of the non-georeferenced CDC model which was the source of this model.
---------------------------------------------------------------------
CDC FW121713-1 Revised West Village Creek Quicksilver Pad Site. Cross-section 133537 - 133770.  Modification of CDC FW022811-1
LOMR 17-06-2291P
---------------------------------------------------------------------
END DESCRIPTION:
XS GIS Cut Line= 6
  2386093.242911 6980100.0657095 2386143.5895918 6974532.8513565
 2386214.9862062 6971139.0165475 2386246.2321702 6969415.2808641
 2386313.9411517 6968384.0209919  2386365.507642 6965190.8051483
#Sta/Elev= 30
     .41     544 2121.03     477 2165.14     464  4038.3  471.91 4765.89   462.8
 5043.55   462.7 5076.88   470.7 5230.58  469.12  5293.6  474.72 5666.69  470.76
 5814.55     468 5895.14     486 7495.41  487.24 7537.46  475.13 7607.93  473.45
 7645.97  445.31 7739.03  444.97 7757.61  458.89 7795.31  469.98 7883.29  471.82
10040.44  473.7510040.45   480.510282.75   480.510282.76  473.56   10297  473.52
   10795   473.411159.66     47211214.69     48413796.99     48414200.95     490
#Mann= 10 ,-1,0
     .41    .055       0 2121.03    .055       0  4038.3     .05       0
 5666.69     .07       0 7607.93     .05       0 7883.29     .05       0
10040.44    .023       010282.76    .045       0   10297    .023       0
   10795     .05       0
#XS Ineff= 2 ,-1
    8210 10210.9  473.75    4300    5100     468
Permanent Ineff=
       T       T
Bank Sta=7607.93,7883.29
XS Rating Curve= 0 ,0
Exp/Cntr=0.3,0.1

Type RM Length L Ch R = 1 ,133505  ,261,44,24
BEGIN DESCRIPTION:
This cross section corresponds to cross section 133537 of the non-georeferenced CDC model which was the source of this model.
---------------------------------------------------------------------
CDC FW121713-1 Revised West Village Creek Quicksilver Pad Site. Cross-section 133537 - 133770.  Modification of CDC FW022811-1
LOMR 17-06-2291P
---------------------------------------------------------------------
END DESCRIPTION:
XS GIS Cut Line= 4
  2386145.723066 6980069.9637047  2386239.473066 6972601.4307186
 2386341.4695938  6968393.531413 2386393.5529271 6965107.9411353
#Sta/Elev= 30
     .35     536 2098.35     477 2148.92     463 2180.87     468  4069.8  471.35
 4923.96  469.68 4970.97  462.59 5002.53  462.77 5029.26   471.2 5639.77  471.32
 5682.87     472 5744.07     486 7417.95  487.05 7462.83  474.12 7551.79  472.05
 7645.48  444.97 7715.47  444.95 7756.01  464.27 7897.13  472.91 10048.5  472.87
10048.51   480.5 10108.5   480.510108.51  472.85   10293   472.9   10805  474.49
   10805   473.710941.07     47411021.15     48814055.12     48814989.83   498.8
#Mann= 10 ,-1,0
     .35    .055       0 2098.35     .07       0  4069.8     .05       0
 5639.77     .07       0 7551.79     .05       0 7897.13     .05       0
 10048.5    .023       010108.51    .045       0   10293    .023       0
   10805     .05       0
#XS Ineff= 1 ,-1
    4900    5050     468
Permanent Ineff=
       T
Bank Sta=7551.79,7897.13
XS Rating Curve= 0 ,0
Exp/Cntr=0.3,0.1

Type RM Length L Ch R = 1 ,133461  ,87,87,87
BEGIN DESCRIPTION:
This cross section corresponds to cross section 133499 of the non-georeferenced CDC model which was the source of this model.
END DESCRIPTION:
XS GIS Cut Line= 6
2386146.418972256980152.44936526   2386231.66688   6974492.05996
   2386256.92109   6972842.08393   2386282.17596   6971882.40311
   2386349.52196   6969146.47288 2386351.0024642 6969056.4576885
#Sta/Elev= 30
     888     500    3088   477.9    3131   467.4    4536   469.2    4886   467.7
    5091   468.7    5139   471.2    5738   469.2    5808   471.2    6016   469.7
    6020   471.8    6535     472    6700   470.2    6700   487.6    8250   487.6
    8250   482.2    8320   473.2    8468   471.8    8504   466.7    8575   449.7
    8595     440    8635     444    8759   470.7    8870   473.9   11770   474.4
   11861   472.9   11947   476.4   11967   479.6   11980     488   11986     488
#Mann= 3 ,0,0
     888     .07       0    8468     .05       0    8759     .07       0
Bank Sta=8468,8759
XS Rating Curve= 0 ,0
Exp/Cntr=0.3,0.1

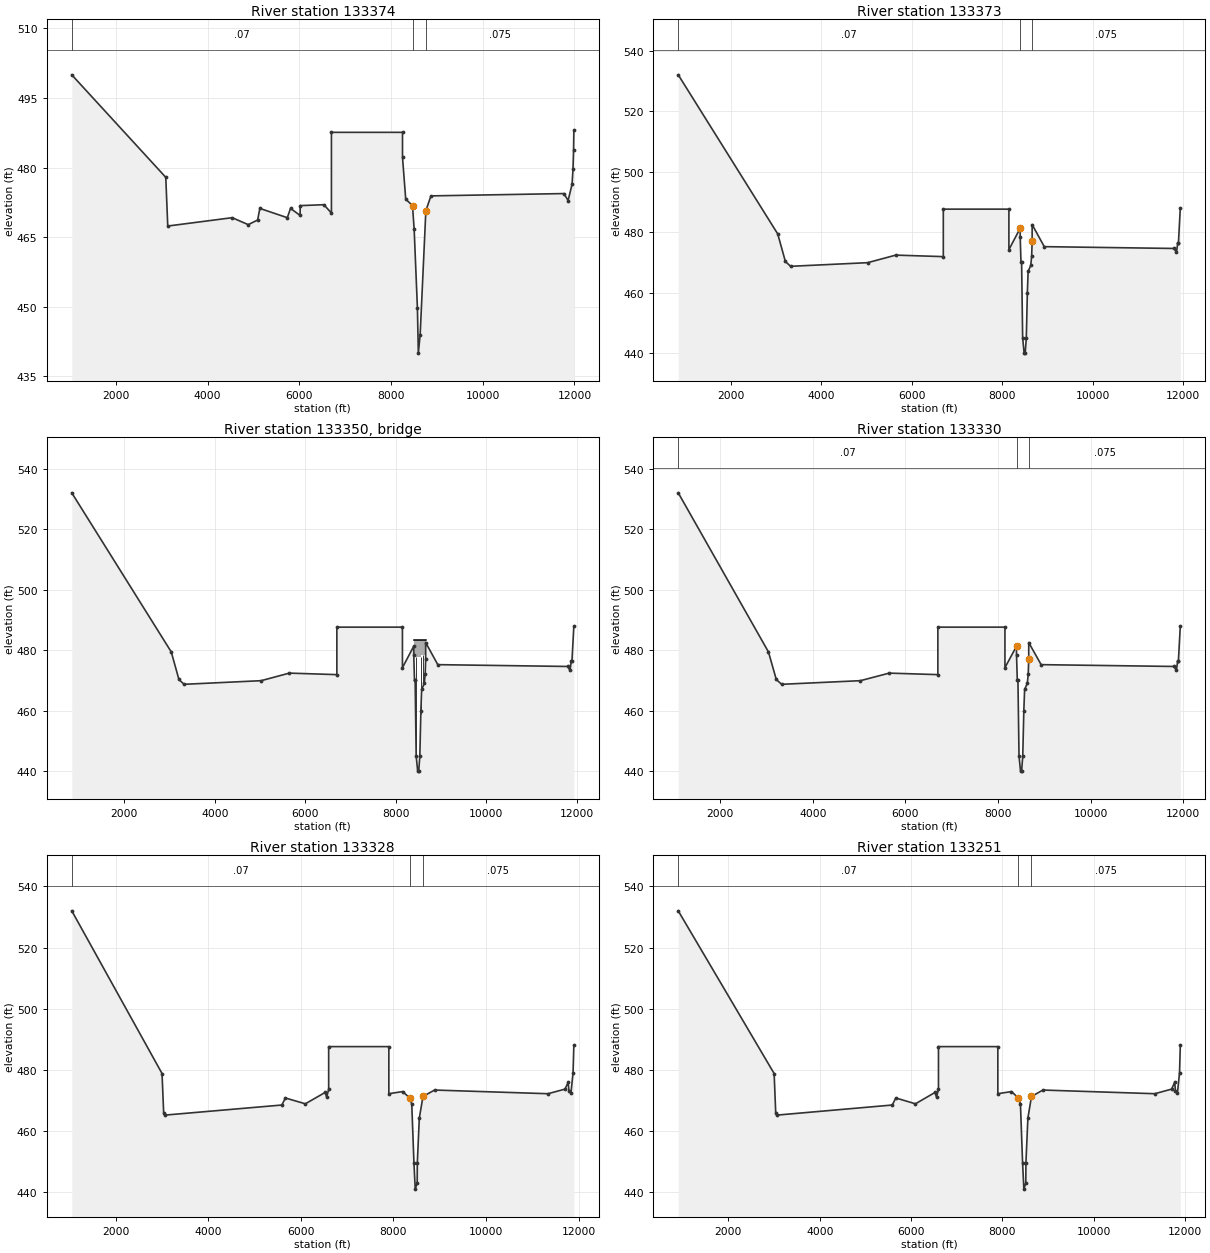
Type RM Length L Ch R = 1 ,133374  ,1,1,1
BEGIN DESCRIPTION:
This cross section corresponds to cross section 133413 of the non-georeferenced CDC model which was the source of this model.
END DESCRIPTION:
XS GIS Cut Line= 6
 2386234.19991786980007.39418702 2386317.1890151 6974496.9877709
 2386342.4432297 6972847.0117402 2386367.6981004 6971887.3309167
 2386435.0440943 6969151.4006931 2386436.5245987 6969061.3855018
#Sta/Elev= 30
    1038     500    3088   477.9    3131   467.4    4536   469.2    4886   467.7
    5091   468.7    5139   471.2    5738   469.2    5808   471.2    6016   469.7
    6020   471.8    6535     472    6700   470.2    6700   487.6    8250   487.6
    8250   482.2    8320   473.2    8468   471.8    8504   466.7    8575   449.7
    8595     440    8635     444    8759   470.7    8870   473.9   11770   474.4
   11861   472.9   11947   476.4   11967   479.6   11980   483.8   11986     488
#Mann= 3 ,0,0
    1038     .07       0    8468    .055       0    8759    .075       0
Bank Sta=8468,8759
XS Rating Curve= 0 ,0
Exp/Cntr=0.3,0.1

Type RM Length L Ch R = 1 ,133373  ,43,43,43
BEGIN DESCRIPTION:
This cross section corresponds to cross section 133412 of the non-georeferenced CDC model which was the source of this model.
END DESCRIPTION:
XS GIS Cut Line= 6
 2386232.96956946980154.93454859 2386318.1798267 6974497.0448574
 2386343.4340413 6972847.0688267 2386368.6889121 6971887.3880032
  2386436.034906 6969151.4577796 2386437.6058582  6969055.943332
#Sta/Elev= 30
     839     532    3039   479.4    3208   470.3    3323   468.7    5026   469.9
    5649   472.4    6700   471.9    6700   487.6    8150   487.6    8150   474.2
    8400   481.3    8400   478.5    8417     470    8431     470    8454     445
    8487     440    8510     440    8535     445    8558     460    8575     467
    8633     469    8653     472    8664     477    8664   482.5    8932   475.2
   11802   474.6   11855   473.3   11883   476.4   11898   476.3   11940     488
#Mann= 3 ,0,0
     839     .07       0    8400    .055       0    8664    .075       0
Bank Sta=8400,8664
XS Rating Curve= 0 ,0
Exp/Cntr=0.3,0.1

Type RM Length L Ch R = 3 ,133350  ,,,
BEGIN DESCRIPTION:
Arlington-Bedford Road
END DESCRIPTION:
Node Name=Arl. Bedford Roa
Bridge Culvert--1,0,-1,-1, 0
Deck Dist Width WeirC Skew NumUp NumDn MinLoCord MaxHiCord MaxSubmerge Is_Ogee
1,40,2.6,0, 11, 11, , , 0.95, 0, ,,,
    8400    8454    8454    8457    8487    8535    8555    8558    8558    8610
    8664
   483.3   483.3   483.3   483.3   483.3   483.3   483.3   483.3   483.3   483.3
   483.3
   478.5   478.5   477.6   477.6   477.6   477.6   477.6   477.6   478.5   478.5
   478.5
    8400    8454    8454    8457    8487    8535    8555    8558    8558    8610
    8664
   483.3   483.3   483.3   483.3   483.3   483.3   483.3   483.3   483.3   483.3
   483.3
   478.5   478.5   477.6   477.6   477.6   477.6   477.6   477.6   478.5   478.5
   478.5
Pier Skew, UpSta & Num, DnSta & Num=  ,8456.5, 2 ,8456.5, 2 , 0 , 0 , 0 ,,
       3       3
     440     480
       3       3
     440     480
Pier Skew, UpSta & Num, DnSta & Num=  ,8556.5, 2 ,8556.5, 2 , 0 , 0 , 0 ,,
       3       3
     440     480
       3       3
     440     480
Pier Skew, UpSta & Num, DnSta & Num=  ,8612.5, 2 ,8612.5, 2 , 0 , 0 , 0 ,,
       3       3
     440     480
       3       3
     440     480
BR Coef= 1 , 0 , 0 ,1.05, 0 ,,,0.8,-1,0.5,1,
WSPro=,,,, 1 ,,,, 0 ,,,, 0 ,,,,-1 ,-1 ,-1 , 0 , 0 , 0 , 0 , 0
BC Design=,, 0 ,, 0 ,,,,,,
BC HTab HWMax=488
BC Use User HTab Curves=0
BC User HTab FreeFlow(D)= 0

Type RM Length L Ch R = 1 ,133330  ,2,2,2
BEGIN DESCRIPTION:
This cross section corresponds to cross section 133370 of the non-georeferenced CDC model which was the source of this model.
END DESCRIPTION:
XS GIS Cut Line= 6
2386290.552566956979930.75752952 2386321.7441241 6977273.9897628
 2386355.4159727 6974529.6409208 2386389.0891337 6972845.9907448
 2386405.9260423 6971962.0748617 2386466.3023447  6969081.276845
#Sta/Elev= 30
    1089     532    3039   479.4    3208   470.3    3323   468.7    5026   469.9
    5649   472.4    6700   471.9    6700   487.6    8150   487.6    8150   474.2
    8400   481.3    8400   478.5    8417     470    8431     470    8454     445
    8487     440    8510     440    8535     445    8558     460    8575     467
    8633     469    8653     472    8664     477    8664   482.5    8932   475.2
   11802   474.6   11855   473.3   11883   476.4   11898   476.3   11940     488
#Mann= 3 ,0,0
    1089     .07       0    8400    .055       0    8664    .075       0
Bank Sta=8400,8664
XS Rating Curve= 0 ,0
Exp/Cntr=0.3,0.1

Type RM Length L Ch R = 1 ,133328  ,76,76,76
BEGIN DESCRIPTION:
This cross section corresponds to cross section 133369 of the non-georeferenced CDC model which was the source of this model.
END DESCRIPTION:
XS GIS Cut Line= 6
     2386292.894     6979908.412     2386323.827     6977273.643
     2386357.499     6974529.294     2386391.172     6972845.644
     2386408.009     6971961.728     2386468.556      6969064.93
#Sta/Elev= 30
    1051     532    3001   478.8    3036   465.9    3060   465.2    5588   468.5
    5666   470.8    6096   468.9    6522   472.6    6557   471.1    6600   473.6
    6600   487.6    7900   487.6    7900   472.2    8199   472.9    8351   470.8
    8395   468.8    8442   449.6    8470     441    8512     443    8515   449.6
    8558   464.2    8637   471.3    8888   473.4   11338   472.2   11704   473.7
   11773   475.9   11790   473.2   11833   472.4   11879   479.1   11896     488
#Mann= 3 ,0,0
    1051     .07       0    8351    .055       0    8637    .075       0
Bank Sta=8351,8637
XS Rating Curve= 0 ,0
Exp/Cntr=0.3,0.1

Type RM Length L Ch R = 1 ,133251  ,250,1822,1239
BEGIN DESCRIPTION:
This cross section corresponds to cross section 133290 of the non-georeferenced CDC model which was the source of this model.
END DESCRIPTION:
XS GIS Cut Line= 6
      2386395.58        6980019.   2386392.53101  6977917.407739
   2386433.70387   6974534.15207   2386467.37703   6972850.50189
   2386484.21394   6971966.58601 2386545.6356243 6969023.7965306
#Sta/Elev= 30
     901     532    3001   478.8    3036   465.9    3060   465.2    5588   468.5
    5666   470.8    6096   468.9    6522   472.6    6557   471.1    6600   473.6
    6600   487.6    7900   487.6    7900   472.2    8199   472.9    8351   470.8
    8395   468.8    8442   449.6    8470     441    8512     443    8515   449.6
    8558   464.2    8637   471.3    8888   473.4   11338   472.2   11704   473.7
   11773   475.9   11790   473.2   11833   472.4   11879   479.1   11896     488
#Mann= 3 ,0,0
     901     .07       0    8351    .055       0    8637    .075       0
Bank Sta=8351,8637
XS Rating Curve= 0 ,0
Exp/Cntr=0.3,0.1

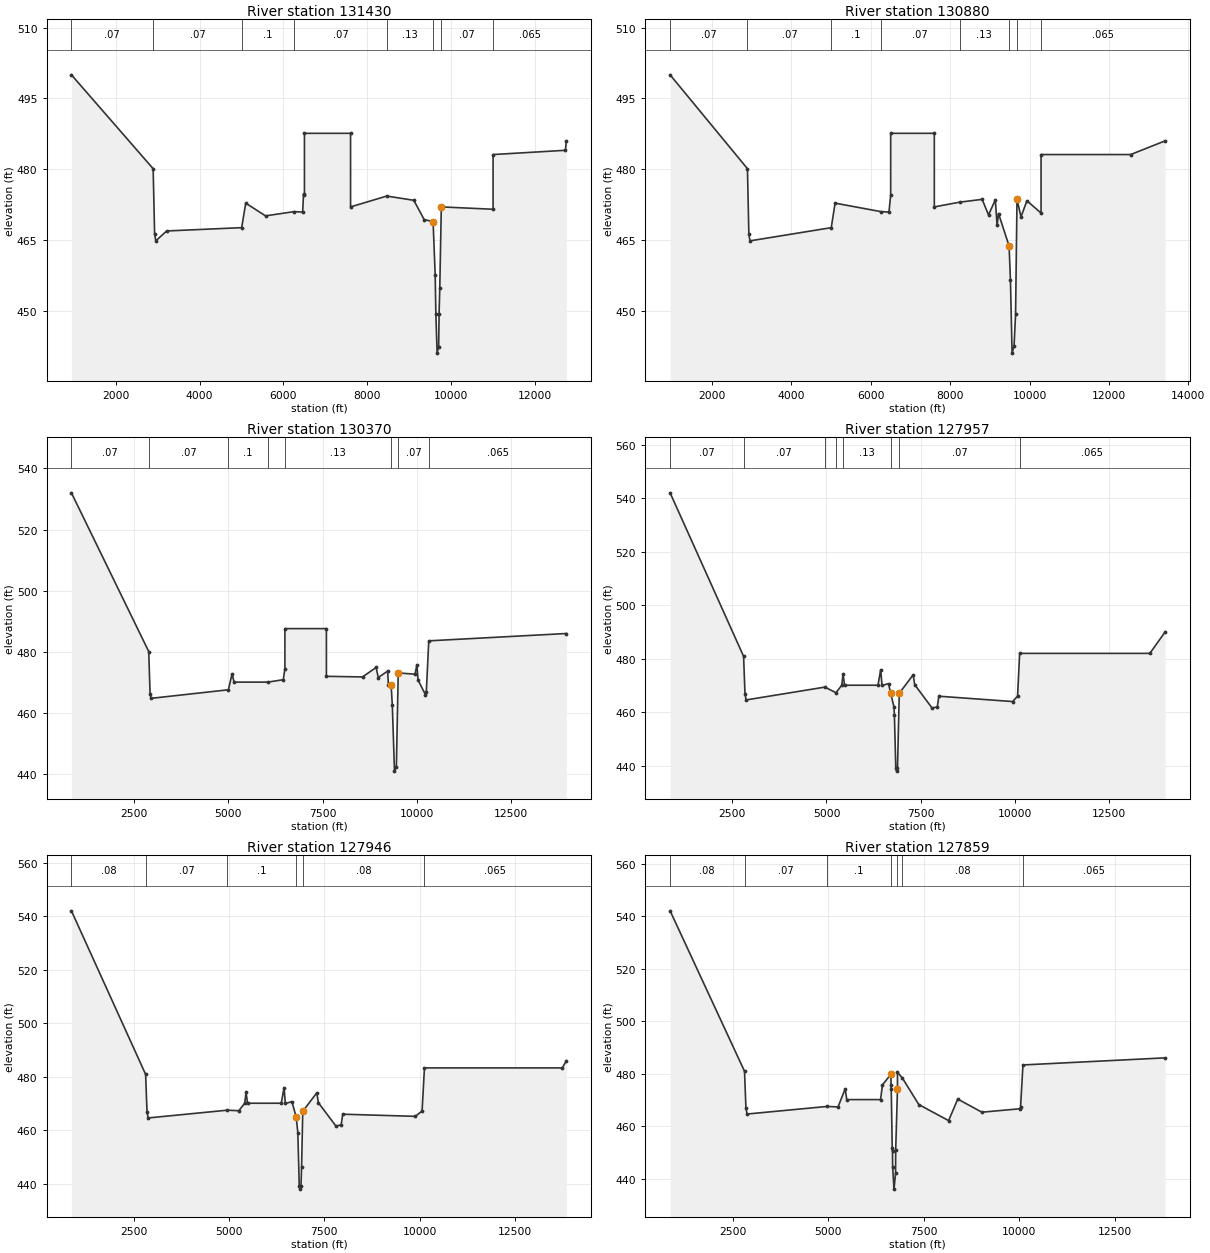
Type RM Length L Ch R = 1 ,131430  ,1,549,721
BEGIN DESCRIPTION:
This cross section corresponds to cross section 131467 of the non-georeferenced CDC model which was the source of this model.
---------------------------------------------------------------------
CDC ARL021511-1 GREENMAN GAS WELL SITE
LOCATED ADJACENT TO VILLAGE CREEK STP IN INEFFECTIVE FLOW AREA.  SITE LOCATED BETWEEN
CROSS-SECTION 131467 AND 133290.
CDC ARL071405-1 SVC Park Highlands, LTD.
In ROB beyond eff. flow line - storage mitigation area d/s SH 360 d/s cross-sect 78083.
END DESCRIPTION:
XS GIS Cut Line= 6
2386728.967360536979883.18641281      2386702.21      6977933.37
   2386634.33897   6972987.58889   2387112.96203   6972235.61303
 2388136.8534676 6969169.68392532388387.094605446968420.36465227
#Sta/Elev= 30
     940     500    2890   480.1    2925   466.3    2953   464.8    3213   466.9
    5002   467.6    5099   472.8    5571   470.1    6252     471    6457   470.9
    6478   474.7    6500   474.5    6500   487.6    7600   487.6    7600     472
    8464   474.3    9109   473.4    9357   469.3    9569   468.9    9619   457.6
    9635   449.4    9665     441    9702   442.4    9712   449.4    9729   454.9
    9765     472   11000   471.5   11000   483.1   12725     484   12750     486
#Mann= 8 ,-1,0
     940     .07       0    2890     .07       0    5002      .1       0
    6252     .07       0    8464     .13       0    9569     .05       0
    9765     .07       0   11000    .065       0
#XS Ineff= 2 , 0
       0                   12725       0
Permanent Ineff=
       F       F
Bank Sta=9569,9765
XS Rating Curve= 0 ,0
Exp/Cntr=0.3,0.1

Type RM Length L Ch R = 1 ,130880  ,1,510,699
BEGIN DESCRIPTION:
This cross section corresponds to cross section 130918 of the non-georeferenced CDC model which was the source of this model.
END DESCRIPTION:
XS GIS Cut Line= 6
2386737.563770176979884.22088967      2386634.99      6972987.54
   2387277.15396   6972359.02584    2388545.9339   6970729.97595
   2389430.32091   6969220.875952389868.684603556968472.86106233
#Sta/Elev= 30
     940     500    2890   480.1    2925   466.3    2953   464.8    5002   467.6
    5099   472.8    6252     471    6457   470.9    6500   474.5    6500   487.6
    7600   487.6    7600     472    8235     473    8806   473.6    8966   470.3
    9138   473.5    9182   468.1    9218   470.6    9485   463.7    9519   456.4
    9560     441    9610   442.5    9648   449.2    9684   473.6    9785   469.9
    9934   473.3   10290   470.7   10290   483.1   12550   483.1   13417     486
#Mann= 8 ,-1,0
     940     .07       0    2890     .07       0    5002      .1       0
    6252     .07       0    8235     .13       0    9485     .05       0
    9684     .07       0   10290    .065       0
#XS Ineff= 2 , 0
       0                   12550       0
Permanent Ineff=
       F       F
Bank Sta=9485,9684
XS Rating Curve= 0 ,0
Exp/Cntr=0.3,0.1

Type RM Length L Ch R = 1 ,130370  ,170,2413,1045
BEGIN DESCRIPTION:
This cross section corresponds to cross section 130407 of the non-georeferenced CDC model which was the source of this model.
END DESCRIPTION:
XS GIS Cut Line= 6
2386745.252862386979985.05101815  2386713.211418 6977935.3014369
      2386635.87      6972987.63    2388739.7511   6971682.79392
   2390208.02999   6969181.893092390587.243143516968535.98413031
#Sta/Elev= 30
     840     532    2890   480.1    2925   466.3    2953   464.8    5002   467.6
    5099   472.8    5153   470.1    6047   470.1    6457   470.9    6500   474.5
    6500   487.6    7600   487.6    7600     472    8558   471.8    8918   474.9
    8975   471.6    9223   473.7    9245     469    9315   469.3    9347   462.7
    9405     441    9455   442.5    9504   473.1    9949   472.7   10000   475.8
   10029   470.8   10226     466   10249     467   10314   483.6   13963     486
#Mann= 8 ,-1,0
     840     .07       0    2890     .07       0    5002      .1       0
    6047     .07       0    6500     .13       0    9315    .055       0
    9504     .07       0   10314    .065       0
#XS Ineff= 2 , 0
       0                   13214       0
Permanent Ineff=
       F       F
Bank Sta=9315,9504
XS Rating Curve= 0 ,0
Exp/Cntr=0.3,0.1

Type RM Length L Ch R = 1 ,127957  ,11,11,384
BEGIN DESCRIPTION:
This cross section corresponds to cross section 127999 of the non-georeferenced CDC model which was the source of this model.
END DESCRIPTION:
XS GIS Cut Line= 6
2386908.972737256979877.95741094   2386799.79894   6974193.06089
   2387388.91489   6974137.69387   2387682.10492   6974075.23107
      2388048.19      6973970.41 2391057.2090427 6968578.4097208
#Sta/Elev= 30
     852     542    2802   480.9    2839   466.9    2869   464.6    4958   469.4
    5252   467.3    5407   470.1    5441   474.2    5481   470.1    6367   470.1
    6440   475.9    6474     470    6647   470.7    6702   467.2    6790   462.1
    6803     459    6840     439    6860     438    6885     439    6932   467.1
    7302     474    7342   470.3    7802   461.6    7942     462    7982     466
    9940     464   10071     466   10126     482 13580.5     482   13985     490
#Mann= 8 ,-1,0
     852     .07       0    2802     .07       0    4958      .1       0
    5252     .07       0    5441     .13       0    6702    .055       0
    6932     .07       0   10126    .065       0
Bank Sta=6702,6932
XS Rating Curve= 0 ,0
Exp/Cntr=0.3,0.1

Type RM Length L Ch R = 1 ,127946  ,1,87,87
BEGIN DESCRIPTION:
This cross section corresponds to cross section 127989 of the non-georeferenced CDC model which was the source of this model.
END DESCRIPTION:
XS GIS Cut Line= 6
2386912.371899496979877.78530247 2386803.0685215  6974202.068684
 2387392.1844715  6974146.701664 2387957.8024315  6974016.957834
 2388597.7926215  6973733.1178442391117.582931756968891.08217855
#Sta/Elev= 30
     852     542    2802   480.9    2839   466.9    2869   464.6    4950   467.5
    5252   467.3    5407   470.1    5441   474.2    5481   470.1    6367   470.1
    6440   475.9    6474     470    6647   470.7    6760   464.9    6803     459
    6840     439    6860     438    6885     439    6901   446.3    6932   467.1
    7302     474    7342   470.3    7802   461.6    7942     462    7982     466
    9890   465.2   10068   467.2   10130   483.3   13752   483.3   13861     486
#Mann= 6 ,-1,0
     852     .08       0    2802     .07       0    4950      .1       0
    6760     .05       0    6932     .08       0   10130    .065       0
#XS Ineff= 2 , 0
       0                   13752       0
Permanent Ineff=
       F       F
Bank Sta=6760,6932
XS Rating Curve= 0 ,0
Exp/Cntr=0.3,0.1

Type RM Length L Ch R = 1 ,127859  ,12,12,12
BEGIN DESCRIPTION:
This cross section corresponds to cross section 127889 of the non-georeferenced CDC model which was the source of this model.
END DESCRIPTION:
XS GIS Cut Line= 6
2386915.380638786979877.47995426 2386808.3232034 6974283.3612296
 2387397.4391512 6974227.9942144 2387963.0571144 6974098.2503794
      2388593.48      6973807.732391132.398256476968920.98900988
#Sta/Elev= 30
     852     542    2802   480.9    2839   466.9    2869   464.6    4970   467.5
    5252   467.3    5441   474.2    5481   470.1    6367   470.1    6417   475.7
    6640   479.8    6640   475.5    6647     474    6673   451.5    6680   450.5
  6683.5   444.5    6719     436    6760     442  6763.5     451    6810     474
    6810   480.5    6935   478.4    7370   468.2    8150   462.1    8390   470.3
    9022   465.3   10011   466.6   10036   467.2   10098   483.3   13823     486
#Mann= 7 ,-1,0
     852     .08       0    2802     .07       0    4970      .1       0
    6640    .055       0    6810     .13       0    6935     .08       0
   10098    .065       0
#XS Ineff= 2 , 0
       0                   13720       0
Permanent Ineff=
       F       F
Bank Sta=6640,6810
XS Rating Curve= 0 ,0
Exp/Cntr=0.3,0.1