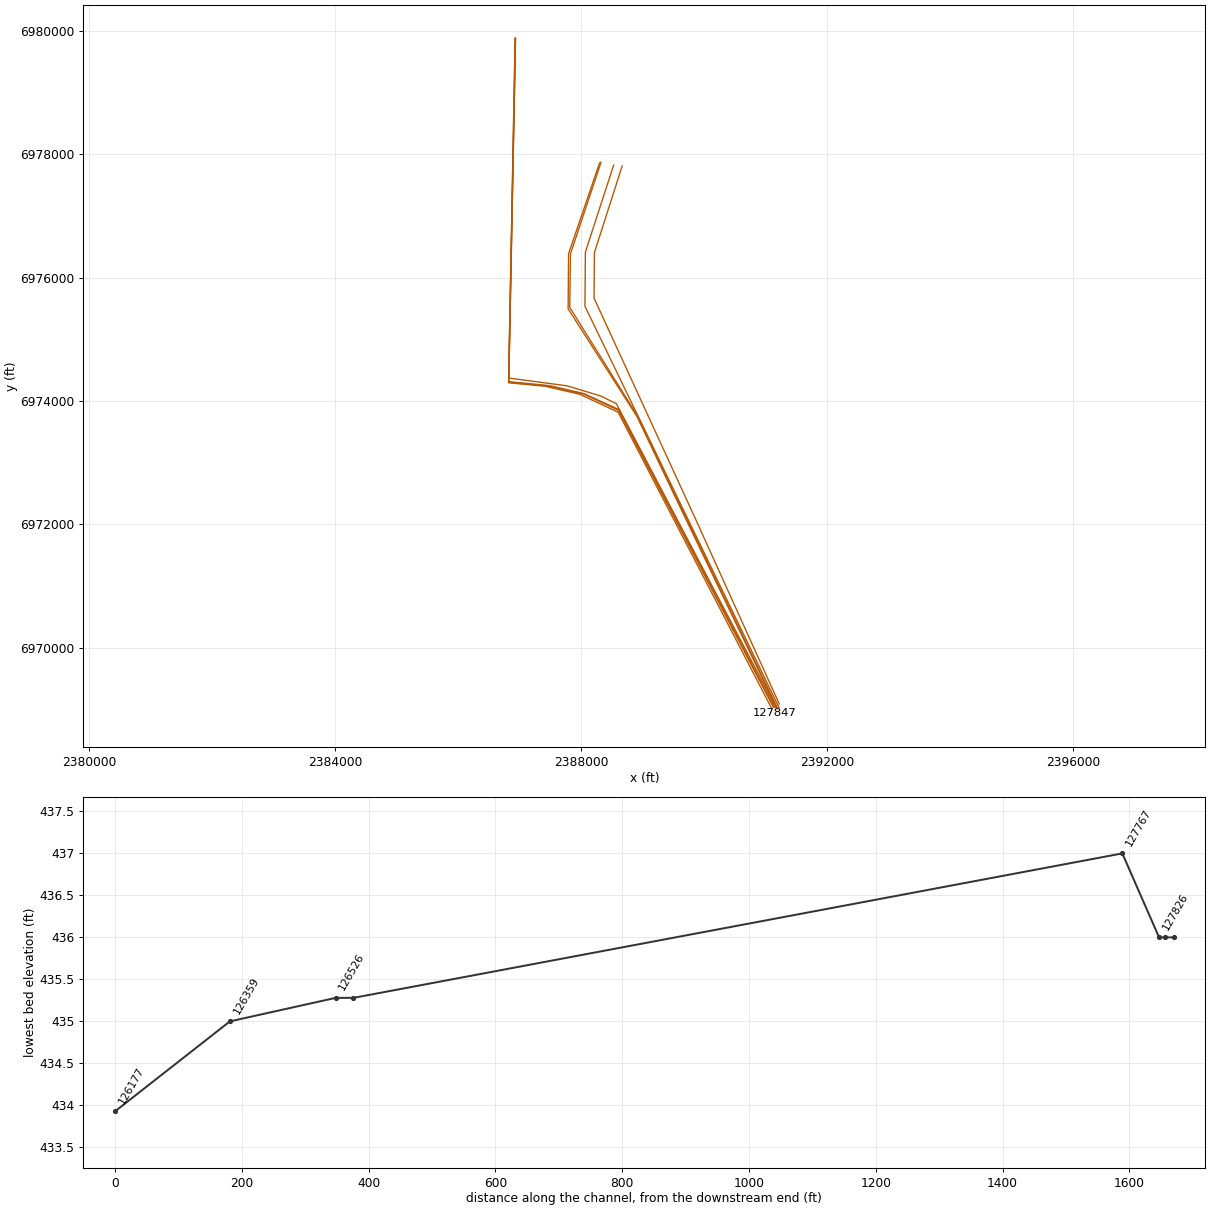
HEC-RAS study CDC_Consolidated_Model.prj: Upper Trinity CDC Consolidated Model

--- CDC_Consolidated_Model.g02 (geometry) --- (continued)

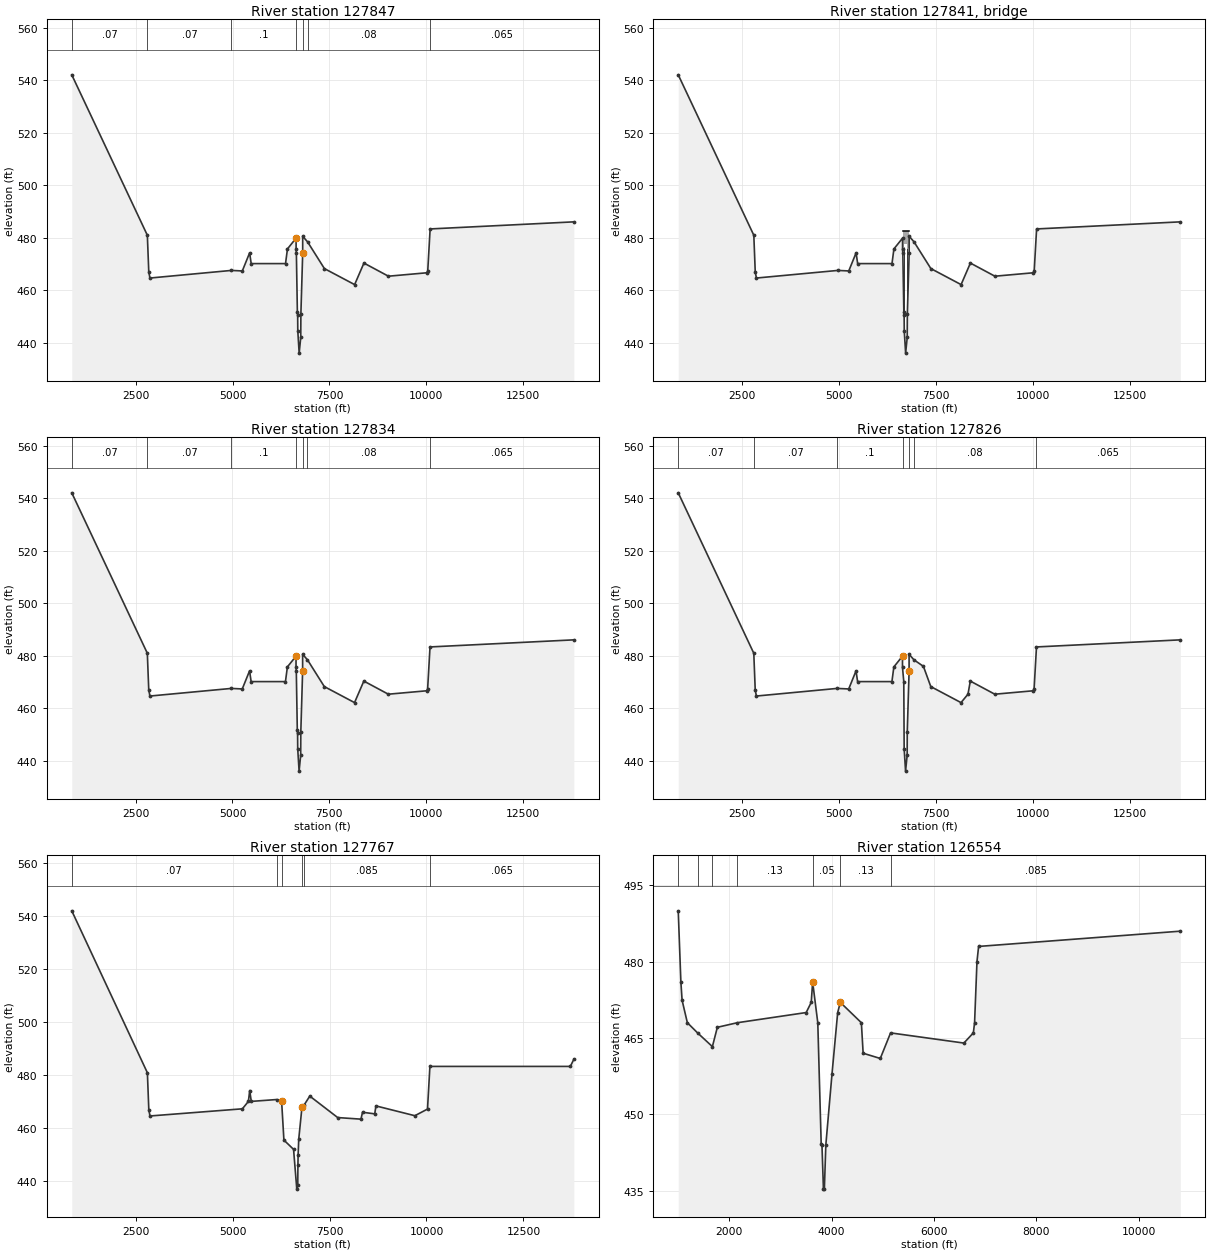
Type RM Length L Ch R = 1 ,127847  ,1,14,14
BEGIN DESCRIPTION:
This cross section corresponds to cross section 127888 of the non-georeferenced CDC model which was the source of this model.
END DESCRIPTION:
XS GIS Cut Line= 6
2386925.189568136979877.72399945 2386818.9094683 6974293.7191486
 2387408.0254161 6974238.3521333 2387973.6433793 6974108.6082983
      2388600.73      6973817.032391137.621004666968934.45215315
#Sta/Elev= 30
     852     542    2802   480.9    2839   466.9    2869   464.6    4970   467.5
    5252   467.3    5441   474.2    5481   470.1    6367   470.1    6417   475.7
    6640   479.8    6640   475.5    6647     474    6673   451.5    6680   450.5
  6683.5   444.5    6719     436    6760     442  6763.5     451    6810     474
    6810   480.5    6935   478.4    7370   468.2    8150   462.1    8390   470.3
    9022   465.3   10011   466.6   10036   467.2   10098   483.3   13806     486
#Mann= 7 ,-1,0
     852     .07       0    2802     .07       0    4970      .1       0
    6640    .055       0    6810     .13       0    6935     .08       0
   10098    .065       0
#XS Ineff= 2 , 0
       0                   13720       0
Permanent Ineff=
       F       F
Bank Sta=6640,6810
XS Rating Curve= 0 ,0
Exp/Cntr=0.3,0.1

Type RM Length L Ch R = 3 ,127841  ,,,
BEGIN DESCRIPTION:
Trammel-Davis Road
END DESCRIPTION:
Node Name=Trammel-Davis Ro
Bridge Culvert--1,0,-1,-1, 0
Deck Dist Width WeirC Skew NumUp NumDn MinLoCord MaxHiCord MaxSubmerge Is_Ogee
0.5,13,2.6,0, 8, 8, , , 0.95, 0, ,,,
    6640    6680  6683.5  6683.5    6760    6760  6763.5    6810
   482.7   482.7   482.7   482.7   482.7   482.7   482.7   482.7
   476.4   476.4   476.4   477.5   477.5   476.1   476.1   476.1
    6640    6680  6683.5  6683.5    6760    6760  6763.5    6810
   482.7   482.7   482.7   482.7   482.7   482.7   482.7   482.7
   476.4   476.4   476.4   477.5   477.5   476.1   476.1   476.1
Pier Skew, UpSta & Num, DnSta & Num=  ,6681.75, 2 ,6681.75, 2 , 0 , 0 , 0 ,,
     3.5     3.5
     440     480
     3.5     3.5
     440     480
Pier Skew, UpSta & Num, DnSta & Num=  ,6761.75, 2 ,6761.75, 2 , 0 , 0 , 0 ,,
     3.5     3.5
     440     480
     3.5     3.5
     440     480
BR Coef= 1 , 0 , 0 ,1.05, 0 ,,,0.8,-1,0.5,1,
WSPro=,,,, 1 ,,,, 0 ,,,, 0 ,,,,-1 ,-1 ,-1 , 0 , 0 , 0 , 0 , 0
BC Design=,, 0 ,, 0 ,,,,,,
BC HTab HWMax=483.3
BC Use User HTab Curves=0
BC User HTab FreeFlow(D)= 0

Type RM Length L Ch R = 1 ,127834  ,9,9,9
BEGIN DESCRIPTION:
This cross section corresponds to cross section 127873 of the non-georeferenced CDC model which was the source of this model.
END DESCRIPTION:
XS GIS Cut Line= 6
2386929.299360276979877.70600843      2386820.11      6974303.42
  2387483.115489 6974238.5142065 2388039.0025006 6974110.8425458
       2388605.3      6973847.922391163.201214666968959.24545689
#Sta/Elev= 30
     852     542    2802   480.9    2839   466.9    2869   464.6    4970   467.5
    5252   467.3    5441   474.2    5481   470.1    6367   470.1    6417   475.7
    6640   479.8    6640   475.5    6647     474    6673   451.5    6680   450.5
  6683.5   444.5    6719     436    6760     442  6763.5     451    6810     474
    6810   480.5    6935   478.4    7370   468.2    8150   462.1    8390   470.3
    9022   465.3   10011   466.6   10036   467.2   10098   483.3   13810     486
#Mann= 7 ,-1,0
     852     .07       0    2802     .07       0    4970      .1       0
    6640    .055       0    6810     .13       0    6935     .08       0
   10098    .065       0
#XS Ineff= 2 , 0
       0                   13720       0
Permanent Ineff=
       F       F
Bank Sta=6640,6810
XS Rating Curve= 0 ,0
Exp/Cntr=0.3,0.1

Type RM Length L Ch R = 1 ,127826  ,1,58,58
BEGIN DESCRIPTION:
This cross section corresponds to cross section 127872 of the non-georeferenced CDC model which was the source of this model.
END DESCRIPTION:
XS GIS Cut Line= 6
2386932.10906372 6979877.4587316      2386822.04      6974312.16
 2387484.9901572 6974247.1218008 2388040.8771687 6974119.4501402
      2388609.57      6973861.052391175.968853386968965.81475918
#Sta/Elev= 30
     852     542    2802   480.9    2839   466.9    2869   464.6    4950   467.5
    5252   467.3    5441   474.2    5481   470.1    6367   470.1    6417   475.7
    6640   479.8    6640   475.5    6673   470.1    6683   444.5    6719     436
    6760     442    6763     451    6810     474    6810   480.5    6935   478.4
    7180   475.9    7370   468.2    8150   462.1    8330   465.3    8390   470.3
    9022   465.3   10011   466.6   10036   467.2   10098   483.3   13810     486
#Mann= 7 ,-1,0
     852     .07       0    2802     .07       0    4950      .1       0
    6640     .05       0    6810     .13       0    6935     .08       0
   10098    .065       0
#XS Ineff= 2 , 0
       0                   13720       0
Permanent Ineff=
       F       F
Bank Sta=6640,6810
XS Rating Curve= 0 ,0
Exp/Cntr=0.3,0.1

Type RM Length L Ch R = 1 ,127767  ,1017,1213,31
BEGIN DESCRIPTION:
This cross section corresponds to cross section 127781 of the non-georeferenced CDC model which was the source of this model.
END DESCRIPTION:
XS GIS Cut Line= 6
2386931.618928986979877.45992418  2386824.310376 6974370.2773944
 2387769.0867018 6974245.0112407 2388318.2667058 6974078.9124916
 2388571.9568152 6973954.1630691 2391195.19937176968974.98647491
#Sta/Elev= 30
     852     542    2802   480.9    2839   466.9    2869   464.6    5252   467.3
    5407   470.1    5441   474.2    5481   470.1    6135   470.8    6264   470.1
    6323   455.5    6572     452    6655     437    6680   438.5    6684   446.1
    6689   449.7    6705   455.8    6790   468.1    6838   468.6    6990   472.1
    7710     464    8310   463.4    8350     466    8665   465.4    8696   468.4
    9700   464.7   10026   467.2   10088   483.3   13710   483.3   13800     486
#Mann= 6 ,-1,0
     852     .07       0    6135     .13       0    6264     .05       0
    6790     .13       0    6838    .085       0   10088    .065       0
#XS Ineff= 2 , 0
       0                   13710       0
Permanent Ineff=
       F       F
Bank Sta=6264,6790
XS Rating Curve= 0 ,0
Exp/Cntr=0.3,0.1

Type RM Length L Ch R = 1 ,126554  ,28,28,28
BEGIN DESCRIPTION:
This cross section corresponds to cross section 126600 of the non-georeferenced CDC model which was the source of this model.
END DESCRIPTION:
XS GIS Cut Line= 6
  2388299.036303 6977858.0265513 2387794.7766111 6976387.3957355
 2387787.2940145 6975492.7790864 2388906.0437455 6973749.0292931
      2389487.45      6972528.08      2391201.25      6968972.53
#Sta/Elev= 30
    1000     490 1051.69     476 1075.57  472.41 1178.35     468 1378.09     466
 1667.97   463.3 1764.61   467.1 2155.82     468 3501.74     470  3600.6     472
 3628.33     476 3728.64     468 3795.53  444.11 3810.14     444  3839.2  435.28
  3857.2  435.28 3886.29     444 4007.36     458 4117.83     470 4169.13     472
 4580.92     468 4615.57     462 4950.74  460.97 5152.15     466 6585.31     464
 6770.58     466 6794.69     468  6841.3     480 6873.42     48310817.42     486
#Mann= 7 ,-1,0
    1000     .13       0 1378.09     .04       0 1667.97     .07       0
 2155.82     .13       0 3628.33     .05       0 4169.13     .13       0
 5152.15    .085       0
#XS Ineff= 2 , 0
       0                 6873.42       0
Permanent Ineff=
       F       F
Bank Sta=3628.33,4169.13
XS Rating Curve= 0 ,0
Exp/Cntr=0.3,0.1

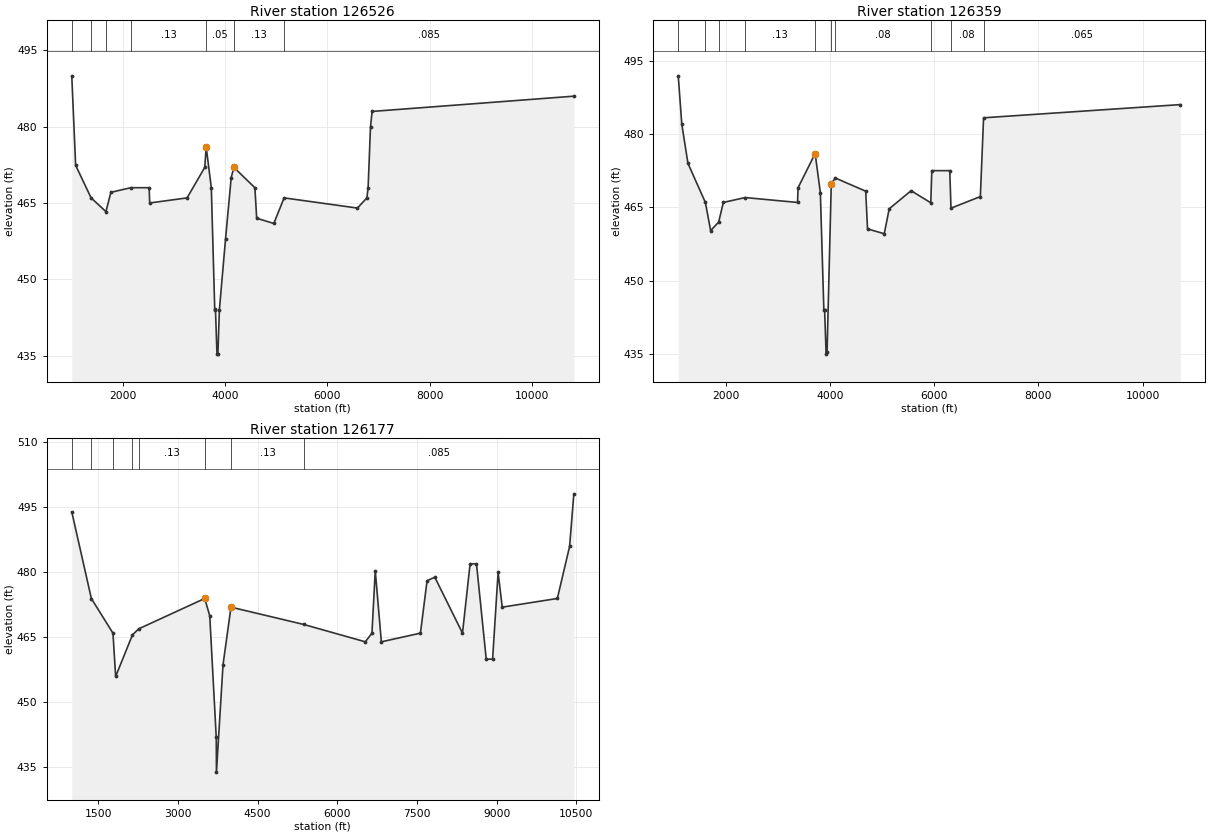
Type RM Length L Ch R = 1 ,126526  ,167,167,167
BEGIN DESCRIPTION:
This cross section corresponds to cross section 126590 of the non-georeferenced CDC model which was the source of this model.
END DESCRIPTION:
XS GIS Cut Line= 6
  2388322.501575 6977868.8919064  2387824.984884 6976382.9902325
 2387813.5528202 6975516.0424913 2388931.2175797 6973731.4945512
      2389503.27      6972526.64      2391214.25      6968969.47
#Sta/Elev= 30
    1000     490 1075.57  472.41 1378.09     466 1667.97   463.3 1764.61   467.1
 2155.82     468    2514     468    2523     465    3255     466  3600.6     472
 3628.33     476 3728.64     468 3795.53  444.11 3810.14     444  3839.2  435.28
  3857.2  435.28 3886.29     444 4007.36     458 4117.83     470 4169.13     472
 4580.92     468 4615.57     462 4950.74  460.97 5152.15     466 6585.31     464
 6770.58     466 6794.69     468  6841.3     480 6873.42     48310817.42     486
#Mann= 7 ,-1,0
    1000     .13       0 1378.09     .04       0 1667.97     .07       0
 2155.82     .13       0 3628.33     .05       0 4169.13     .13       0
 5152.15    .085       0
#XS Ineff= 2 , 0
       0                 6873.42       0
Permanent Ineff=
       F       F
Bank Sta=3628.33,4169.13
XS Rating Curve= 0 ,0
Exp/Cntr=0.3,0.1

Type RM Length L Ch R = 1 ,126359  ,269,181,140
BEGIN DESCRIPTION:
This cross section corresponds to cross section 126400 of the non-georeferenced CDC model which was the source of this model.
END DESCRIPTION:
XS GIS Cut Line= 5
     2388527.595     6977823.304     2388068.022     6976412.168
     2388060.395     6975534.975 2391168.6798068 6969126.0675065
2391236.318686276968986.60431428
#Sta/Elev= 30
  1085.8  491.88 1154.19     482 1271.87     474 1606.85     466 1707.85  460.24
 1862.07     462  1951.6     466  2370.8     467  3376.8     466  3385.8     469
 3714.13     476 3814.44     468 3881.33  444.11 3895.94     444    3925     435
    3943   435.4    4024   469.8    4101     471    4685   468.3    4720   460.6
    5041   459.6    5136   464.7    5556   468.4 5934.31  465.94 5953.99   472.5
 6298.99   472.5    6322  464.83    6886   467.2    6948   483.3   10725     486
#Mann= 10 ,-1,0
  1085.8     .13       0 1606.85     .04       0 1862.07     .07       0
  2370.8     .13       0 3714.13     .05       0    4024     .13       0
    4101     .08       0 5934.31    .023       0    6322     .08       0
    6948    .065       0
#XS Ineff= 2 , 0
       0                   10570       0
Permanent Ineff=
       F       F
Bank Sta=3714.13,4024
XS Rating Curve= 0 ,0
Exp/Cntr=0.3,0.1

Type RM Length L Ch R = 1 ,126177  ,202,202,202
BEGIN DESCRIPTION:
This cross section corresponds to cross section 126217 of the non-georeferenced CDC model which was the source of this model.
END DESCRIPTION:
XS GIS Cut Line= 5
  2388665.624278 6977808.5402029 2388214.2354178 6976402.2900627
 2388209.0270949 6975666.1790021 2389854.8604174 6972092.9151512
      2391219.69      6969087.67
#Sta/Elev= 30
    1000     494  1368.7  473.99 1775.74     466 1826.27     456 2142.74  465.61
    2261     467    3503     474    3598     470 3720.07     442 3724.24  433.93
 3847.75   458.7 3997.76     472 5368.98     468 6526.97     464 6651.85     466
 6714.22   480.4    6829     464 7564.98     466 7689.44   478.1 7835.41  478.91
 8356.56     466 8499.93     482 8620.16     482 8803.73     460 8923.64     460
 9026.94     480 9105.03     47210142.62     47410373.07     48610453.25  498.15
#Mann= 8 ,-1,0
    1000     .08       0  1368.7    .055       0 1775.74     .04       0
 2142.74     .08       0    2261     .13       0    3503     .05       0
 3997.76     .13       0 5368.98    .085       0
Bank Sta=3503,3997.76
XS Rating Curve= 0 ,0
Exp/Cntr=0.3,0.1