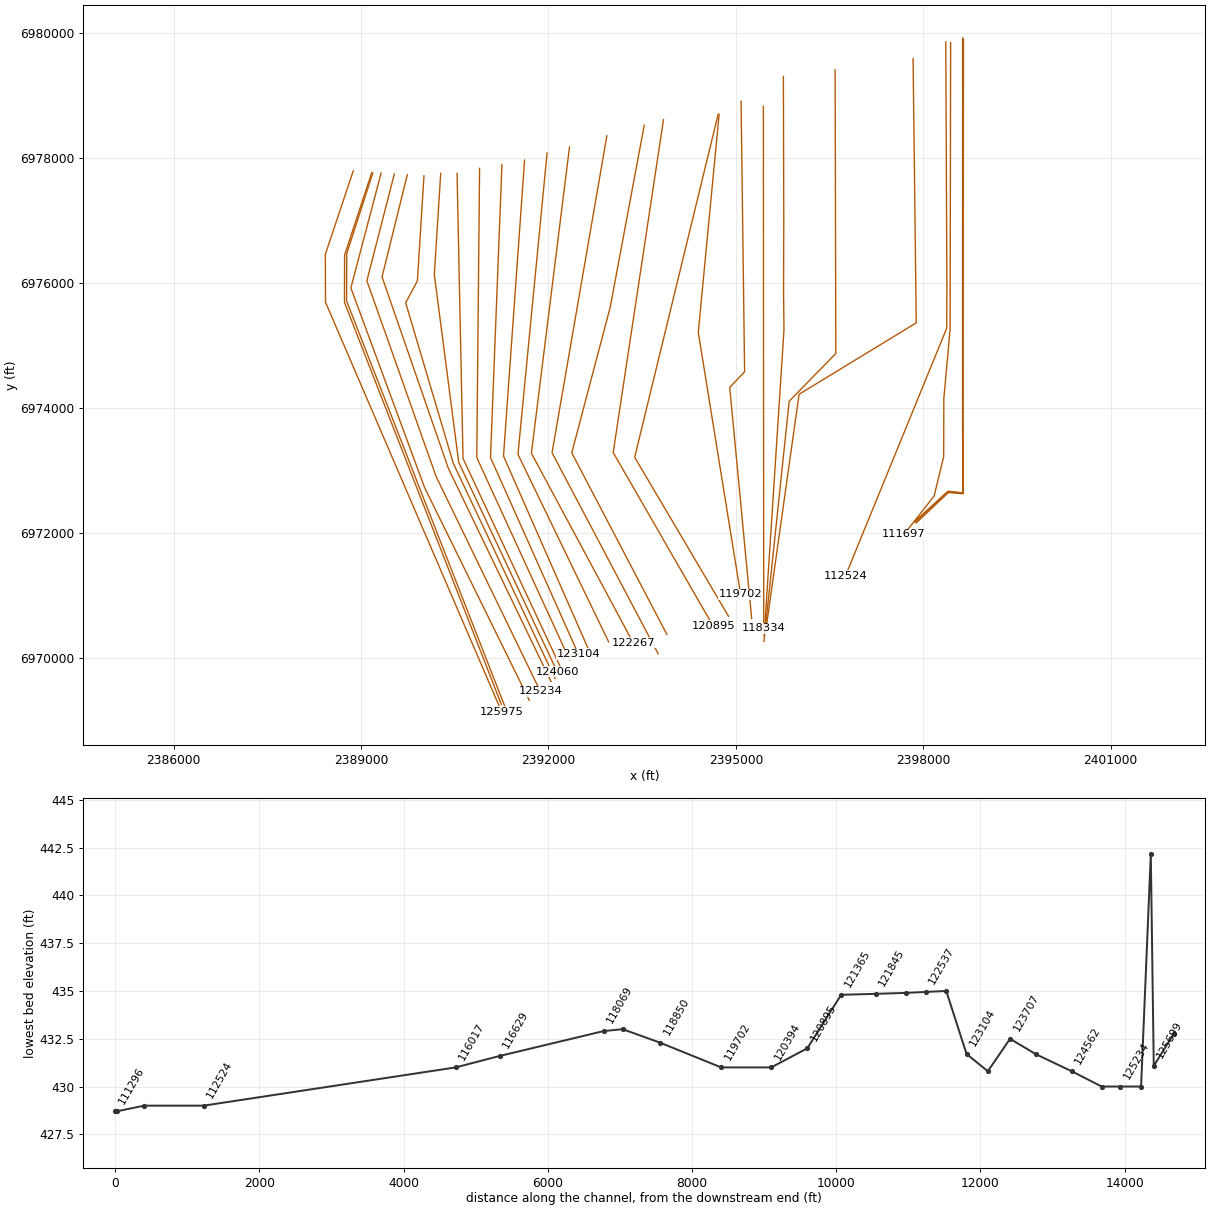
HEC-RAS study CDC_Consolidated_Model.prj: Upper Trinity CDC Consolidated Model

--- CDC_Consolidated_Model.g02 (geometry) --- (continued)

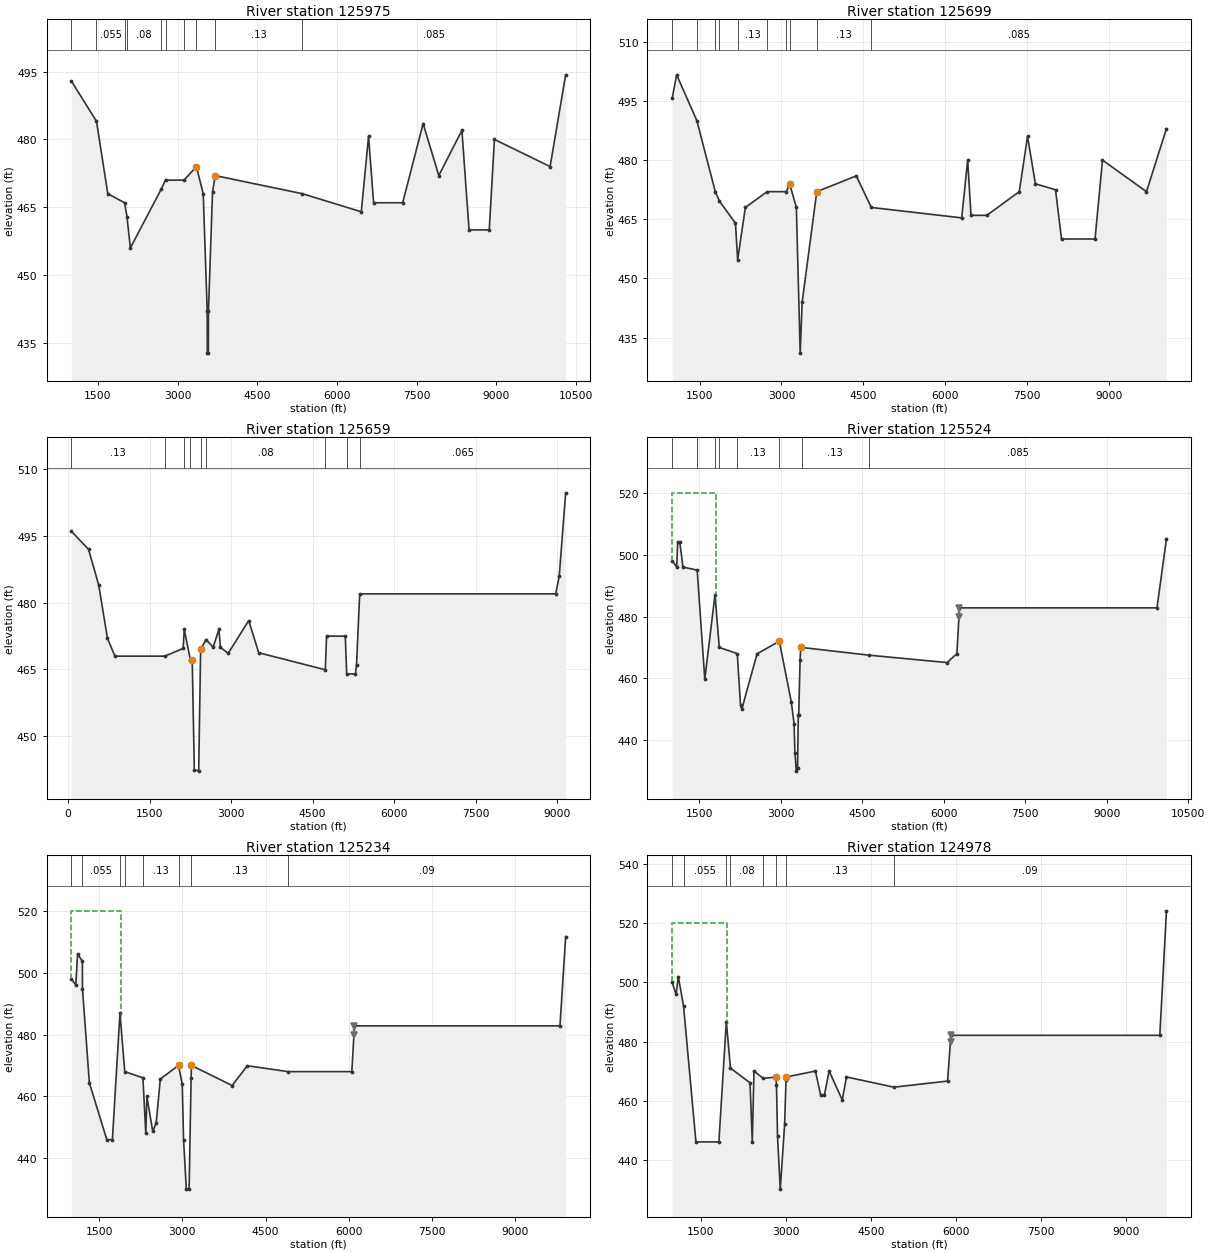
Type RM Length L Ch R = 1 ,125975  ,276,276,276
BEGIN DESCRIPTION:
This cross section corresponds to cross section 126020 of the non-georeferenced CDC model which was the source of this model.
END DESCRIPTION:
XS GIS Cut Line= 5
  2388874.970316 6977784.8132162 2388428.3557245 6976450.1777622
   2388430.96005 6975684.5529811 2390177.4877249 6971625.0909556
 2391249.2213574 6969134.0557175
#Sta/Elev= 30
    1000  492.91 1472.77     484 1685.46     468 2001.02     466 2046.58  462.94
 2110.24     456    2691     469    2772     471    3123     471    3352     474
 3482.03     468 3556.67     442 3558.44  432.75 3578.44  432.75  3580.2     442
  3656.7  468.36 3707.28     472 5347.81     468 6457.58     464 6593.87  480.72
 6688.92     466  7236.3     466 7621.13  483.51 7915.76     472 8351.17     482
 8485.75     460 8865.87     460 8962.86     480 10011.3     47410304.04  494.28
#Mann= 10 ,-1,0
    1000     .08       0 1472.77    .055       0 2001.02     .04       0
 2046.58     .08       0    2691     .13       0    2772     .06       0
    3123     .13       0    3352     .05       0 3707.28     .13       0
 5347.81    .085       0
Bank Sta=3352,3707.28
XS Rating Curve= 0 ,0
Exp/Cntr=0.3,0.1

Type RM Length L Ch R = 1 ,125699  ,41,41,41
BEGIN DESCRIPTION:
This cross section corresponds to cross section 125742 of the non-georeferenced CDC model which was the source of this model.
---------------------------------------------------------------------
CDC FW041812-01 XTO-BASS ARLINGTON PAD SITE
CROSS-SECTION 125742 - 126600
LOCATED IN LOB.
---------------------------------------------------------------------
END DESCRIPTION:
XS GIS Cut Line= 5
  2389170.543216 6977755.9504131 2388736.5155413 6976439.7611163
   2388734.34527 6975682.3827098 2390466.1160847 6971246.6189436
 2391245.1213645 6969251.2721202
#Sta/Elev= 30
    1000  495.67 1081.02  501.61 1451.33     490 1788.79     472 1865.14   469.6
 2158.22     464 2198.04  454.75 2339.61     468    2738     472    3092     472
    3149     474 3272.48     468 3342.83  431.08 3378.71     444 3646.36     472
 4369.45     476 4644.66     468 6298.87  465.36 6408.27     480 6468.96     466
 6759.63     466 7352.94     472 7503.87     486 7647.94     474 8016.48  472.48
 8125.92     460 8739.59     460 8875.92     480 9681.33     47210047.14     488
#Mann= 10 ,-1,0
    1000     .08       0 1451.33    .055       0 1788.79     .04       0
 1865.14     .08       0 2198.04     .13       0    2738     .06       0
    3092     .13       0    3149     .05       0 3646.36     .13       0
 4644.66    .085       0
Bank Sta=3149,3646.36
XS Rating Curve= 0 ,0
Exp/Cntr=0.3,0.1

Type RM Length L Ch R = 1 ,125659  ,218,135,58
BEGIN DESCRIPTION:
This cross section corresponds to cross section 125701 of the non-georeferenced CDC model which was the source of this model.
---------------------------------------------------------------------
CDC FW022811-01 QUICKSILVER EAST AND WEST VILLAGE CREEK PAD SITES
CROSS-SECTION 125701 - 133770
DOWNSTREAM END
---------------------------------------------------------------------
END DESCRIPTION:
XS GIS Cut Line= 6
       2389187.7      6977750.24 2388770.6871038 6976462.3259077
 2388768.5168325 6975704.9475012 2390500.2876472  6971269.183735
 2391295.0475516 6969233.4829617 2391306.4841294 6969204.1892718
#Sta/Elev= 30
   63.22  496.07  378.73     492   565.6     484  727.09     472  864.14     468
 1781.81     468 2119.09469.7464 2138.73 474.001 2252.39467.1733 2285.66467.2199
 2324.26442.4988 2405.04442.1572 2440.27469.5142 2540.09471.7369 2670.93     470
 2775.19     474 2805.71     470 2946.22  468.61  3324.9     476 3507.86  468.77
  4733.4  464.94 4756.08   472.5 5101.08   472.5 5126.58     464    5286     464
    5307     466    5366     482 8971.49     482 9035.63     486 9153.68  504.71
#Mann= 9 ,-1,0
   63.22     .13       0 1781.81     .07       0 2138.73     .13       0
 2252.39     .05       0 2440.27     .13       0 2540.09     .08       0
  4733.4    .023       0 5126.58     .08       0    5366    .065       0
Bank Sta=2285.66,2440.27
XS Rating Curve= 0 ,0
Exp/Cntr=0.3,0.1

Type RM Length L Ch R = 1 ,125524  ,229,290,259
BEGIN DESCRIPTION:
This cross section corresponds to cross section 125562 of the non-georeferenced CDC model which was the source of this model.
---------------------------------------------------------------------
CDC ARL021910-1 ARLINGTON LANDFILL
CROSS-SECTION 116053-125562
UPSTREAM END
---------------------------------------------------------------------
END DESCRIPTION:
XS GIS Cut Line= 4
   2389320.42513   6977750.35397   2388837.06685   6975913.59485
   2390016.65209   6972720.08614   2391693.30097    6969314.4381
#Sta/Elev= 30
    1000     498 1083.35     496 1100.88     504 1140.48     504 1198.36     496
    1460     495    1600   459.7    1788  487.11  1866.4     470 2198.02     468
 2257.54  451.46 2280.55     450 2562.57  467.96 2971.77     472 3192.28  452.43
    3243   445.4    3260     436    3285     430    3308     431 3321.39     448
 3329.01     448 3354.51     466 3366.58     470  3380.8     470    4624   467.5
    6061   465.1    6241     468    6289   482.8  9924.7   482.810099.69  505.15
#Mann= 8 ,-1,0
    1000     .08       0    1460    .055       0    1788     .04       0
  1866.4     .08       0 2198.02     .13       0 2971.77     .05       0
  3380.8     .13       0    4624    .085       0
Levee=0,,,-1,6289,480,,
#XS Ineff= 1 ,-1
    1000    1798     520
Permanent Ineff=
       T
Bank Sta=2971.77,3366.58
XS Rating Curve= 0 ,0
Exp/Cntr=0.3,0.1

Type RM Length L Ch R = 1 ,125234  ,210,256,240
BEGIN DESCRIPTION:
This cross section corresponds to cross section 125286 of the non-georeferenced CDC model which was the source of this model.
END DESCRIPTION:
XS GIS Cut Line= 5
  2389532.435209 6977736.3198749  2389093.198883 6976027.9866774
 2390200.8377438 6972897.7780428 2391837.9906375 6969522.7782311
 2391868.7784544 6969459.3089751
#Sta/Elev= 30
    1000     498 1079.56     496 1111.79     506 1198.18  503.74    1200  494.75
    1324   464.4    1638     446    1739     446  1875.5  486.96 1961.84     468
 2289.23     466 2340.82     448 2360.83     460 2465.96  448.67 2528.22  451.38
 2601.92   465.6 2930.17     470 2997.66     464 3021.26     446    3071     430
    3121     430 3157.25     466 3163.15     470 3896.61  463.51  4169.9   469.9
    4905     468    6053     468    6101   482.8 9803.53   482.8 9905.96  511.66
#Mann= 8 ,-1,0
    1000     .08       0    1200    .055       0  1875.5     .04       0
 1961.84     .08       0 2289.23     .13       0 2930.17     .05       0
 3157.25     .13       0    4905     .09       0
Levee=0,,,-1,6101,480,,
#XS Ineff= 1 ,-1
    1000  1885.5     520
Permanent Ineff=
       T
Bank Sta=2930.17,3163.15
XS Rating Curve= 0 ,0
Exp/Cntr=0.3,0.1

Type RM Length L Ch R = 1 ,124978  ,311,416,173
BEGIN DESCRIPTION:
This cross section corresponds to cross section 125016 of the non-georeferenced CDC model which was the source of this model.
END DESCRIPTION:
XS GIS Cut Line= 4
   2389740.61786   6977723.96393   2389335.93396   6976089.66602
   2390396.79011   6973028.61111   2392041.61687   6969614.79084
#Sta/Elev= 30
    1000     500  1069.3     496 1107.65     502    1200     492    1418     446
    1823     446    1954  486.75    2027     471 2371.99     466 2411.78     446
 2441.59     470 2605.96  467.49 2829.58     468 2838.51  465.16 2856.52     448
    2905     430 2982.01     452 3006.03  466.86 3014.16     468 3525.19     470
 3615.41     462 3684.32     462 3765.78     470  3997.8  460.22 4072.17     468
 4906.75  464.54    5854   466.6    5912   482.1 9595.03   482.1 9712.74  524.27
#Mann= 8 ,-1,0
    1000     .08       0    1200    .055       0    1954     .04       0
    2027     .08       0 2605.96     .13       0 2838.51     .05       0
 3006.03     .13       0 4906.75     .09       0
Levee=0,,,-1,5912,480,,
#XS Ineff= 1 ,-1
    1000    1964     520
Permanent Ineff=
       T
Bank Sta=2829.58,3014.16
XS Rating Curve= 0 ,0
Exp/Cntr=0.3,0.1

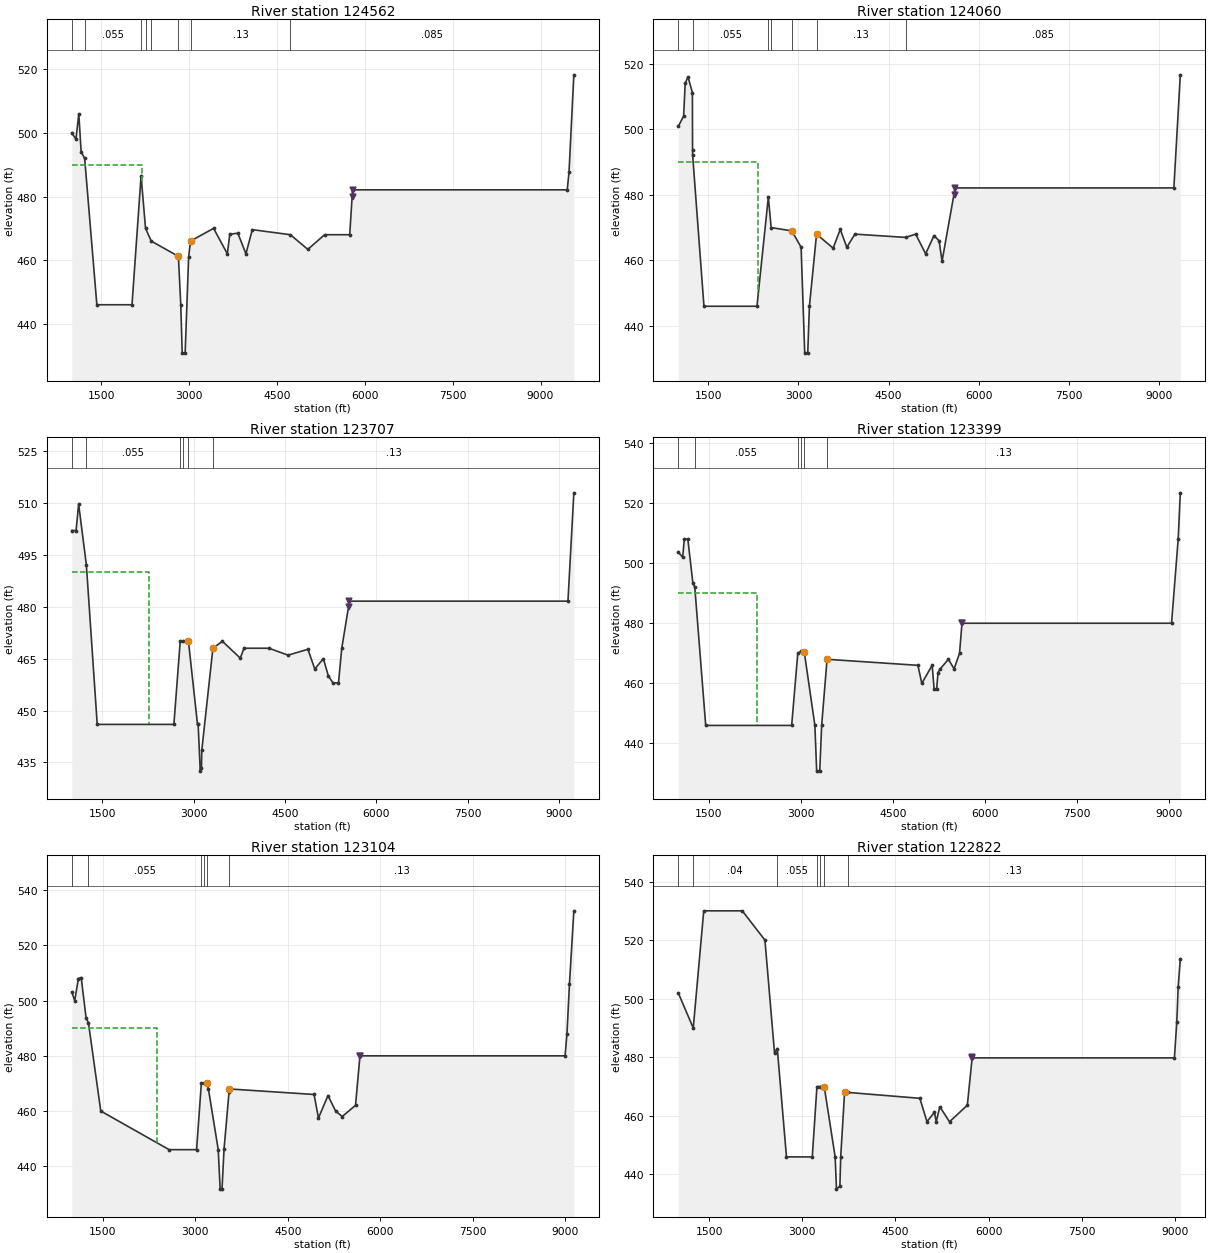
Type RM Length L Ch R = 1 ,124562  ,362,502,201
BEGIN DESCRIPTION:
This cross section corresponds to cross section 124600 of the non-georeferenced CDC model which was the source of this model.
END DESCRIPTION:
XS GIS Cut Line= 6
  2390007.276951 6977707.8241858   2390003.57239 6977648.6461657
 2389902.0099294 6976026.2504604 2389714.5096482 6975674.6878433
   2390477.53076 6973104.3753987 2392104.4494757 6969665.3599211
#Sta/Elev= 30
    1000  500.02  1071.3     498 1120.11     506 1160.02     494    1220     492
    1428     446    2028     446    2183  486.48  2258.9     470 2356.09     466
 2820.15  461.21    2860     446    2885   430.8    2935   430.8 2994.24  460.96
  3026.5     466 3420.17     470 3655.25     462 3696.98  468.15 3834.14  468.48
 3972.35     462 4081.23  469.59 4730.99     468 5028.45   463.4  5315.1     468
    5744     468    5792   482.1 9456.37   482.1 9486.23  487.57 9568.91  518.23
#Mann= 8 ,-1,0
    1000     .08       0    1220    .055       0    2183     .04       0
  2258.9     .08       0 2356.09     .13       0 2820.15     .05       0
  3026.5     .13       0 4730.99    .085       0
Levee=0,,,-1,5792,480,,
#XS Ineff= 1 ,-1
    1000    2193     490
Permanent Ineff=
       T
Bank Sta=2820.15,3026.5
XS Rating Curve= 0 ,0
Exp/Cntr=0.3,0.1

Type RM Length L Ch R = 1 ,124060  ,401,353,223
BEGIN DESCRIPTION:
This cross section corresponds to cross section 124110 of the non-georeferenced CDC model which was the source of this model.
END DESCRIPTION:
XS GIS Cut Line= 5
  2390275.190328 6977746.9998931   2390274.40551 6977734.5836579
 2390172.8430492 6976127.8129213 2390563.4682522 6973122.6046929
 2392138.9890513 6969773.6461677
#Sta/Elev= 30
    1000  500.86  1089.7     504 1115.98  513.99  1162.2     516 1235.94  511.14
    1238  493.61    1240     492    1428     446    2310     446    2499  479.28
  2546.1     470 2889.38     469 3044.48     464  3104.7   431.7  3154.7   431.7
 3182.63     446 3301.52     468 3576.77  463.72 3695.91  469.43 3804.58     464
 3939.78     468    4785     467 4950.58     468 5116.51     462 5255.23  467.54
 5340.02     466 5389.68  459.76    5607   482.1 9246.82   482.1 9353.96   516.6
#Mann= 7 ,-1,0
    1000     .08       0    1240    .055       0    2499     .04       0
  2546.1     .13       0 2889.38     .05       0 3301.52     .13       0
    4785    .085       0
Levee=0,,,-1,5607,480,,
#XS Ineff= 1 ,-1
    1000    2331     490
Permanent Ineff=
       T
Bank Sta=2889.38,3301.52
XS Rating Curve= 0 ,0
Exp/Cntr=0.3,0.1

Type RM Length L Ch R = 1 ,123707  ,311,308,243
BEGIN DESCRIPTION:
This cross section corresponds to cross section 123744 of the non-georeferenced CDC model which was the source of this model.
END DESCRIPTION:
XS GIS Cut Line= 4
  2390536.929823 6977746.1725683   2390536.92992   6977746.16795
   2390632.39889   6973184.36704   2392191.04111   6969848.53184
#Sta/Elev= 30
    1000     502 1070.69     502 1112.73  509.64    1240     492    1418     446
    2677     446    2781     470    2831     470    2916     470 3064.72     446
 3075.36     446    3110   432.5    3130   433.5    3135   438.5 3317.83     468
 3473.31     470    3767  465.15 3828.25     468 4237.24     468 4551.27     466
 4877.43  467.69 4991.06     462 5131.87     465 5212.93     460 5289.21     458
 5379.95     458 5433.71     468    5560   481.6 9148.12   481.6 9244.81  512.89
#Mann= 6 ,-1,0
    1000     .09       0    1240    .055       0    2781     .04       0
    2831     .09       0    2916     .05       0 3317.83     .13       0
Levee=0,,,-1,5560,480,,
#XS Ineff= 1 ,-1
       0    2269     490
Permanent Ineff=
       T
Bank Sta=2916,3317.83
XS Rating Curve= 0 ,0
Exp/Cntr=0.3,0.1

Type RM Length L Ch R = 1 ,123399  ,335,295,261
BEGIN DESCRIPTION:
This cross section corresponds to cross section 123437 of the non-georeferenced CDC model which was the source of this model.
END DESCRIPTION:
XS GIS Cut Line= 4
   2390897.30131 6977827.4877882  2390897.203477 6977817.4279804
 2390852.2960866 6973199.8007327 2392336.8275663 6969963.2035314
#Sta/Elev= 30
    1000  503.64  1072.2     502 1099.39     508  1156.4     508 1238.93  493.34
    1270     492    1448     446    2850     446    2950     470  3005.4  470.65
  3054.8  470.54 3228.73     446    3258   430.8    3308   430.8 3339.01     446
 3427.18     468 4908.99     466 4972.34     460 5141.47     466  5173.9     458
 5213.76     458 5237.26  463.59 5267.44  464.69 5406.68     468 5499.29  464.81
    5588     470    5628     480 9045.75     480 9153.99     508 9188.72  523.38
#Mann= 6 ,-1,0
    1000     .09       0    1270    .055       0    2950     .04       0
  3005.4     .09       0  3054.8     .05       0 3427.18     .13       0
Levee=0,,,-1,5628,480,,
#XS Ineff= 1 ,-1
    1000    2285     490
Permanent Ineff=
       T
Bank Sta=3054.8,3427.18
XS Rating Curve= 0 ,0
Exp/Cntr=0.3,0.1

Type RM Length L Ch R = 1 ,123104  ,313,282,245
BEGIN DESCRIPTION:
This cross section corresponds to cross section 123144 of the non-georeferenced CDC model which was the source of this model.
END DESCRIPTION:
XS GIS Cut Line= 4
  2391255.473889 6977888.0837214  2391253.685047 6977842.3124451
 2391072.2615259 6973200.2114931 2392478.5116662 6970054.3782178
#Sta/Elev= 30
    1000  503.15 1047.68     500 1107.55     508 1152.74  508.37 1232.27   493.7
    1270     492    1470     460    2578     446    3023     446    3100     470
    3150     470  3187.4     470 3214.54     468 3373.82     446    3405   431.7
    3435   431.7  3467.5   446.1 3548.83  466.85 3553.36     468 4927.28     466
 4997.89  457.45 5152.81  465.61 5275.74     460 5383.05     458  5598.6  462.07
    5671     480 8995.42     480 9025.77     488 9066.15     506 9137.29  532.55
#Mann= 6 ,-1,0
    1000     .09       0    1270    .055       0    3100     .04       0
    3150     .09       0  3187.4     .05       0 3548.83     .13       0
Levee=0,,,-1,5671,480,,
#XS Ineff= 1 ,-1
    1000    2388     490
Permanent Ineff=
       T
Bank Sta=3187.4,3553.36
XS Rating Curve= 0 ,0
Exp/Cntr=0.3,0.1

Type RM Length L Ch R = 1 ,122822  ,302,285,227
BEGIN DESCRIPTION:
This cross section corresponds to cross section 122858 of the non-georeferenced CDC model which was the source of this model.
END DESCRIPTION:
XS GIS Cut Line= 3
   2391617.86411   6977958.18787   2391280.48289   6973223.82103
   2392626.45002   6970162.66015
#Sta/Elev= 30
    1000     502    1242     490    1411     530    2032     530    2397     520
 2551.58   481.5    2596     483    2744     446    3160     446    3235     470
    3285     470 3352.13     470  3528.8     446    3550     435    3605     436
 3618.01     446 3680.43     468 3739.37     468 4893.27     466 5007.89  458.04
  5128.7  461.21 5157.14     458 5215.15  463.11 5371.34     458 5658.63  463.64
    5736   479.8 8995.25   479.8 9033.55     492  9055.7     504 9090.37  513.58
#Mann= 7 ,-1,0
    1000     .09       0    1242     .04       0    2596    .055       0
    3235     .04       0    3285     .13       0 3352.13     .05       0
 3739.37     .13       0
Levee=0,,,-1,5736,480,,
Bank Sta=3352.13,3680.43
XS Rating Curve= 0 ,0
Exp/Cntr=0.3,0.1

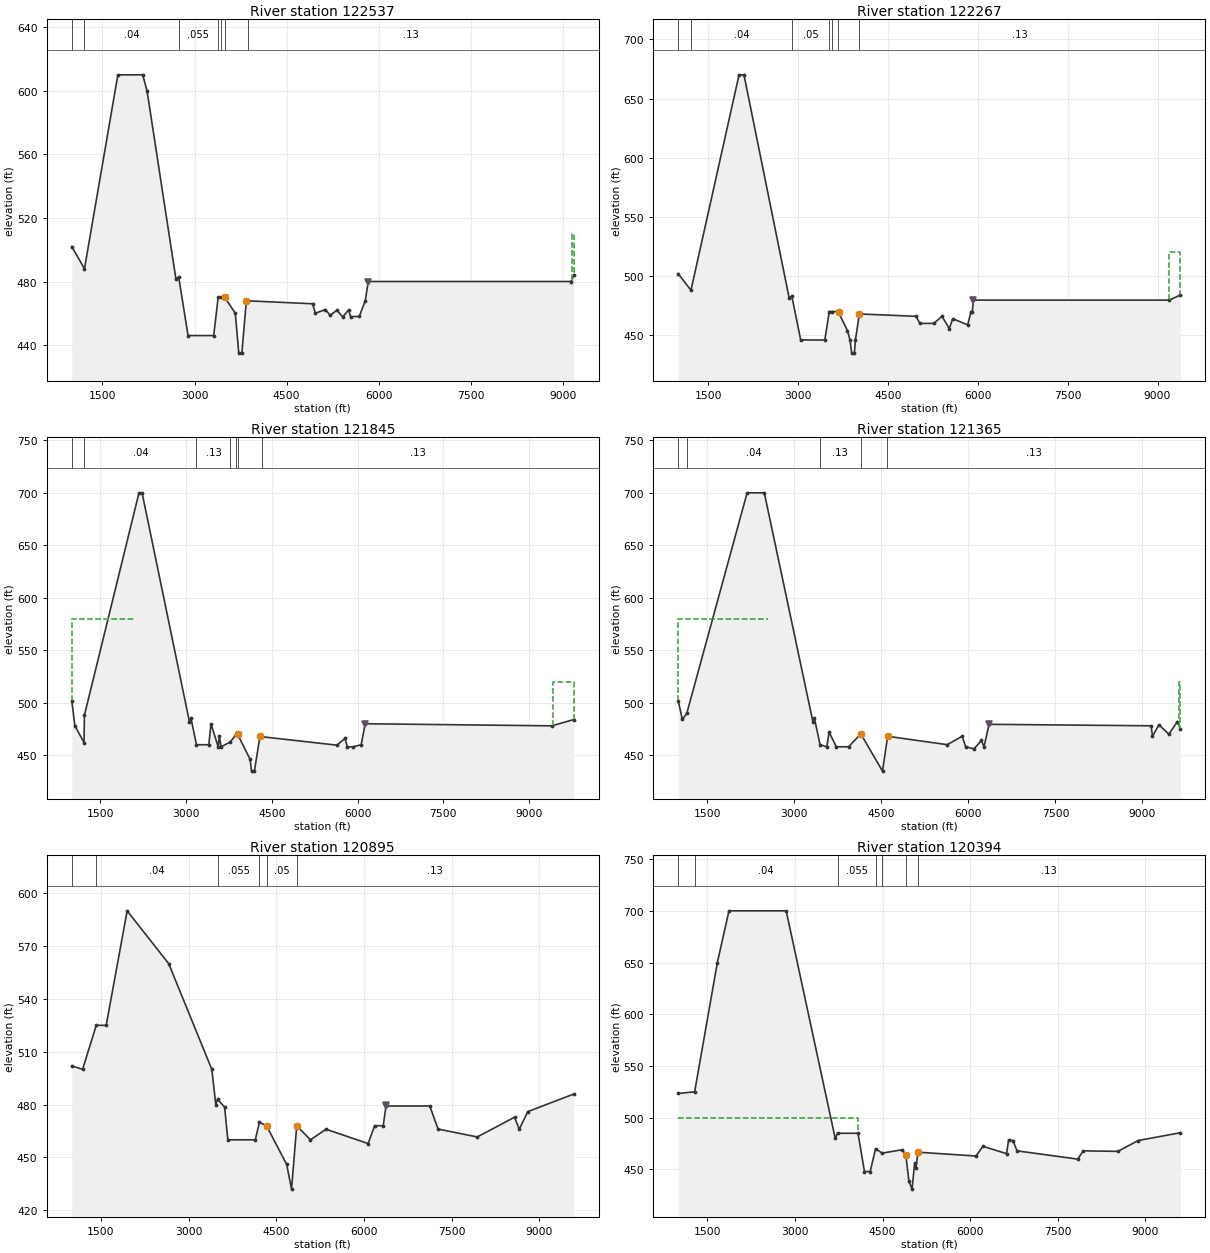
Type RM Length L Ch R = 1 ,122537  ,299,270,224
BEGIN DESCRIPTION:
This cross section corresponds to cross section 122578 of the non-georeferenced CDC model which was the source of this model.
END DESCRIPTION:
XS GIS Cut Line= 5
  2391978.100513 6978072.7867457  2391977.137012  6978062.827424
 2391511.6422088  6973251.195315 2392947.2613848 6970283.5450823
2392963.282608246970250.42669807
#Sta/Elev= 30
    1000     502    1207     488    1751     610    2155     610    2226     600
 2696.58   481.5    2741     483    2894     446    3312     446    3384     470
    3434     470 3492.52     470 3663.85     460    3720  434.95    3770  434.95
 3844.38     468 3865.82  467.84 4924.04     466 4965.29     460 5130.79  462.38
 5208.98  458.67 5316.36  461.93  5413.7  457.75 5508.21  462.12 5541.14  457.94
 5682.84     458    5781     468    5829     480 9133.24     480 9177.55     484
#Mann= 7 ,-1,0
    1000     .09       0    1207     .04       0    2741    .055       0
    3384     .04       0    3434     .09       0 3492.52     .05       0
 3865.82     .13       0
Levee=0,,,-1,5829,480,,
#XS Ineff= 2 ,-1
       0    2500   479.1 9140.76 9177.55     510
Permanent Ineff=
       T       F
Bank Sta=3492.52,3844.38
XS Rating Curve= 0 ,0
Exp/Cntr=0.3,0.1

Type RM Length L Ch R = 1 ,122267  ,539,422,405
BEGIN DESCRIPTION:
This cross section corresponds to cross section 122304 of the non-georeferenced CDC model which was the source of this model.
END DESCRIPTION:
XS GIS Cut Line= 4
   2392336.84397   6978167.12807   2391726.70805   6973268.33111
   2393271.58488   6970394.219072393357.279874226970234.79081665
#Sta/Elev= 30
    1000     502    1212     488    2015     670    2097     670 2851.58   481.5
    2896     483    3044     446    3447     446    3521     470    3571     470
 3665.77     470 3675.17  469.31 3823.93     454 3867.94     446    3895     435
    3940   434.9 3957.83     446 4023.01     468 4969.97     466 5033.93     460
  5266.5     460 5401.55     466 5524.94   455.7 5582.02     464 5832.03  458.76
 5886.82     470 5908.76  470.01    5926   479.7 9199.65   479.7 9380.65     484
#Mann= 7 ,-1,0
    1000     .09       0    1212     .04       0    2896     .05       0
    3521     .04       0    3571     .09       0 3665.77     .05       0
 4023.01     .13       0
Levee=0,,,-1,5926,480,,
#XS Ineff= 2 ,-1
       0    2500  478.99 9199.65 9380.65     520
Permanent Ineff=
       T       F
Bank Sta=3675.17,4023.01
XS Rating Curve= 0 ,0
Exp/Cntr=0.3,0.1

Type RM Length L Ch R = 1 ,121845  ,460,480,345
BEGIN DESCRIPTION:
This cross section corresponds to cross section 121885 of the non-georeferenced CDC model which was the source of this model.
END DESCRIPTION:
XS GIS Cut Line= 5
  2392934.922293 6978346.7119413   2392933.73418 6978339.8455707
 2392057.4321277 6973275.5010407 2393585.4271033 6970382.4887821
 2393756.10261766970059.34219915
#Sta/Elev= 30
    1000     502 1054.54  478.03 1215.04     462  1220.7     488    2176     700
    2230     700    3058     482    3086     485    3182     460 3398.05     460
 3435.39     480 3561.52     458 3580.61     468 3613.07     458 3773.31  462.65
 3878.42     470  3901.4     470  4120.4     446    4145  434.85    4195  434.85
 4292.05     468 4323.75  467.63 5638.54   459.6 5781.26     466 5820.54     458
 5924.02     458 6062.45     460    6134     480 9398.97     478 9783.76     484
#Mann= 7 ,-1,0
    1000     .09       0  1220.7     .04       0    3182     .13       0
 3773.31     .09       0 3878.42     .13       0  3901.4     .05       0
 4323.75     .13       0
Levee=0,,,-1,6134,480,,
#XS Ineff= 2 ,-1
       0 2081.01     580 9418.31 9783.76     520
Permanent Ineff=
       F       F
Bank Sta=3901.4,4292.05
XS Rating Curve= 0 ,0
Exp/Cntr=0.3,0.1

Type RM Length L Ch R = 1 ,121365  ,389,470,599
BEGIN DESCRIPTION:
This cross section corresponds to cross section 121401 of the non-georeferenced CDC model which was the source of this model.
END DESCRIPTION:
XS GIS Cut Line= 4
   2393532.90785   6978515.49187   2392989.30887   6975608.10005
   2392373.15394   6973274.88293   2393895.63514   6970368.50784
#Sta/Elev= 30
    1000     502 1070.87     484  1147.9     490    2187     700    2483     700
    3320     482    3348     485    3444     460 3560.38     458  3599.8     472
 3724.17     458 3934.87     458 4140.99     470 4149.42     470    4520   434.8
 4605.47  466.89 4608.69     468 5635.51     460 5892.36     468 5953.27     458
 6096.46     456 6224.52     464 6269.53     458    6356   479.4 9148.57     478
  9172.7     468 9283.87  479.04 9452.94     470 9603.19     482 9651.98  475.13
#Mann= 5 ,-1,0
    1000     .09       0  1147.9     .04       0    3444     .13       0
 4140.99     .05       0 4605.47     .13       0
Levee=0,,,-1,6356,480,,
#XS Ineff= 2 ,-1
       0 2540.01     580 9637.74 9651.98     520
Permanent Ineff=
       F       F
Bank Sta=4149.42,4608.69
XS Rating Curve= 0 ,0
Exp/Cntr=0.3,0.1

Type RM Length L Ch R = 1 ,120895  ,599,501,399
BEGIN DESCRIPTION:
This cross section corresponds to cross section 120930 of the non-georeferenced CDC model which was the source of this model.
END DESCRIPTION:
XS GIS Cut Line= 5
   2393841.16806   6978605.57207   2393036.23594   6973279.50694
   2394241.37297   6971189.000952394511.087914816970721.13655476
2394635.946686996970504.54872728
#Sta/Elev= 30
    1000     502    1185     500    1419     525    1589     525  1947.4     590
 2658.72     560    3396     500    3464     480    3495     483  3614.8  478.56
    3670     460    4140     460    4210     470 4331.52     468  4676.8     446
    4760     432 4848.52     468 5083.05     460 5350.68     466 6070.55  457.86
 6180.38     468    6328     468    6376   479.2    7125   479.2  7266.5   466.1
 7936.78  461.63 8575.89  472.81 8655.56     466  8801.8     476  9589.6     486
#Mann= 6 ,-1,0
    1000     .09       0    1419     .04       0    3495    .055       0
    4210     .13       0 4331.52     .05       0 4848.52     .13       0
Levee=0,,,-1,6376,480,,
#XS Ineff= 1 ,-1
    1000    3400  478.56
Permanent Ineff=
       T
Bank Sta=4331.52,4848.52
XS Rating Curve= 0 ,0
Exp/Cntr=0.3,0.1

Type RM Length L Ch R = 1 ,120394  ,453,693,1087
BEGIN DESCRIPTION:
This cross section corresponds to cross section 120428 of the non-georeferenced CDC model which was the source of this model.
END DESCRIPTION:
XS GIS Cut Line= 6
      2394715.55       6978688.4      2393380.09     6973203.916
     2394405.682     6971467.403  2394425.264383  6971434.246479
2394755.913786516970874.397154682394882.945671486970659.30916658
#Sta/Elev= 30
    1000  523.49    1281     525    1670     650    1869     700    2849     700
  3689.1     480 3728.15     485    4079     485 4190.18     448    4288     448
    4380     470    4494   465.8    4837   469.1    4899   464.1    4950     439
    5005     431    5050   456.5    5072   451.7    5107   466.7    6101     463
    6218   472.4    6623   465.3    6659   478.5  6731.8     478  6803.8     468
  7843.9     460  7935.8     468  8531.4   467.5  8880.2     478    9600   485.5
#Mann= 7 ,-1,0
    1000     .09       0    1281     .04       0 3728.15    .055       0
    4380     .09       0    4494     .13       0    4899    .055       0
    5107     .13       0
#XS Ineff= 1 ,-1
    1000    4079     500
Permanent Ineff=
       T
Bank Sta=4899,5107
XS Rating Curve= 0 ,0
Exp/Cntr=0.3,0.1

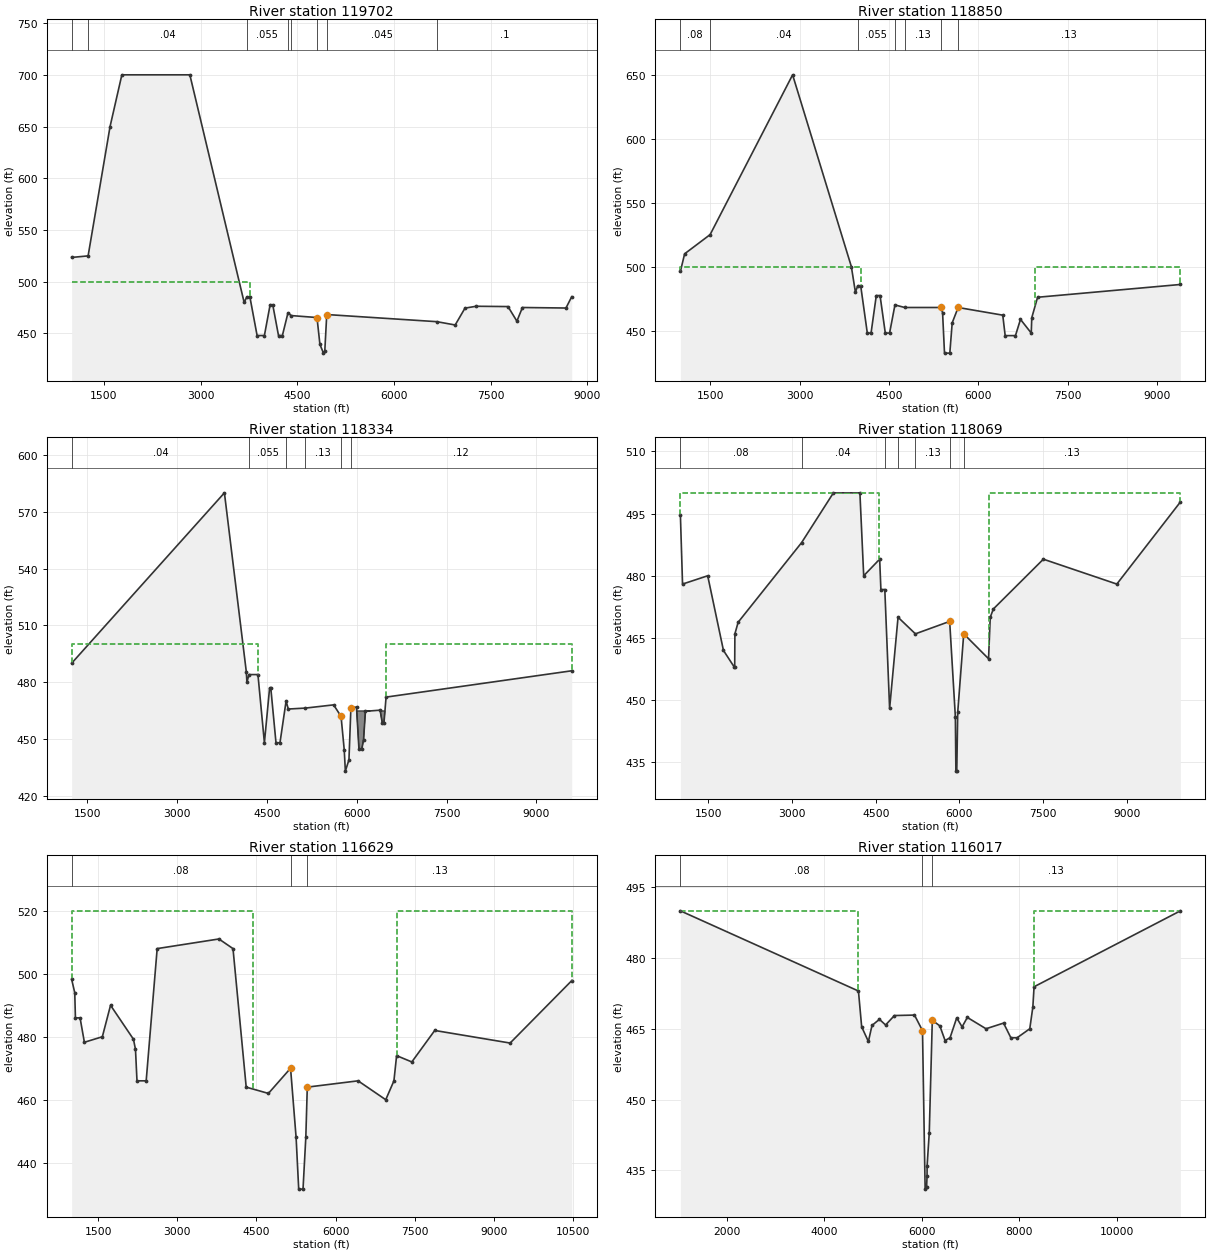
Type RM Length L Ch R = 1 ,119702  ,559,851,527
BEGIN DESCRIPTION:
This cross section corresponds to cross section 119740 of the non-georeferenced CDC model which was the source of this model.
END DESCRIPTION:
XS GIS Cut Line= 4
   2394732.16201   6978693.19165   2394398.25553   6975203.13695
 2394812.1052536 6972642.35400672395076.144963936971008.55229555
#Sta/Elev= 30
    1000  523.49    1255     525  1595.4     650  1778.4     700  2832.9     700
  3675.2     480  3714.2     485    3765     485    3876     448    3989     448
    4078  477.76 4118.51  477.76 4207.78     448    4268     448    4355     470
    4405   467.3    4805   465.4    4850   439.5    4905     431    4926   433.2
    4956   468.3    6664   461.4    6948   458.2    7100   474.5    7274   476.3
    7767     476    7905   461.9    7991   475.1    8666   474.6    8755   485.5
#Mann= 8 ,-1,0
    1000     .08       0    1255     .04       0  3714.2    .055       0
    4355     .08       0    4405     .13       0    4805    .055       0
    4956    .045       0    6664      .1       0
#XS Ineff= 1 ,-1
    1000    3765     500
Permanent Ineff=
       T
Bank Sta=4805,4956
XS Rating Curve= 0 ,0
Exp/Cntr=0.3,0.1

Type RM Length L Ch R = 1 ,118850  ,338,516,320
BEGIN DESCRIPTION:
This cross section corresponds to cross section 118883 of the non-georeferenced CDC model which was the source of this model.
END DESCRIPTION:
XS GIS Cut Line= 5
  2395083.250572  6978901.396929  2395083.604225 6978874.4376774
 2395140.0276686 6974573.2221985 2394901.8765701  6974320.704987
 2395252.8748838 6970623.5696647
#Sta/Elev= 30
    1000  496.19 1071.41     510 1498.73     525  2882.8     650  3868.4     500
  3936.4     480  3975.6     485 4025.26     485 4136.26     448    4199     448
    4287  477.34    4350  477.34    4438     448    4510     448    4600     470
 4763.26     468    5370     468    5399     464 5431.33   432.3 5520.52   432.3
 5560.42     456 5660.13     468 6408.77     462 6449.24     446 6621.78     446
 6706.18   458.7 6886.76     448 6895.43     460 6993.17     476 9389.41     486
#Mann= 7 ,-1,0
    1000     .08       0 1498.73     .04       0  3975.6    .055       0
    4600     .08       0 4763.26     .13       0    5370     .06       0
 5660.13     .13       0
#XS Ineff= 3 ,-1
    1000 4025.26     500                            6951 9389.41     500
Permanent Ineff=
       F       F       T
#Block Obstruct= 2 , 0
       0                    6000       0   464.8
Bank Sta=5370,5660.13
XS Rating Curve= 0 ,0
Exp/Cntr=0.3,0.1

Type RM Length L Ch R = 1 ,118334  ,257,265,61
BEGIN DESCRIPTION:
This cross section corresponds to cross section 118369 of the non-georeferenced CDC model which was the source of this model.
END DESCRIPTION:
XS GIS Cut Line= 6
  2395440.313041 6978817.8179206 2395443.7717583 6973819.8191173
 2395443.8824815 6973659.8191556 2395443.8963219 6973639.8191604
 2395443.9032421 6973629.81916282395446.092103376970466.81992018
#Sta/Elev= 30
    1239     490    3790     580  4155.6   485.5  4165.6     480 4200.75     484
 4349.89     484 4457.89     448 4544.62  476.91 4564.62  476.91  4651.4     448
    4718     448    4820     470    4857   465.8    5144   466.3    5614     468
    5738   461.9    5791   444.3    5810     433    5870     439    5902   466.1
    5996   466.9    6037   444.6    6085   444.7    6114   449.6    6145   464.6
    6390   465.2    6428   458.2    6454   458.2    6490   472.1    9590     486
#Mann= 6 ,-1,0
    1239     .04       0 4200.75    .055       0    4820     .08       0
    5144     .13       0    5738     .06       0    5902     .12       0
#XS Ineff= 2 ,-1
    1000 4349.89     500    6490    9590     500
Permanent Ineff=
       T       F
#Block Obstruct= 1 ,-1
    5996 6489.99   464.8
Bank Sta=5738,5902
XS Rating Curve= 0 ,0
Exp/Cntr=0.3,0.1

Type RM Length L Ch R = 1 ,118069  ,1399,1440,330
BEGIN DESCRIPTION:
This cross section corresponds to cross section 118100 of the non-georeferenced CDC model which was the source of this model.
END DESCRIPTION:
XS GIS Cut Line= 6
  2395760.713111 6979297.4298475 2395766.7639479 6976982.2934958
 2395763.2915139 6975860.7658832 2395770.2360538 6975242.7103608
 2395463.3783998 6970504.2119638      2395452.19      6970348.02
#Sta/Elev= 30
    1000  494.75 1038.75     478 1489.33     480 1771.69     462 1965.04     458
 1973.14     458 1976.69     466 2035.09   468.8  3172.3     488  3742.2     500
  4216.6     500  4284.6     480  4570.7     484 4592.66  476.68  4662.9  476.68
    4749     448    4900     470    5211     466    5825     469 5927.01     446
 5936.54   432.9 5952.36   432.9 5969.27  447.08 6076.95     466  6521.7     460
 6552.17     470 6608.18     472    7504     484 8820.07     478 9959.48   497.8
#Mann= 7 ,-1,0
    1000     .08       0  3172.3     .04       0  4662.9    .055       0
    4900     .08       0    5211     .13       0    5825     .06       0
 6076.95     .13       0
#XS Ineff= 2 ,-1
    1000    4565     500    6531 9959.48     500
Permanent Ineff=
       T       T
Bank Sta=5825,6076.95
XS Rating Curve= 0 ,0
Exp/Cntr=0.3,0.1

Type RM Length L Ch R = 1 ,116629  ,595,612,140
BEGIN DESCRIPTION:
This cross section corresponds to cross section 116664 of the non-georeferenced CDC model which was the source of this model.
END DESCRIPTION:
XS GIS Cut Line= 5
  2396589.089219 6979403.0000038  2396589.255085  6979334.663463
 2396600.1057852 6974864.1773252 2395853.5780788 6974100.2884331
 2395449.8452904 6970257.0592429
#Sta/Elev= 30
    1000  498.22 1058.29     494 1071.33     486 1159.07     486 1240.91  478.25
 1581.06     480  1736.4     490 2170.07  479.22 2208.81     476 2237.19     466
 2411.38     466 2619.58     508 3789.23  511.06 4055.85     508 4305.89     464
 4726.63     462 5146.23     470 5251.18     448 5300.52   431.6 5382.09   431.6
    5435     448    5463     464    6425     466    6949     460 7104.06     466
 7154.89     474 7443.08     472 7877.16     482 9305.03     47810471.31  497.81
#Mann= 3 ,-1,0
    1000     .08       0 5146.23     .06       0    5463     .13       0
#XS Ineff= 2 ,-1
    1000    4430     520    716310471.31     520
Permanent Ineff=
       T       T
Bank Sta=5146.23,5463
XS Rating Curve= 0 ,0
Exp/Cntr=0.3,0.1

Type RM Length L Ch R = 1 ,116017  ,1064,3493,1757
BEGIN DESCRIPTION:
This cross section corresponds to cross section 116053 of the non-georeferenced CDC model which was the source of this model.
---------------------------------------------------------------------
CDC ARL021910-1 ARLINGTON LANDFILL
CROSS-SECTION 116053-125562
DOWNSTREAM END
---------------------------------------------------------------------
END DESCRIPTION:
XS GIS Cut Line= 6
2397836.890235056979581.69371645  2397880.702198 6975931.9566695
   2397887.63011   6975354.82989   2396011.94784   6974211.57791
 2395930.1309836  6973631.1198982395477.915836636970422.83352345
#Sta/Elev= 30
    1050     490    4700     473    4766   465.4    4904   462.3    4978   465.7
    5130     467    5256   465.8    5438   467.8    5849   467.9    6013   464.6
    6067     431    6097   431.4    6106   433.7    6108     436    6152     443
    6214   466.8    6369   465.6    6476   462.5    6578   463.1    6714   467.3
    6825   465.4    6932   467.4    7315     465    7675   466.2    7824   463.1
    7954   463.1    8212     465    8275   469.6    8300   473.9   11300     490
#Mann= 3 ,0,0
    1050     .08       0    6013    .055       0    6214     .13       0
#XS Ineff= 2 ,-1
    1050    4700     490    8300   11300     490
Permanent Ineff=
       F       F
Bank Sta=6013,6214
XS Rating Curve= 0 ,0
Exp/Cntr=0.3,0.1

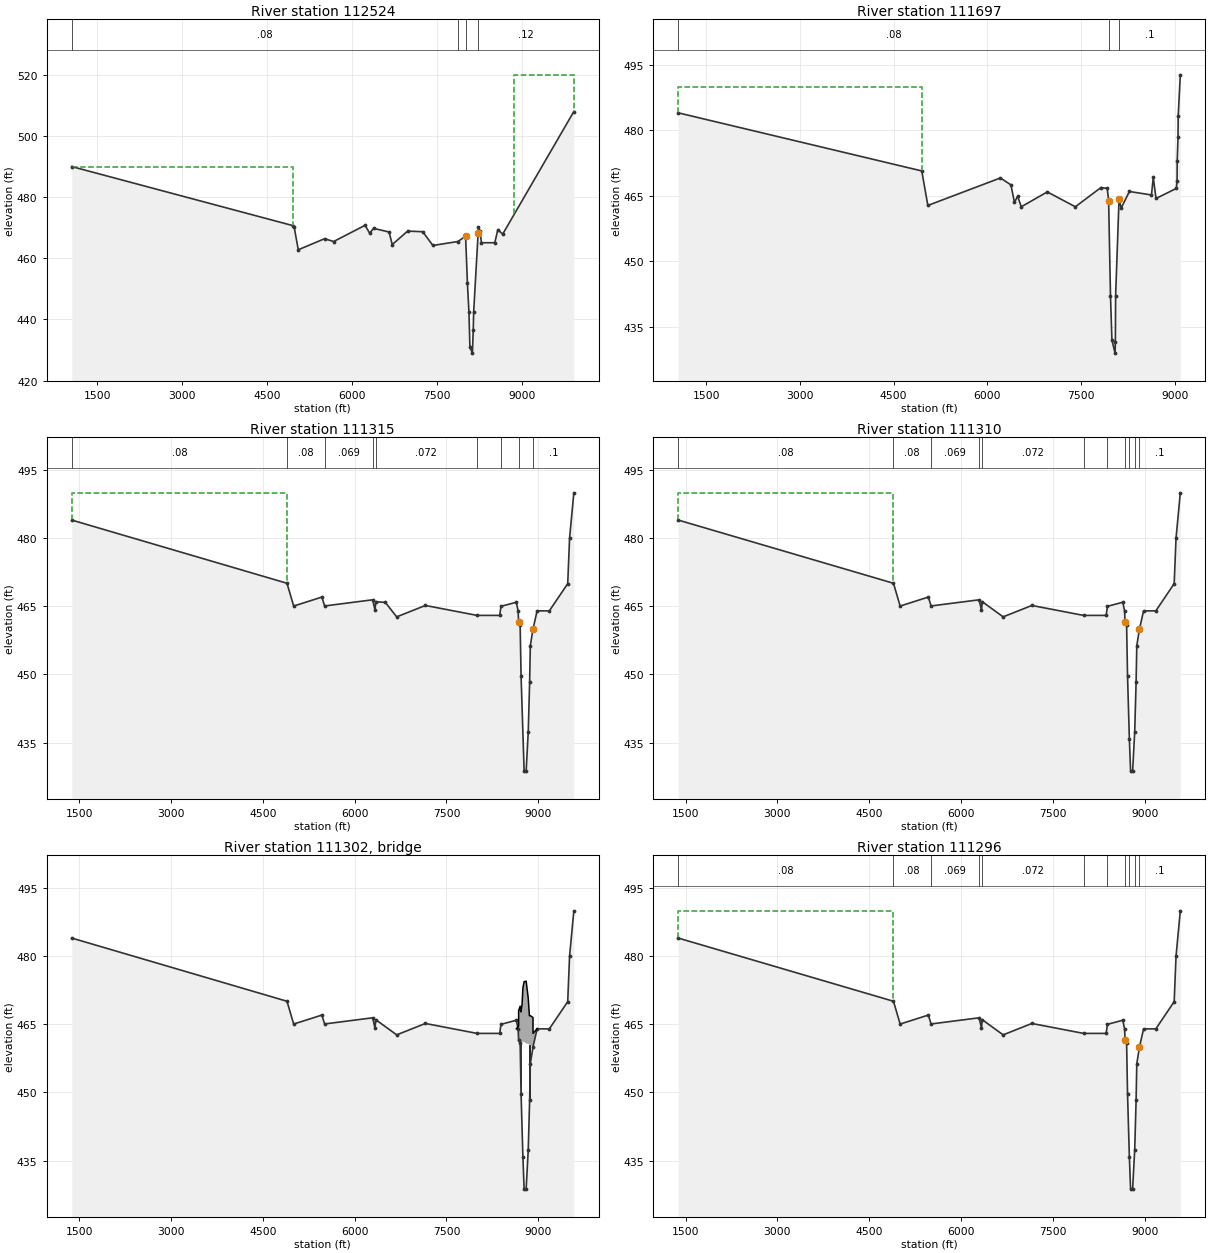
Type RM Length L Ch R = 1 ,112524  ,139,827,888
BEGIN DESCRIPTION:
This cross section corresponds to cross section 112574 of the non-georeferenced CDC model which was the source of this model.
Cross Section Truncated due to Ineffective Flow Areas
END DESCRIPTION:
XS GIS Cut Line= 6
      2398360.36      6979849.11      2398377.95      6975948.18
     2398375.625     6975269.703 2397355.0711938 6972774.1297082
 2397228.1415286 6972463.7469723  2396754.994459 6971306.7543835
#Sta/Elev= 30
    1050     490    4950   470.7    4976   470.1    5047   462.8    5510   466.4
    5672   465.5    6226   470.8    6307   468.2    6375   469.8    6650   468.6
    6705   464.5    6977   468.9    7243   468.7    7423   464.2    7863   465.5
    8000   467.2    8032   451.8    8059   442.3    8076   430.9    8120     429
    8135   436.6    8142   442.4    8221   468.2    8225   470.3    8253   468.9
    8280   465.1    8515   465.1    8569   469.4    8654   467.9    9910     508
#Mann= 4 ,-1,0
    1050     .08       0    7863     .12       0    8000     .05       0
    8221     .12       0
#XS Ineff= 2 ,-1
    1050    4950     490    8860    9910     520
Permanent Ineff=
       F       F
Bank Sta=8000,8221
XS Rating Curve= 0 ,0
Exp/Cntr=0.3,0.1

Type RM Length L Ch R = 1 ,111697  ,118,381,189
BEGIN DESCRIPTION:
This cross section corresponds to cross section 111679 of the non-georeferenced CDC model which was the source of this model.
END DESCRIPTION:
XS GIS Cut Line= 6
     2398438.216     6979837.937     2398429.536     6975250.264
     2398328.751     6974137.508     2398326.893     6973214.789
     2398174.252     6972585.482      2397691.47     6971969.229
#Sta/Elev= 30
    1050     484    4950   470.7    5047   462.8    6210   469.1    6378   467.5
    6434   463.5    6485   464.9    6543   462.5    6960   465.9    7409   462.5
    7819   466.9    7920   466.7    7942   463.9    7972   442.1    7995     432
    8045     429    8050   431.5    8054   442.1    8109   464.3    8143   462.2
    8275     466    8628   465.2    8657   469.2    8701   464.4    9026   466.7
    9038   468.3    9040   472.9    9053   478.4    9056   483.2    9090   492.7
#Mann= 3 ,0,0
    1050     .08       0    7942     .05       0    8109      .1       0
#XS Ineff= 1 ,-1
    1050    4950     490
Permanent Ineff=
       F
Bank Sta=7942,8109
XS Rating Curve= 0 ,0
Exp/Cntr=0.3,0.1

Type RM Length L Ch R = 1 ,111315  ,6,6,6
BEGIN DESCRIPTION:
This cross section corresponds to cross section 111255 of the non-georeferenced CDC model which was the source of this model.
END DESCRIPTION:
XS GIS Cut Line= 5
     2398630.233      6979908.03     2398629.332     6973733.511
     2398633.939     6972634.264      2398394.66     6972660.029
     2397863.089     6972175.199
#Sta/Elev= 30
 1380.36     484 4895.36  470.08 5004.44  465.06 5465.21  467.04 5509.63  465.08
 6294.85  466.44 6332.56  464.16 6345.13  466.02 6501.21  465.86 6686.76  462.68
  7155.7  465.19    8000     463    8369     463    8390     465    8640   465.9
    8670     464    8678   461.5    8703   460.9    8718   449.7    8768   428.7
    8801   428.7    8835   437.3    8858   448.3    8869   456.3    8913     460
    8980     464    9180     464    9480     470    9510     480    9580     490
#Mann= 9 ,-1,0
 1380.36     .08       0 4895.36     .08       0 5509.63    .069       0
 6294.85    .063       0 6345.13    .072       0    8000     .08       0
    8390     .08       0    8678     .05       0    8913      .1       0
#XS Ineff= 1 ,-1
 1380.36 4895.36     490
Permanent Ineff=
       F
Bank Sta=8678,8913
XS Rating Curve= 0 ,0
Exp/Cntr=0.3,0.1

Type RM Length L Ch R = 1 ,111310  ,14,14,14
BEGIN DESCRIPTION:
This cross section corresponds to cross section 111250 of the non-georeferenced CDC model which was the source of this model.
END DESCRIPTION:
XS GIS Cut Line= 5
     2398634.507     6979908.253     2398633.369     6973729.605
     2398637.975     6972630.358     2398397.013     6972653.605
     2397867.326     6972166.018
#Sta/Elev= 30
 1380.36     484 4895.36  470.08 5004.44  465.06 5465.21  467.04 5509.63  465.08
 6294.85  466.44 6332.56  464.16 6345.13  466.02 6686.76  462.68  7155.7  465.19
    8000     463    8369     463    8390     465    8640   465.9    8670     464
    8678   461.5    8703   460.9    8718   449.7    8748   435.8    8768   428.7
    8801   428.7    8835   437.3    8858   448.3    8869   456.3    8913     460
    8980     464    9180     464    9480     470    9510     480    9580     490
#Mann= 11 ,-1,0
 1380.36     .08       0 4895.36     .08       0 5509.63    .069       0
 6294.85    .063       0 6345.13    .072       0    8000     .08       0
    8390     .08       0    8678     .03       0    8748     .05       0
    8835     .03       0    8913      .1       0
#XS Ineff= 1 ,-1
 1380.36 4895.36     490
Permanent Ineff=
       F
Bank Sta=8678,8913
XS Rating Curve= 0 ,0
Exp/Cntr=0.3,0.1

Type RM Length L Ch R = 3 ,111302  ,,,
BEGIN DESCRIPTION:
River Legacy Parks Pedestrian Bridge
END DESCRIPTION:
Node Name=River Legacy Par
Bridge Culvert--1,0,-1,-1, 0
Deck Dist Width WeirC Skew NumUp NumDn MinLoCord MaxHiCord MaxSubmerge Is_Ogee
0.5,12,2.6,0, 16, 16, , , 0.95, 0, 0,0,,
    8640    8678  8678.1    8703    8712    8718    8735    8748    8768    8801
    8835    8854    8869    8913    8913    8980
     464   464.6     468     469   467.8  467.75   469.5     473   474.4   474.5
   470.8   466.9   466.9   466.5     463     464
     464   461.6   461.6   461.5   461.4   461.4  461.25  461.15   461.1   460.8
   460.7   460.5   460.4   460.1   460.1     464
    8640    8678  8678.1    8703    8712    8718    8735    8748    8768    8801
    8835    8854    8869    8913    8913    8980
     464   464.6     468     469   467.8  467.75   469.5     473   474.4   474.5
   470.8   466.9   466.9   466.5     463     464
     464   461.6   461.6   461.5   461.4   461.4  461.25  461.15   461.1   460.8
   460.7   460.5   460.4   460.1   460.1     464
Pier Skew, UpSta & Num, DnSta & Num=  ,8718, 2 ,8718, 2 , 0 , 0 , 0 ,,
       5       5
     454   461.4
       5       5
     454   461.4
Pier Skew, UpSta & Num, DnSta & Num=  ,8858, 2 ,8858, 2 , 0 , 0 , 0 ,,
       5       5
   448.3   463.4
       5       5
   448.3   463.4
BR Coef=-1 , 0 , 0 ,, 0 ,,,0.8,-1,,0,
WSPro=,,,, 1 ,,,, 0 ,,,, 0 ,,,,-1 ,-1 ,-1 , 0 , 0 , 0 , 0 , 0
BC Design=,, 0 ,, 0 ,,,,,,
BC Use User HTab Curves=0
BC User HTab FreeFlow(D)= 0

Type RM Length L Ch R = 1 ,111296  ,11,11,11
BEGIN DESCRIPTION:
This cross section corresponds to cross section 111210 of the non-georeferenced CDC model which was the source of this model.
END DESCRIPTION:
XS GIS Cut Line= 5
     2398643.801     6979883.872     2398636.207     6973725.329
     2398640.156     6972620.358     2398401.527     6972639.716
     2397886.857     6972152.997
#Sta/Elev= 30
 1380.36     484 4895.36  470.08 5004.44  465.06 5465.21  467.04 5509.63  465.08
 6294.85  466.44 6332.56  464.16 6345.13  466.02 6686.76  462.68  7155.7  465.19
    8000     463    8369     463    8390     465    8640   465.9    8670     464
    8678   461.5    8703   460.9    8718   449.7    8748   435.8    8768   428.7
    8801   428.7    8835   437.3    8858   448.3    8869   456.3    8913     460
    8980     464    9180     464    9480     470    9510     480    9580     490
#Mann= 11 ,-1,0
 1380.36     .08       0 4895.36     .08       0 5509.63    .069       0
 6294.85    .063       0 6345.13    .072       0    8000     .08       0
    8390     .08       0    8678     .03       0    8748     .05       0
    8835     .03       0    8913      .1       0
#XS Ineff= 1 ,-1
 1380.36 4895.36     490
Permanent Ineff=
       F
Bank Sta=8678,8913
XS Rating Curve= 0 ,0
Exp/Cntr=0.3,0.1