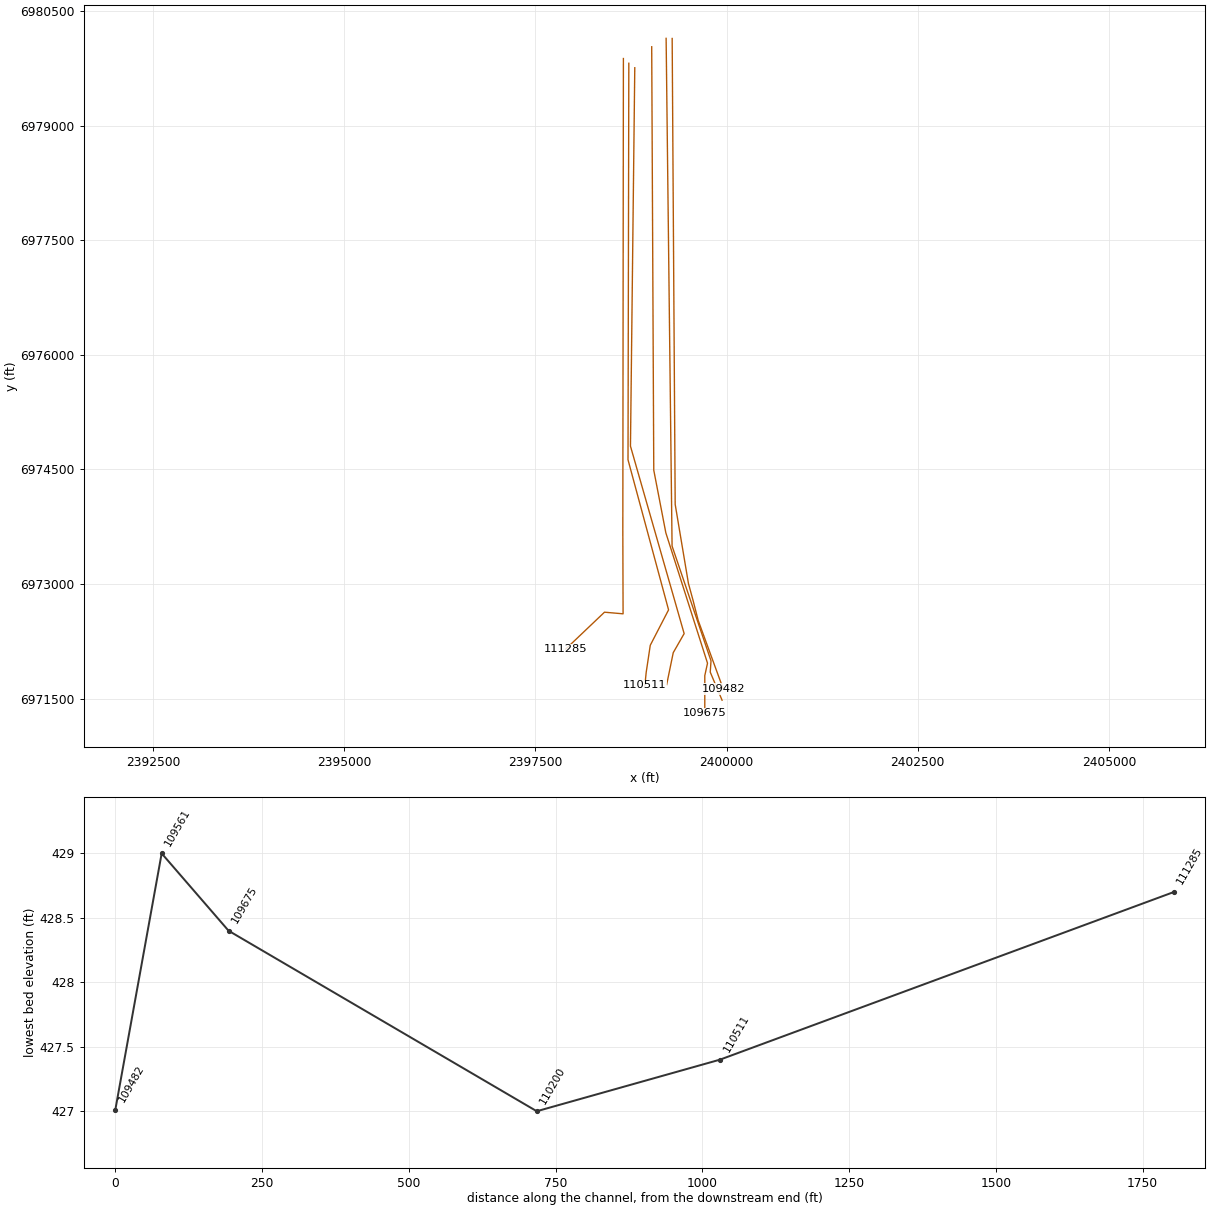
HEC-RAS study CDC_Consolidated_Model.prj: Upper Trinity CDC Consolidated Model

--- CDC_Consolidated_Model.g02 (geometry) --- (continued)

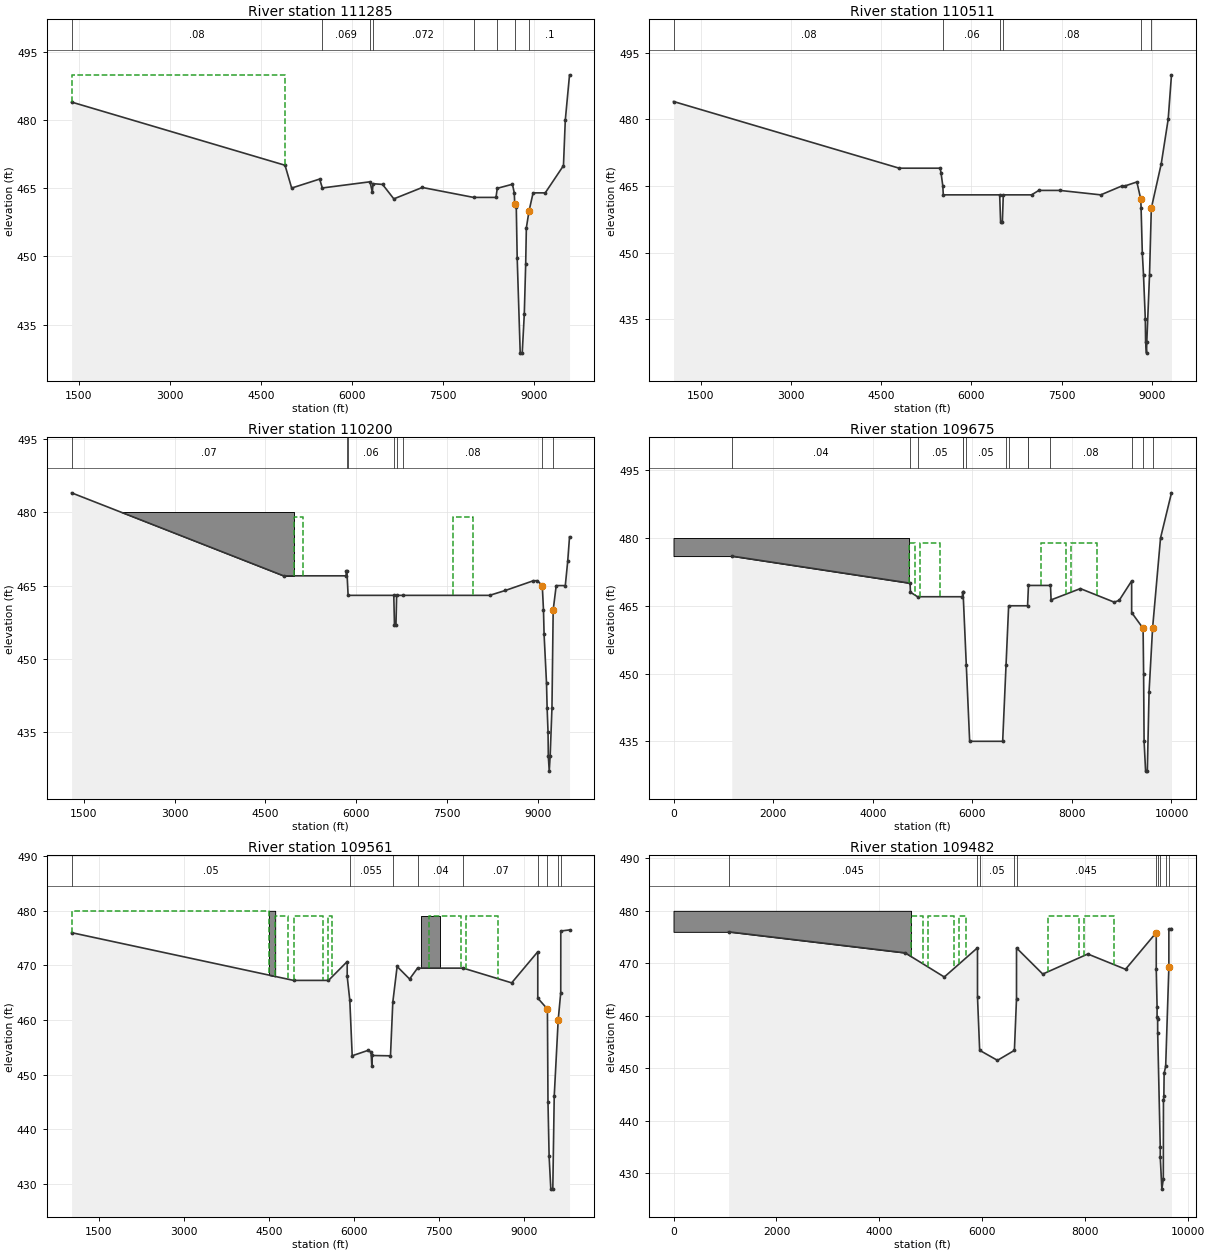
Type RM Length L Ch R = 1 ,111285  ,512,773,736
BEGIN DESCRIPTION:
This cross section corresponds to cross section 111205 of the non-georeferenced CDC model which was the source of this model.
END DESCRIPTION:
XS GIS Cut Line= 5
     2398650.654     6979878.201     2398643.082      6973699.94
     2398646.483     6972609.438      2398403.35     6972630.775
     2397895.972     6972147.789
#Sta/Elev= 30
 1380.36     484 4895.36  470.08 5004.44  465.06 5465.21  467.04 5509.63  465.08
 6294.85  466.44 6332.56  464.16 6345.13  466.02 6501.21  465.86 6686.76  462.68
  7155.7  465.19    8000     463    8369     463    8390     465    8640   465.9
    8670     464    8678   461.5    8703   460.9    8718   449.7    8768   428.7
    8801   428.7    8835   437.3    8858   448.3    8869   456.3    8913     460
    8980     464    9180     464    9480     470    9510     480    9580     490
#Mann= 8 ,-1,0
 1380.36     .08       0 5509.63    .069       0 6294.85    .063       0
 6345.13    .072       0    8000     .08       0    8390     .08       0
    8678     .05       0    8913      .1       0
#XS Ineff= 1 ,-1
 1380.36 4895.36     490
Permanent Ineff=
       F
Bank Sta=8678,8913
XS Rating Curve= 0 ,0
Exp/Cntr=0.3,0.1

Type RM Length L Ch R = 1 ,110511  ,102,312,306
BEGIN DESCRIPTION:
This cross section corresponds to cross section 110515 of the non-georeferenced CDC model which was the source of this model.
Old roadway embankment lowered to 463.  Far LOB of Section based on 2006 topography.
END DESCRIPTION:
XS GIS Cut Line= 6
2398721.547929446979816.53625506      2398710.94      6974626.13
 2399241.3734685 6972661.1961669 2399001.9766376 6972197.6829863
 2398948.6267588 6971842.0358703       2398931.7      6971674.89
#Sta/Elev= 30
    1050     484    4800     469    5480     469    5495     468    5525     465
    5533     463    6470     463    6485     457    6515     457    6530     463
    7000     463    7120     464    7470     464    8150     463    8500     465
    8550     465    8750   465.9    8815     462    8820     460    8840     450
    8860     445    8890     435    8895     430    8910   427.4    8915     430
    8960     445    8990     460    9155     470    9270     480    9325     490
#Mann= 6 ,-1,0
    1050     .08       0    5533     .06       0    6470    .055       0
    6530     .08       0    8815     .05       0    8990      .1       0
#Block Obstruct= 2 , 0
       0    4860                       0
Bank Sta=8815,8990
XS Rating Curve= 0 ,0
Exp/Cntr=0.5,0.3

Type RM Length L Ch R = 1 ,110200  ,286,525,510
BEGIN DESCRIPTION:
This cross section corresponds to cross section 110210 of the non-georeferenced CDC model which was the source of this model.
Proposed fill on LOB.  Old roadway embankment lowered to 463.  END RELIEF CHANNEL CUT  X-SECTION BASED ON 1991 SURVEY DATA
END DESCRIPTION:
XS GIS Cut Line= 6
2398799.416713486979757.82384049        2398743.      6974804.24
  2399292.334293  6972885.222883  2399445.115187 6972350.4894392
 2399302.4960497 6972100.9056208 2399216.6191972  6971683.232204
#Sta/Elev= 30
    1300     484    4800     467    5831     467    5835     468    5845     468
    5865     463    6619     463    6630     457    6655     457    6666     463
    6766     463    8200     463    8460     464    8925     466    8990     466
    9070     465    9090     460    9100     455    9140     445    9150     440
    9165     435    9170     430    9185     427    9200     430    9230     440
    9250     460    9300     465    9450     465    9490     470    9520     475
#Mann= 8 ,-1,0
    1300     .07       0    5845     .08       0    5865     .06       0
    6619    .055       0    6666     .06       0    6766     .08       0
    9070     .05       0    9250      .1       0
#XS Ineff= 2 ,-1
    4970    5115     479    7595    7930     479
Permanent Ineff=
       T       T
#Block Obstruct= 2 , 0
       0    4970     480               0
Bank Sta=9070,9250
XS Rating Curve= 0 ,0
Exp/Cntr=0.5,0.3

Type RM Length L Ch R = 1 ,109675  ,242,114,186
BEGIN DESCRIPTION:
This cross section corresponds to cross section 109695 of the non-georeferenced CDC model which was the source of this model.
Proposed fill & lake on LOB.  X-SECTION BASED ON 1991 SURVEY DATA
END DESCRIPTION:
XS GIS Cut Line= 6
2399020.781517296980032.40315107 2399047.8184094 6974489.7801082
 2399205.7186842 6973669.7187562 2399750.7284209 6971963.3799772
 2399715.0733085 6971800.3862087 2399715.0733085 6971306.3120657
#Sta/Elev= 30
    1170     476    4750     470    4758     468    4900     467    5801     467
    5805     468    5815     468    5879     452    5947     435    6610     435
    6678     452    6730     465    7110     465    7128   469.5    7570   469.5
    7582   466.3    8170   468.8    8850   465.8    8950   466.2    9200   470.5
    9200   463.5    9430     460    9440     450    9450     435    9480   428.4
    9515   428.4    9550     446    9620     460    9780     480   10000     490
#Mann= 14 ,-1,0
    1170     .04       0    4750     .07       0    4900     .05       0
    5805     .07       0    5815     .08       0    5879     .05       0
    6678     .08       0    6730     .05       0    7110     .07       0
    7128     .04       0    7570     .08       0    9200     .08       0
    9430     .05       0    9620      .1       0
#XS Ineff= 5 ,-1
    4730    4840     479    4940    5355     479    5800    6800     451
    7385    7890     479    7990    8495     479
Permanent Ineff=
       T       T       T       T       T
#Block Obstruct= 2 , 0
       0    4730     480               0
Bank Sta=9430,9620
XS Rating Curve= 0 ,0
Exp/Cntr=0.5,0.3

Type RM Length L Ch R = 1 ,109561  ,50,79,72
BEGIN DESCRIPTION:
This cross section corresponds to cross section 109585 of the non-georeferenced CDC model which was the source of this model.
35 FT U/S OF F.M. 157 ROADWAY EMBANKMENT
Bldg between relief br and main br
END DESCRIPTION:
XS GIS Cut Line= 6
2399209.392226516980142.60961722 2399253.3003154 6976392.8666821
 2399287.2152403 6973496.5380002 2399796.5701928 6971993.9412678
 2399786.3832052 6971846.2283087 2399941.2867988 6971478.7115445
#Sta/Elev= 30
    1020     476    4935  467.25    5550  467.25    5880   470.7    5880     468
    5926  463.58    5968  453.44    6251  454.44    6301  454.09    6314  451.53
    6322  453.49    6643  453.43    6684  463.25    6760   469.8    6980   467.5
    7120   469.5    7925   469.5    8780   466.8    9240   472.5    9240     464
    9410     462    9420     445    9440     435    9470     429    9505     429
    9530     446    9600     460    9645     465    9646   476.3    9800   476.5
#Mann= 9 ,-1,0
    1020     .05       0    5926    .055       0    6684     .05       0
    7120     .04       0    7925     .07       0    9240    .065       0
    9410    .055       0    9600    .065       0    9646     .07       0
#XS Ineff= 6 ,-1
    4610    4840     479    4940    5450     479    5550    5610     479
    7315    7880     479    7980    8540     479    1020    4500     480
Permanent Ineff=
       T       T       T       T       T       F
#Block Obstruct= 2 ,-1
    4500    4610     480    7185    7510     479
Bank Sta=9410,9600
XS Rating Curve= 0 ,0
Exp/Cntr=0.5,0.3

Type RM Length L Ch R = 1 ,109482  ,155,124,124
BEGIN DESCRIPTION:
This cross section corresponds to cross section 109530 of the non-georeferenced CDC model which was the source of this model.
U/S FACE OF F.M. 157 BRIDGE Surveyed 2006  Main channel n values in channel reflect conc. and gabions.   Relief channel n values in channel reflect conc. slopes.
END DESCRIPTION:
XS GIS Cut Line= 6
2399288.48546073 6980140.8274858 2399327.9638465 6974041.5477369
 2399501.1442744 6973007.5573508 2399562.2668556 6972783.4413292
 2399628.4832586 6972523.6701952 2399956.6672794 6971624.8928634
#Sta/Elev= 30
    1070     476    4500     472    5261   467.4    5906  472.96  5906.1  463.58
    5948  453.44    6294  451.53    6623  453.43 6663.87  463.25    6664  472.93
    7174  467.96    8049  471.78    8782  468.87    9379  475.85    9379  468.86
    9395  461.73    9395  459.71    9406  459.38    9407  456.74    9457  434.97
    9457  433.08    9488  427.01    9516  428.87    9519  443.91    9527  444.82
    9532  449.07    9562   450.4    9624  469.21    9624  476.52    9675  476.62
#Mann= 10 ,-1,0
    1070    .045       0    5906     .02       0    5948     .05       0
    6623     .02       0    6664    .045       0    9379     .02       0
    9407     .03       0    9457    .055       0    9562     .02       0
    9624    .045       0
#XS Ineff= 5 ,-1
    4615    4840     479    4940    5450     479    5550    5675     479
    7280    7870     479    7970    8565     479
Permanent Ineff=
       T       T       T       T       T
#Block Obstruct= 2 , 0
       0    4615     480               0
Bank Sta=9379,9624
XS Rating Curve= 0 ,0
Exp/Cntr=0.5,0.3