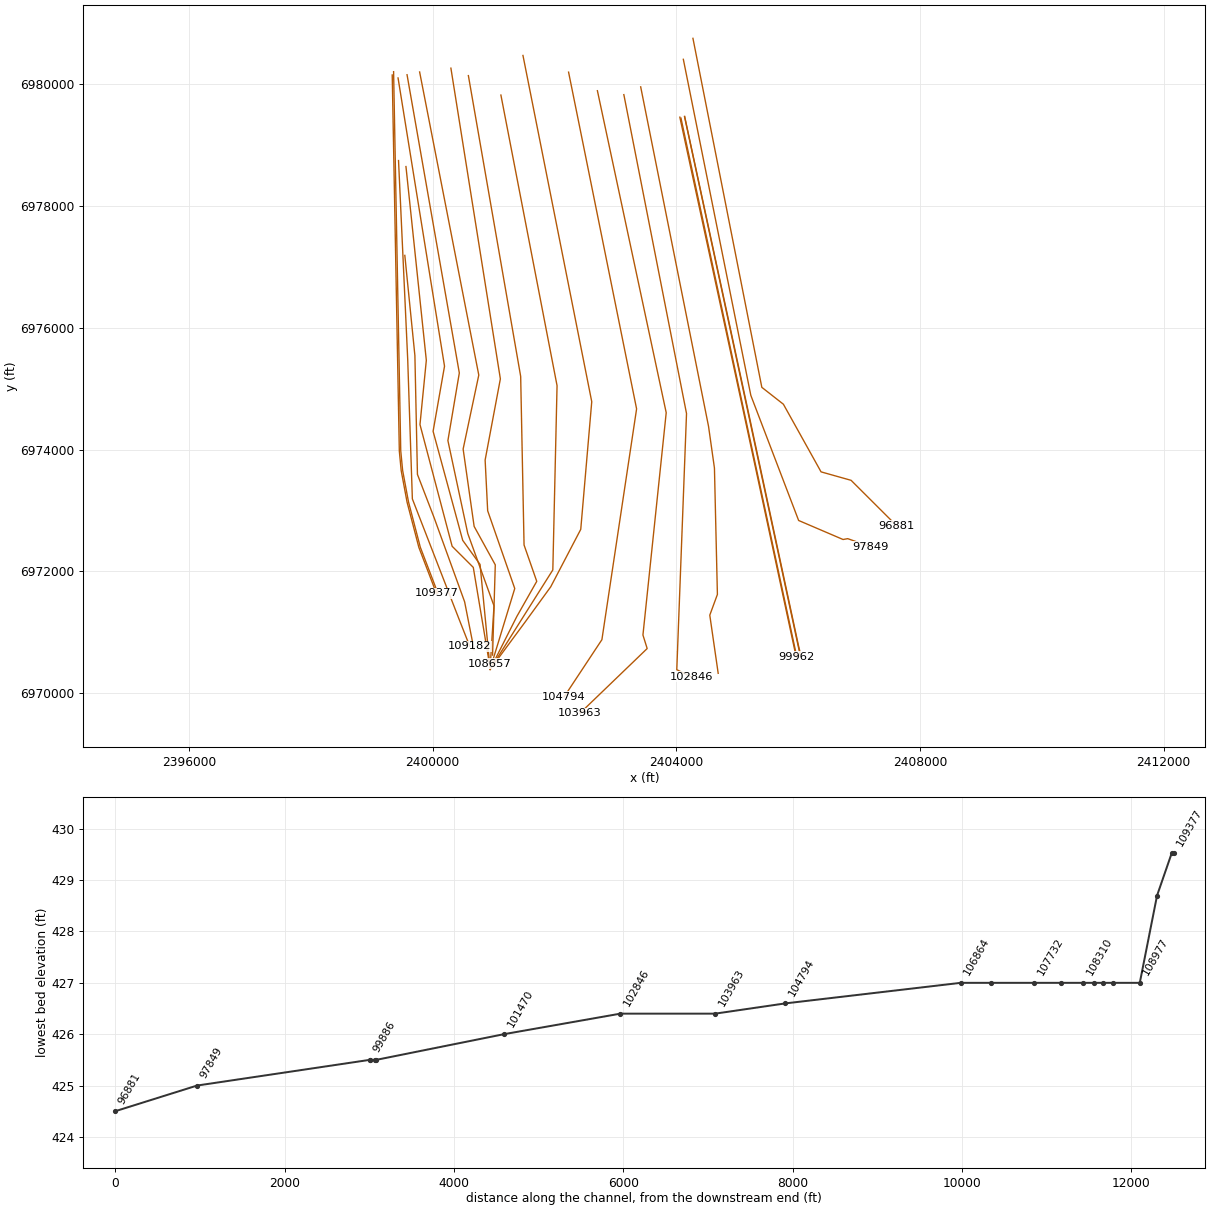
HEC-RAS study CDC_Consolidated_Model.prj: Upper Trinity CDC Consolidated Model

--- CDC_Consolidated_Model.g02 (geometry) --- (continued)

Type RM Length L Ch R = 4 ,109439  ,,,
BEGIN DESCRIPTION:
F.M. 157
NEW X-SECTION BASED ON 1991 SURVEY DATA AND COE BRIDGE SECTIONS
D/S FACE OF WIDENED AND REALIGNED F.M. 157 BRIDGE
END DESCRIPTION:
Node Name=FM 157
Bridge Culvert--1,0,-1,-1, 0
Deck Dist Width WeirC Skew NumUp NumDn MinLoCord MaxHiCord MaxSubmerge Is_Ogee
0.5,123,2.6,0, 31, 31, , , 0.95, 0, 0,0,,
    5886    5906    5986    6059    6122    6122    6194    6263    6339    6407
    6478    6545    6614 6663.87    6683    6683    7072    7123    7174    7224
    7394    7900    8141    8279    8782    8878    9358    9358    9379    9624
    9645
  474.63  474.63   475.6  476.35  476.88  477.54  477.96  478.12  478.11  477.85
  477.29  476.61  475.75  474.61  474.73   471.9  468.52  468.11  467.96  467.89
  468.47  470.63  471.81  470.87  468.87  469.21  475.85  477.13  477.15  477.63
  477.65
     465  465.87  466.84  467.59  468.12  468.12  468.54   468.7  468.69  468.43
  467.87  467.19  466.33  466.19  466.19     465     465     465     465     465
     465     465     465     465     465     465     465     465  469.15  469.63
     465
    5886    5906    5986    6059    6122    6122    6194    6263    6339    6407
    6478    6545    6614 6663.87    6683    6683    7072    7123    7174    7224
    7394    7900    8141    8279    8782    8878    9358    9358    9379    9624
    9645
  474.63  474.63   475.6  476.35  476.88  477.54  477.96  478.12  478.11  477.85
  477.29  476.61  475.75  474.61  474.73   471.9  468.52  468.11  467.96  467.89
  468.47  470.63  471.81  470.87  468.87  469.21  475.85  477.13  477.15  477.63
  477.65
     465  465.87  466.84  467.59  468.12  468.12  468.54   468.7  468.69  468.43
  467.87  467.19  466.33  466.19  466.19     465     465     465     465     465
     465     465     465     465     465     465     465     465  469.15  469.63
     465
Pier Skew, UpSta & Num, DnSta & Num=  ,6015.91, 2 ,6015.91, 2 , 0 , 0 , 0 ,,
    3.28    3.28
  419.95     468
    3.28    3.28
  419.95     468
Pier Skew, UpSta & Num, DnSta & Num=  ,6124.18, 2 ,6124.18, 2 , 0 , 0 , 0 ,,
    3.28    3.28
  419.95   469.8
    3.28    3.28
  419.95   469.8
Pier Skew, UpSta & Num, DnSta & Num=  ,6232.44, 2 ,6232.44, 2 , 0 , 0 , 0 ,,
    3.28    3.28
  413.39   469.8
    3.28    3.28
  413.39   469.8
Pier Skew, UpSta & Num, DnSta & Num=  ,6340.71, 2 ,6340.71, 2 , 0 , 0 , 0 ,,
    3.28    3.28
  413.39   469.8
    3.28    3.28
  413.39   469.8
Pier Skew, UpSta & Num, DnSta & Num=  ,6448.98, 2 ,6448.98, 2 , 0 , 0 , 0 ,,
    3.28    3.28
  413.39   469.8
    3.28    3.28
  413.39   469.8
Pier Skew, UpSta & Num, DnSta & Num=  ,6557.25, 2 ,6557.25, 2 , 0 , 0 , 0 ,,
    3.28    3.28
  413.39   469.8
    3.28    3.28
  413.39   469.8
Pier Skew, UpSta & Num, DnSta & Num=  ,9449, 2 ,9449, 2 , 0 , 0 , 0 ,,
       3       3
     445   469.8
       3       3
     445   469.8
Pier Skew, UpSta & Num, DnSta & Num=  ,9555, 2 ,9555, 2 , 0 , 0 , 0 ,,
       3       3
     450   469.8
       3       3
     450   469.8
BR Coef= 0 , 0 , 1 ,1.05, 0 ,,,0.8,0,1.2,2,468.7
WSPro=,,,, 1 ,,,, 0 ,,,, 0 ,,,,-1 ,-1 ,-1 , 0 , 0 , 0 , 0 , 0
BR Coef= 0 , 0 , 1 ,1.05, 0 ,,,0.8006408,0,1.2,2,469.63
WSPro=,,,, 1 ,,,, 0 ,,,, 0 ,,,,-1 ,-1 ,-1 , 0 , 0 , 0 , 0 , 0
BC Mult= 3 ,1070,8141,1070,8141
BC Mult= 3 ,8141,9675,8141,9675
BC Design=,, 0 ,, 0 ,,,,,,
BC HTab HWMax=476.5
BC Use User HTab Curves=0
BC User HTab FreeFlow(D)= 0

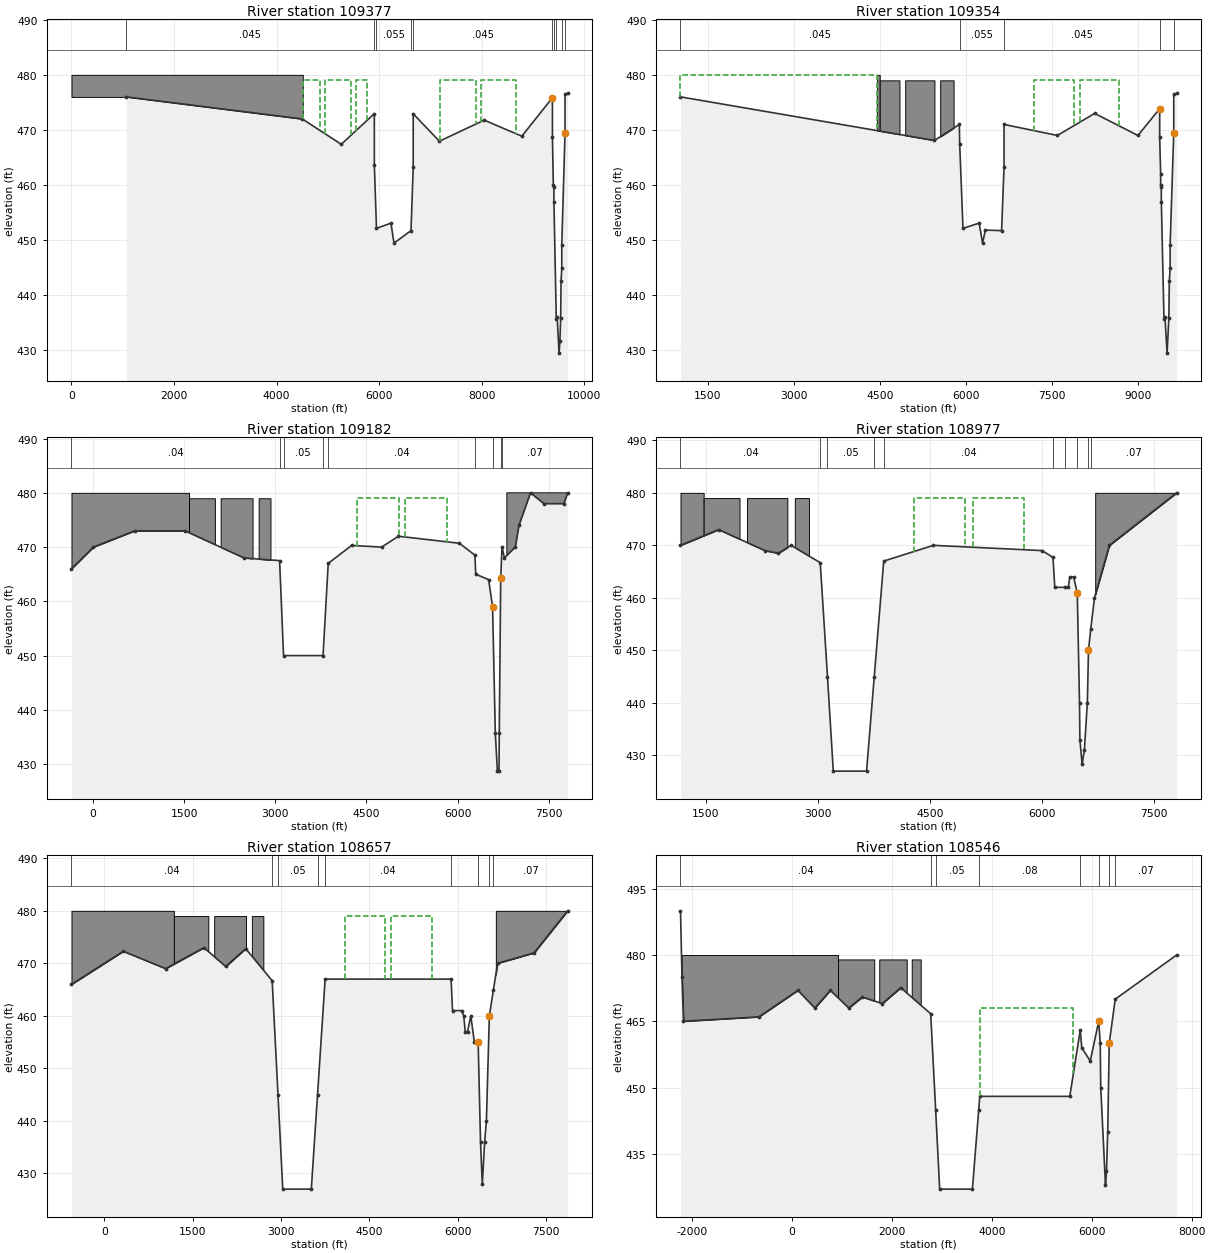
Type RM Length L Ch R = 1 ,109377  ,24,24,24
BEGIN DESCRIPTION:
This cross section corresponds to cross section 109405 of the non-georeferenced CDC model which was the source of this model.
D/S FACE OF F.M. 157 BRIDGE Surveyed 2006  Main channel n values in channel reflect conc. and gabions.  Relief channel n values in channel reflect conc. slopes.
END DESCRIPTION:
XS GIS Cut Line= 6
2399338.723732596980154.00726031 2399455.3025026  6973975.331662
 2399485.8637932 6973654.4382749 2399582.6411587 6973134.8960069
 2399776.1958897 6972391.2380454 2400063.8544932 6971638.3539461
#Sta/Elev= 30
    1070     476    4500     472    5261   467.4    5906  472.96  5906.1  463.58
    5948  452.15    6230   453.1    6289  449.47    6621  451.74 6663.87  463.25
    6664  472.93    7174  467.96    8049  471.78    8782  468.87    9379  475.85
    9379   468.7    9396  459.95    9407  459.62    9408  456.91    9454  435.71
    9471  436.09    9508  429.52    9525  431.77    9539  435.87    9547  442.58
    9561  444.91    9561  449.11    9624  469.38    9624  476.52    9675  476.62
#Mann= 10 ,-1,0
    1070    .045       0    5906     .02       0    5948    .055       0
    6621     .02       0    6664    .045       0    9379     .02       0
    9408     .03       0    9454    .055       0    9561     .02       0
    9624    .045       0
#XS Ineff= 5 ,-1
    4510    4840     479    4940    5450     479    5550    5765     479
    7195    7885     479    7985    8675     479
Permanent Ineff=
       T       T       T       T       T
#Block Obstruct= 2 , 0
       0    4510     480               0
Bank Sta=9379,9624
XS Rating Curve= 0 ,0
Exp/Cntr=0.5,0.3

Type RM Length L Ch R = 1 ,109354  ,109,172,172
BEGIN DESCRIPTION:
This cross section corresponds to cross section 109385 of the non-georeferenced CDC model which was the source of this model.
20 FT D/S OF F.M. 157 ROADWAY EMBANKMENT  Flow limit 4495  X-SECTION BASED ON 1991 SURVEY DATA
END DESCRIPTION:
XS GIS Cut Line= 6
 2399361.27148956980208.07590398 2399478.7934841 6973979.4092031
 2399509.3547747 6973658.5158161 2399606.1321402  6973138.973548
 2399799.6868712 6972395.3155865 2400087.3454747 6971642.4314873
#Sta/Elev= 30
    1020     476    5450   468.1    5884     471    5890   467.5    5948  452.15
    6230   453.1    6289  449.47    6339  451.84    6621  451.74    6664  463.25
    6664     471    7594     469    8245     473    9000     469    9379  473.85
    9379   468.7    9396  461.96    9396  459.95    9407  459.62    9408  456.91
    9454  435.71    9471  436.09    9508  429.52    9539  435.87    9547  442.58
    9561  444.91    9561  449.11    9624  469.38    9624  476.52    9675  476.62
#Mann= 5 ,-1,0
    1020    .045       0    5890    .055       0    6664    .045       0
    9379    .055       0    9624     .12       0
#XS Ineff= 3 ,-1
    7195    7885     479    7985    8675     479    1020    4450     480
Permanent Ineff=
       T       T       F
#Block Obstruct= 4 ,-1
    4450    4495     480    4495    4840     479    4940    5450     479
    5550    5784     479
Bank Sta=9379,9624
XS Rating Curve= 0 ,0
Exp/Cntr=0.5,0.3

Type RM Length L Ch R = 1 ,109182  ,119,204,200
BEGIN DESCRIPTION:
This cross section corresponds to cross section 109220 of the non-georeferenced CDC model which was the source of this model.
Proposed fill on LOB.  Flow limit 1580  LOB from 2001 aerial topo.
ROB of X-SECTION BASED ON 1991 AND 2001 SURVEY DATA
END DESCRIPTION:
XS GIS Cut Line= 6
2399442.385553776978747.88510128      2399455.53      6978462.66
     2399592.973     6975480.245     2399669.362     6973188.578
     2400426.307     6971237.189      2400612.34      6970764.59
#Sta/Elev= 30
    -355     466       5     470     685     473    1515     473    2485     468
    3070   467.5    3135     450    3785     450    3870     467    4255   470.3
    4750     470    5025     472    6030   470.7    6285   468.5    6297     465
    6510     464    6575     459    6620   435.7    6654   428.7    6681   428.8
    6685   435.7    6709   464.3    6730     470    6770     468    6950     470
    7010     474    7200     480    7420     478    7750     478    7810     480
#Mann= 9 ,-1,0
    -355     .04       0    3070     .08       0    3135     .05       0
    3785     .08       0    3870     .04       0    6285    .065       0
    6575    .055       0    6709     .12       0    6730     .07       0
#XS Ineff= 2 ,-1
    4340    5030     479    5130    5820     479
Permanent Ineff=
       T       T
#Block Obstruct= 5 ,-1
    -355    1580     480    1580    2005     479    2100    2625     479
    2725    2920     479    6810    8000     480
Bank Sta=6575,6709
XS Rating Curve= 0 ,0
Exp/Cntr=0.5,0.3

Type RM Length L Ch R = 1 ,108977  ,125,321,306
BEGIN DESCRIPTION:
This cross section corresponds to cross section 109005 of the non-georeferenced CDC model which was the source of this model.
Proposed fill & lake on LOB.  Flow limit 1470  LOB from 2001 aerial topo.  ROB of X-SECTION BASED ON 1991 AND 2001 SURVEY DATA
END DESCRIPTION:
XS GIS Cut Line= 6
2399545.623881226977189.59776567     2399711.029     6975542.745
     2399752.696     6973591.356     2400027.484     6972877.343
     2400527.214     6971498.087       2400681.6      6970712.14
#Sta/Elev= 30
    1160     470    1670     473    2290     469    2470   468.5    2640     470
    3030   466.7    3127     445    3205     427    3650     427    3753     445
    3880     467    4545     470    6000     469    6145   467.7    6169     462
    6300     462    6350     462    6370     464    6420     464    6470     461
    6500     440    6505     433    6535   428.3    6565     431    6605     440
    6620     450    6650     454    6700     460    6900     470    7800     480
#Mann= 10 ,-1,0
    1160     .04       0    3030     .08       0    3127     .05       0
    3753     .08       0    3880     .04       0    6145     .07       0
    6300    .065       0    6470    .055       0    6620     .12       0
    6650     .07       0
#XS Ineff= 3 ,-1
    3000    3800     444    4280    4970     479    5070    5760     479
Permanent Ineff=
       T       T       T
#Block Obstruct= 5 ,-1
    1160    1470     480    1470    1950     479    2050    2590     479
    2690    2880     479    6710    8000     480
Bank Sta=6470,6620
XS Rating Curve= 0 ,0
Exp/Cntr=0.5,0.3

Type RM Length L Ch R = 1 ,108657  ,251,111,101
BEGIN DESCRIPTION:
This cross section corresponds to cross section 108685 of the non-georeferenced CDC model which was the source of this model.
Proposed fill & lake on LOB.  Flow limit 1180  LOB from 2001 aerial topo.  ROB of X-SECTION BASED ON 1991 AND 2001 SURVEY DATA
END DESCRIPTION:
XS GIS Cut Line= 6
      2399564.31      6978649.21     2399898.529     6975466.356
     2399794.362       6974410.8      2400322.14       6972410.8
     2400669.362     6972063.5782400934.385038086970481.20704212
#Sta/Elev= 30
    -560     466     320   472.3    1040     469    1690     473    2060   469.4
    2400   472.8    2850   466.7    2949     445    3030     427    3515     427
    3621     445    3750     467    5890     467    5914     461    6070     461
    6105     460    6130     457    6170     457    6225     460    6285     455
    6350     455    6390     436    6420   427.9    6460     436    6490     440
    6540     460    6610     465    6680     470    7300     472    7870     480
#Mann= 9 ,-1,0
    -560     .04       0    2850     .08       0    2949     .05       0
    3621     .08       0    3750     .04       0    5890     .09       0
    6350    .055       0    6540     .12       0    6610     .07       0
#XS Ineff= 3 ,-1
    2800    3800     444    4080    4770     479    4870    5560     479
Permanent Ineff=
       T       T       T
#Block Obstruct= 5 ,-1
    -560    1180     480    1180    1765     479    1865    2405     479
    2505    2700     479    6650    8000     480
Bank Sta=6350,6540
XS Rating Curve= 0 ,0
Exp/Cntr=0.5,0.3

Type RM Length L Ch R = 1 ,108546  ,284,108,103
BEGIN DESCRIPTION:
This cross section corresponds to cross section 108570 of the non-georeferenced CDC model which was the source of this model.
Proposed fill & lake on LOB.  Flow limit 920  LOB from 2001 aerial topo.  ROB of X-SECTION BASED ON 1991 AND 2001 SURVEY DATA
END DESCRIPTION:
XS GIS Cut Line= 6
      2399434.49      6980104.83      2400197.14     6975369.134
      2400009.64     6974299.689     2400495.751     6972508.023
     2400780.473     6972112.1892400943.305692966970421.89295229
#Sta/Elev= 30
   -2235     490   -2205     475   -2175     465    -665     466     115     472
     455     468     765     472    1135     468    1405   470.5    1805     469
    2175   472.6    2775   466.7    2874     445    2955     427    3610     427
    3737     445    3758     448    5560     448    5770     463    5800     459
    5970     456    6140     465    6170     460    6180     450    6275   427.9
    6295     431    6320     440    6350     460    6470     470    7700     480
#Mann= 8 ,-1,0
   -2235     .04       0    2775     .08       0    2874     .05       0
    3737     .08       0    5770     .12       0    6140    .055       0
    6350     .12       0    6470     .07       0
#XS Ineff= 2 ,-1
    3758    5634     468    2800    3758     444
Permanent Ineff=
       T       T
#Block Obstruct= 4 ,-1
   -2235     920     480     920    1645     479    1745    2295     479
    2395    2575     479
Bank Sta=6140,6350
XS Rating Curve= 0 ,0
Exp/Cntr=0.5,0.3

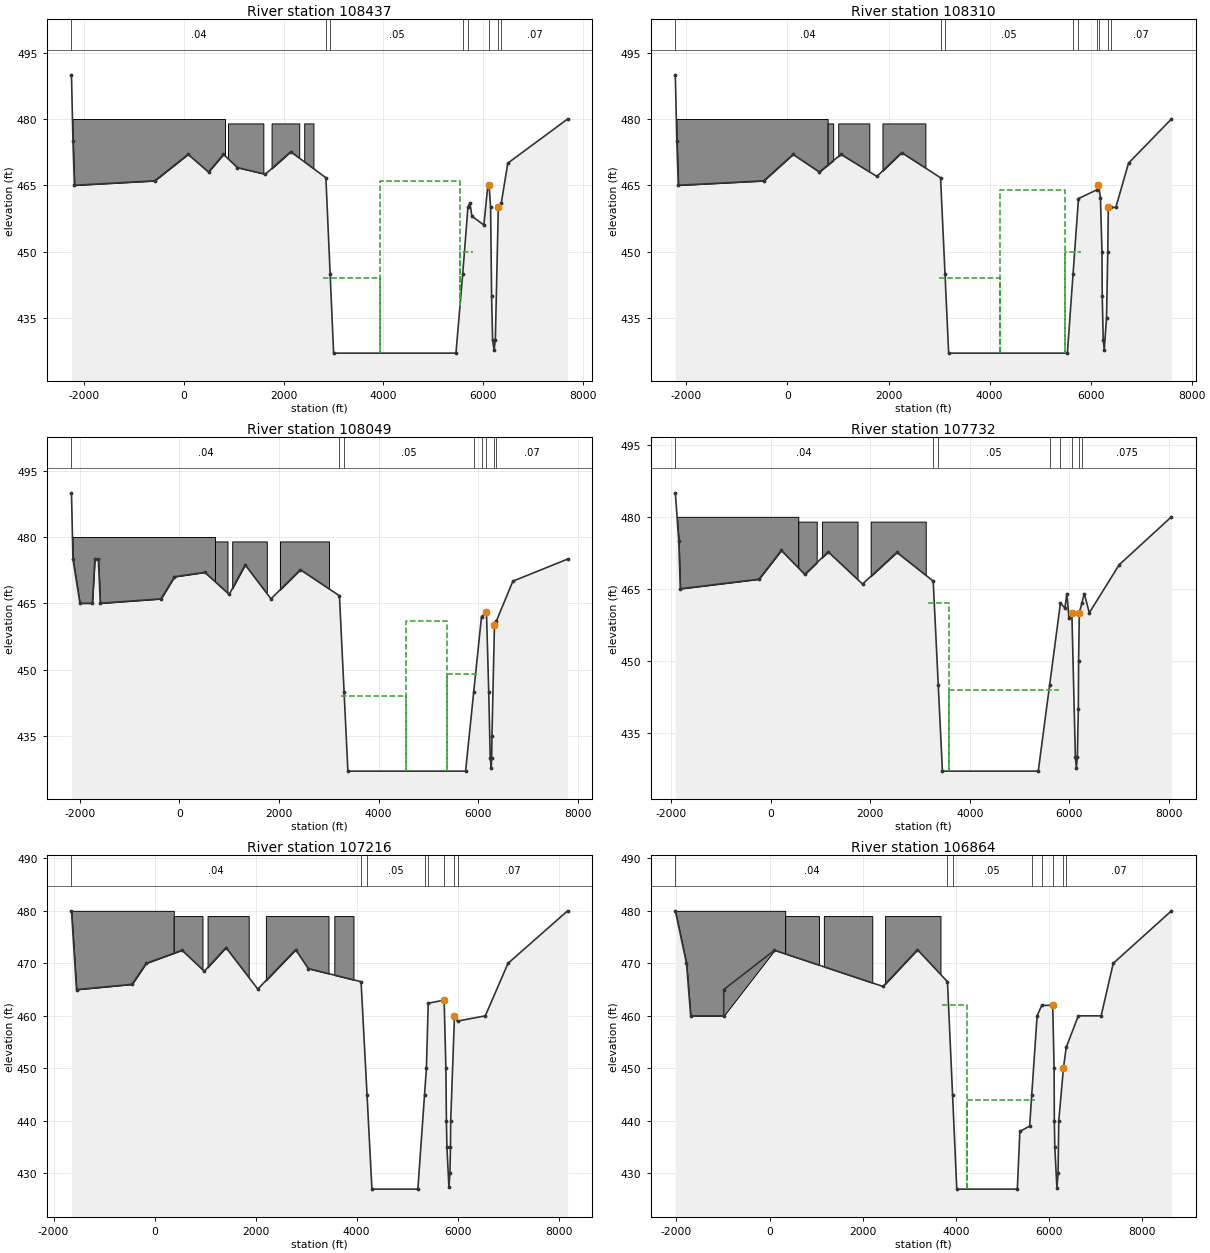
Type RM Length L Ch R = 1 ,108437  ,289,127,113
BEGIN DESCRIPTION:
This cross section corresponds to cross section 108465 of the non-georeferenced CDC model which was the source of this model.
Proposed fill & lake on LOB.  Flow limit 825  LOB from 2001 aerial topo.  ROB of X-SECTION BASED ON 1991 AND 2001 SURVEY DATA
END DESCRIPTION:
XS GIS Cut Line= 6
      2399582.02      6980157.94     2400440.196     6975258.023
     2400252.696     6974146.911     2400579.085     6972619.134
      2401009.64     6971431.6342400947.277455846970435.18187862
#Sta/Elev= 30
   -2255     490   -2225     475   -2195     465    -585     466      85     472
     495     468     795     472    1075     469    1635   467.5    2145   472.6
    2850   466.7    2935     445    3005     427    5460     427    5596     445
    5700     460    5740     461    5780     458    6020     456    6100     465
    6125     465    6155     460    6175     440    6195     430    6225   427.8
    6250     430    6310     460    6370     461    6500     470    7700     480
#Mann= 8 ,-1,0
   -2255     .04       0    2850     .08       0    2935     .05       0
    5596     .08       0    5700     .12       0    6125    .055       0
    6310     .12       0    6370     .07       0
#XS Ineff= 3 ,-1
    3938    5541     466    5541    5800     450    2800    3938     444
Permanent Ineff=
       T       T       T
#Block Obstruct= 4 ,-1
   -2255     825     480     885    1595     479    1760    2315     479
    2415    2600     479
Bank Sta=6125,6310
XS Rating Curve= 0 ,0
Exp/Cntr=0.5,0.3

Type RM Length L Ch R = 1 ,108310  ,389,261,256
BEGIN DESCRIPTION:
This cross section corresponds to cross section 108335 of the non-georeferenced CDC model which was the source of this model.
Proposed fill & lake on LOB.  Flow limit 795  LOB from 2001 aerial topo.  ROB of X-SECTION BASED ON 1991 AND 2001 SURVEY DATA
END DESCRIPTION:
XS GIS Cut Line= 6
      2399788.56      6980203.18      2400759.64       6975223.3
     2400502.696     6974008.023     2400683.251     6972737.189
     2401030.473     6972105.2452400985.958658726970623.15565817
#Sta/Elev= 30
   -2220     490   -2190     475   -2160     465    -470     466     110     472
     630     468    1060     472    1770     467    2260   472.4    3030   466.7
    3118     445    3190     427    5540     427    5653     445    5760     462
    6130     464    6145     465    6160     465    6195   462.1    6225     450
    6230     440    6250     430    6270   427.8    6315     435    6340     450
    6350     460    6400     460    6500     460    6750     470    7600     480
#Mann= 9 ,-1,0
   -2220     .04       0    3030     .08       0    3118     .05       0
    5653     .08       0    5760    .085       0    6130     .12       0
    6160    .055       0    6350     .12       0    6400     .07       0
#XS Ineff= 3 ,-1
    4211    5497     464    5497    5800     450    3000    4211     444
Permanent Ineff=
       T       T       T
#Block Obstruct= 4 ,-1
   -2220     795     480     795     905     479    1005    1620     479
    1880    2730     479
Bank Sta=6145,6350
XS Rating Curve= 0 ,0
Exp/Cntr=0.5,0.3

Type RM Length L Ch R = 1 ,108049  ,573,318,365
BEGIN DESCRIPTION:
This cross section corresponds to cross section 108080 of the non-georeferenced CDC model which was the source of this model.
Proposed fill & lake on LOB.  Flow limit 715  LOB from 2001 aerial topo.  ROB of X-SECTION BASED ON 1991 AND 2001 SURVEY DATA
END DESCRIPTION:
XS GIS Cut Line= 6
      2400301.96      6980266.13     2401113.807       6975160.8
     2400863.807     6973827.467     2400905.473     6972994.134
     2401349.918     6971716.3562400988.144760936970530.56493095
#Sta/Elev= 30
   -2170     490   -2140     475   -2000     465   -1750     465   -1700     475
   -1630     475   -1590     465    -370     466    -100     471     510     472
    1000     467    1320   473.7    1840     466    2430   472.6    3215   466.7
    3308     445    3385     427    5750     427    5914     445    6070     462
    6170     463    6215     445    6245     430    6265   427.7    6275     430
    6280     435    6330     460    6370     461    6700     470    7800     475
#Mann= 8 ,-1,0
   -2170     .04       0    3215     .08       0    3308     .05       0
    5914     .08       0    6070     .12       0    6170    .055       0
    6330     .12       0    6370     .07       0
#XS Ineff= 3 ,-1
    4544    5384     461    5384    6000     449    3240    4544     444
Permanent Ineff=
       T       T       T
#Block Obstruct= 4 ,-1
   -2170     715     480     715     965     479    1060    1755     479
    2020    3005     479
Bank Sta=6170,6330
XS Rating Curve= 0 ,0
Exp/Cntr=0.3,0.1

Type RM Length L Ch R = 1 ,107732  ,521,516,123
BEGIN DESCRIPTION:
This cross section corresponds to cross section 107775 of the non-georeferenced CDC model which was the source of this model.
Proposed fill & lake on LOB.  Flow limit 555  LOB from 2001 aerial topo.  ROB of X-SECTION BASED ON 1991 AND 2001 SURVEY DATA
END DESCRIPTION:
XS GIS Cut Line= 6
2400588.902539156980143.42952312      2401447.14     6975202.467
     2401502.696     6972431.634     2401711.029     6971834.411
      2401384.64     6971258.023      2400986.35       6970469.1
#Sta/Elev= 30
   -1915     485   -1845     475   -1815     465    -235     467     215     473
     685     468    1155   472.7    1845     466    2535   472.6    3265   466.6
    3366     445    3450     427    5375     427    5604     445    5820     462
    5910     461    5950     464    5990     459    6050     460    6120     430
    6140   427.6    6160     430    6180     440    6185     450    6200     460
    6250     462    6300     464    6400     460    7000     470    8050     480
#Mann= 8 ,-1,0
   -1915     .04       0    3265     .08       0    3366     .05       0
    5604     .08       0    5820     .12       0    6050    .055       0
    6200     .12       0    6250    .075       0
#XS Ineff= 2 ,-1
    3170    3580     462    3580    5800     444
Permanent Ineff=
       T       T
#Block Obstruct= 4 ,-1
   -1915     555     480     555     925     479    1030    1745     479
    2010    3115     479
Bank Sta=6050,6200
XS Rating Curve= 0 ,0
Exp/Cntr=0.3,0.1

Type RM Length L Ch R = 1 ,107216  ,489,352,110
BEGIN DESCRIPTION:
This cross section corresponds to cross section 107250 of the non-georeferenced CDC model which was the source of this model.
Proposed fill & lake on LOB.  Flow limit 380  LOB from 2001 aerial topo.  ROB OF X-SECTION BASED ON 1991 AND 2001 SURVEY DATA
END DESCRIPTION:
XS GIS Cut Line= 6
 2401122.66788056979823.86187385     2401426.307     6978251.078
     2402044.362     6975049.689     2401974.918     6972021.911
     2401454.085     6971195.523      2400944.16      6970385.37
#Sta/Elev= 30
   -1645     480   -1545     465    -445     466    -165     470     545   472.5
     985   468.5    1415     473    2045   465.1    2795   472.6    3045     469
    4090   466.5    4208     445    4305     427    5215     427    5347     445
    5384     450    5420   462.4    5735     463    5770     450    5780     440
    5790     435    5830   427.4    5850     430    5860     435    5865     440
    5940     460    6000     459    6550     460    7000     470    8180     480
#Mann= 8 ,-1,0
   -1645     .04       0    4090     .08       0    4208     .05       0
    5347     .08       0    5420     .12       0    5735    .055       0
    5940     .15       0    6000     .07       0
#XS Ineff= 1 ,-1
    4000    5400     444
Permanent Ineff=
       T
#Block Obstruct= 5 ,-1
   -1645     380     480     380     950     479    1050    1865     479
    2205    3445     479    3560    3940     479
Bank Sta=5735,5940
XS Rating Curve= 0 ,0
Exp/Cntr=0.3,0.1

Type RM Length L Ch R = 1 ,106864  ,710,2070,1320
BEGIN DESCRIPTION:
This cross section corresponds to cross section 106865 of the non-georeferenced CDC model which was the source of this model.
Proposed fill & lake on LOB.  Flow limit 335  LOB from 2001 aerial topo. ROB OF X-SECTION BASED ON 1991 AND 2001 SURVEY DATA
END DESCRIPTION:
XS GIS Cut Line= 6
 2401484.79100596980474.72401056     2402613.807       6974785.8
     2402433.251     6972688.578     2401940.196     6971744.134
     2401516.585       6971160.8      2400944.16      6970385.37
#Sta/Elev= 30
   -2025     480   -1785     470   -1695     460    -985     460    -985     465
     105   472.5    2435   465.6    3175   472.6    3820   466.5    3929     445
    4020     427    5320     427    5375     438    5585     439    5630     445
    5745     460    5845     462    6080     462    6110     450    6115     440
    6125     435    6170   427.3    6195     430    6210     440    6310     450
    6370     454    6630     460    7120     460    7380     470    8630     480
#Mann= 8 ,-1,0
   -2025     .04       0    3820     .08       0    3929     .05       0
    5630     .08       0    5845     .12       0    6080    .055       0
    6310     .15       0    6370     .07       0
#XS Ineff= 2 ,-1
    3700    4250     462    4250    5700     444
Permanent Ineff=
       T       T
#Block Obstruct= 4 ,-1
   -2025     335     480     335    1060     479    1165    2205     479
    2480    3670     479
Bank Sta=6080,6310
XS Rating Curve= 0 ,0
Exp/Cntr=0.3,0.1

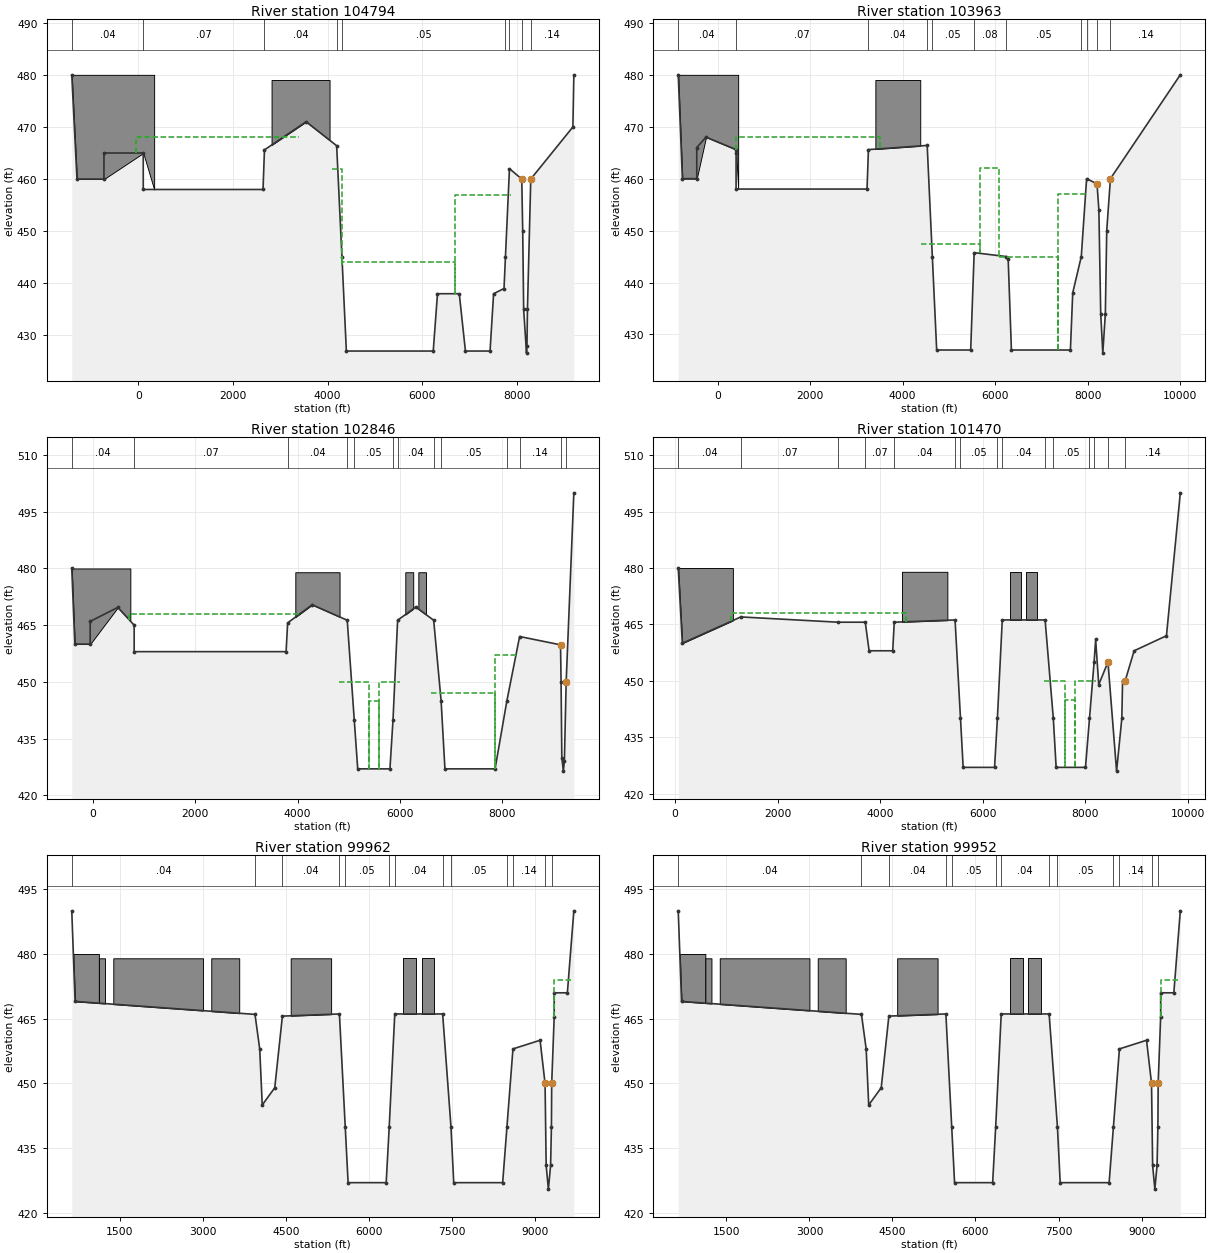
Type RM Length L Ch R = 1 ,104794  ,610,831,885
BEGIN DESCRIPTION:
This cross section corresponds to cross section 104780 of the non-georeferenced CDC model which was the source of this model.
Proposed fill & lake on LOB.  Flow limit 335  LOB from 2001 aerial topo. ROB OF X-SECTION BASED ON 1991 AND 2001 SURVEY DATA
END DESCRIPTION:
XS GIS Cut Line= 5
      2402233.48      6980200.51      2402509.64     6978834.411
     2403349.918     6974667.745     2402780.473     6970876.078
2402159.616075496969936.07634162
#Sta/Elev= 30
   -1405     480   -1295     460    -725     460    -725     465     105     465
     105     458    2635     458    2665   465.6    3545     471    4190   466.4
    4302     445    4395     427    6230     427    6320     438    6780     438
    6910     427    7430     427    7505     438    7725     439    7755     445
    7840     462    8100     460    8120     450    8140     435    8200   426.6
    8210     428    8220     435    8290     460    9180     470    9200     480
#Mann= 9 ,-1,0
   -1405     .04       0     105     .07       0    2665     .04       0
    4190     .08       0    4302     .05       0    7755     .08       0
    7840     .14       0    8100    .057       0    8290     .14       0
#XS Ineff= 4 ,-1
    4310    6700     444    6700    7870     457    4090    4310     462
     -50    3400     468
Permanent Ineff=
       T       T       T       T
#Block Obstruct= 2 ,-1
   -1405     335     480    2815    4040     479
Bank Sta=8100,8290
XS Rating Curve= 0 ,0
Exp/Cntr=0.3,0.1

Type RM Length L Ch R = 1 ,103963  ,443,1118,1027
BEGIN DESCRIPTION:
This cross section corresponds to cross section 107010 of the non-georeferenced CDC model which was the source of this model.
Proposed fill & lake on LOB.  Flow limit 445  LOB from 2001 aerial topo. ROB OF X-SECTION BASED ON 1991 AND 2001 SURVEY DATA
END DESCRIPTION:
XS GIS Cut Line= 6
  2402706.558179 6979895.4893627     2402891.585     6979028.856
     2403836.029     6974605.245     2403454.085     6970952.467
     2403523.529     6970730.2452402418.154492526969665.15331073
#Sta/Elev= 30
    -850     480    -760     460    -450     460    -450     466    -250     468
     400   465.6     400     465     400     458    3230     458    3260   465.6
    4530   466.4    4641     445    4735     427    5470     427    5545  445.75
    6237     445    6280   444.5    6350     427    7625     427    7675     438
    7860     445    7975     460    8200     459    8240     454    8280     434
    8325   426.4    8380     434    8410     450    8490     460   10000     480
#Mann= 11 ,-1,0
    -850     .04       0     400     .07       0    3260     .04       0
    4530     .08       0    4641     .05       0    5545     .08       0
    6237     .05       0    7860     .08       0    7975     .14       0
    8200    .057       0    8490     .14       0
#XS Ineff= 5 ,-1
    5675    6085     462    4400    5675   447.5    6085    7365     445
    7365    8000     457     400    3500     468
Permanent Ineff=
       T       T       T       T       T
#Block Obstruct= 2 ,-1
    -850     445     480    3410    4380     479
Bank Sta=8200,8490
XS Rating Curve= 0 ,0
Exp/Cntr=0.3,0.1

Type RM Length L Ch R = 1 ,102846  ,485,1376,727
BEGIN DESCRIPTION:
This cross section corresponds to cross section 102900 of the non-georeferenced CDC model which was the source of this model.
Proposed fill & lake on LOB.  Flow limit 730  LOB from 2001 aerial topo. ROB OF X-SECTION BASED ON 1991 AND 2001 SURVEY DATA
END DESCRIPTION:
XS GIS Cut Line= 5
  2403140.720865 6979830.9963793     2403280.473     6979119.134
     2404169.362     6974591.356      2404009.64     6970383.023
     2404245.751     6970264.967
#Sta/Elev= 30
    -415     480    -355     460     -55     460     -55     466     485   469.7
     805     465     805     458    3775     458    3805   465.6    4285   470.4
    4970   466.3    5107     440    5175     427    5805     427    5865     440
    5955   466.3    6310   469.8    6660   466.3    6805     445    6880     427
    7860     427    8091     445    8340     462    9140   459.8    9150     450
    9165     430    9195   426.4    9215     429    9250     450    9400     500
#Mann= 13 ,-1,0
    -415     .04       0     805     .07       0    3805     .04       0
    4970     .08       0    5107     .05       0    5865     .08       0
    5955     .04       0    6660     .08       0    6805     .05       0
    8091     .08       0    8340     .14       0    9140    .055       0
    9250     .14       0
#XS Ineff= 6 ,-1
    4800    5400     450    5400    5600     445    5600    6000     450
    6600    7850     447    7850    8310     457     705    4000     468
Permanent Ineff=
       T       T       T       T       T       T
#Block Obstruct= 4 ,-1
    -415     730     480    3955    4820     479    6105    6260     479
    6360    6510     479
Bank Sta=9140,9250
XS Rating Curve= 0 ,0
Exp/Cntr=0.3,0.1

Type RM Length L Ch R = 1 ,101470  ,749,1508,1558
BEGIN DESCRIPTION:
This cross section corresponds to cross section 101480 of the non-georeferenced CDC model which was the source of this model.
Proposed fill & lake on LOB.  Flow limit 1130  LOB from 2001 aerial topo.  ROB OF X-SECTION BASED ON 1991 AND 2001 SURVEY DATA
END DESCRIPTION:
XS GIS Cut Line= 6
 2403416.95511326979958.92533031     2404530.473     6974383.023
     2404627.696     6973695.523     2404676.307     6971619.134
     2404551.307     6971278.856      2404689.15      6970323.56
#Sta/Elev= 30
      65     480     145     460    1285     467    3180   465.6    3710   465.6
    3785     458    4245     458    4275   465.6    5460   466.2    5566     440
    5618     427    6230     427    6285     440    6380   466.2    7215   466.2
    7375     440    7430     427    8002     427    8080     440    8170     455
    8200     461    8260     449    8440     455    8608     426    8710     440
    8725     450    8775     450    8950     458    9580     462    9850     500
#Mann= 15 ,-1,0
      65     .04       0    1285     .07       0    3180     .04       0
    3710     .07       0    4275     .04       0    5460     .08       0
    5566     .05       0    6285     .08       0    6380     .04       0
    7215     .08       0    7375     .05       0    8080     .08       0
    8170     .14       0    8440    .055       0    8775     .14       0
#XS Ineff= 5 ,-1
    5400    6400   449.3    7200    7600     450    7600    7800     445
    7800    8200     450    1100    4500     468
Permanent Ineff=
       T       T       T       T       T
#Block Obstruct= 4 ,-1
      65    1130     480    4425    5310     479    6530    6750     479
    6850    7065     479
Bank Sta=8440,8775
XS Rating Curve= 0 ,0
Exp/Cntr=0.3,0.1

Type RM Length L Ch R = 1 ,99962   ,10,10,10
BEGIN DESCRIPTION:
This cross section corresponds to cross section 99990 of the non-georeferenced CDC model which was the source of this model.
U/S of Bridge #1 & #2.  Proposed fill & lake on LOB.  Flow limit 1120  Repeat of 99980.  X-SECTION BASED ON 1991 AND 2001 SURVEY DATA.
END DESCRIPTION:
XS GIS Cut Line= 3
     2404059.717     6979460.783     2405081.398     6974727.361
     2405969.484     6970594.128
#Sta/Elev= 30
     630     490     690     469    3940     466    4025     458    4071     445
    4297     449    4435   465.6    5465   466.1    5570     440    5622     427
    6310     427    6365     440    6465   466.1    7330   466.1    7480     440
    7530     427    8414     427    8492     440    8600     458    9090     460
    9180     450    9200     431    9240   425.5    9280     431    9295     440
    9300     450    9345   465.5    9345     471    9583     471    9700     490
#Mann= 13 ,-1,0
     630     .04       0    3940     .07       0    4435     .04       0
    5465     .08       0    5570     .05       0    6365     .08       0
    6465     .04       0    7330     .08       0    7480     .05       0
    8492     .08       0    8600     .14       0    9180    .055       0
    9300     .14       0
#XS Ineff= 4 ,-1
    5200    6800     449    7200    8800     447    9345    9650     474
    3900    4400   455.5
Permanent Ineff=
       T       T       T       T
#Block Obstruct= 7 ,-1
     630    1120     480    1120    1230     479    1380    3000     479
    3150    3655     479    4585    5315     479    6615    6850     479
    6950    7180     479
Bank Sta=9180,9300
XS Rating Curve= 0 ,0
Exp/Cntr=0.4,0.2

Type RM Length L Ch R = 1 ,99952   ,61,61,61
BEGIN DESCRIPTION:
This cross section corresponds to cross section 99980 of the non-georeferenced CDC model which was the source of this model.
U/S face of Bridge #1 & #2.  Proposed fill & lake on LOB.  Flow limit 1120  Repeat of 99980.  X-SECTION BASED ON 1991 AND 2001 SURVEY DATA.
END DESCRIPTION:
XS GIS Cut Line= 4
   2404078.04193  6979445.353264     2404113.807     6979278.856
      2405947.14     6970744.134 2405982.9050698 6970577.6367361
#Sta/Elev= 30
     630     490     690     469    3940     466    4025     458    4071     445
    4297     449    4435   465.6    5465   466.1    5570     440    5622     427
    6310     427    6365     440    6465   466.1    7330   466.1    7480     440
    7530     427    8414     427    8492     440    8600     458    9090     460
    9180     450    9200     431    9240   425.5    9280     431    9295     440
    9300     450    9345   465.5    9345     471    9583     471    9700     490
#Mann= 13 ,-1,0
     630     .04       0    3940     .07       0    4435     .04       0
    5465     .08       0    5570     .05       0    6365     .08       0
    6465     .04       0    7330     .08       0    7480     .05       0
    8492     .08       0    8600     .14       0    9180    .055       0
    9300     .14       0
#XS Ineff= 4 ,-1
    5200    6800     449    7200    8800     447    9345    9650     474
    3900    4400   455.5
Permanent Ineff=
       T       T       T       T
#Block Obstruct= 7 ,-1
     630    1120     480    1120    1230     479    1380    3000     479
    3150    3655     479    4585    5315     479    6615    6850     479
    6950    7180     479
Bank Sta=9180,9300
XS Rating Curve= 0 ,0
Exp/Cntr=0.4,0.2

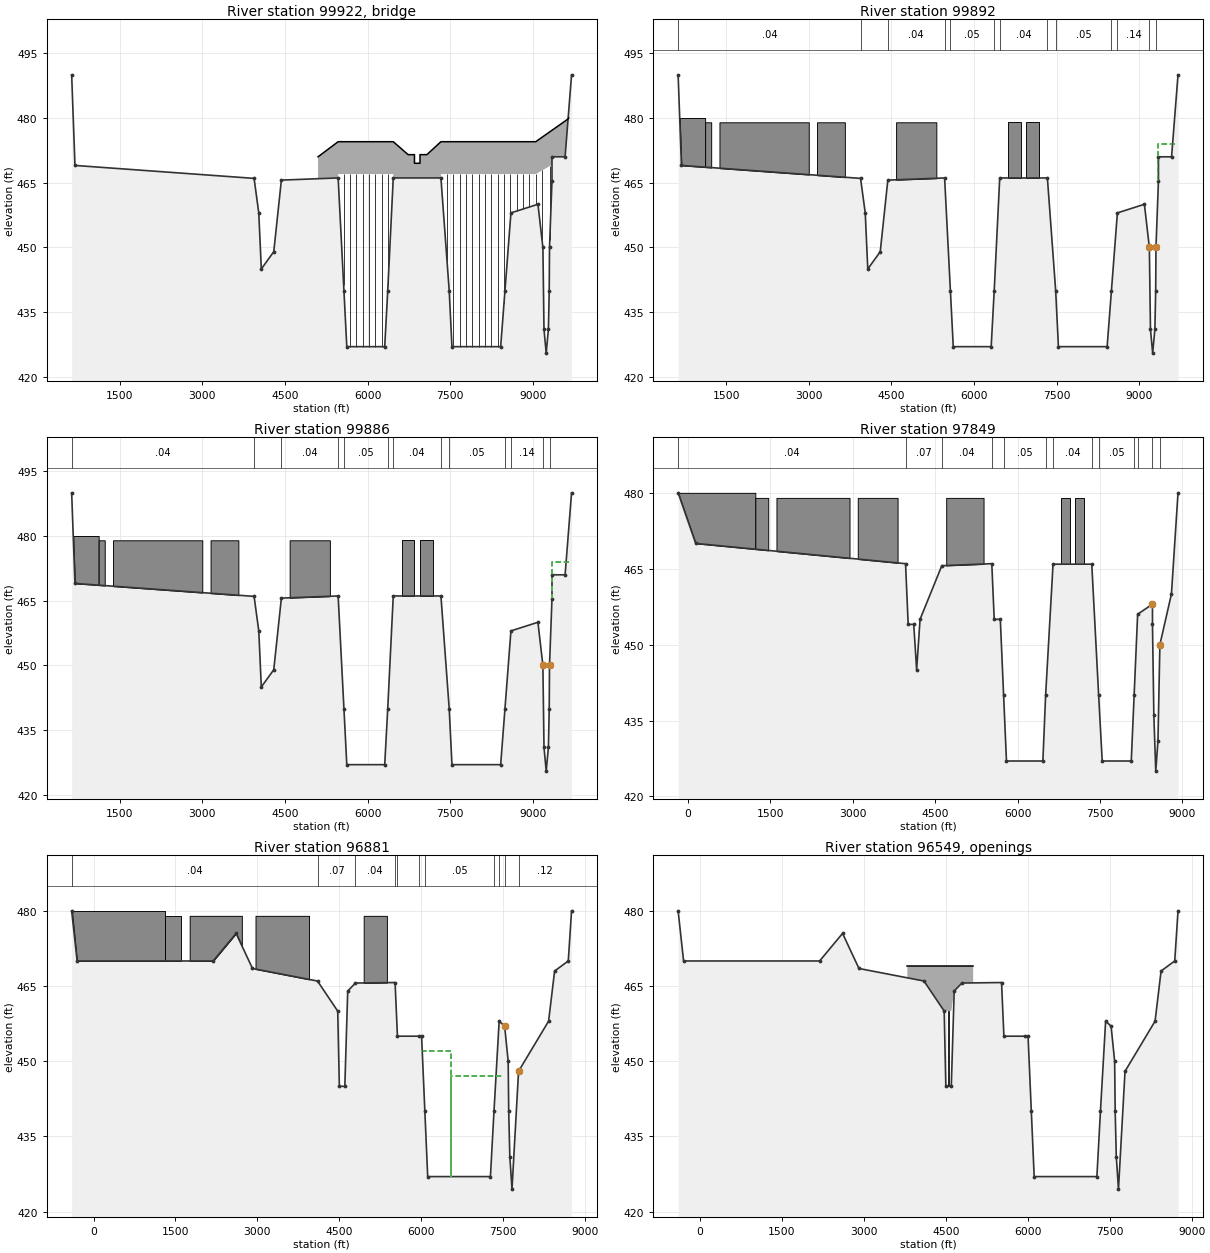
Type RM Length L Ch R = 3 ,99922   ,,,
BEGIN DESCRIPTION:
Ballpark Way
Proposed - 6' low beam to top of curb + 2.5' (30") for barrier
END DESCRIPTION:
Node Name=Ballpark Way
Bridge Culvert--1,0,-1,-1, 0
Deck Dist Width WeirC Skew NumUp NumDn MinLoCord MaxHiCord MaxSubmerge Is_Ogee
0.5,60,2.6,0, 16, 16, 480, , 0.95, 0, 0,0,,
    5100    5465    5465    6465    6465    6735    6850    6850    6950    6950
    7075    7330    7330    9050    9629    9650
     471   474.5   474.5   474.5   474.5   471.5   471.5   469.5   469.5   471.5
   471.5   474.5   474.5   474.5   479.7     480
     466     466     467     467     466     466     466     466     466     466
     466     466     467     467   471.2     474
    5100    5465    5465    6465    6465    6735    6850    6850    6950    6950
    7075    7330    7330    9050    9629    9650
     471   474.5   474.5   474.5   474.5   471.5   471.5   469.5   469.5   471.5
   471.5   474.5   474.5   474.5   479.7     480
     466     466     467     467     466     466     466     466     466     466
     466     466     467     467   471.2     474
Pier Skew, UpSta & Num, DnSta & Num=  ,5565, 2 ,5565, 2 , 0 , 0 , 0 ,,
       3       3
     437     474
       3       3
     437     474
Pier Skew, UpSta & Num, DnSta & Num=  ,5680, 2 ,5680, 2 , 0 , 0 , 0 ,,
       3       3
     437     474
       3       3
     437     474
Pier Skew, UpSta & Num, DnSta & Num=  ,5795, 2 ,5795, 2 , 0 , 0 , 0 ,,
       3       3
     437     474
       3       3
     437     474
Pier Skew, UpSta & Num, DnSta & Num=  ,5910, 2 ,5910, 2 , 0 , 0 , 0 ,,
       3       3
     437     474
       3       3
     437     474
Pier Skew, UpSta & Num, DnSta & Num=  ,6025, 2 ,6025, 2 , 0 , 0 , 0 ,,
       3       3
     437     474
       3       3
     437     474
Pier Skew, UpSta & Num, DnSta & Num=  ,6140, 2 ,6140, 2 , 0 , 0 , 0 ,,
       3       3
     437     474
       3       3
     437     474
Pier Skew, UpSta & Num, DnSta & Num=  ,6255, 2 ,6255, 2 , 0 , 0 , 0 ,,
       3       3
     437     474
       3       3
     437     474
Pier Skew, UpSta & Num, DnSta & Num=  ,6370, 2 ,6370, 2 , 0 , 0 , 0 ,,
       3       3
     437     474
       3       3
     437     474
Pier Skew, UpSta & Num, DnSta & Num=  ,7440, 2 ,7440, 2 , 0 , 0 , 0 ,,
       3       3
     437     474
       3       3
     437     474
Pier Skew, UpSta & Num, DnSta & Num=  ,7555, 2 ,7555, 2 , 0 , 0 , 0 ,,
       3       3
     437     474
       3       3
     437     474
Pier Skew, UpSta & Num, DnSta & Num=  ,7670, 2 ,7670, 2 , 0 , 0 , 0 ,,
       3       3
     437     474
       3       3
     437     474
Pier Skew, UpSta & Num, DnSta & Num=  ,7785, 2 ,7785, 2 , 0 , 0 , 0 ,,
       3       3
     437     474
       3       3
     437     474
Pier Skew, UpSta & Num, DnSta & Num=  ,7900, 2 ,7900, 2 , 0 , 0 , 0 ,,
       3       3
     437     474
       3       3
     437     474
Pier Skew, UpSta & Num, DnSta & Num=  ,8015, 2 ,8015, 2 , 0 , 0 , 0 ,,
       3       3
     437     474
       3       3
     437     474
Pier Skew, UpSta & Num, DnSta & Num=  ,8130, 2 ,8130, 2 , 0 , 0 , 0 ,,
       3       3
     437     474
       3       3
     437     474
Pier Skew, UpSta & Num, DnSta & Num=  ,8245, 2 ,8245, 2 , 0 , 0 , 0 ,,
       3       3
     437     474
       3       3
     437     474
Pier Skew, UpSta & Num, DnSta & Num=  ,8360, 2 ,8360, 2 , 0 , 0 , 0 ,,
       3       3
     437     474
       3       3
     437     474
Pier Skew, UpSta & Num, DnSta & Num=  ,8475, 2 ,8475, 2 , 0 , 0 , 0 ,,
       3       3
     437     474
       3       3
     437     474
Pier Skew, UpSta & Num, DnSta & Num=  ,8590, 2 ,8590, 2 , 0 , 0 , 0 ,,
       3       3
     437     474
       3       3
     437     474
Pier Skew, UpSta & Num, DnSta & Num=  ,8705, 2 ,8705, 2 , 0 , 0 , 0 ,,
       3       3
     437     474
       3       3
     437     474
Pier Skew, UpSta & Num, DnSta & Num=  ,8820, 2 ,8820, 2 , 0 , 0 , 0 ,,
       3       3
     437     474
       3       3
     437     474
Pier Skew, UpSta & Num, DnSta & Num=  ,8935, 2 ,8935, 2 , 0 , 0 , 0 ,,
       3       3
     437     474
       3       3
     437     474
Pier Skew, UpSta & Num, DnSta & Num=  ,9050, 2 ,9050, 2 , 0 , 0 , 0 ,,
       3       3
     437     474
       3       3
     437     474
Pier Skew, UpSta & Num, DnSta & Num=  ,9165, 2 ,9165, 2 , 0 , 0 , 0 ,,
       3       3
     437     474
       3       3
     437     474
Pier Skew, UpSta & Num, DnSta & Num=  ,9305, 2 ,9305, 2 , 0 , 0 , 0 ,,
       3       3
     437     474
       3       3
     437     474
BR Coef=-1 , 0 , 0 ,1.05, 0 ,,,0.8,-1,1.2,0,474
WSPro=,,,, 1 ,,,, 0 ,,,, 0 ,,,,-1 ,-1 ,-1 , 0 , 0 , 0 , 0 , 0
BC Design=,, 0 ,, 0 ,,,,,,
BC Use User HTab Curves=0
BC User HTab FreeFlow(D)= 0

Type RM Length L Ch R = 1 ,99892   ,6,6,6
BEGIN DESCRIPTION:
This cross section corresponds to cross section 99918 of the non-georeferenced CDC model which was the source of this model.
D/S face of Bridge #1 & #2.  Proposed fill & lake on LOB.  Flow limit 1120  Repeat of 99980
END DESCRIPTION:
XS GIS Cut Line= 4
  2404136.934075 6979468.0216169     2404174.942     6979290.844
     2406001.331     6970776.955 2406039.3389245 6970599.7773831
#Sta/Elev= 30
     630     490     690     469    3940     466    4025     458    4071     445
    4297     449    4435   465.6    5465   466.1    5570     440    5622     427
    6310     427    6365     440    6465   466.1    7330   466.1    7480     440
    7530     427    8414     427    8492     440    8600     458    9090     460
    9180     450    9200     431    9240   425.5    9280     431    9295     440
    9300     450    9345   465.5    9345     471    9583     471    9700     490
#Mann= 13 ,-1,0
     630     .04       0    3940     .07       0    4435     .04       0
    5465     .08       0    5570     .05       0    6365     .08       0
    6465     .04       0    7330     .08       0    7480     .05       0
    8492     .08       0    8600     .14       0    9180    .055       0
    9300     .14       0
#XS Ineff= 4 ,-1
    5200    6800     449    7200    8800     447    9345    9650     474
    3900    4400   455.5
Permanent Ineff=
       T       T       T       T
#Block Obstruct= 7 ,-1
     630    1120     480    1120    1230     479    1380    3000     479
    3150    3655     479    4585    5315     479    6615    6850     479
    6950    7180     479
Bank Sta=9180,9300
XS Rating Curve= 0 ,0
Exp/Cntr=0.4,0.2

Type RM Length L Ch R = 1 ,99886   ,257,2038,2145
BEGIN DESCRIPTION:
This cross section corresponds to cross section 99908 of the non-georeferenced CDC model which was the source of this model.
D/S of Bridge #1 & #2.  Proposed fill & lake on LOB.  Flow limit 1120  Repeat of 99980
END DESCRIPTION:
XS GIS Cut Line= 4
      2404138.47     6979473.908     2405155.749     6974749.724
     2406008.784     6970770.542     2406048.819     6970605.992
#Sta/Elev= 30
     630     490     690     469    3940     466    4025     458    4071     445
    4297     449    4435   465.6    5465   466.1    5570     440    5622     427
    6310     427    6365     440    6465   466.1    7330   466.1    7480     440
    7530     427    8414     427    8492     440    8600     458    9090     460
    9180     450    9200     431    9240   425.5    9280     431    9295     440
    9300     450    9345   465.5    9345     471    9583     471    9700     490
#Mann= 13 ,-1,0
     630     .04       0    3940     .07       0    4435     .04       0
    5465     .08       0    5570     .05       0    6365     .08       0
    6465     .04       0    7330     .08       0    7480     .05       0
    8492     .08       0    8600     .14       0    9180    .055       0
    9300     .14       0
#XS Ineff= 4 ,-1
    5200    6800     449    7200    8800     447    9345    9650     474
    3900    4400   455.5
Permanent Ineff=
       T       T       T       T
#Block Obstruct= 7 ,-1
     630    1120     480    1120    1230     479    1380    3000     479
    3150    3655     479    4585    5315     479    6615    6850     479
    6950    7180     479
Bank Sta=9180,9300
XS Rating Curve= 0 ,0
Exp/Cntr=0.4,0.2

Type RM Length L Ch R = 1 ,97849   ,688,967,818
BEGIN DESCRIPTION:
This cross section corresponds to cross section of 97925 the non-georeferenced CDC model which was the source of this model.
Proposed fill & lake on LOB.  Flow limit 1225  452.9 for continuity around island.  LOB from 2001 aerial topo.  ROB OF X-SECTION BASED ON 1991 AND 2001 SURVEY DATA
END DESCRIPTION:
XS GIS Cut Line= 6
  2404117.181044  6980411.203205     2405224.918     6974889.967
      2406009.64     6972834.411     2406738.807     6972521.911
     2406815.196       6972535.8     2407190.196     6972403.856
#Sta/Elev= 30
    -180     480     140     470    3960     466    4008     454    4109     454
    4162     445    4224     455    4620   465.6    5530     466    5574     455
    5685     455    5745     440    5797     427    6460     427    6510     440
    6645   465.9    7350   465.9    7475     440    7540     427    8069     427
    8121     440    8185     456    8455     458    8455     454    8480     436
    8515     425    8555     431    8590     450    8800     460    8920     480
#Mann= 13 ,-1,0
    -180     .04       0    3960     .07       0    4620     .04       0
    5530     .08       0    5745     .05       0    6510     .08       0
    6645     .04       0    7350     .08       0    7475     .05       0
    8121     .08       0    8185     .14       0    8455     .06       0
    8590     .12       0
#XS Ineff= 3 ,-1
    5500    6700   452.3    7200    8200     446    3900    4500   459.8
Permanent Ineff=
       T       T       T
#Block Obstruct= 7 ,-1
    -180    1225     480    1225    1460     479    1610    2940     479
    3090    3815     479    4700    5380     479    6795    6950     479
    7050    7200     479
Bank Sta=8455,8590
XS Rating Curve= 0 ,0
Exp/Cntr=0.3,0.1

Type RM Length L Ch R = 1 ,96881   ,538,363,108
BEGIN DESCRIPTION:
This cross section corresponds to cross section 96955 of the non-georeferenced CDC model which was the source of this model.
Proposed fill & lake on LOB.  U/S face of bridge #3.  Flow limit 1300  Far LOB realigned for hydraulics.  LOB from 2001 aerial topo.  ROB OF X-SECTION BASED ON 1991 AND 2001 SURVEY DATA
END DESCRIPTION:
XS GIS Cut Line= 6
  2404274.836498 6980755.8538621 2405405.4730169 6975021.9109336
 2405759.6399595 6974744.1339302 2406377.6961381 6973633.0229634
 2406870.7509263 6973494.1341336 2407617.8842745 6972748.3311632
#Sta/Elev= 30
    -400     480    -300     470    2190     470    2610   475.5    2910   468.5
    4100     466    4470     460    4500     445    4600     445    4653     464
    4795   465.6    5520   465.7    5563     455    5950     455    6005     455
    6065     440    6117     427    7265     427    7330     440    7425     458
    7525     457    7590     450    7600     440    7620     431    7660   424.5
    7780     448    8330     458    8440     468    8690     470    8750     480
#Mann= 11 ,-1,0
    -400     .04       0    4100     .07       0    4795     .04       0
    5520     .09       0    5563     .12       0    5950     .09       0
    6065     .05       0    7330     .09       0    7425     .14       0
    7525     .06       0    7780     .12       0
#XS Ineff= 2 ,-1
    6000    6550     452    6550    7500     447
Permanent Ineff=
       T       T
#Block Obstruct= 5 ,-1
    -400    1300     480    1300    1610     479    1760    2715     479
    2965    3945     479    4945    5370     479
Bank Sta=7525,7780
XS Rating Curve= 0 ,0
Exp/Cntr=0.3,0.1

Type RM Length L Ch R = 4 ,96549   ,,,
BEGIN DESCRIPTION:
Bridge over Hurricane Creek
2-80' spans
END DESCRIPTION:
Node Name=Bridge over Hurr
Bridge Culvert--1,0,-1,-1, 0
Deck Dist Width WeirC Skew NumUp NumDn MinLoCord MaxHiCord MaxSubmerge Is_Ogee
150,62,2.6,0, 2, 3, 469, , 0.95, 0, 2,2,,
    3796    5000
     469     469
     460     460
    5080    5155    5466
   467.5     469     469
     460     460     460
Pier Skew, UpSta & Num, DnSta & Num=  ,4550, 2 ,5307, 2 , 0 , 0 , 0 ,,
       3       3
     444     460
       3       3
     444     460
Abutment Skew #Up #Dn= , 3 , 3
    4460    4470    4500
     460     460     445
    5180    5227    5259
     460     460     444
Abutment Skew #Up #Dn= , 3 , 3
    4600    4630    4640
     445     460     460
    5355    5387    5430
     444     460     460
BR Coef=-1 , 0 , 0 ,1.05, 0 ,,,0.8,-1,1.2,0,
WSPro=,,,, 1 ,,,, 0 ,,,, 0 ,,,,-1 ,-1 ,-1 , 0 , 0 , 0 , 0 , 0
BC Mult= 1 ,-400,3780,160,4800
BC Mult= 3 ,3780,5150,4800,5485
BC Mult= 1 ,5150,8750,5485,8850
BC Design=,, 0 ,, 0 ,,,,,,
BC Use User HTab Curves=0
BC User HTab FreeFlow(D)= 0