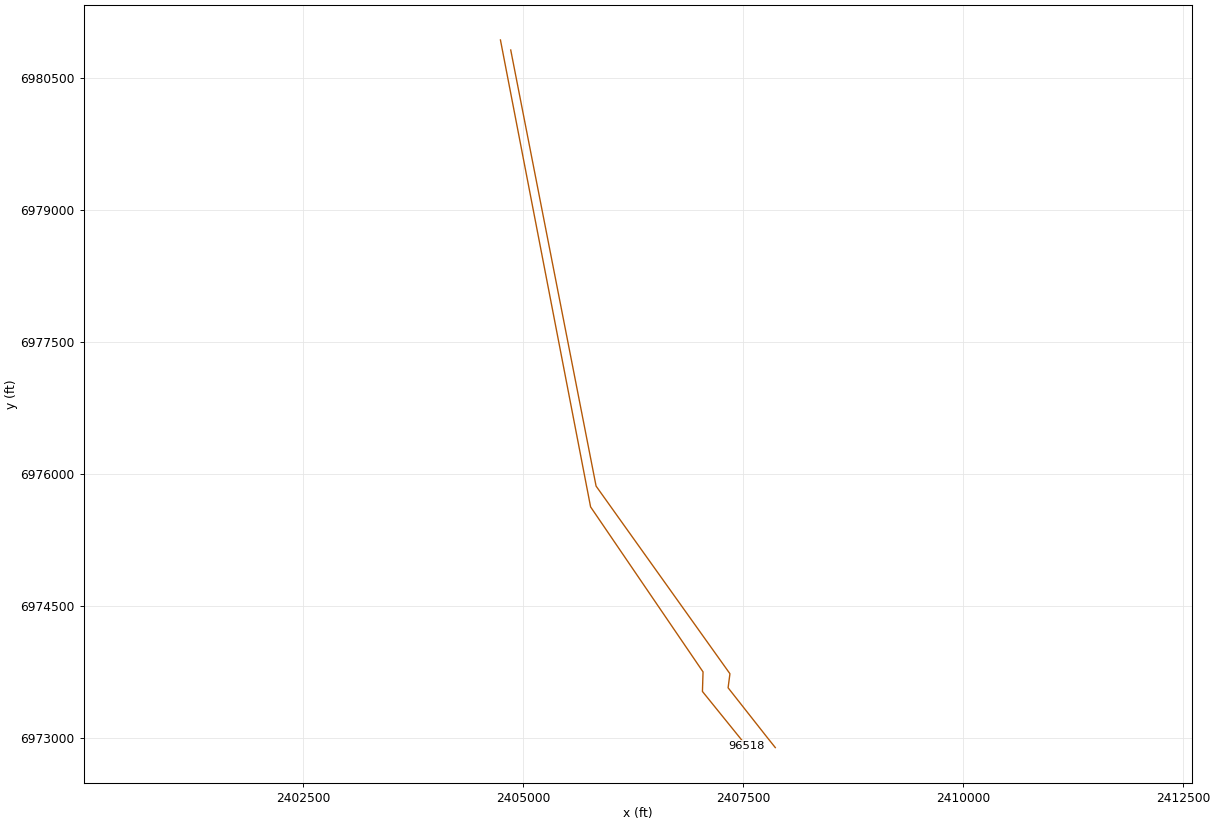
HEC-RAS study CDC_Consolidated_Model.prj: Upper Trinity CDC Consolidated Model

--- CDC_Consolidated_Model.g02 (geometry) --- (continued)

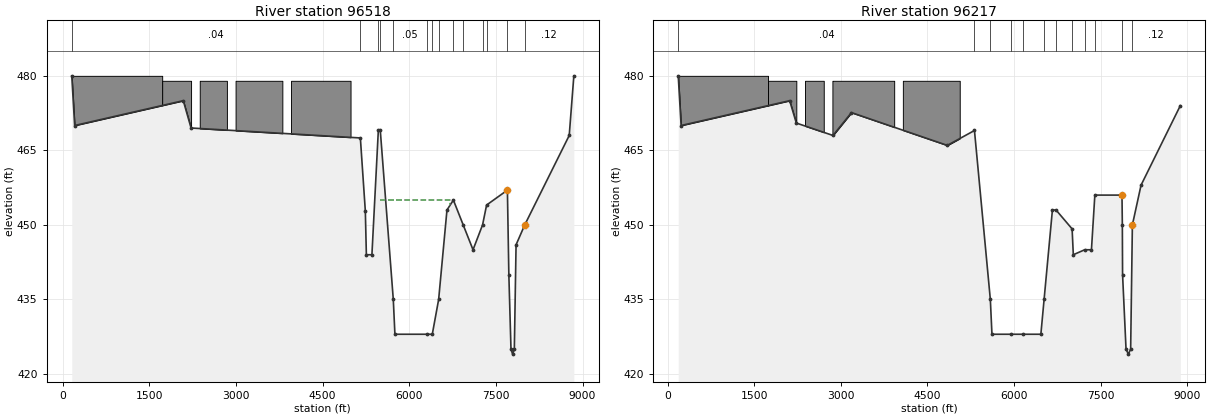
Type RM Length L Ch R = 1 ,96518   ,199,301,272
BEGIN DESCRIPTION:
This cross section corresponds to cross section 96550 of the non-georeferenced CDC model which was the source of this model.
Proposed fill & lake overflow structure on LOB.  D/S face of bridge #3.  Flow limit 1725  Flow limited in LOB due to sewer ridge.  LOB from 2001 aerial topo.  ROB OF X-SECTION BASED ON 1991 AND 2001 SURVEY DATA
END DESCRIPTION:
XS GIS Cut Line= 6
  2404742.167568 6980931.7807449     2405030.473     6979438.578
     2405766.585     6975626.078     2407044.362     6973751.078
     2407037.418     6973528.856     2407537.418       6972910.8
#Sta/Elev= 30
     160     480     210     470    2090     475    2225   469.5    5155   467.5
    5241   452.8    5259     444    5355     444    5466     469    5500     469
    5725     435    5753     428    6300     428    6400     428    6510     435
    6654     453    6765     455    6935     450    7105     445    7270     450
    7340     454    7700     457    7725     440    7762     425    7790     424
    7820     425    7850     446    8000     450    8770     468    8850     480
#Mann= 14 ,-1,0
     160     .04       0    5155     .07       0    5466     .04       0
    5500     .09       0    5725     .05       0    6300     .12       0
    6400     .05       0    6510     .09       0    6765     .08       0
    6935    .025       0    7270     .08       0    7340     .14       0
    7700     .06       0    8000     .12       0
#XS Ineff= 1 ,-1
    5500    6700     455
Permanent Ineff=
       T
#Block Obstruct= 5 ,-1
     160    1725     480    1725    2225     479    2375    2845     479
    2995    3805     479    3955    4985     479
Bank Sta=7700,8000
XS Rating Curve= 0 ,0
Exp/Cntr=0.3,0.1

Type RM Length L Ch R = 1 ,96217   ,166,176,166
BEGIN DESCRIPTION:
This cross section corresponds to cross section 96240 of the non-georeferenced CDC model which was the source of this model.
Proposed fill, lake, & lake ooutfall on LOB.  Flow limit 1740  Flow limited in LOB due to sewer ridge.  LOB from 2001 aerial topo.  ROB OF X-SECTION BASED ON 1991 AND 2001 SURVEY DATA
END DESCRIPTION:
XS GIS Cut Line= 6
  2404859.079752 6980817.8589874 2405829.0850306 6975862.1891087
 2407349.9179469 6973730.2452099 2407329.0849833 6973570.5230884
 2407766.5850926 6973014.9671129 2407865.2499215 6972891.2121111
#Sta/Elev= 30
     185     480     235     470    2115     475    2230   470.5    2865     468
    3185   472.6    4845     466    5315     469    5590     435    5618     428
    5950     428    6150     428    6465     428    6521     435    6665     453
    6728     453    7006   449.2    7027     444    7224     445    7341     445
    7400     456    7870     456    7876     450    7880     440    7940     425
    7980     424    8020     425    8050     450    8200     458    8880     474
#Mann= 12 ,-1,0
     185     .04       0    5315     .09       0    5590     .05       0
    5950     .12       0    6150     .05       0    6521     .09       0
    6728     .08       0    7006     .06       0    7224     .08       0
    7400     .14       0    7870     .06       0    8050     .12       0
#XS Ineff= 1 ,-1
    5400    6700   452.5
Permanent Ineff=
       T
#Block Obstruct= 5 ,-1
     185    1740     480    1740    2230     479    2380    2705     479
    2855    3925     479    4075    5060     479
Bank Sta=7870,8050
XS Rating Curve= 0 ,0
Exp/Cntr=0.3,0.1