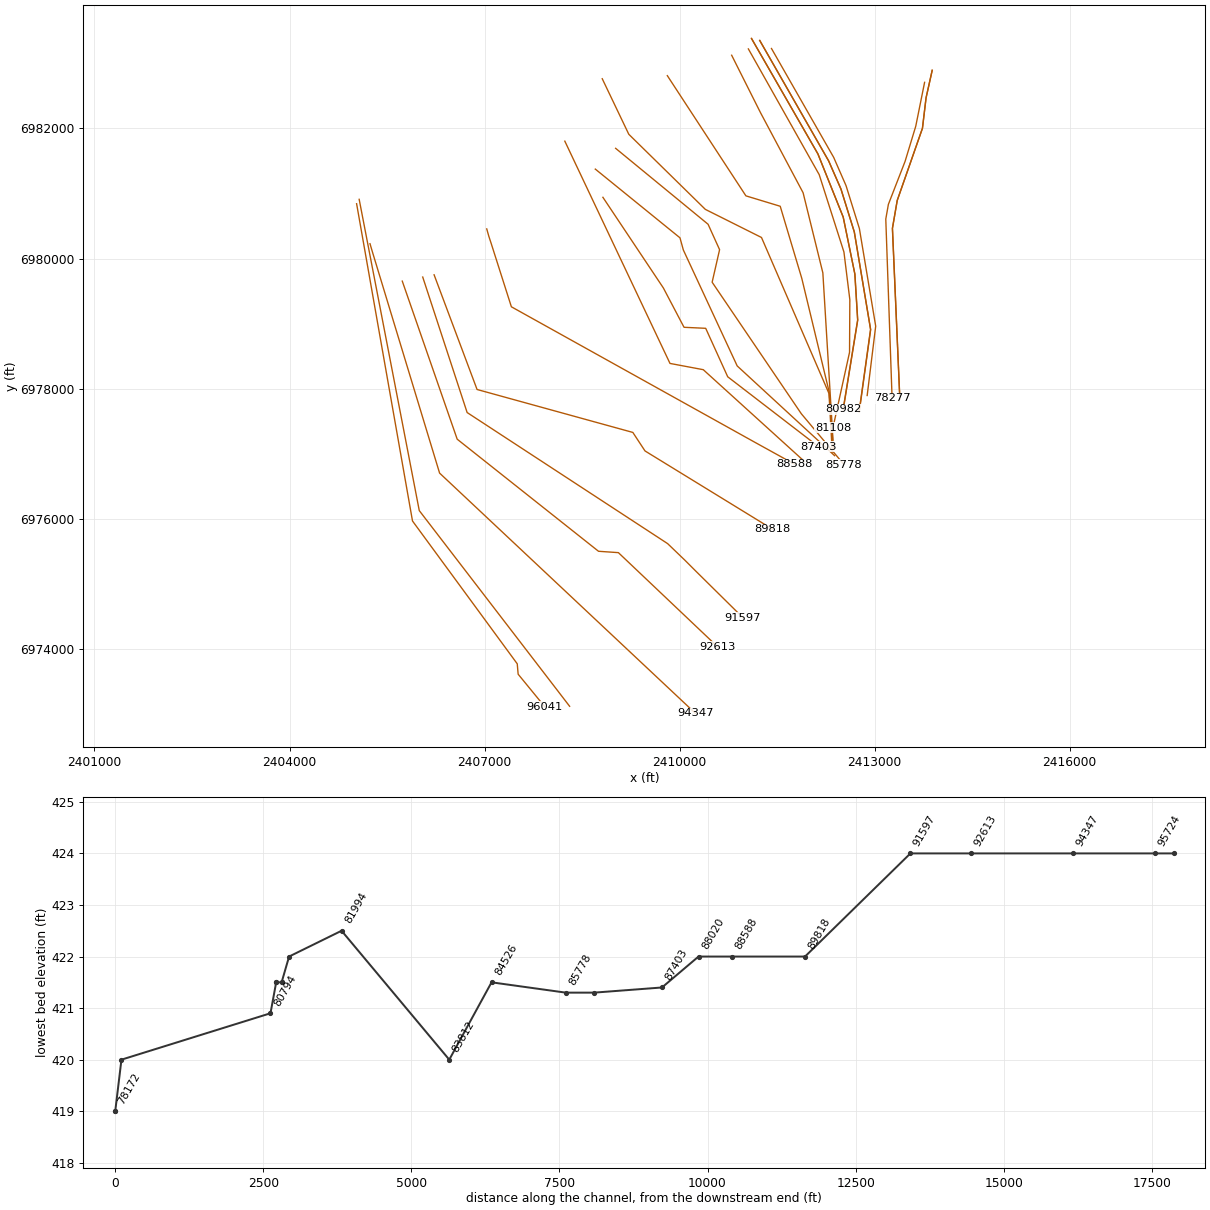
HEC-RAS study CDC_Consolidated_Model.prj: Upper Trinity CDC Consolidated Model

--- CDC_Consolidated_Model.g02 (geometry) --- (continued)

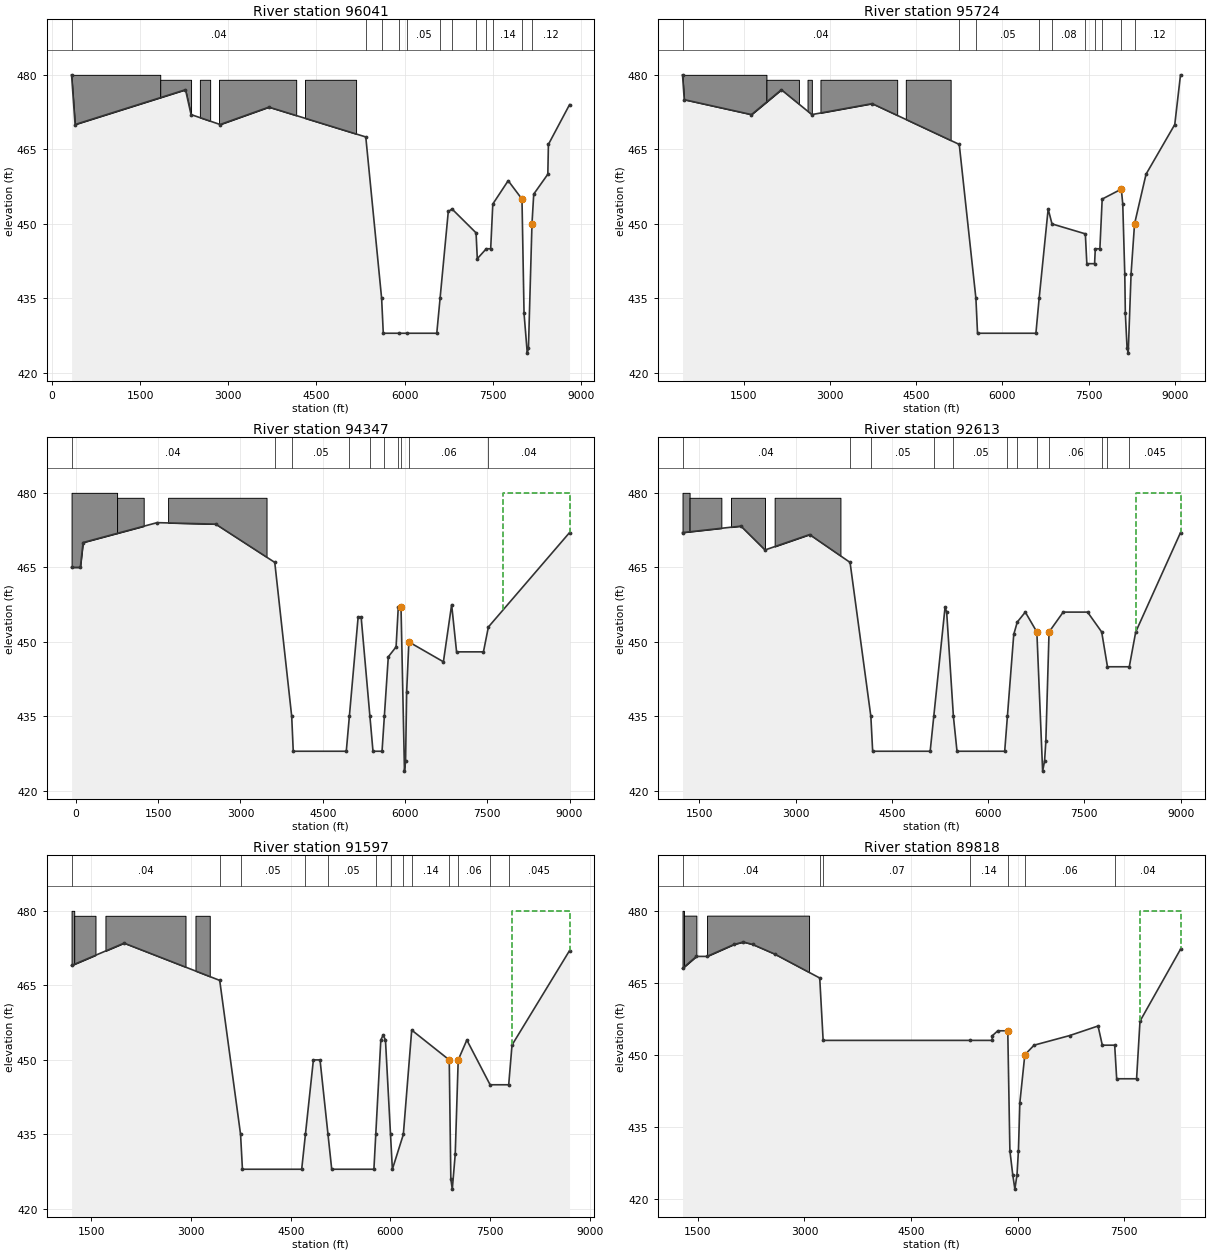
Type RM Length L Ch R = 1 ,96041   ,213,317,333
BEGIN DESCRIPTION:
This cross section corresponds to cross section 96070 of the non-georeferenced CDC model which was the source of this model.
Proposed fill, lake, & lake ooutfall on LOB.  Flow limit 1840  Flow limited in LOB due to sewer ridge.  LOB from 2001 aerial topo.  ROB OF X-SECTION BASED ON 1991 AND 2001 SURVEY DATA
END DESCRIPTION:
XS GIS Cut Line= 6
  2405031.750795 6980841.9999936     2405280.473     6979431.634
     2405891.585     6975966.356     2407502.696     6973771.911
     2407516.585     6973612.189     2407926.307     6973112.189
#Sta/Elev= 30
     330     480     390     470    2270     477    2365     472    2860     470
    3690   473.5    5340   467.5    5610     435    5638     428    5900     428
    6050     428    6549     428    6605     435    6745   452.5    6809     453
    7218   448.2    7239     443    7392     445    7467     445    7503     454
    7765   458.7    8000     455    8035     432    8090     424    8110     425
    8170     450    8200     456    8440     460    8450     466    8810     474
#Mann= 12 ,-1,0
     330     .04       0    5340     .09       0    5610     .05       0
    5900     .12       0    6050     .05       0    6605     .09       0
    6809     .08       0    7218     .06       0    7392     .08       0
    7503     .14       0    8000     .06       0    8170     .12       0
#XS Ineff= 1 ,-1
    5400    6800   452.5
Permanent Ineff=
       T
#Block Obstruct= 5 ,-1
     330    1840     480    1840    2365     479    2515    2690     479
    2840    4155     479    4305    5175     479
Bank Sta=8000,8170
XS Rating Curve= 0 ,0
Exp/Cntr=0.3,0.1

Type RM Length L Ch R = 1 ,95724   ,883,1377,1200
BEGIN DESCRIPTION:
This cross section corresponds to cross section 95765 of the non-georeferenced CDC model which was the source of this model.
Proposed fill, lake, & lake ooutfall on LOB.  Flow limit 1895  Flow limited in LOB due to sewer ridge.  LOB from 2001 aerial topo.  ROB OF X-SECTION BASED ON 1991 AND 2001
END DESCRIPTION:
XS GIS Cut Line= 4
  2405071.277154 6980909.2250994     2405356.862     6979431.634
     2405995.751     6976126.078     2408308.251     6973119.134
#Sta/Elev= 30
     435     480     465     475    1635     472    2155     477    2685     472
    3735   474.2    5250     466    5540     435    5568     428    6584     428
    6640     435    6797     453    6864     450    7444     448    7470     442
    7605     442    7617     445    7697     445    7737     455    8070     457
    8095     454    8130     440    8140     432    8170     425    8190     424
    8240     440    8300     450    8500     460    9000     470    9100     480
#Mann= 10 ,-1,0
     435     .04       0    5250     .09       0    5540     .05       0
    6640     .09       0    6864     .08       0    7444     .06       0
    7617     .08       0    7737     .14       0    8070     .06       0
    8300     .12       0
#XS Ineff= 1 ,-1
    5300    6800     452
Permanent Ineff=
       T
#Block Obstruct= 5 ,-1
     435    1895     480    1895    2460     479    2610    2685     479
    2835    4170     479    4320    5100     479
Bank Sta=8070,8300
XS Rating Curve= 0 ,0
Exp/Cntr=0.3,0.1

Type RM Length L Ch R = 1 ,94347   ,681,1734,1008
BEGIN DESCRIPTION:
This cross section corresponds to cross section 94400 of the non-georeferenced CDC model which was the source of this model.
Proposed fill & lakes (2) on LOB.  Flow limit 750  Flow limited in LOB due to sewer ridge.  LOB from 2001 aerial topo.  ROB OF X-SECTION BASED ON 1991 AND 2001 SURVEY DATA  SET COE NON-EFFECTIVE FLOW LIMIT AT FILL LINE IN ROB
END DESCRIPTION:
XS GIS Cut Line= 6
  2405237.782735 6980227.1465862 2405275.2327918 6980100.3282702
 2405467.9728919  6979466.356113  2406308.251067 6976702.4669557
 2409357.6514643 6973841.55108962410243.73420308 6973010.2374424
#Sta/Elev= 30
     -80     465      80     465     130     470    1480     474    2548   473.7
    3625     466    3934     435    3962     428    4929     428    4985     435
    5145     455    5200     455    5360     435    5416     428    5581     428
    5623     435    5695     447    5837     449    5877     457    5927     457
    5990     424    6010     426    6030     440    6070     450    6700     446
    6850   457.5    6940     448    7430     448    7520     453    9000     472
#Mann= 10 ,-1,0
     -80     .04       0    3625     .09       0    3934     .05       0
    4985     .09       0    5360     .05       0    5623     .09       0
    5877     .14       0    5927    .055       0    6070     .06       0
    7520     .04       0
#XS Ineff= 2 ,-1
    3700    5800   447.5    7785    9000     480
Permanent Ineff=
       T       F
#Block Obstruct= 3 ,-1
     -80     750     480     750    1235     479    1680    3475     479
Bank Sta=5927,6070
XS Rating Curve= 0 ,0
Exp/Cntr=0.3,0.1

Type RM Length L Ch R = 1 ,92613   ,555,1016,585
BEGIN DESCRIPTION:
This cross section corresponds to cross section 92680 of the non-georeferenced CDC model which was the source of this model.
Proposed fill & lakes (2) on LOB.  Flow limit 1350  Flow limited in LOB due to sewer ridge.  LOB from 2001 aerial topo.  ROB OF X-SECTION BASED ON 1991 AND 2001 SURVEY DATA  SET COE NON-EFFECTIVE FLOW LIMIT AT FILL LINE IN ROB
END DESCRIPTION:
XS GIS Cut Line= 6
  2405734.098521 6979652.6362441     2406579.085       6977223.3
     2408752.696     6975501.078     2409058.251     6975480.245
     2410080.402      6974511.272410586.963189156974031.06196004
#Sta/Elev= 30
    1240     472    2150   473.3    2525   468.5    3220   471.6    3850     466
    4174     435    4202     428    5098     428    5154     435    5330     457
    5355     456    5460     435    5516     428    6259     428    6301     435
    6400   451.5    6455     454    6580     456    6760     452    6850     424
    6880     426    6900     430    6950     452    7170     456    7550     456
    7770     452    7860     445    8200     445    8300     452    8998     472
#Mann= 12 ,-1,0
    1240     .04       0    3850     .09       0    4174     .05       0
    5154     .09       0    5460     .05       0    6301     .09       0
    6455     .14       0    6760    .055       0    6950     .06       0
    7770    .055       0    7860    .035       0    8200    .045       0
#XS Ineff= 2 ,-1
    4000    6500     449    8300    8998     480
Permanent Ineff=
       T       F
#Block Obstruct= 4 ,-1
    1240    1350     480    1350    1845     479    1995    2525     479
    2675    3700     479
Bank Sta=6760,6950
XS Rating Curve= 0 ,0
Exp/Cntr=0.3,0.1

Type RM Length L Ch R = 1 ,91597   ,856,1779,1148
BEGIN DESCRIPTION:
This cross section corresponds to cross section 91637 of the non-georeferenced CDC model which was the source of this model.
Proposed fill & lakes (3) on LOB.  Flow limit 1240  Flow limited in LOB due to sewer ridge.  LOB from 2001 aerial topo.  ROB OF X-SECTION BASED ON 1991 AND 2001 SURVEY DATA  SET COE NON-EFFECTIVE FLOW LIMIT AT FILL LINE IN ROB
END DESCRIPTION:
XS GIS Cut Line= 6
  2406048.778816 6979715.1134895 2406731.8620964 6977633.0231655
 2409815.1961528 6975619.1341486 2410079.0358482 6975366.1579486
 2410266.5617199 6975179.07695792410972.212002316974482.48745869
#Sta/Elev= 30
    1200     469    1990   473.5    3430     466    3744     435    3772     428
    4664     428    4720     435    4840     450    4940     450    5060     435
    5116     428    5751     428    5779     435    5855     454    5890     455
    5925     454    6001     435    6029     428    6194     435    6320     456
    6885     450    6909     426    6931     424    6975     431    7020     450
    7150     454    7500     445    7780     445    7830     453    8696     472
#Mann= 13 ,-1,0
    1200     .04       0    3430     .09       0    3744     .05       0
    4720     .09       0    5060     .05       0    5779     .09       0
    6001     .05       0    6194     .09       0    6320     .14       0
    6885    .055       0    7020     .06       0    7500    .035       0
    7780    .045       0
#XS Ineff= 2 ,-1
    3500    6300     452    7830    8696     480
Permanent Ineff=
       T       F
#Block Obstruct= 4 ,-1
    1200    1240     480    1240    1560     479    1710    2915     479
    3065    3280     479
Bank Sta=6885,7020
XS Rating Curve= 0 ,0
Exp/Cntr=0.3,0.1

Type RM Length L Ch R = 1 ,89818   ,1028,1230,1023
BEGIN DESCRIPTION:
This cross section corresponds to cross section 89870 of the non-georeferenced CDC model which was the source of this model.
Proposed fill on LOB.  Flow limit 1305  LOB ground lowered to 457 and 453  LOB along sewer ridge.  Existing pond added to ROB.  LOB from 2001 aerial topo.  ROB OF X-SECTION BASED ON 1991 AND 2001 SURVEY DATA  SET COE NON-EFFECTIVE FLOW LIMIT AT FILL LINE IN ROB
END DESCRIPTION:
XS GIS Cut Line= 6
  2406223.789271 6979749.4576084      2406884.64     6977987.189
     2409280.473     6977327.467     2409467.973     6977042.745
     2410940.196     6976139.9672411426.112855726975841.99920085
#Sta/Elev= 30
    1285     468    1480   470.5    1630   470.5    2010     473    2140   473.5
    2270     473    2580     471    3215     466    3263     453    5325     453
    5640     453    5645     454    5720     455    5860     455    5890     430
    5930     425    5960     422    5990     425    6010     430    6030     440
    6100     450    6230     452    6730     454    7130     456    7190     452
    7364     452    7392     445    7672     445    7720     457    8290     472
#Mann= 7 ,-1,0
    1285     .04       0    3215     .09       0    3263     .07       0
    5325     .14       0    5860    .055       0    6100     .06       0
    7364     .04       0
#XS Ineff= 1 ,-1
    7720    8290     480
Permanent Ineff=
       F
#Block Obstruct= 3 ,-1
    1285    1305     480    1305    1480     479    1630    3065     479
Bank Sta=5860,6100
XS Rating Curve= 0 ,0
Exp/Cntr=0.3,0.1

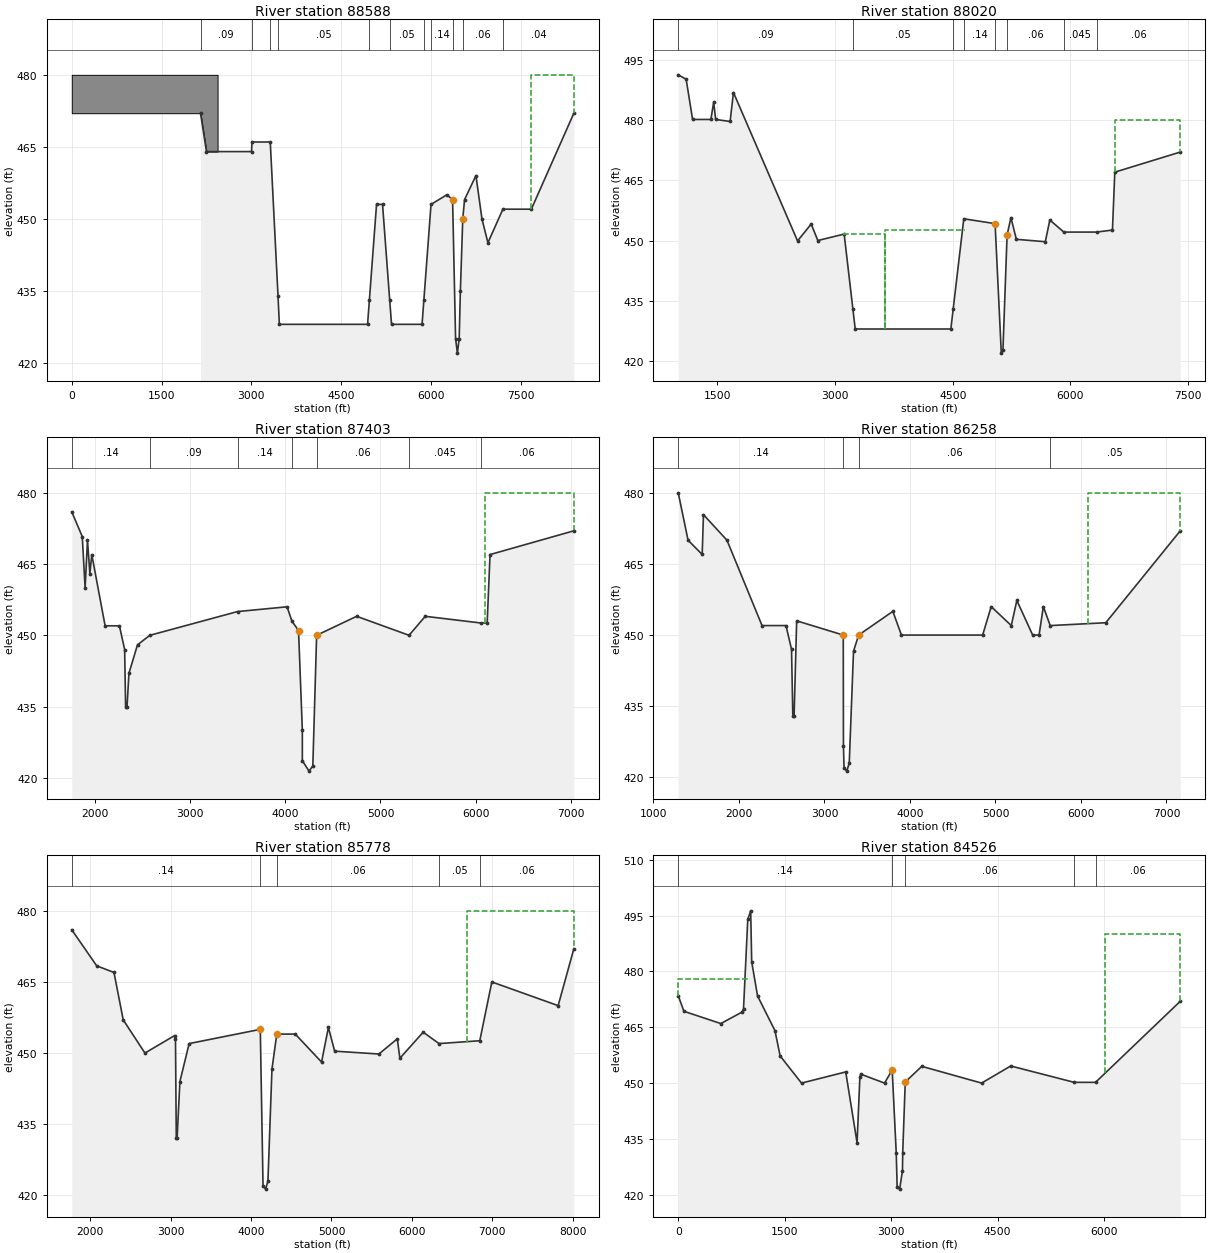
Type RM Length L Ch R = 1 ,88588   ,1110,568,444
BEGIN DESCRIPTION:
This cross section corresponds to cross section 88710 of the non-georeferenced CDC model which was the source of this model.
Proposed fill and lakes (2) in LOB.  Flow limited in LOB due to sewer ridge and D/S high ground.  LOB from 2001 aerial topo. - realigned for hydraulics - ROB OF X-SECTION BASED ON 1991 AND 2001 SURVEY DATA  SET COE NON-EFFECTIVE FLOW LIMIT AT FILL LINE IN ROB
END DESCRIPTION:
XS GIS Cut Line= 6
2407033.356106516980454.86166243  2407066.078149 6980339.7788345
     2407099.918     6980237.189     2407412.418     6979258.023
     2411174.952     6977166.217      2411765.65      6976840.42
#Sta/Elev= 30
    2150     472    2250     464    3002     464    3010     466    3315     466
    3444     434    3467     428    4940     428    4970     433    5090     453
    5190     453    5310     433    5340     428    5850     428    5880     433
    6000     453    6265     455    6360     454    6410     425    6440     422
    6470     425    6490     435    6530     450    6560     454    6750     459
    6850     450    6950     445    7200     452    7675     452    8385     472
#Mann= 11 ,-1,0
    2150     .09       0    3010     .04       0    3315     .09       0
    3444     .05       0    4970     .09       0    5310     .05       0
    5880     .09       0    6000     .14       0    6360    .055       0
    6530     .06       0    7200     .04       0
#XS Ineff= 3 ,-1
    3315    5100     453    5190    6000     453    7675    8385     480
Permanent Ineff=
       T       T       F
#Block Obstruct= 2 , 0
       0    2435     480               0
Bank Sta=6360,6530
XS Rating Curve= 0 ,0
Exp/Cntr=0.3,0.1

Type RM Length L Ch R = 1 ,88020   ,377,617,157
BEGIN DESCRIPTION:
This cross section corresponds to cross section 88045 of the non-georeferenced CDC model which was the source of this model.
Proposed lake in LOB.  Flow limited in LOB due to sewer ridge and D/S high ground.  CHANNEL BASED ON 1991 SURVEY DATA  SET COE NON-EFFECTIVE FLOW LIMIT AT FILL LINE IN ROB
END DESCRIPTION:
XS GIS Cut Line= 6
  2408234.632056 6981803.1598383 2409022.6114519 6980139.1474183
 2409395.8925295 6979350.9380367 2409852.1491629 6978387.5771026
 2410363.9699897 6978291.61108712411920.070240386976881.40353538
#Sta/Elev= 30
    1000   491.2    1101   490.1    1183   480.1    1416   480.1    1452   484.4
    1477   480.1    1661   479.6    1704   486.8    2521   449.9    2695   454.1
    2779     450    3115   451.6    3226     433    3256     428    4475     428
    4505     433    4640   455.4    5039   454.2    5118     422    5139   422.7
    5192   451.4    5241   455.7    5310   450.3    5679   449.7    5737   455.1
    5915   452.1    6332   452.1    6535   452.6    6565     467    7400     472
#Mann= 8 ,-1,0
    1000     .09       0    3226     .05       0    4505     .09       0
    4640     .14       0    5039    .055       0    5192     .06       0
    5915    .045       0    6332     .06       0
#XS Ineff= 3 ,-1
    3100    3640   451.5    3640    4650   452.5    6565    7400     480
Permanent Ineff=
       T       T       F
Bank Sta=5039,5192
XS Rating Curve= 0 ,0
Exp/Cntr=0.3,0.1

Type RM Length L Ch R = 1 ,87403   ,688,1145,205
BEGIN DESCRIPTION:
This cross section corresponds to cross section 87415 of the non-georeferenced CDC model which was the source of this model.
LOB from 2001 aerial topo. Far ROB from 2001 aerial topo - realigned for hydraulics -  ROB OF X-SECTION BASED ON 1991 AND 2001 SURVEY DATA  SET COE NON-EFFECTIVE FLOW LIMIT AT FILL LINE IN ROB  Added 2001 survey information for flood plain
END DESCRIPTION:
XS GIS Cut Line= 6
  2408820.035717 6980940.3439224 2409750.3609807 6979547.1033268
 2410068.0693348 6978942.9368842 2410401.4026576 6978927.3119155
 2410739.9443033  6978182.5200982412135.246462176977110.01177108
#Sta/Elev= 30
    1760     476    1870   470.8    1900     460    1925     470    1950     463
    1970     467    2110     452    2260     452    2315     447    2325     435
    2340     435    2360     442    2450     448    2580     450    3500     455
    4020     456    4070     453    4140     451    4180     430    4180   423.6
    4250   421.4    4290   422.5    4330     450    4750     454    5300     450
    5470     454    6050   452.6    6120   452.6    6150     467  7029.6     472
#Mann= 7 ,-1,0
    1760     .14       0    2580     .09       0    3500     .14       0
    4070    .055       0    4330     .06       0    5300    .045       0
    6050     .06       0
#XS Ineff= 2 , 0
       0                    6100       0     480
Permanent Ineff=
       F       F
Bank Sta=4140,4330
XS Rating Curve= 0 ,0
Exp/Cntr=0.3,0.1

Type RM Length L Ch R = 1 ,86258   ,394,480,411
BEGIN DESCRIPTION:
This cross section corresponds to cross section 86300 of the non-georeferenced CDC model which was the source of this model.
LOB from 2001 aerial topo. - realigned for hydraulics -  ROB OF X-SECTION BASED ON 1991 AND 2001 SURVEY DATA  SET COE NON-EFFECTIVE FLOW LIMIT AT FILL LINE IN ROB  Added 2001 survey information for flood plain
END DESCRIPTION:
XS GIS Cut Line= 6
  2408703.405812 6981373.7449416 2408849.3191476 6981255.4368524
 2410005.5694597 6980317.9367589 2410057.6526889 6980130.4368058
 2410885.7776731 6978349.18675942412384.155768146976970.24438076
#Sta/Elev= 30
    1290     480    1405     470    1570     467    1585   475.4    1860     470
    2270     452    2550     452    2615     447    2630     433    2645     433
    2675     453    3220     450    3222   426.7    3229     422    3261   421.3
    3290     423    3340   446.6    3400     450    3800     455    3900     450
    4850     450    4950     456    5185     452    5250   457.3    5435     450
    5510     450    5560     456    5640     452    6290   452.6 7161.68     472
#Mann= 4 ,-1,0
    1290     .14       0    3220    .055       0    3400     .06       0
    5640     .05       0
#XS Ineff= 2 , 0
       0                    6080       0     480
Permanent Ineff=
       F       F
Bank Sta=3220,3400
XS Rating Curve= 0 ,0
Exp/Cntr=0.3,0.1

Type RM Length L Ch R = 1 ,85778   ,264,1252,793
BEGIN DESCRIPTION:
This cross section corresponds to cross section 85875 of the non-georeferenced CDC model which was the source of this model.
LOB from 2001 aerial topo.-realigned for hydraulics - ROB from COE section 86951.  CHANNEL BASED ON 1991 AND 2001 SURVEY DATA  SET COE NON-EFFECTIVE FLOW LIMIT AT FILL LINE IN ROB  Added 2001 survey information for flood plain
CDC GP041795-1 Riverside Development
Cross-section 85875 - 94400
Located in ROB.
END DESCRIPTION:
XS GIS Cut Line= 6
     2409015.986     6981692.937     2410437.861      6980526.27
     2410614.944     6980135.645     2410500.361     6979635.645
     2411872.557     6977613.7562412527.285983586976834.47057364
#Sta/Elev= 30
    1770     476    2080   468.4    2295     467    2410     457    2680     450
    3050   453.7    3060     453    3070     432    3080     432    3115     444
    3230     452    4115     455    4149     422    4181   421.3    4210     423
    4260   446.6    4320     454    4550     454    4877   448.1    4962   455.4
    5040   450.4    5590   449.8    5819     453    5851   448.9    6141   454.4
    6338     452    6845   452.6    6995     465 7819.67     460    8015     472
#Mann= 5 ,-1,0
    1770     .14       0    4115    .055       0    4320     .06       0
    6338     .05       0    6845     .06       0
#XS Ineff= 2 , 0
       0                    6690       0     480
Permanent Ineff=
       F       F
Bank Sta=4115,4320
XS Rating Curve= 0 ,0
Exp/Cntr=0.3,0.1

Type RM Length L Ch R = 1 ,84526   ,902,714,211
BEGIN DESCRIPTION:
This cross section corresponds to cross section 84548 of the non-georeferenced CDC model which was the source of this model.
Flow limit moved for SPF conditions.  GRs added from storage model.  Boyd Br added.
END DESCRIPTION:
XS GIS Cut Line= 6
     2408810.039     6982762.393     2409218.499     6981908.865
     2410395.959      6980754.75     2411259.658     6980322.901
     2412297.668     6977925.6072412347.992532436977025.01205531
#Sta/Elev= 30
       0   473.5      80   469.3     600     466     900   469.1     920     470
     980     494    1021   496.3    1035   482.6    1118   473.4    1363   464.1
    1436   457.3    1737     450    2360     453    2520     434    2560   451.7
    2573   452.4    2907     450    3015   453.5    3072   431.2    3085     422
    3120   421.5    3160   426.5    3163   431.2    3199   450.3    3432   454.5
    4275     450    4685   454.6    5580   450.2    5880   450.2    7075     472
#Mann= 5 ,-1,0
       0     .14       0    3015    .055       0    3199     .06       0
    5580    .045       0    5880     .06       0
#XS Ineff= 2 , 0
       0    1000     478    6015       0     490
Permanent Ineff=
       F       F
Bank Sta=3015,3199
XS Rating Curve= 0 ,0
Exp/Cntr=0.3,0.1

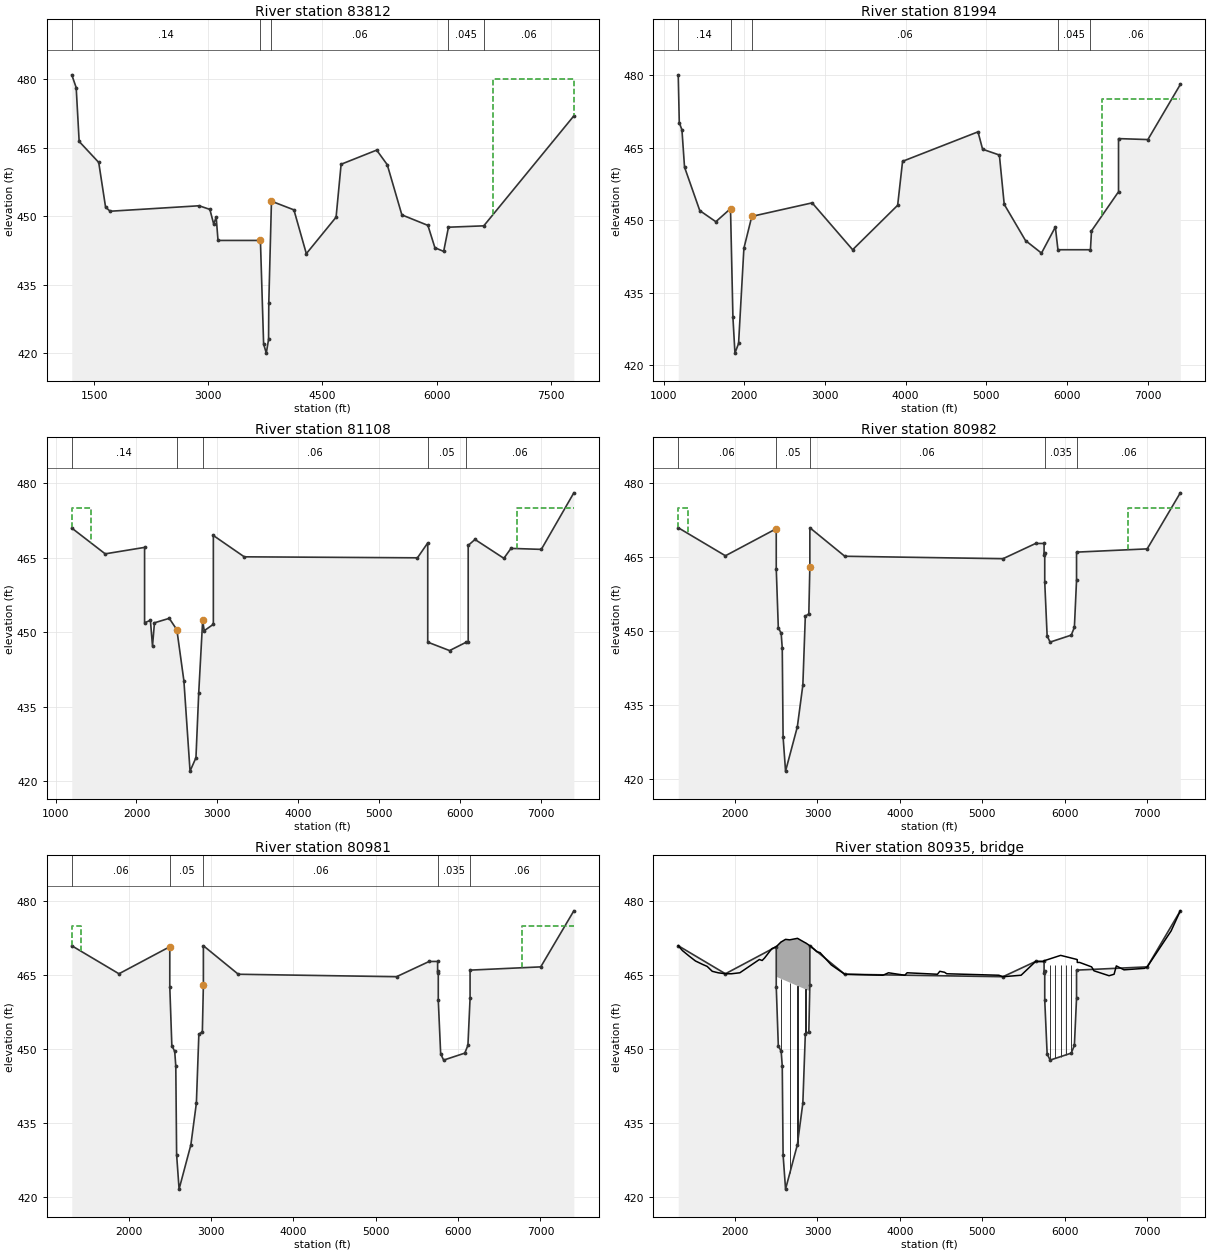
Type RM Length L Ch R = 1 ,83812   ,950,1818,200
BEGIN DESCRIPTION:
This cross section corresponds to cross section 83836 of the non-georeferenced CDC model which was the source of this model.
Flow limit moved for SPF conditions.  GRs added from storage model and 1991 topo.  Section modified for continuity.  See 100 yr model for modifications.
END DESCRIPTION:
XS GIS Cut Line= 6
     2409811.199     6982809.534     2411019.741     6980962.678
     2411547.557     6980802.734     2411878.949     6979696.036
     2412299.304     6977953.9412412366.388365966977067.47714849
#Sta/Elev= 30
    1207     481    1265   478.2    1304   466.4    1561   461.8    1651     452
    1711   451.1    2880   452.3    3021   451.5    3071   448.3    3104   449.8
    3128   444.7    3685   444.7    3727     422    3762     420    3792     423
    3795     431    3830   453.3    4125   451.4    4288   441.8    4679   449.8
    4745   461.4    5212   464.5    5351   461.3    5543   450.3    5885     448
    5977   443.1    6092   442.3    6155   447.6    6619   447.9    7802     472
#Mann= 5 ,-1,0
    1207     .14       0    3685    .055       0    3830     .06       0
    6155    .045       0    6619     .06       0
#XS Ineff= 2 , 0
       0                    6735       0     480
Permanent Ineff=
       F       F
Bank Sta=3685,3830
XS Rating Curve= 0 ,0
Exp/Cntr=0.5,0.3

Type RM Length L Ch R = 1 ,81994   ,309,886,399
BEGIN DESCRIPTION:
This cross section corresponds to cross section 82018 of the non-georeferenced CDC model which was the source of this model.
Flow limit moved for SPF conditions.  Data added to relief from CORPS data.  See 100 yr model for modifications.
END DESCRIPTION:
XS GIS Cut Line= 6
     2410800.738     6983123.357     2411243.663     6982242.231
     2411899.434     6981010.661     2412203.328     6979779.091
     2412351.956     6977334.862     2412358.376     6977209.727
#Sta/Elev= 30
    1182   480.1    1195   470.2    1228   468.7    1260     461    1449     452
    1648   449.7    1830   452.4    1860   429.9    1885   422.5    1930   424.5
    1996   444.2    2094   450.8    2842   453.6    3344   443.9    3902   453.1
    3963   462.2    4898   468.3    4955   464.7    5163   463.5    5223   453.3
    5487   445.8    5685   443.2    5857   448.6    5889   443.9    6292   443.9
    6305   447.8    6640   455.9    6640   466.9    7004   466.7    7406   478.1
#Mann= 5 ,-1,0
    1182     .14       0    1830    .055       0    2094     .06       0
    5889    .045       0    6292     .06       0
#XS Ineff= 2 , 0
       0                    6430       0     475
Permanent Ineff=
       F       F
Bank Sta=1830,2094
XS Rating Curve= 0 ,0
Exp/Cntr=0.5,0.3

Type RM Length L Ch R = 1 ,81108   ,126,126,126
BEGIN DESCRIPTION:
This cross section corresponds to cross section 81130 of the non-georeferenced CDC model which was the source of this model.
Left flow limit due to u/s high ground.  Right flow limit due to d/s high ground.  Data added to relief from CORPS data.  Cont/Exp raised due to influences from SH 360.  'n' value lowered to reflect irregular pavement section and short vegetation. CDC ARL062007-1 Viridian Project
Cross-section 81131 - 109405
Located in LOB.
END DESCRIPTION:
XS GIS Cut Line= 6
   2411057.64181 6983220.6152984 2412147.2449664 6981288.3380333
 2412527.5119224 6980100.0031396  2412618.258132  6979367.557098
 2412613.9359622 6978559.4901446 2412358.3597017 6977398.0984385
#Sta/Elev= 30
    1200     471    1613   465.8    2100   467.1    2100   451.9    2172   452.4
    2198   447.2    2222   451.9    2405   452.8    2499   450.5    2586   440.2
    2662     422    2735   424.7    2769   437.7    2818   452.4    2837   450.3
    2950   451.6    2950   469.5    3332   465.2    5473     465    5600     468
    5600     448    5870   446.3    6077     448    6100     448    6100   467.5
    6184   468.7    6541   464.9    6629   466.9    7004   466.7    7406   478.1
#Mann= 5 ,-1,0
    1200     .14       0    2499    .055       0    2818     .06       0
    5600     .05       0    6077     .06       0
#XS Ineff= 2 , 0
       0    1435     475    6700       0     475
Permanent Ineff=
       F       F
Bank Sta=2499,2818
XS Rating Curve= 0 ,0
Exp/Cntr=0.5,0.3

Type RM Length L Ch R = 1 ,80982   ,1,1,1
BEGIN DESCRIPTION:
This cross section corresponds to cross section 81004 of the non-georeferenced CDC model which was the source of this model.
Left flow limit due to u/s high ground.  Right flow limit due to d/s high ground.  'n' value lowered through relief bridge to reflect normal high grass and regular pavement section.  Relief bridge surveyed 10-06.
END DESCRIPTION:
XS GIS Cut Line= 6
  2411103.941935 6983383.1987873 2412126.6193515 6981607.3331302
 2412515.5283506 6980637.2202411 2412694.8593567 6979762.1740909
 2412738.0715407 6979055.6551627 2412514.6582736 6977680.4269421
#Sta/Elev= 30
    1310     471    1883   465.3    2500   470.8    2500   462.7    2525   450.7
    2560   449.5    2573   446.5    2583   428.5    2613   421.5    2756   430.5
    2823     439    2853     453  2895.5   453.5    2908     463    2908     471
    3332   465.2    5253   464.7    5649   467.8    5752   467.8    5752  465.51
    5760  465.88    5760  459.92    5789  449.02    5825  447.74    6082  449.16
    6120  450.76    6146  460.29    6146  466.04    7004   466.7    7406   478.1
#Mann= 5 ,-1,0
    1310     .06       0    2500     .05       0    2908     .06       0
    5760    .035       0    6146     .06       0
#XS Ineff= 2 , 0
       0    1425     475    6775       0     475
Permanent Ineff=
       F       F
Bank Sta=2500,2908
XS Rating Curve= 0 ,0
Exp/Cntr=0.5,0.3

Type RM Length L Ch R = 1 ,80981   ,90,90,90
BEGIN DESCRIPTION:
This cross section corresponds to cross section 81003 of the non-georeferenced CDC model which was the source of this model.
Left flow limit due to u/s high ground.  Right flow limit due to d/s high ground.  'n' value lowered through relief bridge to reflect normal high grass and regular pavement section.  Relief bridge surveyed 10-06.
END DESCRIPTION:
XS GIS Cut Line= 6
  2411108.350972 6983377.5437578 2412127.4631818 6981607.7986805
 2412517.0785443 6980635.8980652 2412696.7199173 6979759.3079549
 2412740.0065762 6979051.5711814 2412516.3026272 6977674.0076636
#Sta/Elev= 30
    1310     471    1883   465.3    2500   470.8    2500   462.7    2525   450.7
    2560   449.5    2573   446.5    2583   428.5    2613   421.5    2756   430.5
    2823     439    2853     453  2895.5   453.5    2908     463    2908     471
    3332   465.2    5253   464.7    5649   467.8    5752   467.8    5752  465.51
    5760  465.88    5760  459.92    5789  449.02    5825  447.74    6082  449.16
    6120  450.76    6146  460.29    6146  466.04    7004   466.7    7406   478.1
#Mann= 5 ,-1,0
    1310     .06       0    2500     .05       0    2908     .06       0
    5760    .035       0    6146     .06       0
#XS Ineff= 2 , 0
       0    1425     475    6775       0     475
Permanent Ineff=
       F       F
Bank Sta=2500,2908
XS Rating Curve= 0 ,0
Exp/Cntr=0.5,0.3

Type RM Length L Ch R = 3 ,80935   ,,,
BEGIN DESCRIPTION:
S.H. 360
Relief bridge superelevated.  D/S sided higher.  Relief bridge surveyed 10-06.
END DESCRIPTION:
Node Name=S.H. 360
Bridge Culvert--1,0,-1,-1, 0
Deck Dist Width WeirC Skew NumUp NumDn MinLoCord MaxHiCord MaxSubmerge Is_Ogee
1,88,2.6,0, 62, 62, , , 0.95, 0, ,,,
    1310    1362    1442    1519    1606    1661    1723    1795    1883    1956
    2058    2295    2329    2358    2446    2500    2500    2560  2562.5    2613
    2663    2756  2758.5    2853  2855.5    2908    2908    2952    2992    3032
    3168    3332    3796    3863    4061    4089    4457    4486    4544    4570
    5203    5253    5473    5649    5752    5752    5760    5953    6146    6155
    6155    6184    6329    6358    6541    6602    6629    6722    6970    7004
    7294    7406
     471     470   468.9   467.9   467.2   466.8   465.8   465.5   465.3   465.3
   465.5   468.2     468   468.5   470.4   470.8   470.8   471.8   471.8   472.3
   472.2   472.5   472.5   471.6   471.6     471     471   470.4   469.8   469.6
   467.1   465.2     465   465.5     465   465.5   465.2   465.8   465.6   465.3
     465   464.7     465   467.8   467.8  467.89  467.99  469.04  468.23  468.17
   467.6   467.6   466.7   465.9   464.9   465.2   466.9   466.1   466.4   466.7
     474   478.1
                                                   464.6     465   464.1   464.1
   464.1   464.1   464.1   464.1   465.1   464.7
                                                  461.75  462.86  461.93
    1310    1362    1442    1519    1606    1661    1723    1795    1883    1956
    2058    2295    2329    2358    2446    2500    2500    2560  2562.5    2613
    2663    2756  2758.5    2853  2855.5    2908    2908    2952    2992    3032
    3168    3332    3796    3863    4061    4089    4457    4486    4544    4570
    5203    5253    5473    5649    5751    5751    5760    5956    6153    6161
    6161    6184    6329    6358    6541    6602    6629    6722    6970    7004
    7294    7406
     471     470   468.9   467.9   467.2   466.8   465.8   465.5   465.3   465.3
   465.5   468.2     468   468.5   470.4   470.8   470.8   471.8   471.8   472.3
   472.2   472.5   472.5   471.6   471.6     471     471   470.4   469.8   469.6
   467.1   465.2     465   465.5     465   465.5   465.2   465.8   465.6   465.3
     465   464.7     465     468   468.9  470.78  470.89  472.11  470.89  470.79
     469   468.7   466.7   465.9   464.9   465.2   466.9   466.1   466.4   466.7
     474   478.1
                                                   464.6     465   464.1   464.1
   464.1   464.1   464.1   464.1   465.1   464.7
                                                  464.04  465.24  464.06
Pier Skew, UpSta & Num, DnSta & Num=  ,2561.25, 2 ,2561.25, 2 , 0 , 0 , 0 ,,
     2.5     2.5
     420     467
     2.5     2.5
     420     467
Pier Skew, UpSta & Num, DnSta & Num=  ,2664.25, 2 ,2664.25, 2 , 0 , 0 , 0 ,,
     2.5     2.5
     420     467
     2.5     2.5
     420     467
Pier Skew, UpSta & Num, DnSta & Num=  ,2758.25, 2 ,2758.25, 2 , 0 , 0 , 0 ,,
     2.5     2.5
     420     467
     2.5     2.5
     420     467
Pier Skew, UpSta & Num, DnSta & Num=  ,2854.25, 2 ,2854.25, 2 , 0 , 0 , 0 ,,
     2.5     2.5
     420     467
     2.5     2.5
     420     467
Pier Skew, UpSta & Num, DnSta & Num=  ,5825, 2 ,5825, 2 , 0 , 0 , 0 ,,
       3       3
     420     467
       3       3
     420     467
Pier Skew, UpSta & Num, DnSta & Num=  ,5889, 2 ,5891, 2 , 0 , 0 , 0 ,,
       3       3
     420     467
       3       3
     420     467
Pier Skew, UpSta & Num, DnSta & Num=  ,5953, 2 ,5956, 2 , 0 , 0 , 0 ,,
       3       3
     420     467
       3       3
     420     467
Pier Skew, UpSta & Num, DnSta & Num=  ,6017, 2 ,6022, 2 , 0 , 0 , 0 ,,
       3       3
     420     467
       3       3
     420     467
Pier Skew, UpSta & Num, DnSta & Num=  ,6082, 2 ,6087, 2 , 0 , 0 , 0 ,,
       3       3
     420     467
       3       3
     420     467
BR Coef= 1 , 0 , 0 ,1.05, 0 ,,,0.8,-1,0.5,1,
WSPro=,,,, 1 ,,,, 0 ,,,, 0 ,,,,-1 ,-1 ,-1 , 0 , 0 , 0 , 0 , 0
BC Design=,, 0 ,, 0 ,,,,,,
BC HTab HWMax=478.1
BC Use User HTab Curves=0
BC User HTab FreeFlow(D)= 0

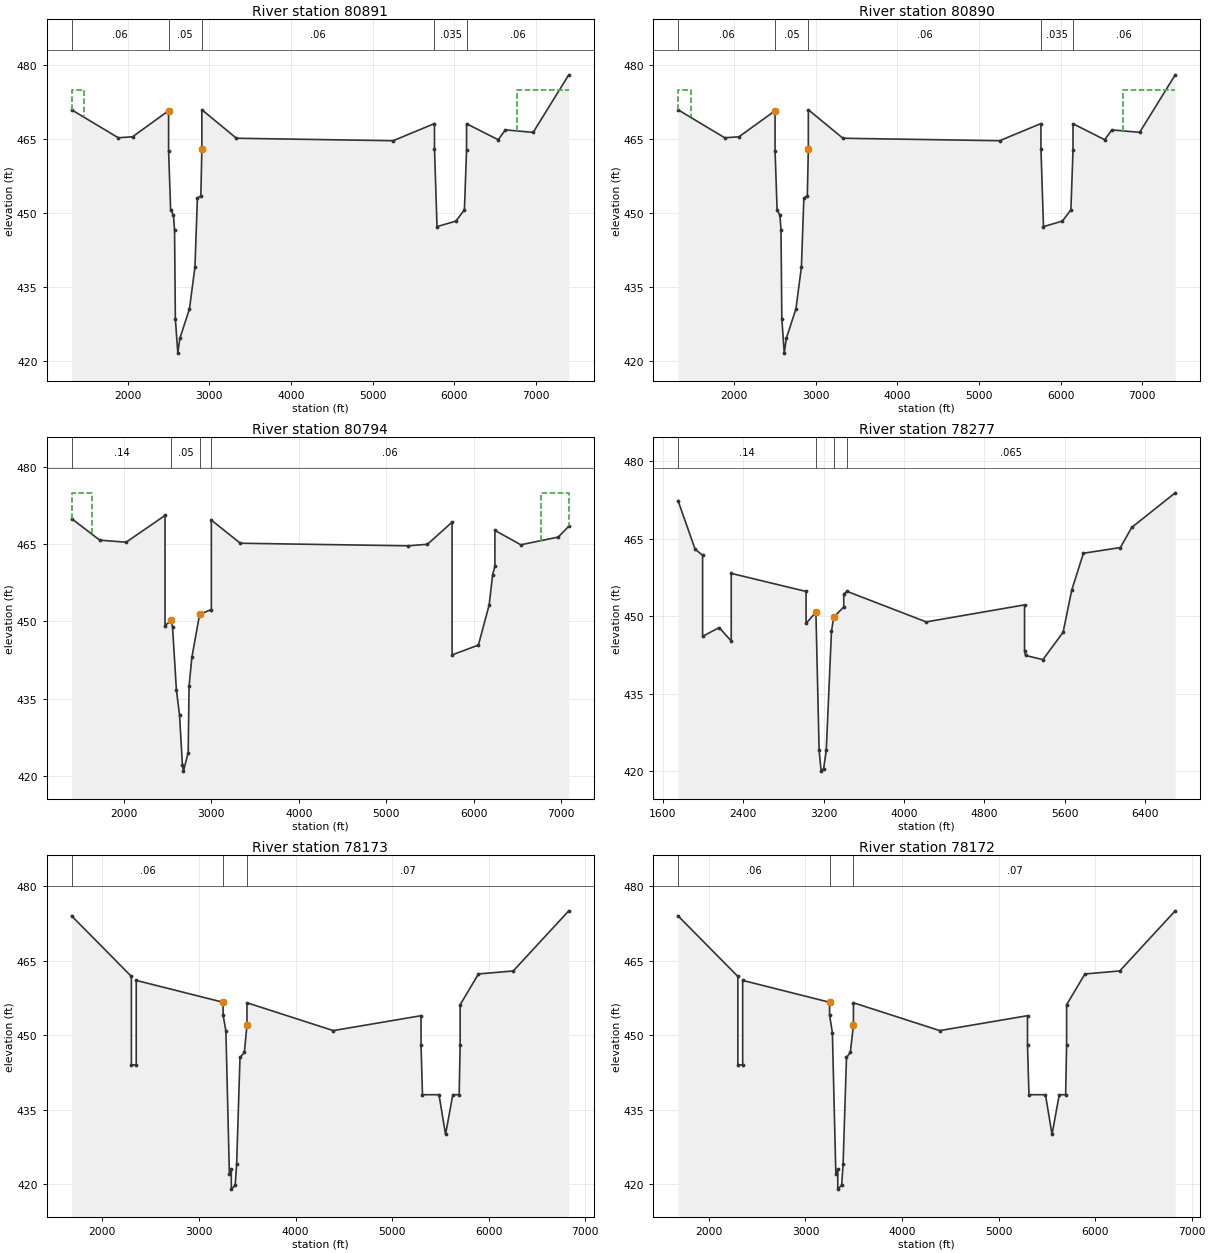
Type RM Length L Ch R = 1 ,80891   ,1,1,1
BEGIN DESCRIPTION:
This cross section corresponds to cross section 80913 of the non-georeferenced CDC model which was the source of this model.
Flow limits due to d/s high ground.  'n' value lowered through relief bridge to reflect normal high grass and regular pavement section.  Relief bridge surveyed 10-06.
END DESCRIPTION:
XS GIS Cut Line= 6
  2411231.377001 6983351.3869289 2412291.5563576 6981500.4291446
 2412481.2931828 6981067.0664942 2412686.2429042 6980409.0701068
 2412936.8290172 6978910.7876703 2412760.6915345 6977645.8100276
#Sta/Elev= 30
    1310     471    1883   465.3    2058   465.5    2500   470.8    2500   462.7
    2525   450.7    2560   449.5    2573   446.5    2583   428.5    2613   421.5
    2638   424.5    2756   430.5    2823     439    2853     453  2895.5   453.5
    2908     463    2908     471    3332   465.2    5253   464.7    5760  468.19
    5760  462.97    5791  447.23    6022  448.35    6127  450.63    6153  462.81
    6153  468.15    6541   464.9    6629   466.9    6970   466.4    7406   478.1
#Mann= 5 ,-1,0
    1310     .06       0    2500     .05       0    2908     .06       0
    5760    .035       0    6153     .06       0
#XS Ineff= 2 , 0
       0    1465     475    6770       0     475
Permanent Ineff=
       F       F
Bank Sta=2500,2908
XS Rating Curve= 0 ,0
Exp/Cntr=0.5,0.3

Type RM Length L Ch R = 1 ,80890   ,96,96,96
BEGIN DESCRIPTION:
This cross section corresponds to cross section 80912 of the non-georeferenced CDC model which was the source of this model.
Flow limits due to d/s high ground.  'n' value lowered through relief bridge to reflect normal high grass and regular pavement section.  Relief bridge surveyed 10-06.
END DESCRIPTION:
XS GIS Cut Line= 6
  2411234.004349 6983348.8685622 2412292.6410011 6981500.5239607
 2412482.7738229 6981066.2410366 2412688.0319426  6980407.255806
 2412938.9389211 6978907.3877427 2412763.3695778 6977642.9633245
#Sta/Elev= 30
    1310     471    1883   465.3    2058   465.5    2500   470.8    2500   462.7
    2525   450.7    2560   449.5    2573   446.5    2583   428.5    2613   421.5
    2638   424.5    2756   430.5    2823     439    2853     453  2895.5   453.5
    2908     463    2908     471    3332   465.2    5253   464.7    5760  468.19
    5760  462.97    5791  447.23    6022  448.35    6127  450.63    6153  462.81
    6153  468.15    6541   464.9    6629   466.9    6970   466.4    7406   478.1
#Mann= 5 ,-1,0
    1310     .06       0    2500     .05       0    2908     .06       0
    5760    .035       0    6153     .06       0
#XS Ineff= 2 , 0
       0    1465     475    6770       0     475
Permanent Ineff=
       F       F
Bank Sta=2500,2908
XS Rating Curve= 0 ,0
Exp/Cntr=0.5,0.3

Type RM Length L Ch R = 1 ,80794   ,2199,2516,280
BEGIN DESCRIPTION:
This cross section corresponds to cross section 80816 of the non-georeferenced CDC model which was the source of this model.
Flow limits due to d/s high ground.  Left 'n' value corrected from 0.014 to 0.14.  Data added to relief from CORPS data.
END DESCRIPTION:
XS GIS Cut Line= 6
  2411413.125112 6983226.9088134 2412369.7881565 6981554.0930792
 2412559.9209783 6981119.8101552  2412765.179098 6980460.8249246
 2413016.0860765 6978960.9568613 2412884.9808202 6977894.6029986
#Sta/Elev= 30
    1400     470    1723   465.8    2025   465.4    2470   470.6    2470   449.2
    2542   450.2    2556   448.9    2600   436.7    2636   431.8    2669   422.1
    2681   420.9    2735   424.5    2745   437.4    2777     443    2866   451.4
    3000   452.3    3000   469.7    3332   465.2    5253   464.7    5473     465
    5755   469.3    5755   443.5    6056   445.4    6179   453.2    6219   459.1
    6245   460.7    6245   467.7    6541   464.9    6970   466.4    7090   468.5
#Mann= 4 ,-1,0
    1400     .14       0    2542     .05       0    2866     .09       0
    3000     .06       0
#XS Ineff= 2 , 0
       0    1635     475    6770       0     475
Permanent Ineff=
       F       F
Bank Sta=2542,2866
XS Rating Curve= 0 ,0
Exp/Cntr=0.5,0.3

Type RM Length L Ch R = 1 ,78277   ,105,105,105
BEGIN DESCRIPTION:
This cross section corresponds to cross section 78299 of the non-georeferenced CDC model which was the source of this model.
Railroad lowered 2' below rails.  Left 'n' value corrected from 0.014 to 0.14.  Data added to LOB from CORPS data.  'n' value changed in ROB  to transition from RR to 360 'n' value.
END DESCRIPTION:
XS GIS Cut Line= 6
  2413768.241068 6982706.7886085 2413632.3000672 6982032.7138412
 2413467.6439004 6981491.1801473 2413211.5141633 6980832.5590892
    2413171.2649 6980605.6999629  2413268.339753 6977849.5186728
#Sta/Elev= 30
    1750   472.4    1920     463    1995   461.8    1995   446.1    2160   447.8
    2280   445.2    2280   458.3    3025   454.8    3025   448.6    3123   450.8
    3155     424    3175     420    3200   420.5    3226     424    3278   447.1
    3300   449.8    3400   451.8    3400   454.3    3435   454.8    4221   448.9
    5200   452.2    5200   443.3    5210   442.4    5383   441.6    5584   446.9
    5669     455    5786   462.2    6154   463.3    6267   467.2    6700   473.9
#Mann= 4 ,-1,0
    1750     .14       0    3123     .05       0    3300     .09       0
    3435    .065       0
Bank Sta=3123,3300
XS Rating Curve= 0 ,0
Exp/Cntr=0.5,0.3

Type RM Length L Ch R = 1 ,78173   ,1,1,1
BEGIN DESCRIPTION:
This cross section corresponds to cross section 78195 of the non-georeferenced CDC model which was the source of this model.
Far LOB extended with 1991 topo.  High ground from u/s added to ROB.  'n' value raised in ROB  to be consistent.
END DESCRIPTION:
XS GIS Cut Line= 6
  2413884.730336  6982892.148474 2413790.3046724 6982468.5171034
 2413734.5738128 6982000.4803098 2413346.8859398 6980892.4546387
 2413272.9149592 6980463.4548406 2413387.0961613 6977837.8193438
#Sta/Elev= 30
    1680     474    2300   461.8    2300     444    2350     444    2350     461
    3250   456.6    3250     454    3279   450.8    3315     422    3335     423
    3335     419    3375   419.8    3390     424    3425   445.5    3470   446.5
    3497     452    3497   456.5    4391   450.9    5300   453.9    5300     448
    5315     438    5486     438    5554     430    5629     438    5695     438
    5705     448    5705   456.1    5895   462.3    6255   462.9    6830     475
#Mann= 3 ,0,0
    1680     .06       0    3250     .05       0    3497     .07       0
Bank Sta=3250,3497
XS Rating Curve= 0 ,0
Exp/Cntr=0.5,0.3

Type RM Length L Ch R = 1 ,78172   ,10,10,10
BEGIN DESCRIPTION:
This cross section corresponds to cross section 78194 of the non-georeferenced CDC model which was the source of this model.
Far LOB extended with 1991 topo.  High ground from u/s added to ROB.  'n' value raised in ROB  to be consistent.
END DESCRIPTION:
XS GIS Cut Line= 6
  2413885.692276 6982891.6369921 2413791.4414812  6982468.980029
 2413735.6144931 6982000.5170552 2413347.9069352 6980892.4146126
 2413274.0288021 6980463.9505745 2413388.2470776 6977837.5526121
#Sta/Elev= 30
    1680     474    2300   461.8    2300     444    2350     444    2350     461
    3250   456.6    3250     454    3279   450.5    3315     422    3335     423
    3335     419    3375   419.8    3390     424    3425   445.5    3465   446.5
    3497     452    3497   456.5    4391   450.9    5300   453.9    5300     448
    5315     438    5486     438    5554     430    5629     438    5695     438
    5705     448    5705   456.1    5895   462.3    6255   462.9    6830     475
#Mann= 3 ,0,0
    1680     .06       0    3250     .05       0    3497     .07       0
Bank Sta=3250,3497
XS Rating Curve= 0 ,0
Exp/Cntr=0.5,0.3