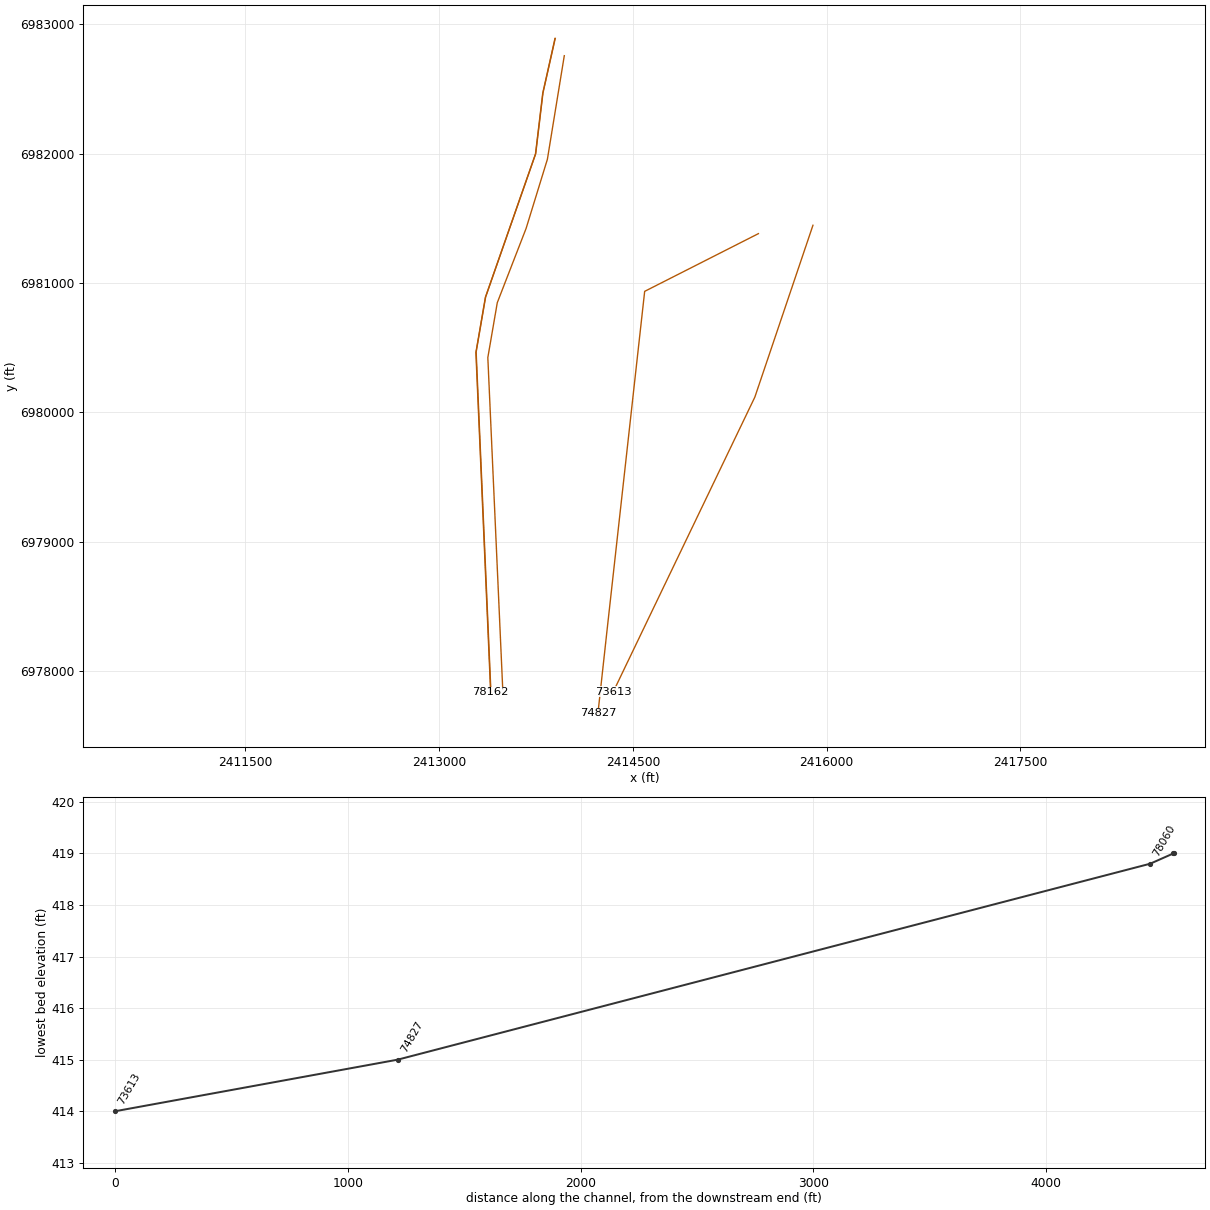
HEC-RAS study CDC_Consolidated_Model.prj: Upper Trinity CDC Consolidated Model

--- CDC_Consolidated_Model.g02 (geometry) --- (continued)

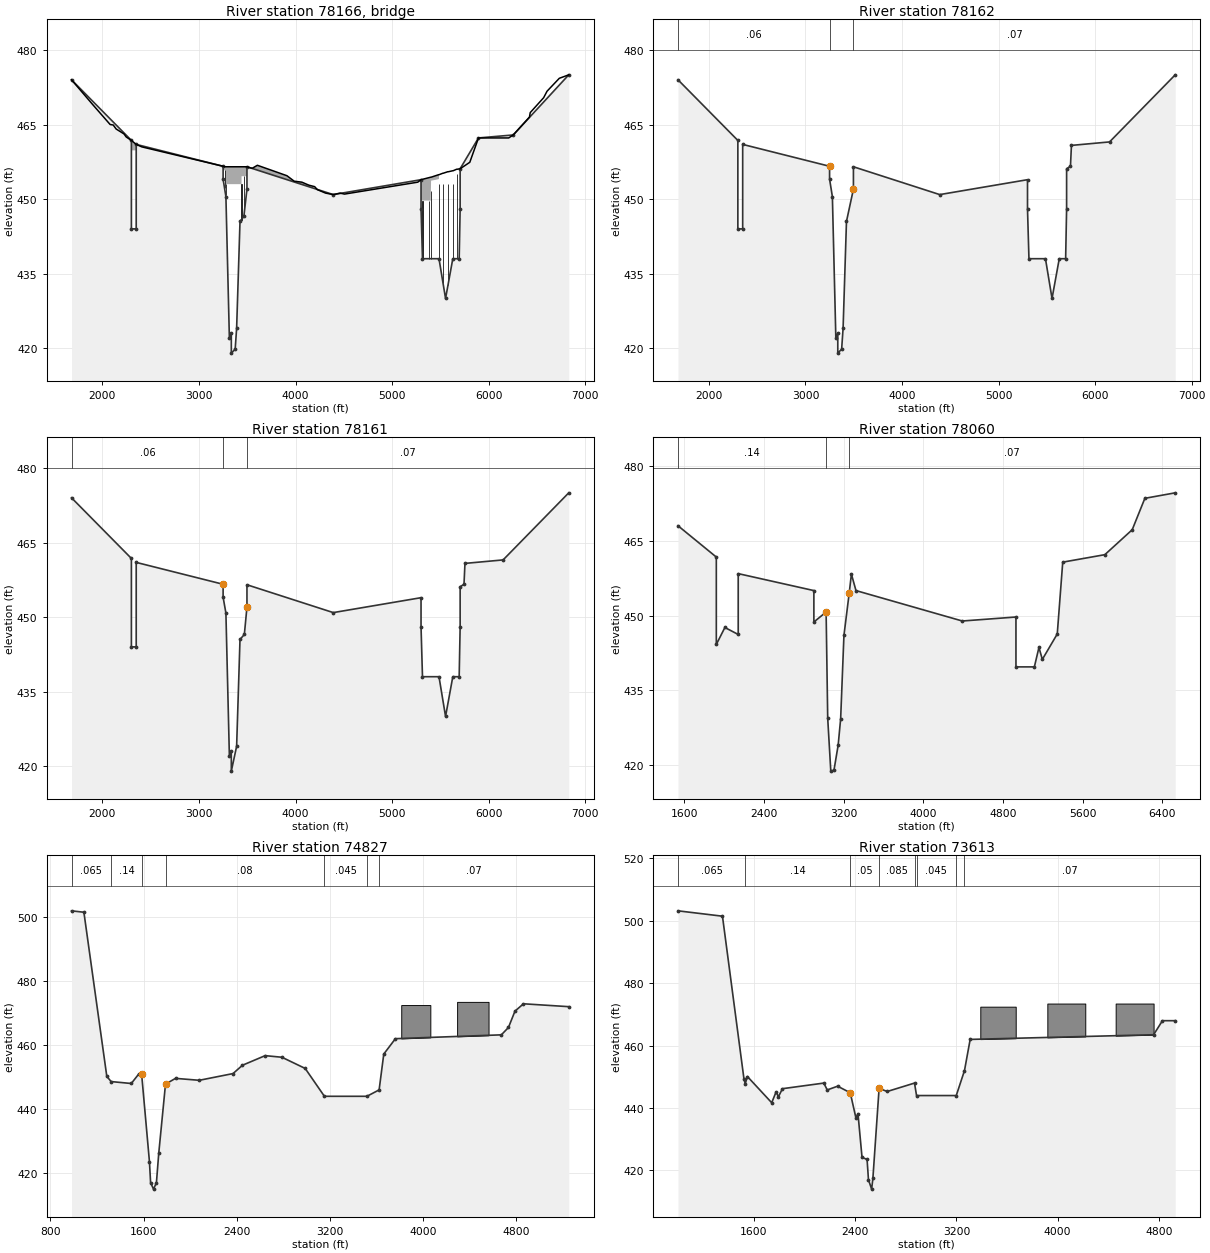
Type RM Length L Ch R = 3 ,78166   ,,,
BEGIN DESCRIPTION:
Union Pacific Railroad
END DESCRIPTION:
Node Name=Union Pacific Ra
Bridge Culvert--1,0,-1,-1, 0
Deck Dist Width WeirC Skew NumUp NumDn MinLoCord MaxHiCord MaxSubmerge Is_Ogee
1,8,2.6,0, 68, 73, , , 0.95, 0, 0,0,,
    1680    1900    2080    2112    2142    2224    2246    2300    2300    2350
    2350    2408    3250    3250    3265    3266    3275    3275    3279    3437
    3441    3441    3465    3470    3497    3497    3529    3552    3605    3911
    3986    4066    4138    4198    4226    4311    4391    4462    4507    5266
    5300    5300    5400    5404    5482    5482    5486    5526    5530    5577
    5583    5629    5633    5633    5668    5673    5705    5705    5805    5895
    6208    6255    6423    6431    6570    6605    6732    6830
     474     469     465   464.9   464.1   463.1   462.5   461.8   461.8     461
     461   460.5   456.6   456.6   456.5   456.5   456.5   456.5   456.5   456.5
   456.5   456.5   456.5   456.5   456.5   456.5   456.3   456.2   456.8   454.7
   453.6   453.4   452.8   452.5   451.9   451.2   450.9   451.2     451   453.4
   453.9   453.9   454.4   454.4   454.9   454.9   454.9   455.2   455.2   455.5
   455.5   455.7   455.7   455.7     456     456   456.1   456.1   457.4   462.3
   462.3   462.9   466.5   467.4   470.4   471.7   474.3     475
                                                                   459.8   459.8
                           455.8   455.8   455.8   455.8     453     453     453
     453   454.6   454.6   454.6   454.6
           452.5   452.5   452.5   452.5   448.9   448.9   449.2   449.2   449.5
   449.5   449.7   449.7   453.7     454     454   454.1
    1680    1900    2080    2112    2142    2224    2246    2300    2300    2350
    2350    2408    3250    3250    3265    3266    3275    3275    3279    3437
    3441    3441    3465    3470    3497    3497    3529    3552    3605    3911
    3986    4066    4138    4198    4226    4311    4391    4462    4507    5266
    5300    5300    5400    5404    5482    5482    5486    5526    5530    5577
    5583    5629    5633    5633    5668    5673    5705    5705    5745    5755
    5770    5900    5960    6010    6100    6150    6255    6423    6431    6570
    6605    6732    6830
     474     469     465   464.9   464.1   463.1   462.5   461.8   461.8     461
     461   460.5   456.6   456.6   456.5   456.5   456.5   456.5   456.5   456.5
   456.5   456.5   456.5   456.5   456.5   456.5   456.3   456.2   456.8   454.7
   453.6   453.4   452.8   452.5   451.9   451.2   450.9   451.2     451   453.4
   453.9   453.9   454.4   454.4   454.9   454.9   454.9   455.2   455.2   455.5
   455.5   455.7   455.7   455.7     456     456   456.1   456.1   456.6   460.8
     461     461     462     462   461.5   461.5   462.9   466.5   467.4   470.4
   471.7   474.3     475
                                                                   459.8   459.8
                           455.8   455.8   455.8   455.8     453     453     453
     453   454.6   454.6   454.6   454.6
           452.5   452.5   452.5   452.5   448.9   448.9   449.2   449.2   449.5
   449.5   449.7   449.7   453.7     454     454   454.1
Pier Skew, UpSta & Num, DnSta & Num=  ,3265.5, 2 ,3265.5, 2 , 0 , 0 , 0 ,,
       1       1
     450     456
       1       1
     450     456
Pier Skew, UpSta & Num, DnSta & Num=  ,3277, 2 ,3277, 2 , 0 , 0 , 0 ,,
       4       4
     450     456
       4       4
     450     456
Pier Skew, UpSta & Num, DnSta & Num=  ,3439, 2 ,3439, 2 , 0 , 0 , 0 ,,
       4       4
     450     456
       4       4
     450     456
Pier Skew, UpSta & Num, DnSta & Num=  ,3467.5, 2 ,3467.5, 2 , 0 , 0 , 0 ,,
       5       5
     450     456
       5       5
     450     456
Pier Skew, UpSta & Num, DnSta & Num=  ,5317, 2 ,5317, 2 , 0 , 0 , 0 ,,
       4       4
     430     453
       4       4
     430     453
Pier Skew, UpSta & Num, DnSta & Num=  ,5382, 2 ,5382, 2 , 0 , 0 , 0 ,,
       4       4
     430     453
       4       4
     430     453
Pier Skew, UpSta & Num, DnSta & Num=  ,5402, 2 ,5402, 2 , 0 , 0 , 0 ,,
       4       4
     430     453
       4       4
     430     453
Pier Skew, UpSta & Num, DnSta & Num=  ,5484, 2 ,5484, 2 , 0 , 0 , 0 ,,
       4       4
     430     453
       4       4
     430     453
Pier Skew, UpSta & Num, DnSta & Num=  ,5528, 2 ,5528, 2 , 0 , 0 , 0 ,,
       4       4
     430     453
       4       4
     430     453
Pier Skew, UpSta & Num, DnSta & Num=  ,5579, 2 ,5579, 2 , 0 , 0 , 0 ,,
       4       4
     430     453
       4       4
     430     453
Pier Skew, UpSta & Num, DnSta & Num=  ,5631, 2 ,5631, 2 , 0 , 0 , 0 ,,
       4       4
     430     453
       4       4
     430     453
Pier Skew, UpSta & Num, DnSta & Num=  ,5670.5, 2 ,5670.5, 2 , 0 , 0 , 0 ,,
       4       4
     430     455
       4       4
     430     455
BR Coef=-1 , 0 , 0 ,, 0 ,,,0.8,-1,,1,
WSPro=,,,, 1 ,,,, 0 ,,,, 0 ,,,,-1 ,-1 ,-1 , 0 , 0 , 0 , 0 , 0
BC Design=,, 0 ,, 0 ,,,,,,
BC HTab HWMax=475
BC Use User HTab Curves=0
BC User HTab FreeFlow(D)= 0

Type RM Length L Ch R = 1 ,78162   ,1,1,1
BEGIN DESCRIPTION:
This cross section corresponds to cross section 78184 of the non-georeferenced CDC model which was the source of this model.
Far LOB extended with 1991 topo.  Cont/Exp raised due to railroad.   High ground from d/s added to ROB.  'n' value raised in ROB  to be consistent.
END DESCRIPTION:
XS GIS Cut Line= 6
  2413895.712598 6982889.0162624 2413801.1278135 6982466.7277369
 2413745.0603403 6981997.1998046  2413357.303898 6980888.9047771
  2413283.658376 6980461.7806313 2413398.0075567 6977832.6179107
#Sta/Elev= 30
    1680     474    2300   461.8    2300     444    2350     444    2350     461
    3250   456.6    3250     454    3279   450.5    3315     422    3335     423
    3335     419    3375   419.8    3390     424    3425   445.5    3497     452
    3497   456.5    4391   450.9    5300   453.9    5300     448    5315     438
    5486     438    5554     430    5629     438    5695     438    5705     448
    5705   456.1    5745   456.6    5755   460.8    6150   461.5    6830     475
#Mann= 3 ,0,0
    1680     .06       0    3250     .05       0    3497     .07       0
Bank Sta=3250,3497
XS Rating Curve= 0 ,0
Exp/Cntr=0.5,0.3

Type RM Length L Ch R = 1 ,78161   ,100,100,100
BEGIN DESCRIPTION:
This cross section corresponds to cross section 78183 of the non-georeferenced CDC model which was the source of this model.
LOB 'n' value lowered to 0.06.  Far LOB extended with 1991 topo.  Cont/Exp raised due to railroad.   High ground from d/s added to ROB.
END DESCRIPTION:
XS GIS Cut Line= 6
    2413898.2267 6982891.6724251 2413803.3873234  6982470.609947
 2413746.8392082 6981998.9511134 2413358.9843408 6980890.2719003
 2413285.8043691 6980465.8268831 2413400.2562399 6977834.6457937
#Sta/Elev= 30
    1680     474    2300   461.8    2300     444    2350     444    2350     461
    3250   456.6    3250     454    3279   450.8    3315     422    3335     423
    3335     419    3390     424    3425   445.5    3470   446.5    3497     452
    3497   456.5    4391   450.9    5300   453.9    5300     448    5315     438
    5486     438    5554     430    5629     438    5695     438    5705     448
    5705   456.1    5745   456.6    5755   460.8    6150   461.5    6830     475
#Mann= 3 ,0,0
    1680     .06       0    3250     .05       0    3497     .07       0
Bank Sta=3250,3497
XS Rating Curve= 0 ,0
Exp/Cntr=0.5,0.3

Type RM Length L Ch R = 1 ,78060   ,1773,3234,942
BEGIN DESCRIPTION:
This cross section corresponds to cross section 78083 of the non-georeferenced CDC model which was the source of this model.
Flow limit due to railroad.  Railroad lowered 2' below rails.  Cont/Exp raised due to railroad.  'n' value lowered in ROB  to be consistent.
---------------------------------------------------------------------
CDC ARL071405-1 SVC Park Highlands, LTD.
In ROB beyond eff. flow line - storage mitigation area d/s SH 360 d/s cross-sect 78083.
----------------------------------------
END DESCRIPTION:
XS GIS Cut Line= 6
  2413968.174395 6982757.5342419 2413837.2038568 6981955.8740998
 2413672.5490024 6981421.6589609 2413449.3489895 6980847.1948867
 2413376.1690177 6980422.74986952413491.596804136977856.21586878
#Sta/Elev= 30
    1535     468    1920  461.72    1920   444.2    2006   447.6    2140   446.2
    2140   458.4    2900     455    2900   448.7    3023   450.7    3039   429.4
    3070   418.8    3102     419    3144     424    3169   429.3    3202     446
    3255   454.5    3277   458.3    3323     455    4391   448.9    4930   449.7
    4930   439.7    5115   439.7    5161   443.6    5195   441.2    5345   446.3
    5400   460.7    5823   462.2    6098   467.2    6225   473.5    6530   474.6
#Mann= 3 ,0,0
    1535     .14       0    3023     .05       0    3255     .07       0
Bank Sta=3023,3255
XS Rating Curve= 0 ,0
Exp/Cntr=0.5,0.3

Type RM Length L Ch R = 1 ,74827   ,869,1214,1352
BEGIN DESCRIPTION:
This cross section corresponds to cross section 74891 of the non-georeferenced CDC model which was the source of this model.
END DESCRIPTION:
XS GIS Cut Line= 6
  2415471.004723 6981381.1974277 2414978.3492123 6981131.3980585
 2414590.3768912 6980934.6858535 2414446.0609068 6979635.9505901
 2414301.7314711 6978337.2163109 2414228.4960533 6977670.7035363
#Sta/Elev= 30
 980.741501.94171086.999   501.51283.878450.2066    1321   448.6    1494     448
    1557   450.9    1583   450.9    1650   423.6    1660     417    1685     415
    1710     417    1730   426.2    1788   447.8    1874   449.6    2078     449
    2368   451.1    2449   453.7    2644   456.7    2788   456.2    2988   452.7
    3153     444    3518     444    3623     446    3663   457.2    3763     462
    4673   463.2    4734   465.5    4790   470.6    4863   472.9    5252     472
#Mann= 7 ,-1,0
 980.741    .065       0    1321     .14       0    1583    .055       0
    1788     .08       0    3153    .045       0    3518     .08       0
    3623     .07       0
#Block Obstruct= 2 ,-1
    3813    4063   472.5    4293    4563   473.5
Bank Sta=1583,1788
XS Rating Curve= 0 ,0
Exp/Cntr=0.3,0.1

Type RM Length L Ch R = 1 ,73613   ,332,332,332
BEGIN DESCRIPTION:
This cross section corresponds to cross section 73634 of the non-georeferenced CDC model which was the source of this model.
END DESCRIPTION:
XS GIS Cut Line= 6
  2415893.225007 6981445.9968387 2415683.3592852 6980825.8635646
 2415443.5021534 6980117.1418849 2414906.6088702 6979000.7527135
 2414617.4969157 6978399.6239945 2414347.8555254 6977839.0005659
#Sta/Elev= 30
  999.19503.22311350.739   501.51520.912 449.257    1531   447.8    1548   450.1
    1740   441.7    1775   445.2    1793   443.6    1825   446.2    2152     448
    2179   445.8    2261     447    2361   444.9    2406   436.8    2422   438.2
    2454   424.2    2494   423.5    2505     417    2530     414    2540   417.5
    2589   446.3    2653   445.3    2869     448    2885     444    3199     444
    3264     452    3309     462    4759   463.5    4829     468    4930     468
#Mann= 8 ,-1,0
  999.19    .065       0    1531     .14       0    2361     .05       0
    2589    .085       0    2869     .08       0    2885    .045       0
    3199     .08       0    3264     .07       0
#Block Obstruct= 3 ,-1
    3389    3669   472.5    3919    4219   473.5    4459    4759   473.5
Bank Sta=2361,2589
XS Rating Curve= 0 ,0
Exp/Cntr=0.3,0.1