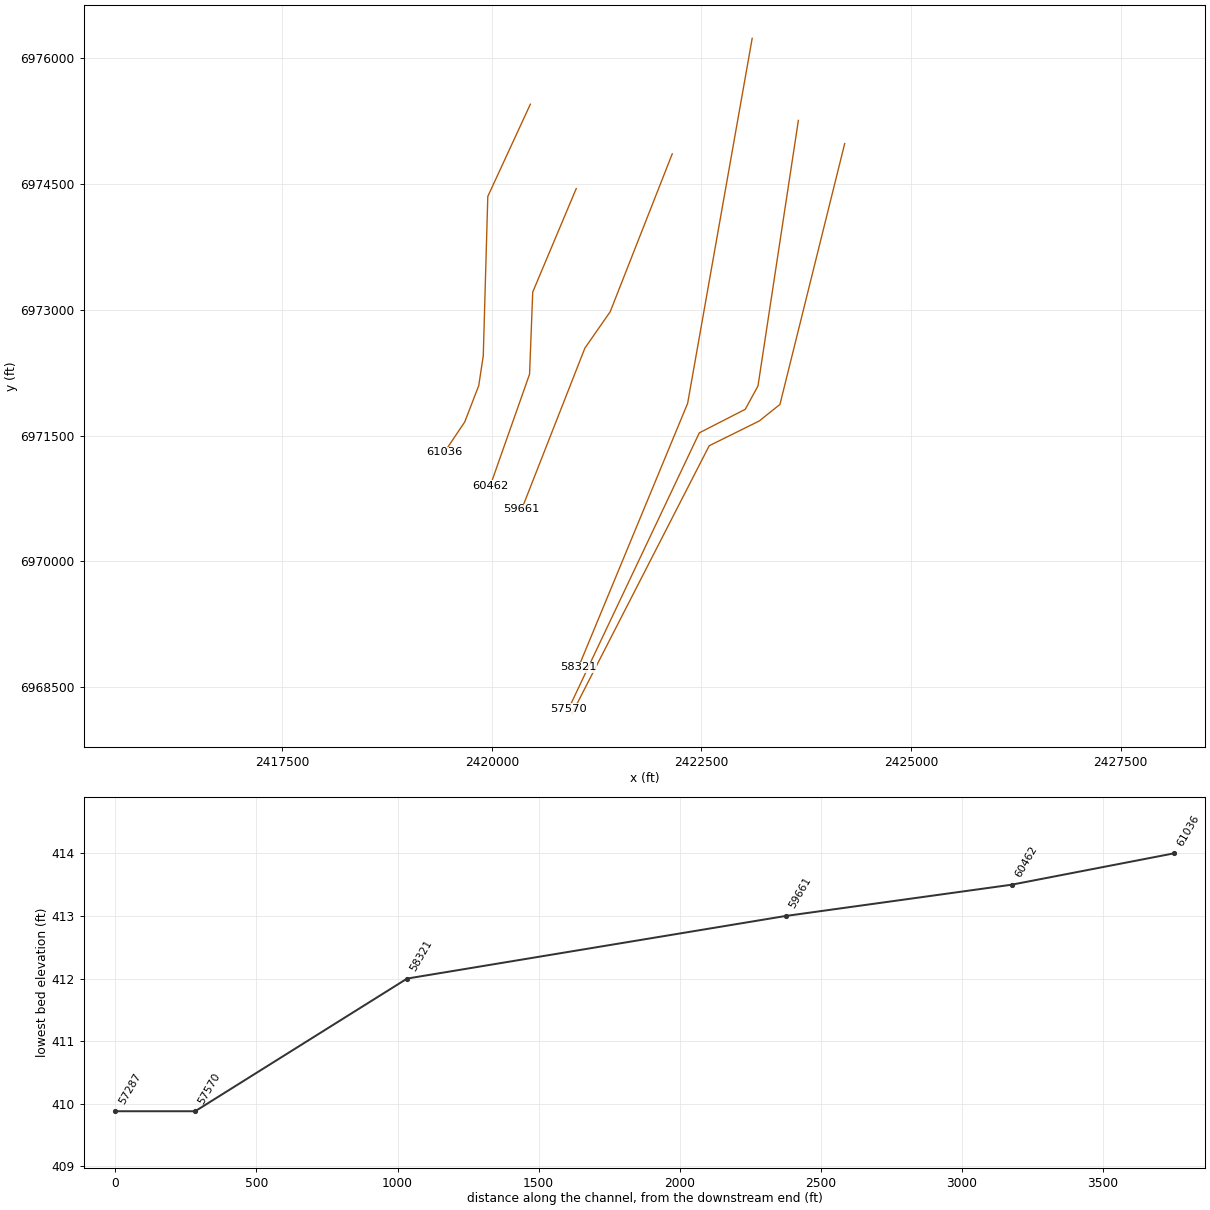
HEC-RAS study CDC_Consolidated_Model.prj: Upper Trinity CDC Consolidated Model

--- CDC_Consolidated_Model.g02 (geometry) --- (continued)

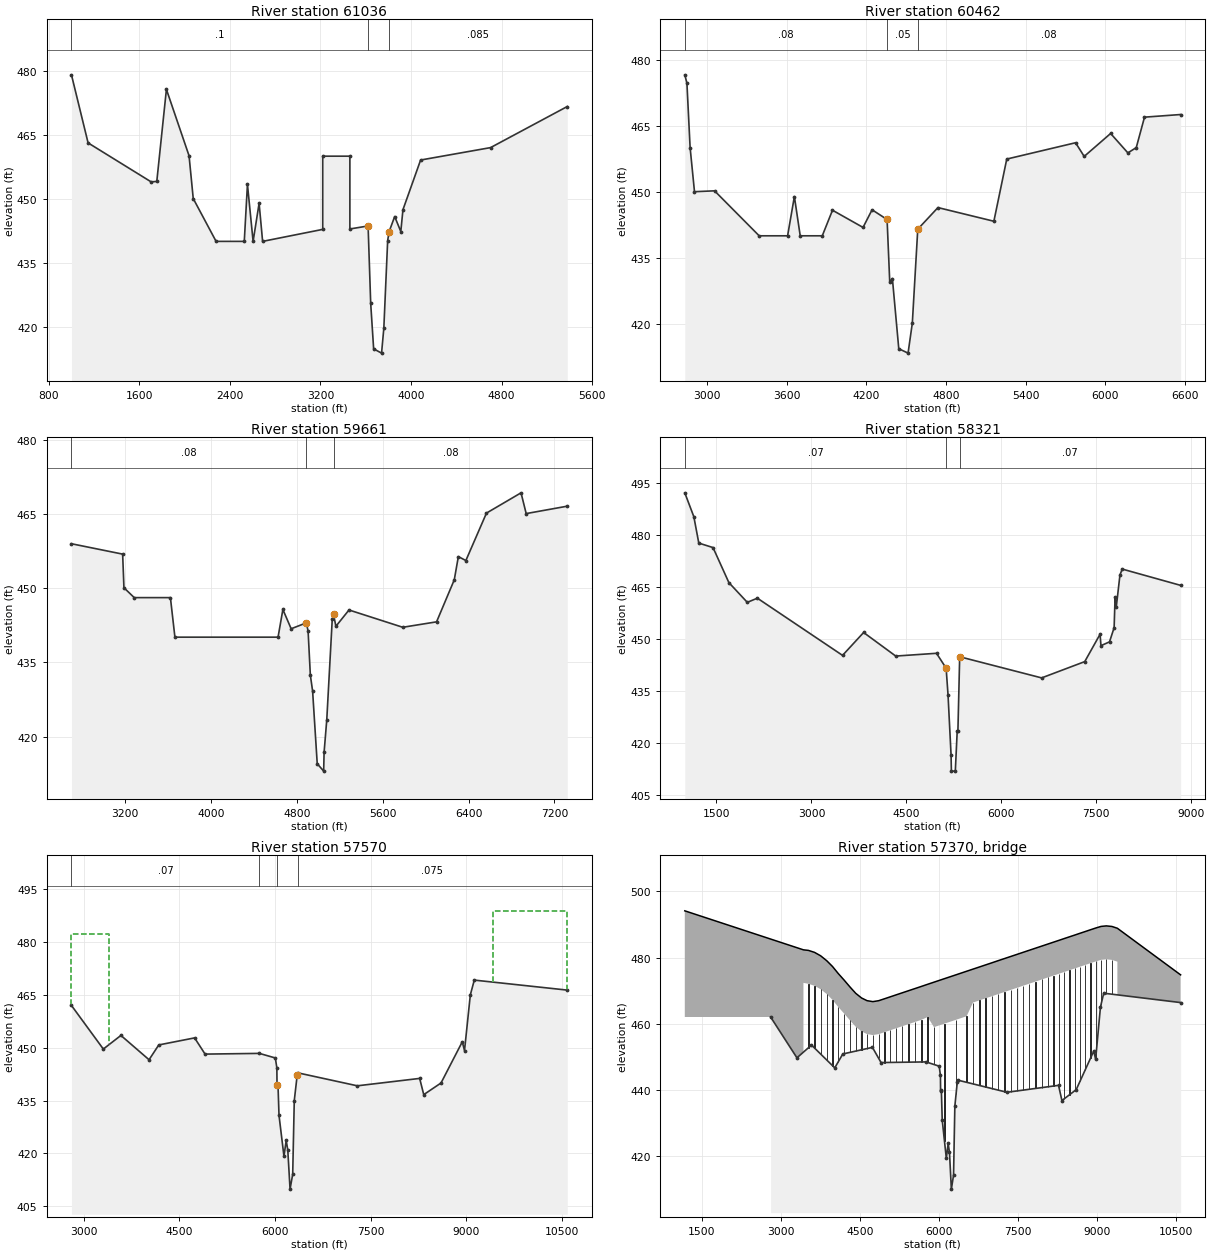
Type RM Length L Ch R = 1 ,61036   ,851,574,550
BEGIN DESCRIPTION:
This cross section corresponds to cross section 61054 of the non-georeferenced CDC model which was the source of this model.
END DESCRIPTION:
XS GIS Cut Line= 6
     2420460.066     6975453.575     2419952.594     6974352.991
     2419898.504     6972450.827     2419844.414     6972094.735
     2419677.637     6971662.016     2419433.446     6971298.123
#Sta/Elev= 30
    1000     479    1147   463.1    1704     454    1754   454.1    1839   475.6
    2039   460.1    2076   450.1    2278   440.1    2527   440.1    2555   453.4
    2605   440.1    2658     449    2689   440.1    3220   442.9    3220     460
    3460     460    3460     443    3621   443.7    3644   425.6    3670     415
    3740     414    3760   419.8    3794   440.3    3807   442.4    3856   445.9
    3910   442.4    3929   447.5    4085   459.1    4703     462    5381   471.6
#Mann= 3 ,0,0
    1000      .1       0    3621     .05       0    3807    .085       0
Bank Sta=3621,3807
XS Rating Curve= 0 ,0
Exp/Cntr=0.3,0.1

Type RM Length L Ch R = 1 ,60462   ,951,801,550
BEGIN DESCRIPTION:
This cross section corresponds to cross section 60480 of the non-georeferenced CDC model which was the source of this model.
END DESCRIPTION:
XS GIS Cut Line= 6
  2421007.528312 6974447.4330934  2420749.167067  6973832.761081
 2420488.2978381 6973212.1491332 2420450.6020473 6972232.0470908
  2420200.416196 6971521.6413594 2419981.4940617 6970900.0379438
#Sta/Elev= 30
    2834   476.6    2850   474.7    2874   460.1    2907   450.1    3058   450.3
    3394   440.1    3608   440.1    3659     449    3703   440.1    3869   440.1
    3946   445.9    4176     442    4244     446    4357   443.8    4377   429.6
    4397   430.4    4445   414.5    4515   413.5    4547   420.3    4588   441.6
    4740   446.5    5161   443.4    5258   457.5    5776   461.2    5841   458.1
    6040   463.3    6170   458.9    6233   460.1    6295     467    6567   467.6
#Mann= 3 ,0,0
    2834     .08       0    4357     .05       0    4588     .08       0
Bank Sta=4357,4588
XS Rating Curve= 0 ,0
Exp/Cntr=0.3,0.1

Type RM Length L Ch R = 1 ,59661   ,948,1341,1597
BEGIN DESCRIPTION:
This cross section corresponds to cross section 59680 of the non-georeferenced CDC model which was the source of this model.
END DESCRIPTION:
XS GIS Cut Line= 6
  2422152.102599 6974861.3943193  2421770.165025  6973888.859394
 2421411.8550461 6972976.5478984 2421110.2860954 6972543.0408914
 2420767.5013479 6971668.2998587 2420356.1340604 6970618.6159345
#Sta/Elev= 30
    2700     459    3177   456.9    3189   450.1    3285   448.1    3622   448.1
    3664   440.1    4625   440.1    4670   445.7    4747   441.8    4889     443
    4905   441.3    4926   432.4    4947   429.2    4990   414.5    5050     413
    5054   416.8    5079   423.4    5130   443.7    5142   444.7    5164   442.3
    5286   445.6    5787   442.1    6102   443.2    6267   451.7    6305   456.4
    6375   455.6    6567   465.2    6889   469.3    6937   465.1    7320   466.6
#Mann= 3 ,0,0
    2700     .08       0    4889     .05       0    5142     .08       0
Bank Sta=4889,5142
XS Rating Curve= 0 ,0
Exp/Cntr=0.3,0.1

Type RM Length L Ch R = 1 ,58321   ,714,751,739
BEGIN DESCRIPTION:
This cross section corresponds to cross section 58337 of the non-georeferenced CDC model which was the source of this model.
END DESCRIPTION:
XS GIS Cut Line= 6
  2423105.205005 6976239.6250337 2422745.9967347 6974206.6970129
 2422335.4129103 6971883.3568433 2421702.9167999 6970353.5770945
 2421368.0408292 6969543.6991211 2421033.8755708 6968735.5843649
#Sta/Elev= 30
    1000   492.3    1143   485.4    1221   477.8    1446   476.5    1696   466.4
    1987   460.7    2146   461.9    3491   445.4    3824     452    4331   445.2
    4975     446    5127   441.7    5157     434    5205   416.6    5210     412
    5272     412    5302   423.6    5313   423.6    5341     445    6635   438.9
    7316   443.6    7558   451.5    7572   448.2    7707   449.3    7780   453.4
    7795   462.2    7814   459.4    7872   468.6    7908   470.3    8830   465.6
#Mann= 3 ,0,0
    1000     .07       0    5127     .05       0    5341     .07       0
Bank Sta=5127,5341
XS Rating Curve= 0 ,0
Exp/Cntr=0.3,0.1

Type RM Length L Ch R = 1 ,57570   ,354,283,357
BEGIN DESCRIPTION:
This cross section corresponds to cross section 57586 of the non-georeferenced CDC model which was the source of this model.
Upstream bounding cross-section.
Section data is generated through the TXdot's topo file.
END DESCRIPTION:
XS GIS Cut Line= 6
  2423656.005741 6975259.9862449 2423174.4397755  6972091.859051
 2423098.6620399 6971952.4134637 2423022.8846324 6971812.9675484
 2422474.5373039 6971531.5150273 2420915.9629932 6968239.1420189
#Sta/Elev= 30
    2807     462    3307  449.63    3583   453.5 4024.62   446.6 4177.12   450.8
 4739.32   452.8 4903.42   448.2 5756.12   448.4 6006.02   447.1 6029.82   444.3
 6032.72  439.46 6047.22   439.8 6063.82   430.8 6141.52   419.2 6176.42   423.7
 6201.42     421 6237.12  409.88 6278.62   414.1 6303.32     435 6350.22   442.4
6353.921   442.9 7292.62   439.2 8270.82   441.3 8334.92   436.7 8605.92     440
 8939.92   451.7 8974.52   449.2 9065.82     465 9128.12   469.210587.26  466.36
#Mann= 4 ,-1,0
    2807     .07       0 5756.12    .075       0 6032.72     .05       0
6353.921    .075       0
#XS Ineff= 2 , 0
       0 3395.12  482.16 9422.26       0  488.86
Permanent Ineff=
       F       F
Bank Sta=6032.72,6350.22
XS Rating Curve= 0 ,0
Exp/Cntr=0.5,0.3

Type RM Length L Ch R = 3 ,57370   ,,,
BEGIN DESCRIPTION:
SH 161
---------------------
CDC GP011404-1 SH 161
---------------------
END DESCRIPTION:
Node Name=SH 161
Bridge Culvert--1,0,-1,-1, 0
Deck Dist Width WeirC Skew NumUp NumDn MinLoCord MaxHiCord MaxSubmerge Is_Ogee
47,166,2.6,0, 56, 56, , , 0.95, 0, 3,3,,
 1179.12 3430.12 3430.12 3525.12 3641.12 3757.12 3872.12 3982.12 4092.12 4202.12
 4312.12 4422.12 4532.12 4637.12 4747.12 4857.12 4967.12 5077.12 5187.12 5307.12
 5427.12 5547.12 5667.12 5787.12 5907.12 6107.12 6327.12 6527.12 6647.12 6767.12
 6887.12 7007.12 7127.12 7247.12 7367.12 7487.12 7595.26 7715.26 7835.26 7955.26
 8075.26 8176.26 8277.26 8377.26 8477.26 8577.26 8677.26 8777.26 8877.26 8977.26
 9077.26 9177.26 9285.26 9387.26 9387.2610587.26
  494.14  482.33  482.33  482.16  481.56  480.52  479.04  477.28  475.13  473.17
  471.11  469.17  467.76  466.94  466.65  466.93  467.51   468.1  468.69  469.33
  469.97  470.61  471.25   471.9  472.54  473.61  474.78  475.85  476.49  477.13
  477.77  478.41  479.06   479.7  480.34  480.98  481.56   482.2  482.84  483.48
  484.12  484.66   485.2  485.74  486.27   486.8  487.34  487.87  488.41  488.94
  489.42  489.58   489.4  488.86  488.86  474.75
       0       0  472.33  472.04  471.44   470.4  468.95  467.16  465.01  463.05
  460.99  459.05  457.64  456.82  456.53  456.81  457.39  457.98  458.57  459.21
  459.85  460.49  461.13  461.98  458.92  459.99  461.16  462.23  466.37  467.01
  467.65  468.29  468.94  469.58  470.22  470.86  471.44  472.08  472.72  473.36
     474  474.54  475.08  475.62  476.15  476.68  477.22  477.75  478.29  478.82
   479.3  479.46  479.28  478.74       0       0
 1179.12 3430.12 3430.12 3525.12 3641.12 3757.12 3872.12 3982.12 4092.12 4202.12
 4312.12 4422.12 4532.12 4637.12 4747.12 4857.12 4967.12 5077.12 5187.12 5307.12
 5427.12 5547.12 5667.12 5787.12 5907.12 6107.12 6327.12 6527.12 6647.12 6767.12
 6887.12 7007.12 7127.12 7247.12 7367.12 7487.12 7595.26 7715.26 7835.26 7955.26
 8075.26 8176.26 8277.26 8377.26 8477.26 8577.26 8677.26 8777.26 8877.26 8977.26
 9077.26 9177.26 9285.26 9387.26 9387.2610587.26
  494.14  482.33  482.33  482.16  481.56  480.52  479.04  477.28  475.13  473.17
  471.11  469.17  467.76  466.94  466.65  466.93  467.51   468.1  468.69  469.33
  469.97  470.61  471.25   471.9  472.54  473.61  474.78  475.85  476.49  477.13
  477.77  478.41  479.06   479.7  480.34  480.98  481.56   482.2  482.84  483.48
  484.12  484.66   485.2  485.74  486.27   486.8  487.34  487.87  488.41  488.94
  489.42  489.58   489.4  488.86  488.86  474.75
       0       0  472.33  472.04  471.44   470.4  468.95  467.16  465.01  463.05
  460.99  459.05  457.64  456.82  456.53  456.81  457.39  457.98  458.57  459.21
  459.85  460.49  461.13  461.98  458.92  459.99  461.16  462.23  466.37  467.01
  467.65  468.29  468.94  469.58  470.22  470.86  471.44  472.08  472.72  473.36
     474  474.54  475.08  475.62  476.15  476.68  477.22  477.75  478.29  478.82
   479.3  479.46  479.28  478.74       0       0
Pier Skew, UpSta & Num, DnSta & Num=  ,3525.12, 2 ,3525.12, 2 , 0 , 0 , 0 ,,
       4       4
     440  482.33
       4       4
     440  482.33
Pier Skew, UpSta & Num, DnSta & Num=  ,3641.12, 2 ,3641.12, 2 , 0 , 0 , 0 ,,
       4       4
     440  482.33
       4       4
     440  482.33
Pier Skew, UpSta & Num, DnSta & Num=  ,3757.12, 2 ,3757.12, 2 , 0 , 0 , 0 ,,
       4       4
     440  482.33
       4       4
     440  482.33
Pier Skew, UpSta & Num, DnSta & Num=  ,3872.12, 2 ,3872.12, 2 , 0 , 0 , 0 ,,
       4       4
     440  482.33
       4       4
     440  482.33
Pier Skew, UpSta & Num, DnSta & Num=  ,3982.12, 2 ,3982.12, 2 , 0 , 0 , 0 ,,
       4       4
     440  482.33
       4       4
     440  482.33
Pier Skew, UpSta & Num, DnSta & Num=  ,4092.12, 2 ,4092.12, 2 , 0 , 0 , 0 ,,
       4       4
     440  482.33
       4       4
     440  482.33
Pier Skew, UpSta & Num, DnSta & Num=  ,4202.12, 2 ,4202.12, 2 , 0 , 0 , 0 ,,
       4       4
     440  482.33
       4       4
     440  482.33
Pier Skew, UpSta & Num, DnSta & Num=  ,4312.12, 2 ,4312.12, 2 , 0 , 0 , 0 ,,
       4       4
     440  482.33
       4       4
     440  482.33
Pier Skew, UpSta & Num, DnSta & Num=  ,4422.12, 2 ,4422.12, 2 , 0 , 0 , 0 ,,
       4       4
     440  482.33
       4       4
     440  482.33
Pier Skew, UpSta & Num, DnSta & Num=  ,4532.12, 2 ,4532.12, 2 , 0 , 0 , 0 ,,
       4       4
     440  482.33
       4       4
     440  482.33
Pier Skew, UpSta & Num, DnSta & Num=  ,4632.12, 2 ,4632.12, 2 , 0 , 0 , 0 ,,
       4       4
     440  482.33
       4       4
     440  482.33
Pier Skew, UpSta & Num, DnSta & Num=  ,4747.12, 2 ,4747.12, 2 , 0 , 0 , 0 ,,
       4       4
     440  479.46
       4       4
     440  479.46
Pier Skew, UpSta & Num, DnSta & Num=  ,4857.12, 2 ,4857.12, 2 , 0 , 0 , 0 ,,
       4       4
     440  482.33
       4       4
     440  482.33
Pier Skew, UpSta & Num, DnSta & Num=  ,4967.12, 2 ,4967.12, 2 , 0 , 0 , 0 ,,
       4       4
     440  482.33
       4       4
     440  482.33
Pier Skew, UpSta & Num, DnSta & Num=  ,5077.12, 2 ,5077.12, 2 , 0 , 0 , 0 ,,
       4       4
     440  482.33
       4       4
     440  482.33
Pier Skew, UpSta & Num, DnSta & Num=  ,5187.12, 2 ,5187.12, 2 , 0 , 0 , 0 ,,
       4       4
     440  482.33
       4       4
     440  482.33
Pier Skew, UpSta & Num, DnSta & Num=  ,5307.12, 2 ,5307.12, 2 , 0 , 0 , 0 ,,
       4       4
     440  479.46
       4       4
     440  479.46
Pier Skew, UpSta & Num, DnSta & Num=  ,5427.12, 2 ,5427.12, 2 , 0 , 0 , 0 ,,
       8       8
     440  482.33
       8       8
     440  482.33
Pier Skew, UpSta & Num, DnSta & Num=  ,5547.12, 2 ,5547.12, 2 , 0 , 0 , 0 ,,
       8       8
     440  482.33
       8       8
     440  482.33
Pier Skew, UpSta & Num, DnSta & Num=  ,5667.12, 2 ,5667.12, 2 , 0 , 0 , 0 ,,
       8       8
     440  482.33
       8       8
     440  482.33
Pier Skew, UpSta & Num, DnSta & Num=  ,5787.12, 2 ,5787.12, 2 , 0 , 0 , 0 ,,
       8       8
     440  482.33
       8       8
     440  482.33
Pier Skew, UpSta & Num, DnSta & Num=  ,5907.12, 2 ,5907.12, 2 , 0 , 0 , 0 ,,
       8       8
     440  482.33
       8       8
     440  482.33
Pier Skew, UpSta & Num, DnSta & Num=  ,6107.12, 2 ,6107.12, 2 , 0 , 0 , 0 ,,
       8       8
     440  482.33
       8       8
     440  482.33
Pier Skew, UpSta & Num, DnSta & Num=  ,6327.12, 2 ,6327.12, 2 , 0 , 0 , 0 ,,
       8       8
     440  482.33
       8       8
     440  482.33
Pier Skew, UpSta & Num, DnSta & Num=  ,6527.12, 2 ,6527.12, 2 , 0 , 0 , 0 ,,
       8       8
     440  482.33
       8       8
     440  482.33
Pier Skew, UpSta & Num, DnSta & Num=  ,6647.12, 2 ,6647.12, 2 , 0 , 0 , 0 ,,
       8       8
     440  482.33
       8       8
     440  482.33
Pier Skew, UpSta & Num, DnSta & Num=  ,6767.12, 2 ,6767.12, 2 , 0 , 0 , 0 ,,
       8       8
     440  482.33
       8       8
     440  482.33
Pier Skew, UpSta & Num, DnSta & Num=  ,6887.12, 2 ,6887.12, 2 , 0 , 0 , 0 ,,
       8       8
     440  482.33
       8       8
     440  482.33
Pier Skew, UpSta & Num, DnSta & Num=  ,7007.12, 2 ,7007.12, 2 , 0 , 0 , 0 ,,
       4       4
     440  482.33
       4       4
     440  482.33
Pier Skew, UpSta & Num, DnSta & Num=  ,7127.12, 2 ,7127.12, 2 , 0 , 0 , 0 ,,
       4       4
     440  482.33
       4       4
     440  482.33
Pier Skew, UpSta & Num, DnSta & Num=  ,7247.12, 2 ,7247.12, 2 , 0 , 0 , 0 ,,
       4       4
     440  482.33
       4       4
     440  482.33
Pier Skew, UpSta & Num, DnSta & Num=  ,7367.12, 2 ,7367.12, 2 , 0 , 0 , 0 ,,
       4       4
     440  482.33
       4       4
     440  482.33
Pier Skew, UpSta & Num, DnSta & Num=  ,7487.12, 2 ,7487.12, 2 , 0 , 0 , 0 ,,
       4       4
     440  482.33
       4       4
     440  482.33
Pier Skew, UpSta & Num, DnSta & Num=  ,7595.26, 2 ,7595.26, 2 , 0 , 0 , 0 ,,
       4       4
     440  482.33
       4       4
     440  482.33
Pier Skew, UpSta & Num, DnSta & Num=  ,7715.26, 2 ,7715.26, 2 , 0 , 0 , 0 ,,
       4       4
     440  482.33
       4       4
     440  482.33
Pier Skew, UpSta & Num, DnSta & Num=  ,7835.26, 2 ,7835.26, 2 , 0 , 0 , 0 ,,
       4       4
     440  482.33
       4       4
     440  482.33
Pier Skew, UpSta & Num, DnSta & Num=  ,7955.26, 2 ,7955.26, 2 , 0 , 0 , 0 ,,
       4       4
     440  482.33
       4       4
     440  482.33
Pier Skew, UpSta & Num, DnSta & Num=  ,8075.26, 2 ,8075.26, 2 , 0 , 0 , 0 ,,
       4       4
     440  482.33
       4       4
     440  482.33
Pier Skew, UpSta & Num, DnSta & Num=  ,8176.26, 2 ,8176.26, 2 , 0 , 0 , 0 ,,
       4       4
     440  482.33
       4       4
     440  482.33
Pier Skew, UpSta & Num, DnSta & Num=  ,8277.26, 2 ,8277.26, 2 , 0 , 0 , 0 ,,
       4       4
     440  482.33
       4       4
     440  482.33
Pier Skew, UpSta & Num, DnSta & Num=  ,8377.26, 2 ,8377.26, 2 , 0 , 0 , 0 ,,
       4       4
     440  482.33
       4       4
     440  482.33
Pier Skew, UpSta & Num, DnSta & Num=  ,8477.26, 2 ,8477.26, 2 , 0 , 0 , 0 ,,
       4       4
     440  482.33
       4       4
     440  482.33
Pier Skew, UpSta & Num, DnSta & Num=  ,8577.26, 2 ,8577.26, 2 , 0 , 0 , 0 ,,
       4       4
     440  482.33
       4       4
     440  482.33
Pier Skew, UpSta & Num, DnSta & Num=  ,8677.26, 2 ,8677.26, 2 , 0 , 0 , 0 ,,
       4       4
     440  482.33
       4       4
     440  482.33
Pier Skew, UpSta & Num, DnSta & Num=  ,8777.26, 2 ,8777.26, 2 , 0 , 0 , 0 ,,
       4       4
     440  482.33
       4       4
     440  482.33
Pier Skew, UpSta & Num, DnSta & Num=  ,8877.26, 2 ,8877.26, 2 , 0 , 0 , 0 ,,
       4       4
     440  482.33
       4       4
     440  482.33
Pier Skew, UpSta & Num, DnSta & Num=  ,8977.26, 2 ,8977.26, 2 , 0 , 0 , 0 ,,
       4       4
     440  482.33
       4       4
     440  482.33
Pier Skew, UpSta & Num, DnSta & Num=  ,9077.26, 2 ,9077.26, 2 , 0 , 0 , 0 ,,
       4       4
     440  482.33
       4       4
     440  482.33
Pier Skew, UpSta & Num, DnSta & Num=  ,9177.26, 2 ,9177.26, 2 , 0 , 0 , 0 ,,
       4       4
     440  482.33
       4       4
     440  482.33
Pier Skew, UpSta & Num, DnSta & Num=  ,9282.26, 2 ,9282.26, 2 , 0 , 0 , 0 ,,
       4       4
     440  482.33
       4       4
     440  482.33
Abutment Skew #Up #Dn= , 2 , 2
 3430.12    3465
  482.33     440
 3430.12    3465
  482.33     440
Abutment Skew #Up #Dn= , 2 , 2
    9335 9387.26
     440  488.86
    9335 9387.26
     440  488.86
BR Coef=-1 , 1 , 1 ,0.9, 0 ,,,0.8,-1,1.33,0,
WSPro=,,,, 1 ,,,, 0 ,,,, 0 ,,,,-1 ,-1 ,-1 , 0 , 0 , 0 , 0 , 0
BC Design=,, 0 ,, 0 ,,,,,,
BC Use User HTab Curves=0
BC User HTab FreeFlow(D)= 0

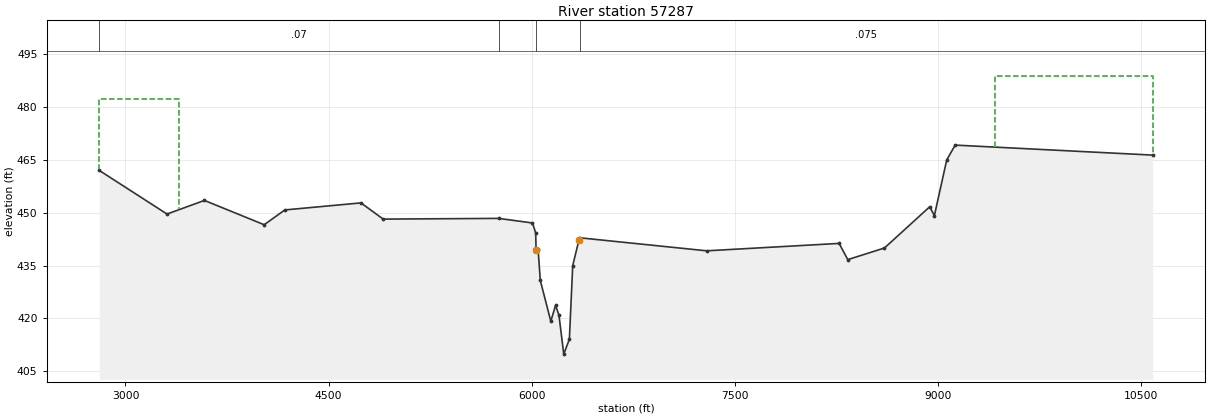
Type RM Length L Ch R = 1 ,57287   ,926,204,183
BEGIN DESCRIPTION:
This cross section corresponds to cross section 57303 of the non-georeferenced CDC model which was the source of this model.
Downstream bounding cross-section.
Copied from cross-section 57586
END DESCRIPTION:
XS GIS Cut Line= 6
  2424208.296303 6974983.5566797 2423436.3326244 6971871.1475502
 2423312.4001295 6971772.0109374 2423188.4676346 6971672.8743247
 2422592.5928421 6971377.8693372 2420957.5370571  6968184.162142
#Sta/Elev= 30
    2807     462    3307  449.63    3583   453.5 4024.62   446.6 4177.12   450.8
 4739.32   452.8 4903.42   448.2 5756.12   448.4 6006.02   447.1 6029.82   444.3
 6032.72  439.46 6047.22   439.8 6063.82   430.8 6141.52   419.2 6176.42   423.7
 6201.42     421 6237.12  409.88 6278.62   414.1 6303.32     435 6350.22   442.4
6353.921   442.9 7292.62   439.2 8270.82   441.3 8334.92   436.7 8605.92     440
 8939.92   451.7 8974.52   449.2 9065.82     465 9128.12   469.210587.26  466.36
#Mann= 4 ,-1,0
    2807     .07       0 5756.12    .075       0 6032.72     .05       0
6353.921    .075       0
#XS Ineff= 2 , 0
       0 3395.12  482.16 9422.26       0  488.86
Permanent Ineff=
       F       F
Bank Sta=6032.72,6350.22
XS Rating Curve= 0 ,0
Exp/Cntr=0.5,0.3