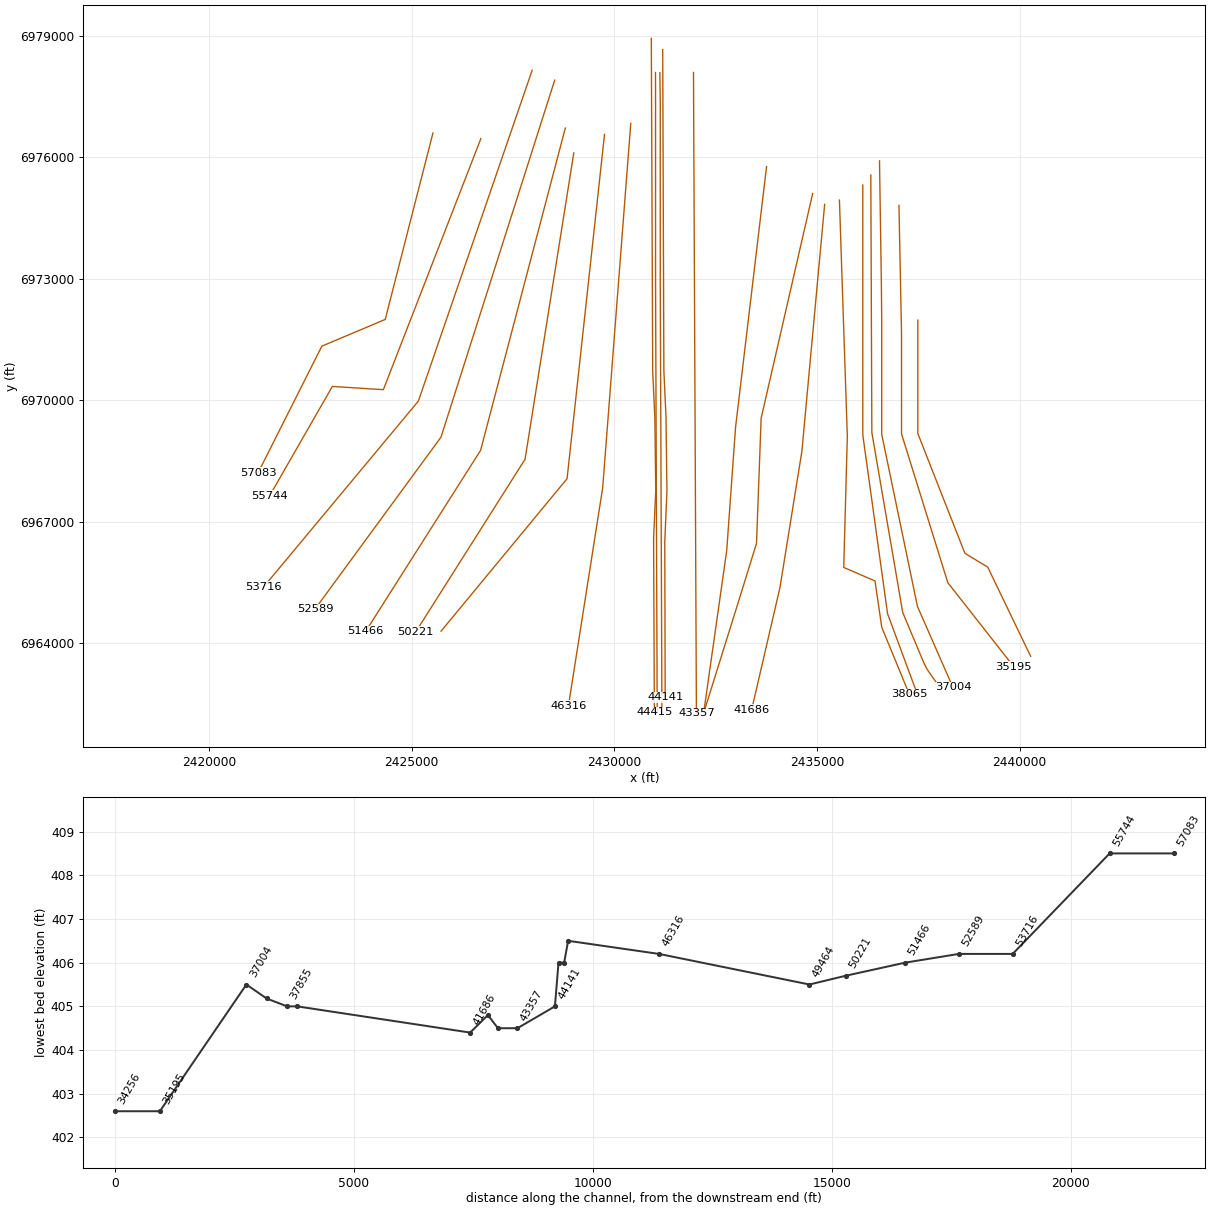
HEC-RAS study CDC_Consolidated_Model.prj: Upper Trinity CDC Consolidated Model

--- CDC_Consolidated_Model.g02 (geometry) --- (continued)

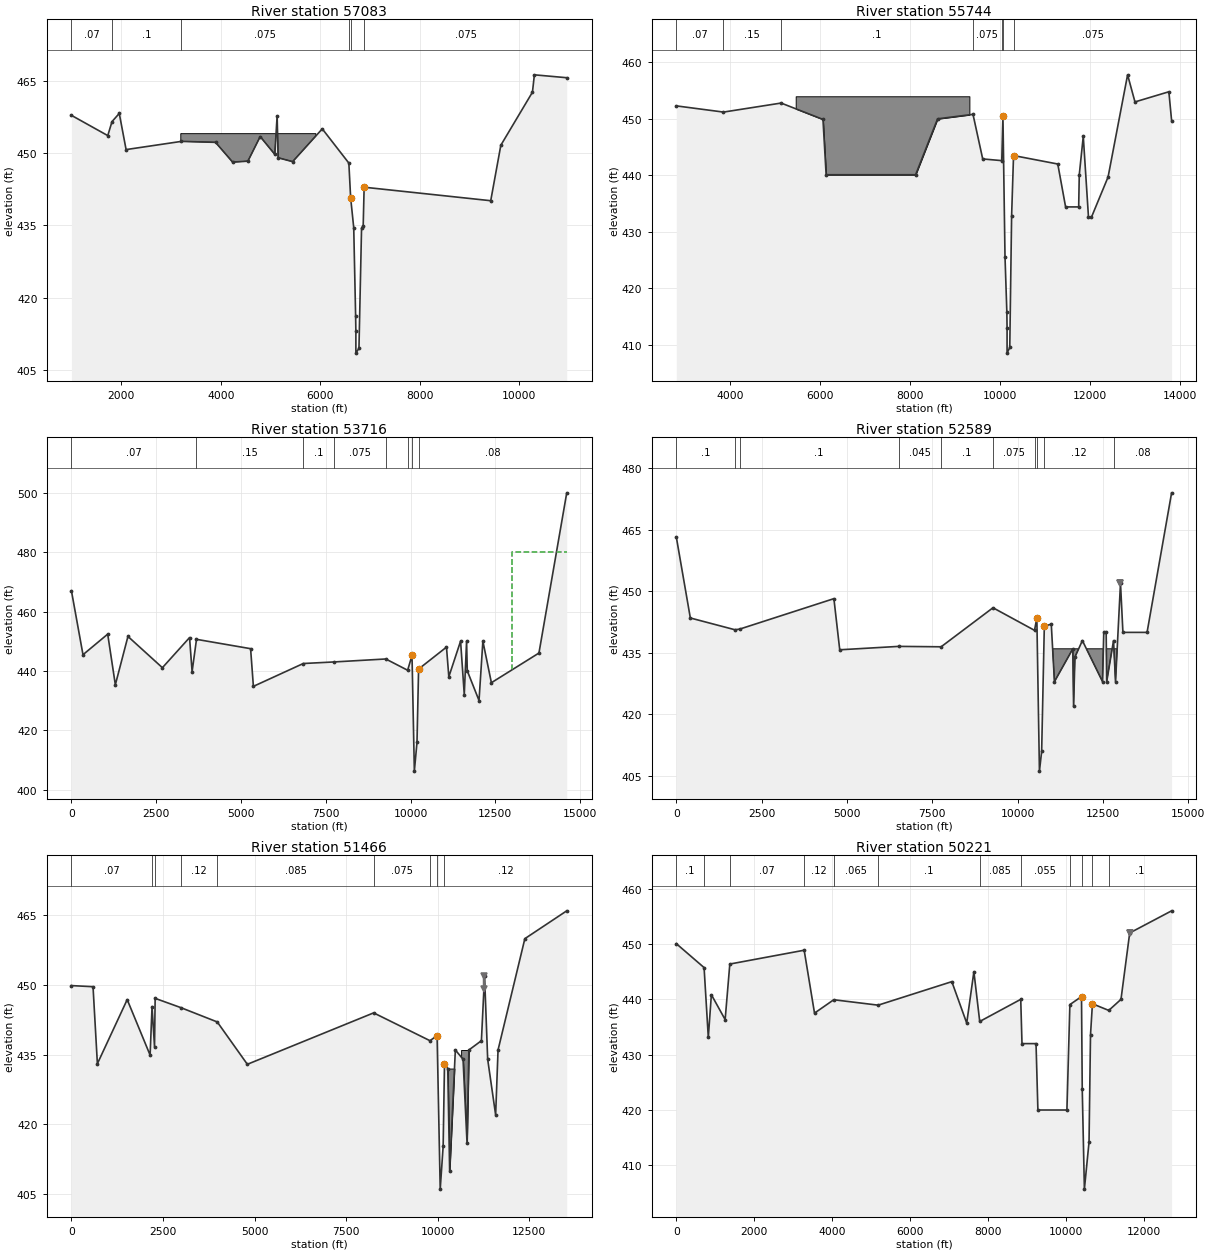
Type RM Length L Ch R = 1 ,57083   ,650,1339,650
BEGIN DESCRIPTION:
This cross section corresponds to cross section 57099 of the non-georeferenced CDC model which was the source of this model.
END DESCRIPTION:
XS GIS Cut Line= 6
  2425526.340911 6976594.0629731 2424937.7092148 6974292.6948724
 2424348.9889356 6971991.3389108 2422785.3798581 6971331.7588652
 2421970.7965135   6969712.04885 2421211.8458218 6968203.1268699
#Sta/Elev= 30
    1000   457.8    1730   453.6    1815   456.5    1961   458.2    2098   450.7
    3209   452.4    3895   452.2    4238   448.1    4545   448.3    4792   453.4
    5086   449.7    5132   457.7    5153     449    5444   448.2    6039     455
    6573   447.9    6609   440.7    6671   434.5    6709   416.2    6714     413
    6714   408.5    6776   409.5    6828   434.4    6861   434.9    6880   442.9
    9423   440.1    9626   451.6   10261   462.6   10300   466.2   10950   465.6
#Mann= 6 ,-1,0
    1000     .07       0    1815      .1       0    3209    .075       0
    6573     .12       0    6609     .05       0    6880    .075       0
#Block Obstruct= 1 ,-1
    3197    5910     454
Bank Sta=6609,6880
XS Rating Curve= 0 ,0
Exp/Cntr=0.3,0.1

Type RM Length L Ch R = 1 ,55744   ,2029,2029,2029
BEGIN DESCRIPTION:
This cross section corresponds to cross section 55761 of the non-georeferenced CDC model which was the source of this model.
END DESCRIPTION:
XS GIS Cut Line= 6
  2426708.155149 6976454.2332002 2425510.9052469 6973368.7994105
 2424303.4358771 6970257.6930999 2423045.2090628 6970337.7700395
 2422241.3379672 6968935.5973189 2421497.8404384 6967638.8620515
#Sta/Elev= 30
    2798   452.3    3848   451.2    5130   452.8    6061   449.9    6131   440.1
    8122   440.1    8610     450    9398   450.8    9614   442.9   10038   442.6
   10064   450.5   10110   425.6   10151   415.8   10156     413   10156   408.5
   10216   409.5   10257   432.8   10300   443.5   11284     442   11458   434.4
   11749   434.4   11762   440.1   11851   446.9   11967   432.6   12034   432.6
   12403   439.7   12837   457.8   13001     453   13755   454.8   13816   449.7
#Mann= 7 ,-1,0
    2798     .07       0    3848     .15       0    5130      .1       0
    9398    .075       0   10038     .12       0   10064     .05       0
   10300    .075       0
#Block Obstruct= 1 ,-1
    5454    9318     454
Bank Sta=10064,10300
XS Rating Curve= 0 ,0
Exp/Cntr=0.3,0.1

Type RM Length L Ch R = 1 ,53716   ,1363,1127,1159
BEGIN DESCRIPTION:
This cross section corresponds to cross section 53730 of the non-georeferenced CDC model which was the source of this model.
END DESCRIPTION:
XS GIS Cut Line= 6
   2427973.59198 6978142.1615694 2426568.5632366 6974053.6789462
 2425867.6797958 6972014.6088774 2425166.7041637 6969975.5548846
 2423257.7466955 6967680.7162985 2421348.5149497 6965385.9918853
#Sta/Elev= 30
       0  466.98  340.87  445.44 1069.55  452.37 1294.81  435.31 1666.57   451.6
 2682.26  441.06 3483.04  451.21 3558.14  439.73 3687.83  450.62 5283.42  447.47
 5365.51  434.77 6836.28  442.47 7746.08     443    9270     444    9914   440.2
   10043   445.2   10112   406.2   10190   415.9   10237   440.611059.73     448
11128.44     43811475.07     45011583.97     43211652.12     45011672.87     440
12019.06     43012132.55     45012383.62     43613786.05     44614605.66     500
#Mann= 8 ,-1,0
       0     .07       0 3687.83     .15       0 6836.28      .1       0
 7746.08    .075       0    9270    .075       0    9914     .12       0
   10043     .05       0   10237     .08       0
#XS Ineff= 2 , 0
       0                   13000       0     480
Permanent Ineff=
       F       F
Bank Sta=10043,10237
XS Rating Curve= 0 ,0
Exp/Cntr=0.3,0.1

Type RM Length L Ch R = 1 ,52589   ,1357,1123,1233
BEGIN DESCRIPTION:
This cross section corresponds to cross section 52592 of the non-georeferenced CDC model which was the source of this model.
END DESCRIPTION:
XS GIS Cut Line= 6
  2428529.736807  6977898.615154 2427839.5436342 6975729.3947549
 2427124.8232789 6973483.4241812 2425724.8621681 6969085.1140802
 2424173.9420416 6966966.3991576 2422614.9451596 6964837.0100437
#Sta/Elev= 30
       0  463.26  411.38  443.51 1719.49  440.64 1857.49   440.8 4618.21  448.22
 4789.26  435.76 6517.48  436.59 7760.53  436.49    9280     44610496.67   440.5
   10565   443.5   10641   406.2   10706     411   10784   441.510987.93     442
11080.78     428 11619.3     43611641.57     42211681.36     43411899.36     438
12490.09     42812525.85     44012596.46     44012612.16     42812811.75     438
12870.43     428 13016.3     45213087.25     440 13794.8     440 14513.8     474
#Mann= 10 ,-1,0
       0      .1       0 1719.49    .065       0 1857.49      .1       0
 6517.48    .045       0 7760.53      .1       0    9280    .075       0
10496.67     .11       0   10565     .05       0   10784     .12       0
12811.75     .08       0
Levee=0,,,-1,13016.2,452,,
#Block Obstruct= 1 ,-1
   11000   13200     436
Bank Sta=10565,10784
XS Rating Curve= 0 ,0
Exp/Cntr=0.3,0.1

Type RM Length L Ch R = 1 ,51466   ,1048,1245,1120
BEGIN DESCRIPTION:
This cross section corresponds to cross section 51481 of the non-georeferenced CDC model which was the source of this model.
END DESCRIPTION:
XS GIS Cut Line= 6
  2428792.155574 6976717.4905477 2428255.6648493 6974674.6278356
 2427729.3785003 6972670.8956226 2426701.6689415 6968758.8739191
 2425283.6255178 6966522.8610027 2423867.0381278 6964289.5219654
#Sta/Elev= 30
       0  449.88  589.71  449.64  708.61  433.04  1522.3  446.86 2147.65  434.89
 2200.56  445.37 2268.28  436.69 2285.34  447.13 2983.59  445.14 3980.97  442.04
 4802.25  432.91    8250     444 9787.86     438    9982   439.1   10067     406
   10147   415.2   10184     43310272.72     43210324.68     41010480.26     436
10690.35     43410798.95     416 10850.2     43611191.49     43811277.45     452
11362.48     43411580.19     42211645.85     436 12377.7     46013520.99     466
#Mann= 9 ,-1,0
       0     .07       0 2200.56     .05       0 2285.34     .07       0
 2983.59     .12       0 3980.97    .085       0    8250    .075       0
 9787.86     .09       0    9982    .055       0   10184     .12       0
Levee=0,,,-1,11259.76,452,,
#Block Obstruct= 2 ,-1
10272.72   10550     43210637.55   10900     436
Bank Sta=9982,10184
XS Rating Curve= 0 ,0
Exp/Cntr=0.3,0.1

Type RM Length L Ch R = 1 ,50221   ,1095,757,668
BEGIN DESCRIPTION:
This cross section corresponds to cross section 50225 of the non-georeferenced CDC model which was the source of this model.
END DESCRIPTION:
XS GIS Cut Line= 6
  2429001.342726 6976101.2903723 2428396.3348435 6972296.1739311
 2427798.8422721 6968539.2975866 2427143.2340033 6967502.8852893
 2426437.1461766 6966386.7638339  2425102.682599 6964277.6183724
#Sta/Elev= 30
       0  450.07  712.53  445.74  820.76  433.12   899.3  440.84 1252.62  436.34
 1372.33  446.38 3278.76  448.88 3544.05  437.51  4037.1  439.93 5175.31  438.95
 7064.74   443.2 7446.47  435.71 7630.48     445    7780     436  8831.7     440
  8863.7     432  9223.7     432  9271.7     420 10015.7     420 10091.7  439.05
 10389.7   440.5 10408.7   423.8 10463.7   405.7 10582.7   414.2 10620.7   433.6
 10669.7   439.211089.03     43811402.21     44011625.44     45212699.94     456
#Mann= 12 ,-1,0
       0      .1       0  712.53    .065       0 1372.33     .07       0
 3278.76     .12       0  4037.1    .065       0 5175.31      .1       0
    7780    .085       0  8831.7    .055       0 10091.7     .09       0
 10389.7     .05       0 10669.7     .04       011089.03      .1       0
Levee=0,,,-1,11625.44,452,,
Bank Sta=10389.7,10669.7
XS Rating Curve= 0 ,0
Exp/Cntr=0.3,0.1

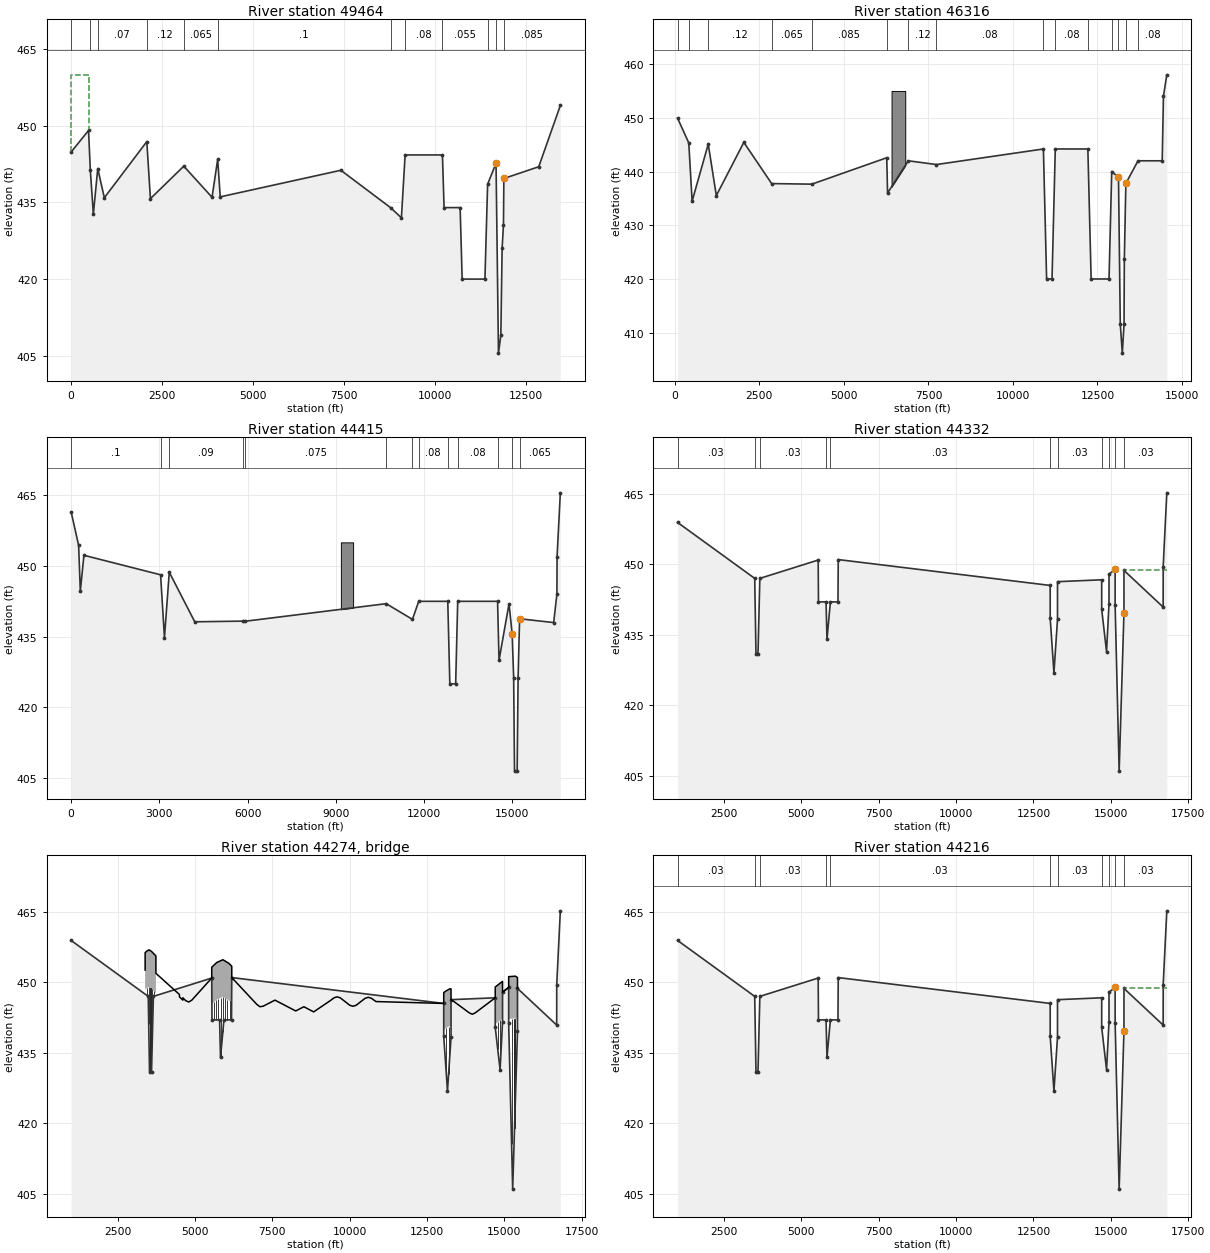
Type RM Length L Ch R = 1 ,49464   ,803,3148,3446
BEGIN DESCRIPTION:
This cross section corresponds to cross section 49477 of the non-georeferenced CDC model which was the source of this model.
END DESCRIPTION:
XS GIS Cut Line= 3
  2429759.517812 6976561.5827231  2428835.198139 6968058.7621303
 2425726.7138704 6964295.5813365
#Sta/Elev= 30
       0  444.88   477.9   449.1  527.69  441.29  610.17   432.7   731.1  441.64
  911.56  435.93 2078.27  446.92 2177.35  435.75 3093.81  442.11 3869.88  436.02
 4024.67  443.47 4094.16   436.1 7406.48  441.31    8770     434 9069.62     432
  9171.5  444.31 10196.2  444.31   10241     434   10682     434   10738     420
   11363     420   11437  438.58   11668   442.7   11735   405.5   11800     409
   11835     426   11872   430.6   11883   439.712840.75     44213433.91     454
#Mann= 12 ,-1,0
       0      .1       0  527.69    .065       0   731.1     .07       0
 2078.27     .12       0 3093.81    .065       0 4024.67      .1       0
    8770     .11       0  9171.5     .08       0 10196.2    .055       0
   11437     .09       0   11668     .05       0   11883    .085       0
#XS Ineff= 2 , 0
       0   477.9     460               0
Permanent Ineff=
       F       F
Bank Sta=11668,11883
XS Rating Curve= 0 ,0
Exp/Cntr=0.3,0.1

Type RM Length L Ch R = 1 ,46316   ,836,1901,1978
BEGIN DESCRIPTION:
This cross section corresponds to cross section 46329 of the non-georeferenced CDC model which was the source of this model.
END DESCRIPTION:
XS GIS Cut Line= 6
  2430406.963215   6976831.81924 2430067.3711996 6972422.0506478
 2429890.7065267 6970128.5421115 2429714.0119982 6967835.0358717
 2429284.4127917 6965095.9268487 2428870.0809433  6962454.649979
#Sta/Elev= 30
   81.47  449.93  412.21  445.33     511  434.48  987.91   445.1 1226.81  435.52
 2040.52  445.43 2862.94  437.76 4053.32  437.65    6268  442.57    6292     436
    6906     442    7738   441.3   10901   444.2   10996     420   11156     420
 11252.8   444.2 12216.2   444.2   12313     420   12842     420   12922     440
   13122   438.9   13175   411.6   13235   406.2   13286   411.6   13295   423.7
   13340   437.813699.83     44214415.12     44214451.41     45414551.07     458
#Mann= 15 ,-1,0
   81.47      .1       0  412.21    .065       0  987.91     .12       0
 2862.94    .065       0 4053.32    .085       0    6268    .065       0
    6906     .12       0    7738     .08       0   10901    .055       0
 11252.8     .08       0 12216.2    .055       0   12922     .09       0
   13122    .055       0   13340     .04       013699.83     .08       0
#Block Obstruct= 1 ,-1
    6409    6815     455
Bank Sta=13122,13340
XS Rating Curve= 0 ,0
Exp/Cntr=0.3,0.1

Type RM Length L Ch R = 1 ,44415   ,83,83,83
BEGIN DESCRIPTION:
This cross section corresponds to cross section 44427 of the non-georeferenced CDC model which was the source of this model.
END DESCRIPTION:
XS GIS Cut Line= 6
  2430913.642398 6978931.8831911  2430948.008874 6970715.5409375
 2431001.3181506 6969547.1820537 2431023.5300484 6967770.2089016
 2430970.2210999 6966597.4061292 2430989.0199468 6962293.8081091
#Sta/Elev= 30
       0  461.45     255  454.39  312.79  444.64  435.51  452.26 3043.06  448.12
 3174.56  434.79 3338.56  448.67 4205.09  438.16 5831.08   438.3 5927.27  438.28
   10717     442   11611  438.67   11823   442.5   12812   442.5   12882     425
   13080     425   13150   442.5   14506   442.5   14555     430   14896     442
   15003   435.5   15053   426.3   15082   406.5   15172   406.5   15204   426.2
   15255   438.8   16414     438   16524     444   16530     452   16641   465.5
#Mann= 13 ,-1,0
       0      .1       0 3043.06    .075       0 3338.56     .09       0
 5831.08    .065       0 5927.27    .075       0   10717     .07       0
   11611     .09       0   11823     .08       0   12812    .055       0
   13150     .08       0   14506    .055       0   15003     .05       0
   15255    .065       0
#Block Obstruct= 1 ,-1
    9175    9592     455
Bank Sta=15003,15255
XS Rating Curve= 0 ,0
Exp/Cntr=0.3,0.1

Type RM Length L Ch R = 1 ,44332   ,118,118,118
BEGIN DESCRIPTION:
This cross section corresponds to cross section 44351 of the non-georeferenced CDC model which was the source of this model.
Belt Line Road upstream bounding cross-section.
END DESCRIPTION:
XS GIS Cut Line= 6
  2431017.183604 6978088.3306538 2431018.2610301 6977391.1883473
 2431018.2610301 6972897.9719401 2431032.2075245 6969275.3079256
 2431044.5969354 6966055.1641034 2431059.1234812 6962280.6076762
#Sta/Elev= 30
    1000   458.9    3492     447    3533     431    3598     431    3658     447
    5543   450.9  5552.3     442    5797     442    5827     434    5937     442
  6182.3     442    6191     451   13040   445.5   13040   438.5   13161   426.9
   13276   438.3   13276   446.3   14704   446.7   14704   440.4   14861   431.4
   14940   441.6   14940   447.9   15138   448.9   15138   441.4   15268     406
   15423   439.6   15423   448.7   16690   440.9   16691   449.5   16808   465.2
#Mann= 11 ,-1,0
    1000     .03       0    3492     .05       0    3658     .03       0
    5797     .05       0    5937     .03       0   13040     .05       0
   13276     .03       0   14704     .05       0   14940     .03       0
   15138     .05       0   15423     .03       0
#XS Ineff= 2 , 0
       0                   15423       0   448.7
Permanent Ineff=
       F       T
Bank Sta=15138,15423
XS Rating Curve= 0 ,0
Exp/Cntr=0.3,0.1

Type RM Length L Ch R = 3 ,44274   ,,,
BEGIN DESCRIPTION:
Belt Line Road
END DESCRIPTION:
Node Name=Belt Line Road
Bridge Culvert--1,0,-1,-1, 0
Deck Dist Width WeirC Skew NumUp NumDn MinLoCord MaxHiCord MaxSubmerge Is_Ogee
0.5,117,2.6,0, 59, 59, , , 0.95, 0, 0,0,,
    3391    3391    3438    3515    3592    3740    3740    4500    4500    4610
    4610    4700    4800    4900    5543    5543    5704    5904    6104    6191
    6191    7000    7100    7200    7587    8257    8521    8837    9397    9495
    9595    9695   10007   10107   10207   10502   10602   10702   10850   13040
   13040   13040   13100   13231   13276   13276   13350   13864   13962   14060
   14704   14704   14940   14940   15138   15138   15357   15423   15423
   452.6   456.3   456.6   456.9   456.6   455.6   451.9   447.4   446.9   446.2
   446.7   446.1   445.8   446.2   450.9   453.2   454.2   454.8     454   453.4
     451   445.3   444.8   444.9   446.2   443.9   444.8   443.7   446.2   446.7
   446.9   446.7   445.1   444.9   445.1   446.6   446.8   446.6   445.9   445.5
   445.5   447.8   448.1   448.6   448.6   446.3     446   443.5   443.2   443.5
   446.7     449   450.2   447.9   448.9   451.2   451.3     451   448.7
   452.6   448.4   448.7     449   448.7   447.7   451.9   447.4   446.9   446.2
   446.7   446.1   445.8   446.2   450.9   445.3   446.3   446.9   446.1   445.5
     451   445.3   444.8   444.9   446.2   443.9   444.8   443.7   446.2   446.7
   446.9   446.7   445.1   444.9   445.1   446.6   446.8   446.6   445.9   445.5
   445.5   439.9   440.2   440.7   440.7   446.3     446   443.5   443.2   443.5
   446.7   441.1   442.3   447.9   448.9   442.2   442.3     442   448.7
    3391    3391    3438    3515    3592    3740    3740    4500    4500    4610
    4610    4700    4800    4900    5543    5543    5704    5904    6104    6191
    6191    7000    7100    7200    7587    8257    8521    8837    9397    9495
    9595    9695   10007   10107   10207   10502   10602   10702   10850   13040
   13040   13040   13100   13231   13276   13276   13350   13864   13962   14060
   14704   14704   14940   14940   15138   15138   15357   15423   15423
   452.6   456.3   456.6   456.9   456.6   455.6   451.9   447.4   446.9   446.2
   446.7   446.1   445.8   446.2   450.9   453.2   454.2   454.8     454   453.4
     451   445.3   444.8   444.9   446.2   443.9   444.8   443.7   446.2   446.7
   446.9   446.7   445.1   444.9   445.1   446.6   446.8   446.6   445.9   445.5
   445.5   447.8   448.1   448.6   448.6   446.3     446   443.5   443.2   443.5
   446.7     449   450.2   447.9   448.9   451.2   451.3     451   448.7
   452.6   448.4   448.7     449   448.7   447.7   451.9   447.4   446.9   446.2
   446.7   446.1   445.8   446.2   450.9   445.3   446.3   446.9   446.1   445.5
     451   445.3   444.8   444.9   446.2   443.9   444.8   443.7   446.2   446.7
   446.9   446.7   445.1   444.9   445.1   446.6   446.8   446.6   445.9   445.5
   445.5   439.9   440.2   440.7   440.7   446.3     446   443.5   443.2   443.5
   446.7   441.1   442.3   447.9   448.9   442.2   442.3     442   448.7
Pier Skew, UpSta & Num, DnSta & Num=  ,3449, 2 ,3449, 2 , 0 , 0 , 0 ,,
     2.5     2.5
     430     450
     2.5     2.5
     430     450
Pier Skew, UpSta & Num, DnSta & Num=  ,3507, 2 ,3507, 2 , 0 , 0 , 0 ,,
     2.5     2.5
     430     450
     2.5     2.5
     430     450
Pier Skew, UpSta & Num, DnSta & Num=  ,3565, 2 ,3565, 2 , 0 , 0 , 0 ,,
     2.5     2.5
     430     450
     2.5     2.5
     430     450
Pier Skew, UpSta & Num, DnSta & Num=  ,3623, 2 ,3623, 2 , 0 , 0 , 0 ,,
     2.5     2.5
     430     450
     2.5     2.5
     430     450
Pier Skew, UpSta & Num, DnSta & Num=  ,3681, 2 ,36812.54, 2 , 0 , 0 , 0 ,,
     2.5     2.5
     430     450
     2.5     2.5
     430     450
Pier Skew, UpSta & Num, DnSta & Num=  ,5615, 2 ,56152.54, 2 , 0 , 0 , 0 ,,
     2.5     2.5
     430     450
     2.5     2.5
     430     450
Pier Skew, UpSta & Num, DnSta & Num=  ,5687, 2 ,56872.54, 2 , 0 , 0 , 0 ,,
     2.5     2.5
     430     450
     2.5     2.5
     430     450
Pier Skew, UpSta & Num, DnSta & Num=  ,5759, 2 ,57592.54, 2 , 0 , 0 , 0 ,,
     2.5     2.5
     430     450
     2.5     2.5
     430     450
Pier Skew, UpSta & Num, DnSta & Num=  ,5831, 2 ,58312.54, 2 , 0 , 0 , 0 ,,
     2.5     2.5
     430     450
     2.5     2.5
     430     450
Pier Skew, UpSta & Num, DnSta & Num=  ,5903, 2 ,59032.54, 2 , 0 , 0 , 0 ,,
     2.5     2.5
     430     450
     2.5     2.5
     430     450
Pier Skew, UpSta & Num, DnSta & Num=  ,5975, 2 ,59752.54, 2 , 0 , 0 , 0 ,,
     2.5     2.5
     430     450
     2.5     2.5
     430     450
Pier Skew, UpSta & Num, DnSta & Num=  ,6047, 2 ,60472.54, 2 , 0 , 0 , 0 ,,
     2.5     2.5
     430     450
     2.5     2.5
     430     450
Pier Skew, UpSta & Num, DnSta & Num=  ,6119, 2 ,61192.54, 2 , 0 , 0 , 0 ,,
     2.5     2.5
     430     450
     2.5     2.5
     430     450
Pier Skew, UpSta & Num, DnSta & Num=  ,13119, 2 ,13119, 2 , 0 , 0 , 0 ,,
     2.5     2.5
     400     444
     2.5     2.5
     400     444
Pier Skew, UpSta & Num, DnSta & Num=  ,13198, 2 ,13198, 2 , 0 , 0 , 0 ,,
     2.5     2.5
     400     444
     2.5     2.5
     400     444
Pier Skew, UpSta & Num, DnSta & Num=  ,14783, 2 ,14783, 2 , 0 , 0 , 0 ,,
     2.5     2.5
     400     444
     2.5     2.5
     400     444
Pier Skew, UpSta & Num, DnSta & Num=  ,14862, 2 ,14862, 2 , 0 , 0 , 0 ,,
     2.5     2.5
     400     444
     2.5     2.5
     400     444
Pier Skew, UpSta & Num, DnSta & Num=  ,15233, 2 ,15233, 2 , 0 , 0 , 0 ,,
       3       3
     400     444
       3       3
     400     444
Pier Skew, UpSta & Num, DnSta & Num=  ,15328, 2 ,15328, 2 , 0 , 0 , 0 ,,
       3       3
     400     444
       3       3
     400     444
BR Coef=-1 , 0 , 0 ,, 0 ,,,0.8,-1,,1,
WSPro=,,,, 1 ,,,, 0 ,,,, 0 ,,,,-1 ,-1 ,-1 , 0 , 0 , 0 , 0 , 0
BC Design=,, 0 ,, 0 ,,,,,,
BC HTab HWMax=454.8
BC Use User HTab Curves=0
BC User HTab FreeFlow(D)= 0

Type RM Length L Ch R = 1 ,44216   ,56,75,75
BEGIN DESCRIPTION:
This cross section corresponds to cross section 44232 of the non-georeferenced CDC model which was the source of this model.
Belt Line Road downstream bounding cross-section.
CDC GP080808-1 Belt Line West Reclamation
Cross-section 44232 - 55761
Located in LOB.
CDC IRV120304-1 Belt Line Road from IH30 to Rock
END DESCRIPTION:
XS GIS Cut Line= 6
  2431124.406487 6978083.6410307 2431134.5770704 6977312.3341743
 2431134.5770704 6972896.8479266 2431148.5235648 6969272.4381807
 2431172.6019287 6963012.1170399 2431175.4516606 6962265.3324442
#Sta/Elev= 30
    1000   458.9    3492     447    3533     431    3598     431    3658     447
    5543   450.9  5552.3     442    5797     442    5827     434    5937     442
  6182.3     442    6191     451   13040   445.5   13040   438.5   13161   426.9
   13276   438.3   13276   446.3   14704   446.7   14704   440.4   14861   431.4
   14940   441.6   14940   447.9   15138   448.9   15138   441.4   15268     406
   15423   439.6   15423   448.7   16690   440.9   16691   449.5   16808   465.2
#Mann= 11 ,-1,0
    1000     .03       0    3492     .05       0    3658     .03       0
    5797     .05       0    5937     .03       0   13040    .055       0
   13276     .03       0   14704     .05       0   14940     .03       0
   15138     .05       0   15423     .03       0
#XS Ineff= 2 , 0
       0                   15423       0   448.7
Permanent Ineff=
       F       T
Bank Sta=15138,15423
XS Rating Curve= 0 ,0
Exp/Cntr=0.3,0.1

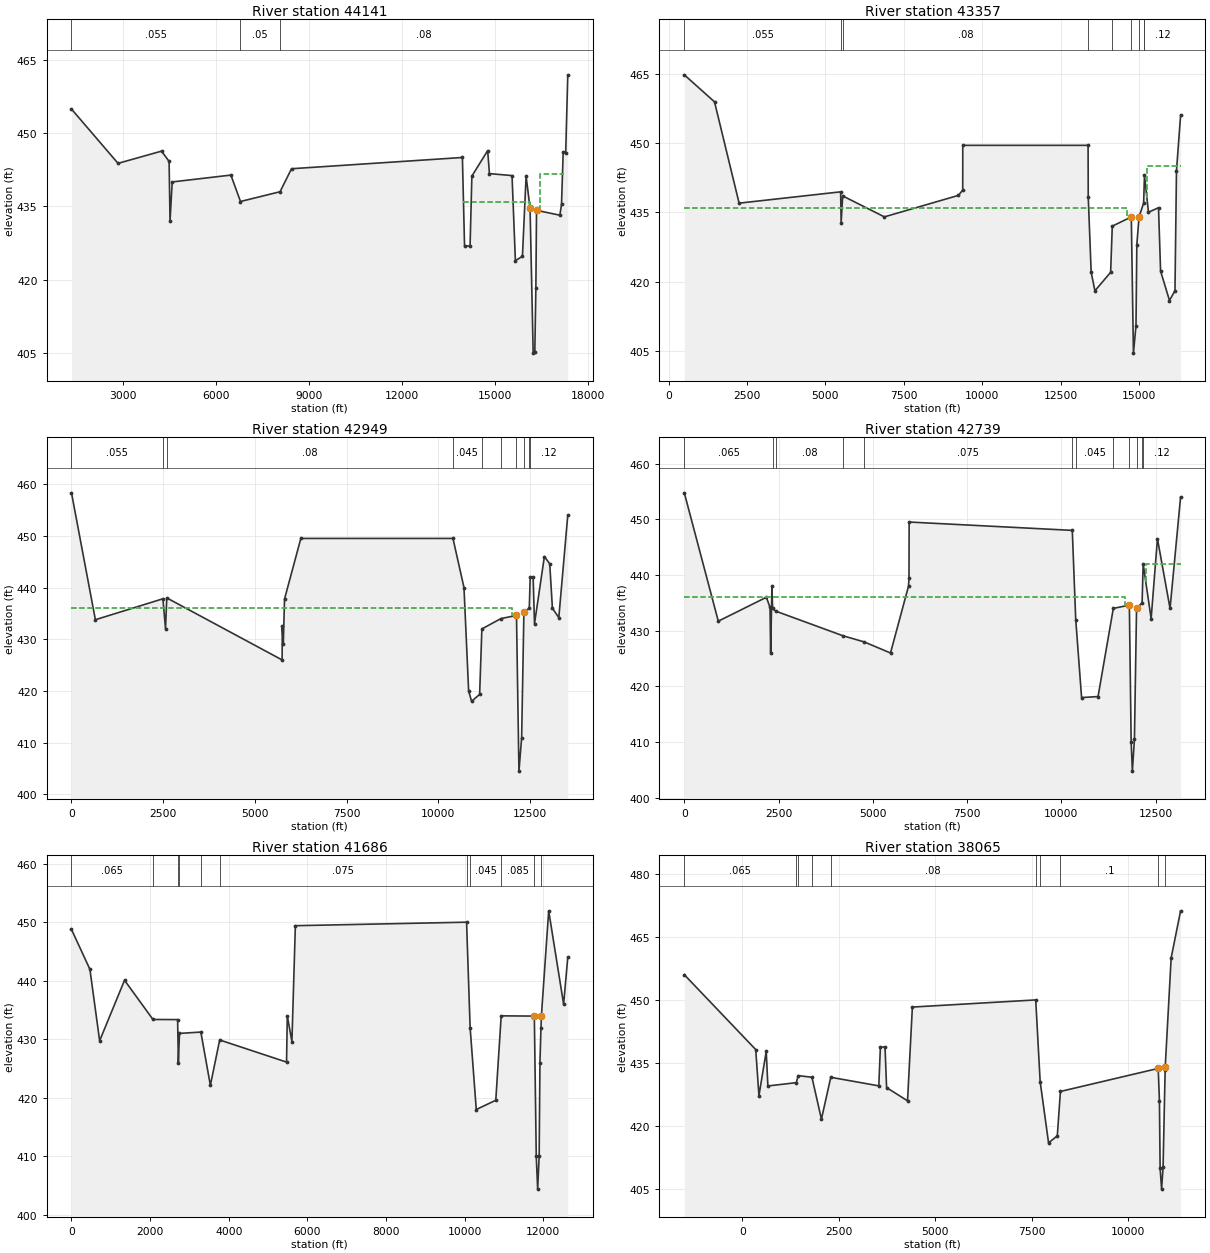
Type RM Length L Ch R = 1 ,44141   ,764,784,790
BEGIN DESCRIPTION:
This cross section corresponds to cross section 44153 of the non-georeferenced CDC model which was the source of this model.
END DESCRIPTION:
XS GIS Cut Line= 6
  2431194.921402 6978653.9746285 2431223.4400817 6970733.3109151
 2431276.7490302 6969573.8358718  2431298.960928 6967747.9960196
 2431245.6519795 6966495.2301524 2431255.9631441  6962666.794463
#Sta/Elev= 30
    1355   454.9    2855   443.8    4257   446.3    4500   444.2    4530     432
    4600     440    6491   441.4    6800     436    8075     438    8444   442.7
   13950     445   14019   426.9   14197   426.9   14255   441.2   14764   446.4
   14821   441.7   15549   441.3   15657   423.9   15884   424.8   16002   441.2
   16130   434.6   16230     405   16283   405.2   16317   418.4   16338   434.2
   17090   433.2   17143   435.4   17197   446.1   17278     446   17345   461.9
#Mann= 3 ,-1,0
    1355    .055       0    6800     .05       0    8075     .08       0
#XS Ineff= 2 ,-1
   13954   16130     436   16450   17209   441.7
Permanent Ineff=
       F       T
Bank Sta=16130,16338
XS Rating Curve= 0 ,0
Exp/Cntr=0.3,0.1

Type RM Length L Ch R = 1 ,43357   ,1524,408,390
BEGIN DESCRIPTION:
This cross section corresponds to cross section 43369 of the non-georeferenced CDC model which was the source of this model.
END DESCRIPTION:
XS GIS Cut Line= 6
  2431954.349471 6978088.4298544 2431962.0452317 6976397.8681555
 2431973.5291327 6973874.3981368 2431990.9772605 6970038.7263462
 2432008.8751906 6966102.1187339 2432026.3049457 6962266.4528488
#Sta/Elev= 30
  502.22  464.77 1465.36  458.92 2249.31  436.98 5486.05  439.43 5502.55  432.76
 5551.55  438.55 6880.06  434.01 9241.59  438.66 9378.37  439.81    9380   449.5
   13375   449.5   13380   438.3 13473.4     42213592.98     41814093.83     422
14146.09     43214752.67     434 14820.7   404.514902.11  410.4214928.83     428
14999.68     434 15145.7     437 15172.7     443 15300.7     43515620.13     436
15686.37  422.2715970.38  415.8916144.95  418.0316192.98     44416324.36     456
#Mann= 9 ,-1,0
  502.22    .055       0 5486.05     .05       0 5551.55     .08       0
   13380    .045       014146.09    .065       014752.67     .05       0
14999.68     .12       0 15145.7     .06       0 15172.7     .12       0
#XS Ineff= 2 , 0
       014620.61     436 15249.7       0     445
Permanent Ineff=
       F       T
Bank Sta=14752.67,14999.68
XS Rating Curve= 0 ,0
Exp/Cntr=0.3,0.1

Type RM Length L Ch R = 1 ,42949   ,959,210,80
BEGIN DESCRIPTION:
This cross section corresponds to cross section 42961 of the non-georeferenced CDC model which was the source of this model.
END DESCRIPTION:
XS GIS Cut Line= 6
  2433756.997022 6975764.3681102 2433380.5187728 6972596.3711653
 2432992.1888408 6969329.3809802 2432773.6699208 6966280.6098467
 2432482.0799528 6964227.1884287   2432204.33707   6962271.55192
#Sta/Elev= 30
       0  458.32  651.49  433.78 2493.22  437.83 2563.56     432 2597.63     438
 5743.17     426 5746.48  432.47 5774.92  429.14 5808.16  437.78  6252.6   449.5
   10400   449.510700.38     44010827.49     42010907.34     41811127.15  419.34
11188.12     43211707.37     43412131.79  434.61   12199   404.512272.56  410.98
12334.37  435.31   12481     436   12506     442   12586     442   12623     433
12892.35     44613038.21   444.6 13111.5     43613285.71  434.1913530.27     454
#Mann= 10 ,-1,0
       0    .055       0 2493.22     .05       0 2597.63     .08       0
   10400    .045       011188.12     .06       011707.37    .075       0
12131.79     .05       012334.37     .12       0   12481     .06       0
   12506     .12       0
#XS Ineff= 2 , 0
       012021.51     436   12586       0     442
Permanent Ineff=
       F       T
Bank Sta=12131.79,12334.37
XS Rating Curve= 0 ,0
Exp/Cntr=0.3,0.1

Type RM Length L Ch R = 1 ,42739   ,295,371,363
BEGIN DESCRIPTION:
This cross section corresponds to cross section 42751 of the non-georeferenced CDC model which was the source of this model.
END DESCRIPTION:
XS GIS Cut Line= 6
   2434894.38169 6975098.5194684 2433623.2600852 6969551.4290925
 2433619.7614045 6969451.9460237 2433509.1149722 6966463.8066588
 2433107.9458271 6965164.6596508 2432206.9518942 6962279.9246067
#Sta/Elev= 30
       0  454.74  901.57  431.71 2177.29     436 2273.31  434.17 2290.27     426
 2323.98     438 2341.81     434 2421.07  433.52 4211.51  429.08 4766.46     428
 5468.73     426 5946.82     438 5958.78  439.45  5963.2   449.510289.95     448
10381.16     43210536.37     41810973.11  418.1811378.03     43411803.32  434.59
11851.23     410 11883.5   404.811938.17  410.5511994.12     434 12141.5     435
 12169.5     44212380.89  432.1712548.39  446.5112882.52     43413162.44     454
#Mann= 12 ,-1,0
       0    .065       0 2341.81     .05       0 2421.07     .08       0
 4211.51     .05       0 4766.46    .075       010289.95    .035       0
10381.16    .045       011378.03    .085       011803.32     .05       0
11994.12     .12       0 12141.5     .06       0 12169.5     .12       0
#XS Ineff= 2 , 0
       0 11679.3     436 12241.5       0     442
Permanent Ineff=
       F       T
Bank Sta=11803.32,11994.12
XS Rating Curve= 0 ,0
Exp/Cntr=0.3,0.1

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
Type RM Length L Ch R = 1 ,41686   ,703,3622,3928
BEGIN DESCRIPTION:
This cross section corresponds to cross section 41697 of the non-georeferenced CDC model which was the source of this model.
---------------------------------------------------------------------
LOMR # 16-06-2467P Running Bear Park Levee reflected in LOB.
---------------------------------------------------------------------
END DESCRIPTION:
XS GIS Cut Line= 6
  2435190.386695 6974832.8061043 2434905.2466944 6971739.3092312
 2434627.8902938 6968730.9185944 2434087.7909803 6965372.5119254
 2433727.3727378 6963816.1361012 2433389.4469045 6962357.0379695
#Sta/Elev= 30
       0  448.76     469  441.95  716.11  429.74  1349.4  440.08 2072.76  433.38
 2699.91  433.36    2719     426    2747     431 3290.84  431.23    3533  422.14
 3769.76  429.88 5470.74   426.1 5489.52     434 5607.24   429.6 5695.09   449.4
10050.02     450 10140.5     432 10296.7     41810793.14  419.5810930.77     434
 11773.7  433.9611822.75     410 11858.7   404.411896.72  410.0711916.56     426
11942.83     43211953.44     43412139.03  451.9412518.51     436 12624.6     444
#Mann= 11 ,-1,0
       0    .065       0 2072.76     .08       0 2699.91     .05       0
    2747    .075       0 3290.84     .04       0 3769.76    .075       0
10050.02    .035       0 10140.5    .045       010930.77    .085       0
 11773.7     .05       011942.83     .06       0
#XS Ineff= 2 , 0
       0 11773.7  433.96               0
Permanent Ineff=
       F       F
#Block Obstruct= 2 , 0
       0                   12136       0   451.7
Bank Sta=11773.7,11953.44
XS Rating Curve= 0 ,0
Exp/Cntr=0.3,0.1

Type RM Length L Ch R = 1 ,38065   ,770,209,217
BEGIN DESCRIPTION:
This cross section corresponds to cross section 38059 of the non-georeferenced CDC model which was the source of this model.
END DESCRIPTION:
XS GIS Cut Line= 6
2435554.826474776974938.42010256 2435749.6282077  6969102.156369
 2435661.4889483  6965868.123467 2436432.5313695 6965535.1343036
 2436599.6320852 6964389.3009653 2437280.4043457 6962733.3626761
#Sta/Elev= 30
   -1508     456  343.27  438.19  426.76  427.24  615.23  437.76  658.13  429.54
 1394.74  430.32    1444     432  1800.4   431.6    2046  421.65  2288.4   431.6
 3533.25  429.56    3574   438.8    3694   438.8 3734.96  429.15 4277.66     426
 4403.05   448.3    7600     450 7714.85  430.58 7932.69     416 8159.45  417.68
 8240.12  428.2310774.35  433.7110806.32  425.9910823.78     41010862.19     405
 10900.6  410.1510954.14  433.3910955.89     43411110.31     46011354.83  471.19
#Mann= 10 ,-1,0
   -1508    .065       0 1394.74     .05       0    1444     .08       0
  1800.4     .04       0  2288.4     .08       0    7600    .035       0
 7714.85    .045       0 8240.12      .1       010774.35    .055       0
10954.14    .065       0
#XS Ineff= 2 , 0
       010774.35  433.71               0
Permanent Ineff=
       F       F
Bank Sta=10774.35,10955.89
XS Rating Curve= 0 ,0
Exp/Cntr=0.3,0.1

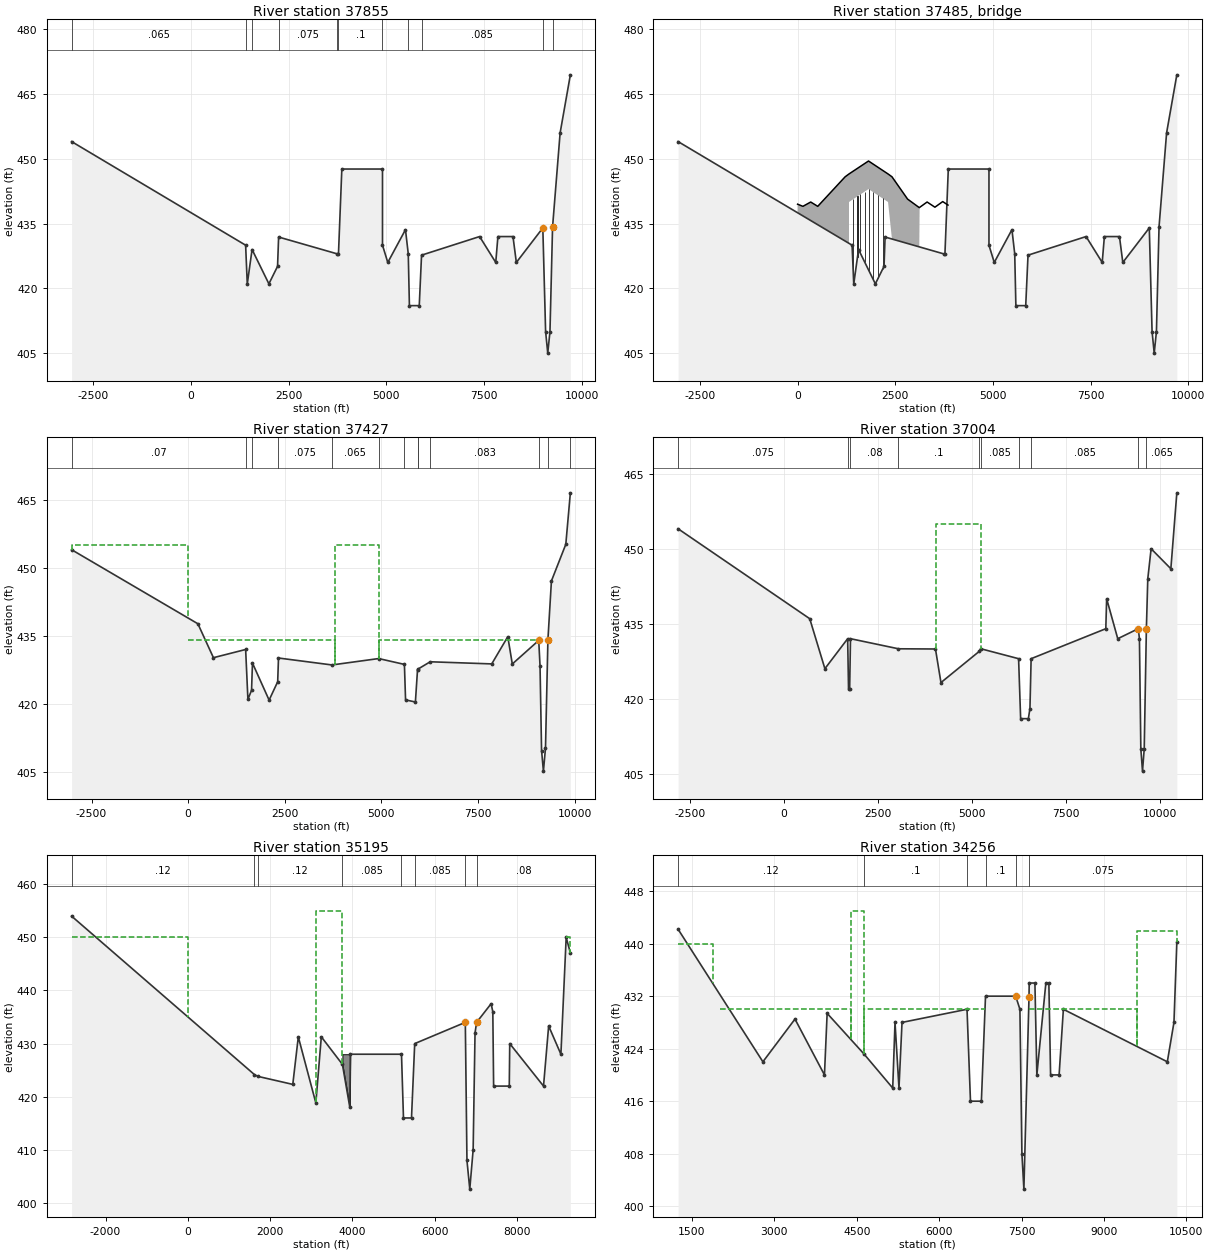
Type RM Length L Ch R = 1 ,37855   ,187,428,428
BEGIN DESCRIPTION:
This cross section corresponds to cross section 37866 of the non-georeferenced CDC model which was the source of this model.
END DESCRIPTION:
XS GIS Cut Line= 6
2436131.889009176975308.98213912 2436131.6080868 6969150.7218887
 2436144.5601607 6969044.5088465 2436457.0890632 6966787.1573901
 2436742.4759596 6964726.1011447 2437486.3639075 6962714.0569405
#Sta/Elev= 30
   -3060     454  1395.6     430 1437.89     421  1560.6     429  1991.1  421.05
  2213.1   425.1 2240.28  431.89 3737.69     428 3772.86     428 3858.86  447.64
    4900  447.64    4900     430  5035.5     426 5488.37   433.6 5559.52     428
 5589.05     416 5841.23     416 5899.89  427.69 7386.27     432  7799.7     426
 7854.91     432 8241.02     432 8326.98     426 9004.99     434 9076.18     410
    9131     405 9187.95     410 9254.37  434.22 9447.76     456 9710.02  469.46
#Mann= 11 ,-1,0
   -3060    .065       0  1395.6     .05       0  1560.6     .04       0
 2240.28    .075       0 3737.69    .065       0 3772.86      .1       0
    4900    .085       0 5559.52    .045       0 5899.89    .085       0
 9004.99    .055       0 9254.37    .065       0
#XS Ineff= 2 , 0
       0 9004.99     434               0
Permanent Ineff=
       F       F
Bank Sta=9004.99,9254.37
XS Rating Curve= 0 ,0
Exp/Cntr=0.3,0.1

Type RM Length L Ch R = 3 ,37485   ,,,
BEGIN DESCRIPTION:
Hunter Ferrell Road
END DESCRIPTION:
Node Name=Hunter Ferrell R
Bridge Culvert--1,0,-1,-1, 0
Deck Dist Width WeirC Skew NumUp NumDn MinLoCord MaxHiCord MaxSubmerge Is_Ogee
92,115,2.6,0, 17, 17, , , 0.95, 0, 0,0,,
       0     136     336   516.1  1216.1  1316.1  1316.1  1816.1  2316.1  2316.1
  2416.1  2816.1  3116.1  3316.1  3516.1  3716.1  3851.1
   439.5     439     440     439  445.83   446.5   446.5   449.5   446.5   446.5
  445.85  440.68   438.7     440   438.8   440.1  439.29
                                                     440     443     440
       0     136     336  642.15 1342.15 1442.15 1442.15 1942.15 2442.15 2442.15
 2542.15 2942.15 3242.15 3442.15 3642.15 3842.15 3977.15
   439.5     439     440     439  445.83   446.5   446.5   449.5   446.5   446.5
  445.85  440.68   438.7     440   438.8   440.1  439.29
                                                     440     443     440
Pier Skew, UpSta & Num, DnSta & Num=  ,1425.1, 2 ,1529.5, 2 , 0 , 0 , 0 ,,
       3       3
     415     443
       3       3
     415     443
Pier Skew, UpSta & Num, DnSta & Num=  ,1535.1, 2 ,1639.5, 2 , 0 , 0 , 0 ,,
       3       3
     415     443
       3       3
     415     443
Pier Skew, UpSta & Num, DnSta & Num=  ,1607.26, 2 ,1711.66, 2 , 0 , 0 , 0 ,,
       3       3
     415     443
       3       3
     415     443
Pier Skew, UpSta & Num, DnSta & Num=  ,1721.26, 2 ,1825.66, 2 , 0 , 0 , 0 ,,
       3       3
     415     443
       3       3
     415     443
Pier Skew, UpSta & Num, DnSta & Num=  ,1824, 2 ,1928.4, 2 , 0 , 0 , 0 ,,
       3       3
     415     443
       3       3
     415     443
Pier Skew, UpSta & Num, DnSta & Num=  ,1942, 2 ,2046.43, 2 , 0 , 0 , 0 ,,
       3       3
     415     443
       3       3
     415     443
Pier Skew, UpSta & Num, DnSta & Num=  ,2060, 2 ,2164.43, 2 , 0 , 0 , 0 ,,
       3       3
     415     443
       3       3
     415     443
Pier Skew, UpSta & Num, DnSta & Num=  ,2178, 2 ,2282.43, 2 , 0 , 0 , 0 ,,
       3       3
     415     443
       3       3
     415     443
Abutment Skew #Up #Dn= , 2 , 2
  1316.1  1396.1
     440     420
 1442.15 1522.15
     440     420
Abutment Skew #Up #Dn= , 2 , 2
    2236  2316.1
     420     440
 2362.15 2442.15
     420     440
BR Coef=-1 , 0 , 0 ,, 0 ,,,0.8,0,1.2,0,
WSPro=,,,, 1 ,,,, 0 ,,,, 0 ,,,,-1 ,-1 ,-1 , 0 , 0 , 0 , 0 , 0
BC Design=,, 0 ,, 0 ,,,,,,
BC Use User HTab Curves=0
BC User HTab FreeFlow(D)= 0

Type RM Length L Ch R = 1 ,37427   ,423,423,423
BEGIN DESCRIPTION:
This cross section corresponds to cross section 37566 of the non-georeferenced CDC model which was the source of this model.
---------------------------------------------------------------------
CDC IRV081607-01 Hunter Ferrell Road Improvements
Cross-section 37566 - 41697
---------------------------------------------------------------------
END DESCRIPTION:
XS GIS Cut Line= 6
2436329.184343616975557.11367137     2436354.375     6969200.773
     2437116.528     6964755.894     2437642.492     6963499.962
     2437719.337     6963350.069     2438012.405     6962933.117
#Sta/Elev= 30
   -3015     454  252.59  437.67  654.85  430.19  1488.2     432    1547     421
    1641     423    1665     429  2095.5  420.84  2317.5  424.89 2338.42  430.12
 3721.44  428.59 4930.73     430 5596.53  428.71 5626.32  420.89  5880.7  420.42
 5935.55  427.48 5939.87  427.64 6263.96  429.29 7856.31  428.82 8271.45  434.82
  8388.2   428.8 9072.14     434 9105.54   428.4 9145.31  409.72 9193.43  405.18
 9247.12  410.28 9309.74  434.14 9400.59  447.11 9772.67  455.19 9890.54  466.54
#Mann= 13 ,-1,0
   -3015     .07       0  1488.2     .05       0    1665     .04       0
 2338.42    .075       0 3721.44    .065       0 4930.73    .085       0
 5596.53     .05       0 5935.55    .071       0 5939.87    .071       0
 6263.96    .083       0 9072.14    .055       0 9309.74    .065       0
 9890.54    .065       0
#XS Ineff= 4 ,-1
       0    3800     434    3800    4948     455    4948 9072.14     434
   -3015       0     455
Permanent Ineff=
       F       F       F       F
Bank Sta=9072.14,9309.74
XS Rating Curve= 0 ,0
Exp/Cntr=0.3,0.1

Type RM Length L Ch R = 1 ,37004   ,732,1810,1504
BEGIN DESCRIPTION:
This cross section corresponds to cross section 37015 of the non-georeferenced CDC model which was the source of this model.
END DESCRIPTION:
XS GIS Cut Line= 6
2436543.657249816975906.95023638 2436589.3968694 6972878.6783435
 2436597.8515769 6972023.9274283 2436597.6829421 6969156.6519949
  2437479.554866 6964906.8940902 2438355.5619722 6962905.7901528
#Sta/Elev= 30
   -2825     454  680.82     436 1084.36     426  1690.5     432 1713.73     422
 1743.65     422 1766.01     432    3044  429.98 4028.45  429.94 4174.51  423.22
    5200   429.5    5230     430 6241.83     428  6296.2     416  6501.7     416
 6544.24     418 6575.47     428 8564.02     434 8586.23     440 8882.11     432
 9428.39     434  9459.4     432 9496.32     410    9541   405.5 9587.13     410
 9644.33     434 9681.73     444 9770.36     45010295.96     44610454.99  461.19
#Mann= 10 ,-1,0
   -2825    .075       0  1690.5     .05       0 1766.01     .08       0
    3044      .1       0    5200      .1       0    5230    .085       0
 6241.83    .045       0 6575.47    .085       0 9428.39    .055       0
 9644.33    .065       0
#XS Ineff= 1 ,-1
    4030    5230     455
Permanent Ineff=
       F
Bank Sta=9428.39,9644.33
XS Rating Curve= 0 ,0
Exp/Cntr=0.3,0.1

Type RM Length L Ch R = 1 ,35195   ,411,938,901
BEGIN DESCRIPTION:
This cross section corresponds to cross section 35205 of the non-georeferenced CDC model which was the source of this model.
END DESCRIPTION:
XS GIS Cut Line= 6
2437023.32523453 6974807.8117066 2437086.9480397 6971651.6624248
 2437087.0700867 6969165.9708739 2437672.7779048 6967281.6327791
 2438229.2610438  6965491.521858 2439856.7000461 6963416.2750242
#Sta/Elev= 30
   -2825     454 1621.39  424.16 1703.39  423.83 2553.24  422.32 2687.39  431.26
 3113.89  418.83 3246.96  431.28    3760  426.09 3940.26     418 3952.48     428
  5196.6     428 5244.83     416 5439.96     416 5518.02     430 6748.51     434
 6788.34     408    6857   402.6 6938.95     410 6984.78     432 7023.02     434
 7375.95  437.51 7417.23     436 7436.85     422 7817.63     422 7828.68     430
 8650.17     422 8775.02  433.32 9072.88     428  9201.1     450 9302.89  447.09
#Mann= 8 ,-1,0
   -2825     .12       0 1621.39    .055       0 1703.39     .12       0
    3760    .085       0  5196.6    .045       0 5518.02    .085       0
 6748.51    .055       0 7023.02     .08       0
#XS Ineff= 3 ,-1
    3110    3760     455  9201.1 9302.89     450   -2825       0     450
Permanent Ineff=
       F       T       F
#Block Obstruct= 1 ,-1
    3760    3953     428
Bank Sta=6748.51,7023.02
XS Rating Curve= 0 ,0
Exp/Cntr=0.3,0.1

Type RM Length L Ch R = 1 ,34256   ,672,902,305
BEGIN DESCRIPTION:
This cross section corresponds to cross section 34268 of the non-georeferenced CDC model which was the source of this model.
STATIONS 7543-7573 ADDED FROM EFFECTIVE SECTION
FOR FLOWLINE
END DESCRIPTION:
XS GIS Cut Line= 6
  2437489.231482 6971974.3446556 2437489.3931009 6969173.6319478
 2438052.3463713 6967740.4245124 2438650.5371041 6966217.6529516
 2439213.2738395 6965876.4180698 2440272.3609602 6963674.9818559
#Sta/Elev= 30
    1249   442.2 2793.01     422 3376.86  428.51  3913.3     420 3962.13  429.38
 4627.69  423.24 5155.75     418 5197.43     428 5269.62     418 5325.11     428
 6507.97     430    6571     416 6769.38     416 6844.63     432 7393.73     432
 7470.61     430 7506.88     408    7543   402.6 7636.07  431.81 7639.87     434
 7743.76     434 7778.93     420 7943.02     434 7997.58     434 8028.91     420
 8184.18     420 8261.76     43010153.69     42210274.37     42810326.63   440.2
#Mann= 6 ,-1,0
    1249     .12       0 4627.69      .1       0 6507.97    .045       0
 6844.63      .1       0 7393.73    .055       0 7639.87    .075       0
#XS Ineff= 6 ,-1
    1249    1878     440 2003.31    4389     430 4389.04 4626.26     445
 4626.26    6844     430    7639    9600     430    960010326.63     442
Permanent Ineff=
       F       F       T       F       F       F
Bank Sta=7393.73,7636.07
XS Rating Curve= 0 ,0
Exp/Cntr=0.3,0.1