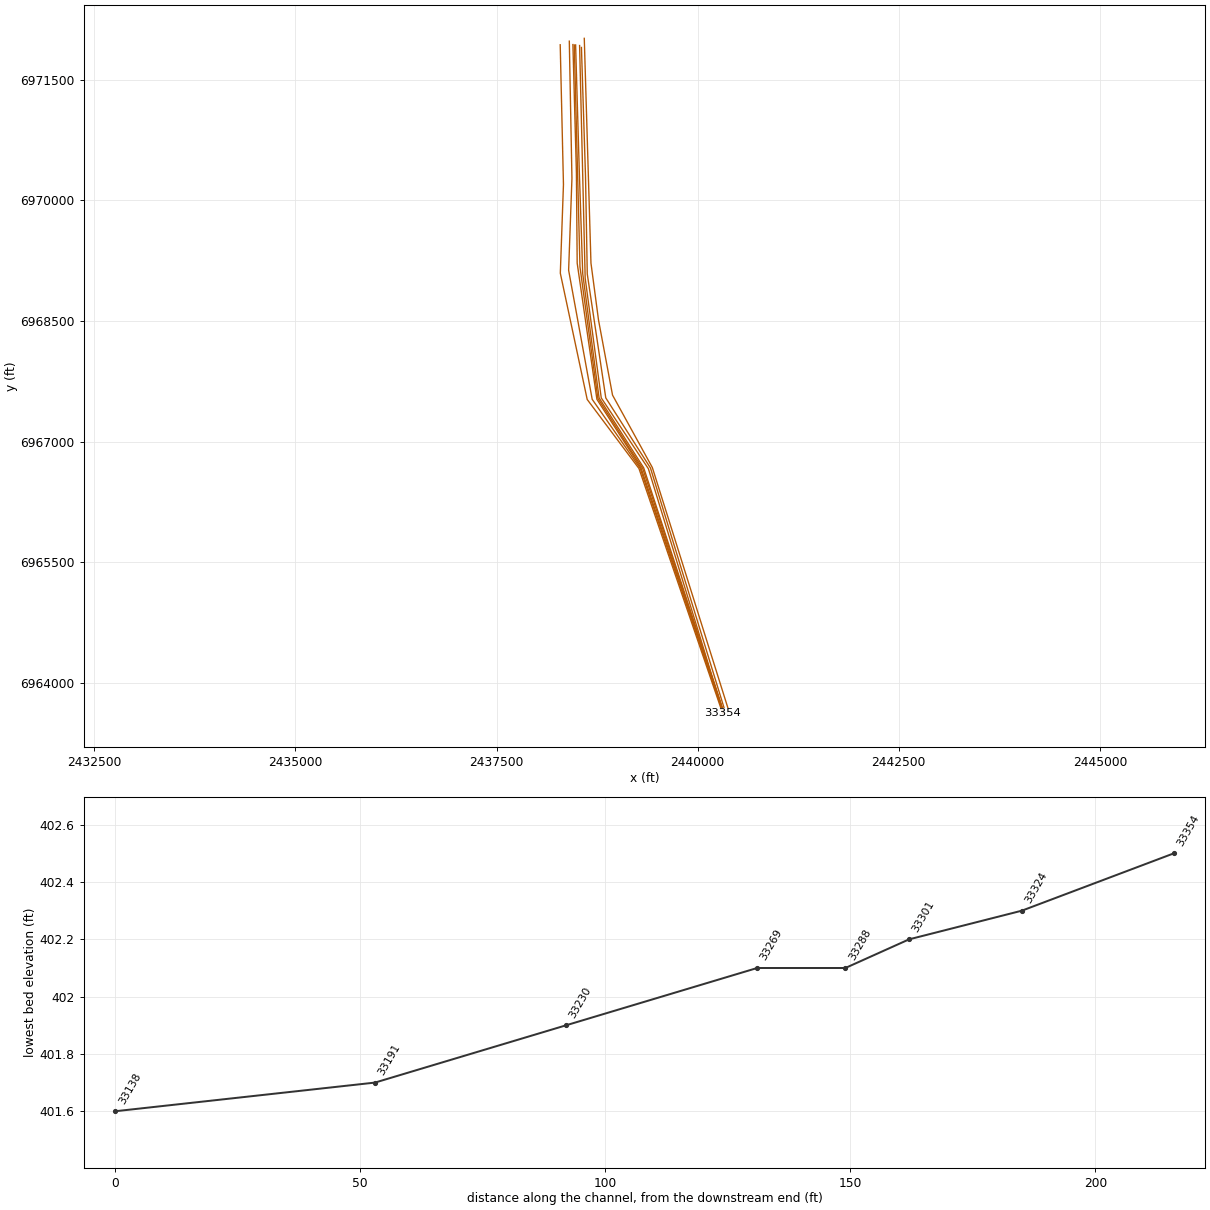
HEC-RAS study CDC_Consolidated_Model.prj: Upper Trinity CDC Consolidated Model

--- CDC_Consolidated_Model.g02 (geometry) --- (continued)

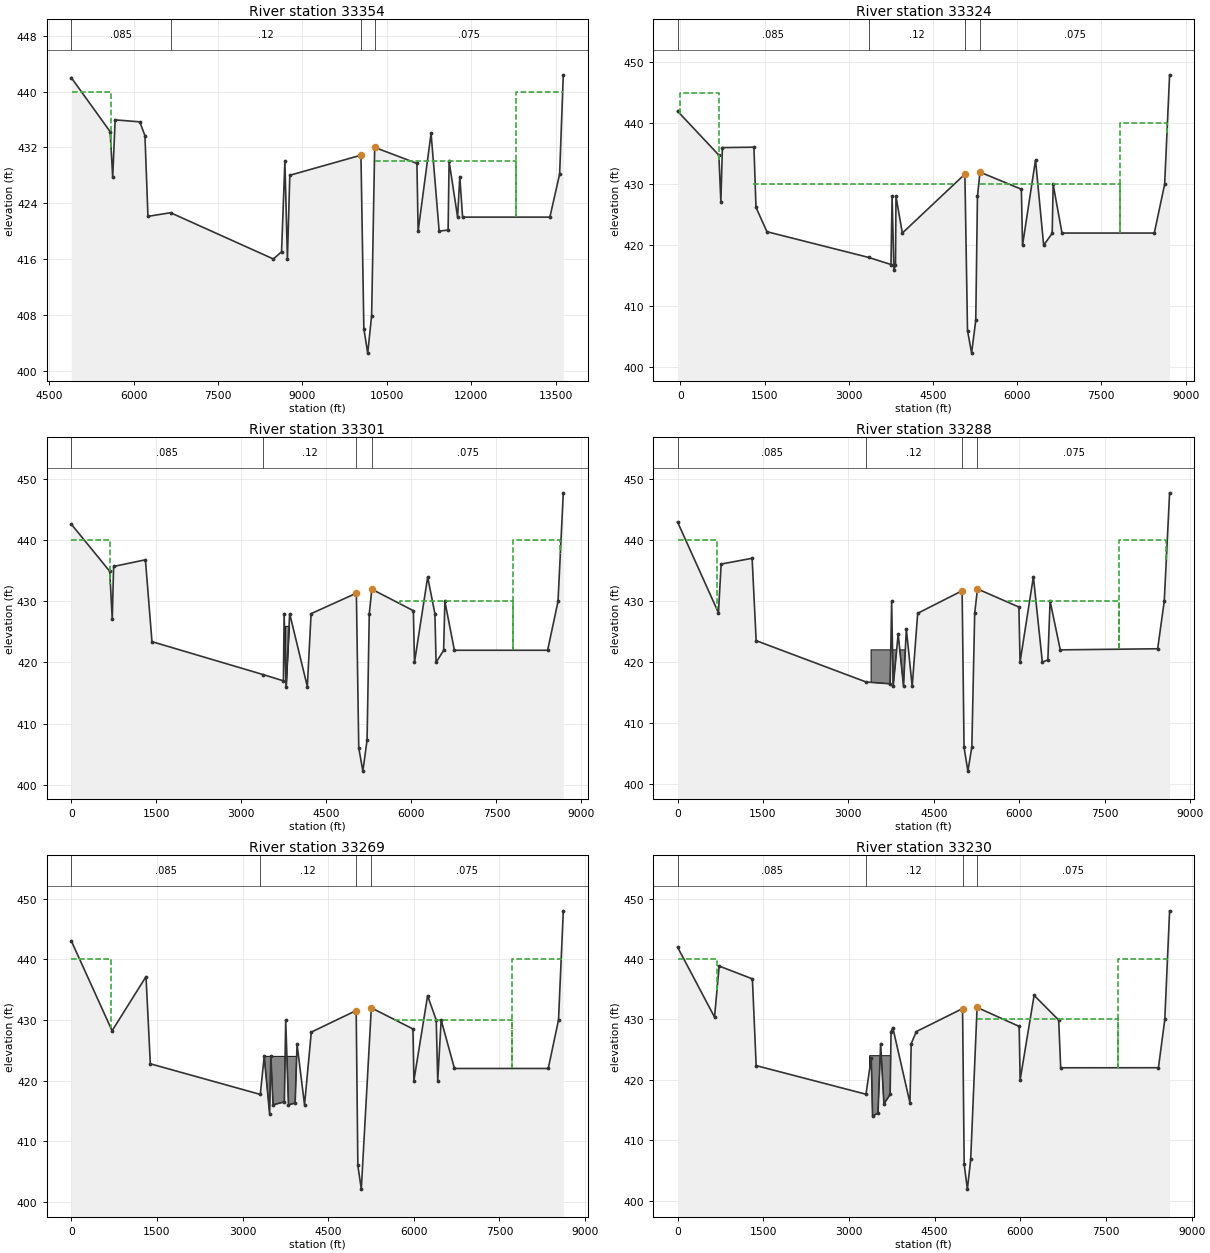
Type RM Length L Ch R = 1 ,33354   ,37,31,7
BEGIN DESCRIPTION:
This cross section corresponds to cross section 33382 of the non-georeferenced CDC model which was the source of this model.
END DESCRIPTION:
XS GIS Cut Line= 6
2438291.259691846971935.47088762  2438331.631902 6970196.5311487
 2438292.5693161 6969094.1006108 2438626.7707474 6967522.9200262
  2439270.000104  6966664.413213  2440310.726369 6963618.0446338
#Sta/Elev= 30
    4890     442 5581.54  434.25 5626.66  427.69 5669.97  435.94 6107.35  435.66
 6199.87  433.68 6253.14  422.11 6654.71  422.63 8482.86     416 8628.25  417.03
  8687.4  429.99 8732.44     416 8775.09     42810039.77  430.8810091.57     406
   10160   402.510229.52  407.8710283.96     432 11034.7   429.711056.13     420
11286.22     43411430.16     42011589.17  420.1411606.73     43011757.83     422
11797.07  427.8111846.53     42213398.52     422 13571.5  428.1613636.92   442.4
#Mann= 4 ,-1,0
    4890    .085       0 6654.71     .12       010039.77    .055       0
10283.96    .075       0
#XS Ineff= 4 ,-1
    4895    5601     440    6137    9895     430   10283   12790     430
   12790   13636     440
Permanent Ineff=
       T       F       F       F
Bank Sta=10039.77,10283.96
XS Rating Curve= 0 ,0
Exp/Cntr=0.3,0.1

Type RM Length L Ch R = 1 ,33324   ,57,23,13
BEGIN DESCRIPTION:
This cross section corresponds to cross section 33335 of the non-georeferenced CDC model which was the source of this model.
END DESCRIPTION:
XS GIS Cut Line= 6
2438404.312439446971980.21623686  2438437.076573 6970272.2472047
 2438395.8440439 6969130.7540808 2438688.8126181 6967524.8511246
  2439284.515823 6966668.7314458 2440320.4317302 6963618.9268499
#Sta/Elev= 30
     -50     442  685.59  434.78  721.21  427.12  748.19  436.02 1310.33  436.09
 1346.95  426.21 1542.07  422.22 3354.07     418 3751.43  416.84 3771.72     428
 3803.44     416  3832.1   416.7 3840.67     428    3954     422 5068.05  431.67
 5115.05     406    5188   402.3 5261.81   407.7 5291.99     428 5337.17     432
 6074.34  429.19 6095.09     420 6326.51     434 6471.56     420 6623.51  421.96
 6640.13     430 6798.23     422 8442.34     422 8626.45     430 8714.93  447.96
#Mann= 4 ,-1,0
     -50    .085       0 3354.07     .12       0 5068.05    .055       0
 5337.17    .075       0
#XS Ineff= 4 ,-1
     -.5     690     445    1288    4867     430    5337    7840     430
    7840    8667     440
Permanent Ineff=
       T       F       F       F
Bank Sta=5068.05,5337.17
XS Rating Curve= 0 ,0
Exp/Cntr=0.3,0.1

Type RM Length L Ch R = 1 ,33301   ,34,13,9
BEGIN DESCRIPTION:
This cross section corresponds to cross section 33313 of the non-georeferenced CDC model which was the source of this model.
END DESCRIPTION:
XS GIS Cut Line= 6
  2438449.083438 6971937.8288472 2438492.4862391 6970352.5423197
 2438502.2519676 6969218.6446531  2438747.477527 6967524.8511246
 2439295.4377172 6966671.9866886 2440324.8431387 6963618.9268499
#Sta/Elev= 30
       0  442.66  678.57  434.94  722.84  427.09  747.05  435.73 1307.99  436.82
 1423.46  423.41 3390.11     418 3742.22  416.99  3754.7     428 3788.34     416
 3852.63     428 4163.98  416.06 4230.62     428 5029.25  431.35 5071.39     406
    5144   402.2  5217.9   407.3 5256.99     428 5302.07     432 6034.87  428.48
 6054.32     420 6286.96     434 6414.76     428 6435.46     420 6568.16  421.99
  6590.6     430 6758.66     422 8403.08     422 8586.15     430 8679.42  447.79
#Mann= 4 ,-1,0
       0    .085       0 3390.11     .12       0 5029.25    .055       0
 5302.07    .075       0
#XS Ineff= 4 ,-1
       0     690     440    1325    4795     430    5795    7789     430
    7789    8627     440
Permanent Ineff=
       T       F       F       F
#Block Obstruct= 1 ,-1
    3770    3839     426
Bank Sta=5029.25,5302.07
XS Rating Curve= 0 ,0
Exp/Cntr=0.3,0.1

Type RM Length L Ch R = 1 ,33288   ,29,18,17
BEGIN DESCRIPTION:
This cross section corresponds to cross section 33294 of the non-georeferenced CDC model which was the source of this model.
END DESCRIPTION:
XS GIS Cut Line= 6
  2438466.397708 6971932.2832547 2438536.9011765 6969172.1270296
 2438759.4706132 6967536.5367968  2439181.315242 6966872.0099106
 2439316.3395782  6966666.023446 2440325.2043584 6963620.2086715
#Sta/Elev= 30
       0  442.98   717.8  428.09   765.3  436.08 1308.83  437.03 1380.07  423.51
  3310.3  416.73 3732.68  416.43 3759.42     430 3786.24     416 3874.24   424.6
  3967.7  416.06 4017.49  425.41  4120.3     416 4216.51     428 4996.94   431.7
 5030.93     406  5098.5   402.1 5167.67  406.06 5217.83     428  5266.5     432
 5993.88  429.03 6014.47     420 6248.52     434 6405.88     420 6502.63  420.34
 6541.85     430 6720.75     422 8431.15  422.18  8546.9     430 8640.66  447.77
#Mann= 4 ,-1,0
       0    .085       0  3310.3     .12       0 4996.94    .055       0
  5266.5    .075       0
#XS Ineff= 4 ,-1
       0     690     440    1322    4814     430    5795    7745     430
    7745    8582     440
Permanent Ineff=
       T       F       F       F
#Block Obstruct= 1 ,-1
    3398    4017     422
Bank Sta=4996.94,5266.5
XS Rating Curve= 0 ,0
Exp/Cntr=0.3,0.1

Type RM Length L Ch R = 1 ,33269   ,35,39,21
BEGIN DESCRIPTION:
This cross section corresponds to cross section 33267 of the non-georeferenced CDC model which was the source of this model.
END DESCRIPTION:
XS GIS Cut Line= 6
  2438482.626678 6971933.4085805 2438526.8975876 6970412.5753361
 2438571.1681683 6969087.0543651 2438774.2934182 6967542.7835035
 2439328.9806291  6966672.991936 2440325.7256828 6963620.6916101
#Sta/Elev= 30
       0  443.06  715.21  428.22 1309.13  437.15 1384.98  422.77 3311.17  417.72
 3379.19     424  3473.6  414.57 3495.88     424 3534.83     416 3732.06  416.49
    3756     430 3804.84     416  3921.5   416.3 3954.56     426 4085.74     416
  4204.4     428 4990.42  431.55 5019.67     406    5080   402.1 5255.59     432
 5984.58  428.52  6001.4     420 6241.36     434 6392.41     430 6418.87     420
  6478.8     430 6711.57     422 8354.55     422 8534.31     430 8618.13     448
#Mann= 4 ,-1,0
       0    .085       0 3311.17     .12       0 4990.42    .055       0
 5255.59    .075       0
#XS Ineff= 4 ,-1
       0     690     440    1301    4782     430    5645    7714     430
    7714    8580     440
Permanent Ineff=
       T       F       F       F
#Block Obstruct= 1 ,-1
    3378    3953     424
Bank Sta=4990.42,5255.59
XS Rating Curve= 0 ,0
Exp/Cntr=0.3,0.1

Type RM Length L Ch R = 1 ,33230   ,76,39,24
BEGIN DESCRIPTION:
This cross section corresponds to cross section 33220 of the non-georeferenced CDC model which was the source of this model.
END DESCRIPTION:
XS GIS Cut Line= 6
  2438532.237143 6971926.2183062 2438601.6815588 6969031.2532956
 2438801.3343747 6967542.5377691 2439387.2718511 6966661.4614472
 2440174.6144365 6964094.3209122 2440326.7896571 6963622.5708715
#Sta/Elev= 30
       0  441.98  647.03   430.4   728.1  438.85  1309.7  436.73 1375.63  422.36
 3297.73  417.62 3390.82  423.64 3412.93     414 3508.32  414.49 3554.53     426
 3611.89     416 3720.65  417.58 3737.11     428 3767.38  428.66 4067.54  416.19
 4089.48     426 4179.87     428 4988.64  431.81 5016.95     406    5073   401.9
 5130.83  406.81 5242.89     432 5979.18  428.86 5996.39     420 6241.17     434
 6671.55   429.9 6705.82     422 8417.35  422.01 8528.57     430 8612.74     448
#Mann= 4 ,-1,0
       0    .085       0 3297.73     .12       0 4988.64    .055       0
 5242.89    .075       0
#XS Ineff= 4 ,-1
       0     687     440    1320    4853     430    5243    7705     430
    7705    8573     440
Permanent Ineff=
       T       F       F       F
#Block Obstruct= 1 ,-1
    3362    3737     424
Bank Sta=4988.64,5242.89
XS Rating Curve= 0 ,0
Exp/Cntr=0.3,0.1

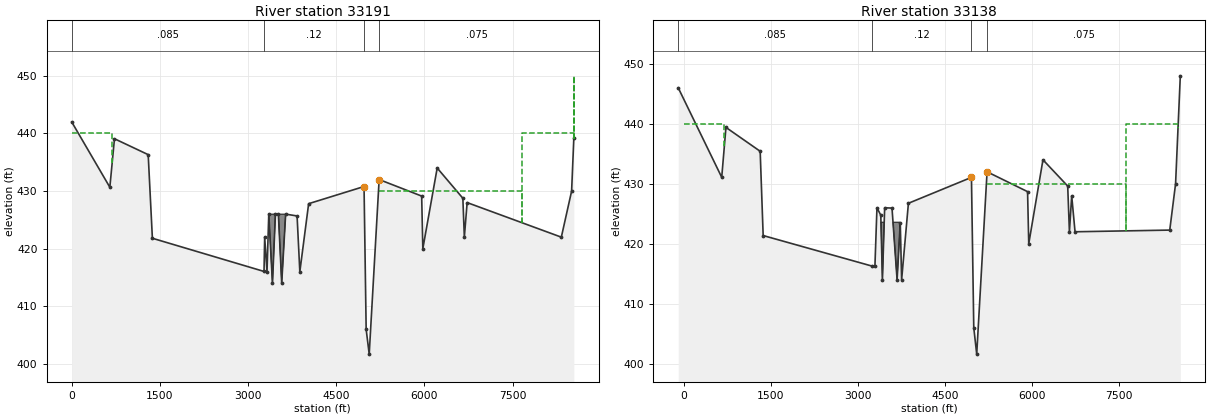
Type RM Length L Ch R = 1 ,33191   ,121,53,26
BEGIN DESCRIPTION:
This cross section corresponds to cross section 33188 of the non-georeferenced CDC model which was the source of this model.
END DESCRIPTION:
XS GIS Cut Line= 6
  2438555.120912 6971901.7966485 2438606.0217732 6970289.9338491
 2438627.7231733 6969083.3365247 2438857.7581463 6967542.5377691
 2439413.3134657 6966670.1422042 2440331.1514135 6963676.4437544
#Sta/Elev= 30
       0  441.98  647.84  430.66  726.52  439.08 1300.35  436.32 1371.67  421.81
  3271.2  416.05 3282.27     422 3321.97  416.01 3352.08     426 3414.85     414
 3465.11     426 3516.09  425.95    3572     414 3639.22     426 3833.73  425.68
 3880.52     416 4030.41  427.81 4973.02  430.79 5009.14     406    5061   401.7
 5230.03     432 5953.65  429.13 5973.27     420 6217.76     434 6654.42  428.75
 6679.69     422 6727.25     428 8329.99     422 8504.98     430 8542.89  439.24
#Mann= 4 ,-1,0
       0    .085       0  3271.2     .12       0 4973.02    .055       0
 5230.03    .075       0
#XS Ineff= 5 ,-1
       0     687     440    1320    4973     430    5230    7662     430
    7662    8542     440    8542 8542.89     450
Permanent Ineff=
       T       F       F       F       F
#Block Obstruct= 1 ,-1
    3352    3639     426
Bank Sta=4973.02,5230.03
XS Rating Curve= 0 ,0
Exp/Cntr=0.3,0.1

Type RM Length L Ch R = 1 ,33138   ,221,89,30
BEGIN DESCRIPTION:
This cross section corresponds to cross section 33136 of the non-georeferenced CDC model which was the source of this model.
END DESCRIPTION:
XS GIS Cut Line= 6
2438590.401429576972015.51360178 2438673.4770188 6969220.4169592
 2438767.2271594 6968512.0837302 2438941.7061412 6967577.1876342
 2439436.4978025 6966676.1461292 2440386.2980214  6963652.287014
#Sta/Elev= 30
    -100     446  649.96  431.08  722.97   439.4 1313.22  435.42 1364.85  421.37
 3241.53  416.28 3292.24  416.23 3327.43     426 3393.52  424.76 3421.65     414
 3460.22     426 3586.96  425.95 3674.75     414  3729.4  423.52 3752.83     414
  3869.9  426.75 4957.16  431.07 4997.22     406    5048   401.6 5226.59     432
 5924.98  428.69  5945.4     420 6190.62     434  6617.3  429.62 6646.77     422
 6686.18     428  6743.7     422 8377.38  422.28 8477.76     430 8559.47     448
#Mann= 4 ,-1,0
    -100    .085       0 3241.53     .12       0 4957.16    .055       0
 5226.59    .075       0
#XS Ineff= 4 ,-1
       0     693     440    1300    4815     430    5227    7618     430
    7618    8520     440
Permanent Ineff=
       T       F       F       F
#Block Obstruct= 1 ,-1
    3327    3717   423.6
Bank Sta=4957.16,5226.59
XS Rating Curve= 0 ,0
Exp/Cntr=0.3,0.1