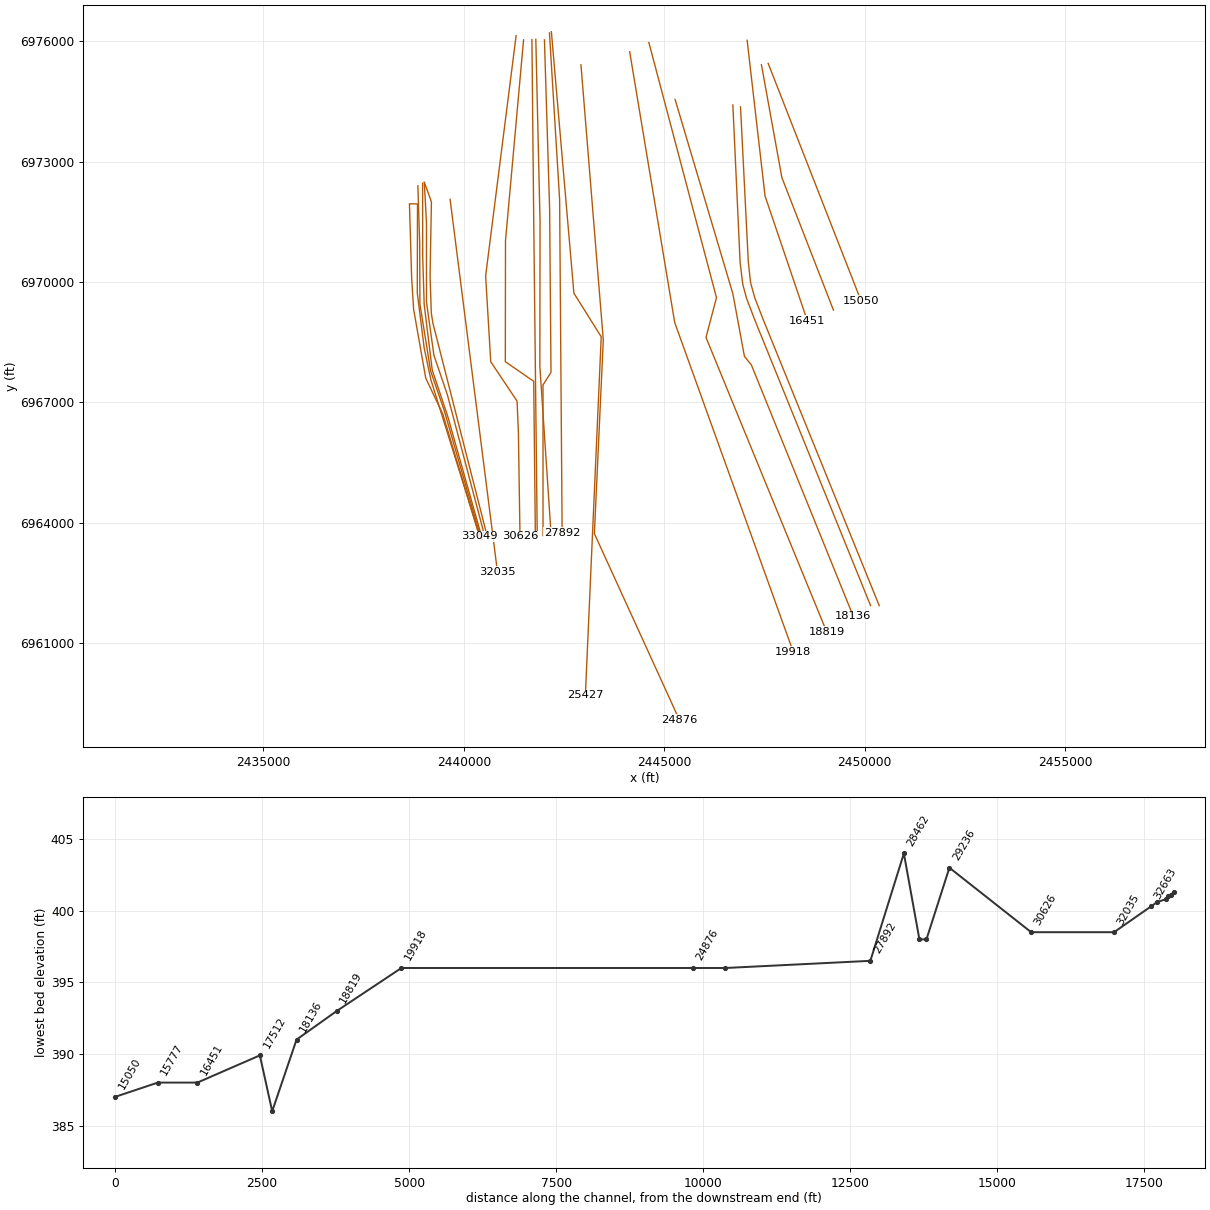
HEC-RAS study CDC_Consolidated_Model.prj: Upper Trinity CDC Consolidated Model

--- CDC_Consolidated_Model.g02 (geometry) --- (continued)

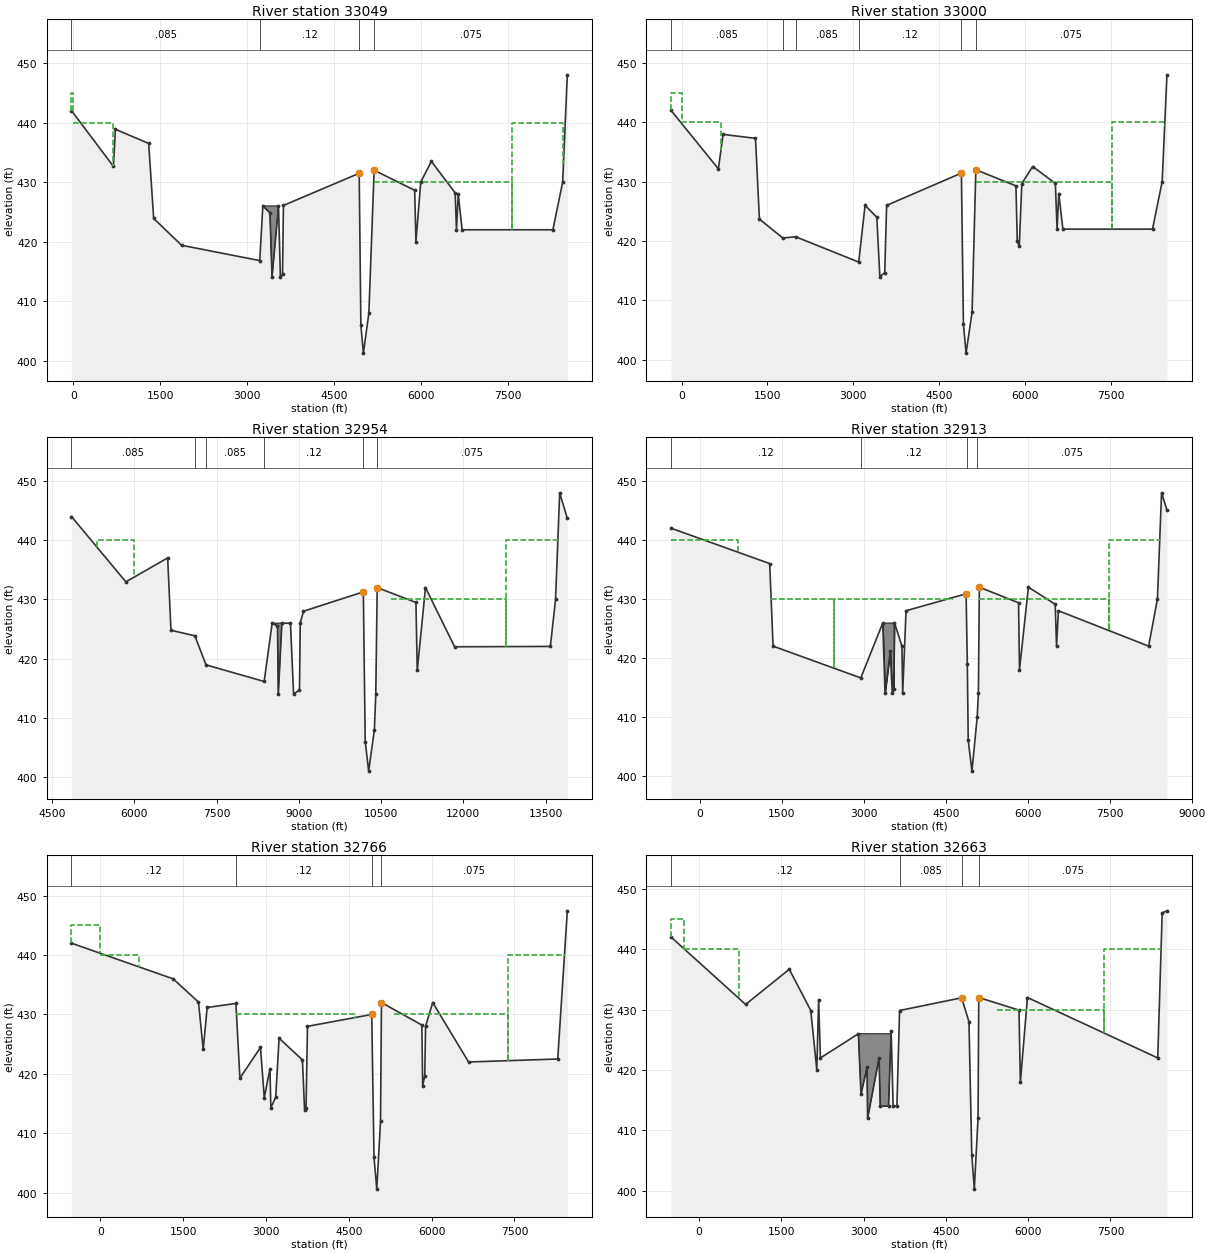
Type RM Length L Ch R = 1 ,33049   ,196,49,21
BEGIN DESCRIPTION:
This cross section corresponds to cross section 33062 of the non-georeferenced CDC model which was the source of this model.
END DESCRIPTION:
XS GIS Cut Line= 6
2438644.562984596971946.22990404 2438699.5186334 6970095.4168496
 2438748.9978652 6969314.1670998 2439051.0812505 6967600.6252513
 2439478.1643858 6966699.5837463 2440390.0312769  6963658.915321
#Sta/Elev= 30
     -30     442  693.06  432.63  727.78  438.86 1301.06  436.49 1386.77  423.91
 1867.57   419.4 3215.26  416.83 3269.16     426 3391.74  424.83 3426.82     414
 3538.61  425.96 3571.63     414  3608.2  414.51 3623.64  426.08 4929.56  431.48
 4958.48     406    5002   401.3 5096.21     408 5187.05     432 5885.88  428.62
 5907.44     420 5990.47     430 6173.44  433.48 6583.87  428.19 6606.15     422
 6637.21     428 6703.77     422  8268.2     422 8436.84     430 8516.96     448
#Mann= 4 ,-1,0
     -30    .085       0 3215.26     .12       0 4929.56    .055       0
 5187.05    .075       0
#XS Ineff= 5 ,-1
       0     683     440    1300    4929     430    5187    7559     430
    7559    8450     440     -30       0     445
Permanent Ineff=
       T       F       F       F       F
#Block Obstruct= 1 ,-1
    3269 3533.41     426
Bank Sta=4929.56,5187.05
XS Rating Curve= 0 ,0
Exp/Cntr=0.3,0.1

Type RM Length L Ch R = 1 ,33000   ,58,45,23
BEGIN DESCRIPTION:
This cross section corresponds to cross section 33014 of the non-georeferenced CDC model which was the source of this model.
END DESCRIPTION:
XS GIS Cut Line= 6
      2438665.14     6971948.509 2438845.4033841 6971945.8300519
 2438840.1436802 6969725.6252664 2439012.0186646 6968353.2293892
  2439178.685326 6967561.5626654 2440395.8313012 6963661.4534976
#Sta/Elev= 30
    -182     442  643.82  432.15  724.93  437.96 1291.08   437.3 1359.37  423.69
 1768.05   420.5 1991.42  420.71 3092.42  416.45 3203.19     426 3408.66     424
 3461.08     414 3546.68  414.65 3579.51     426 4884.41  431.44 4919.89     406
    4966   401.1 5070.81     408 5136.79     432 5836.33  429.29 5859.65     420
 5893.81  419.08 5939.06  429.67 6127.95  432.55 6523.96  429.71  6554.5     422
 6583.38     428 6656.08     422 8219.81     422 8388.13     430 8471.68     448
#Mann= 6 ,-1,0
    -182    .085       0 1768.05    .065       0 1991.42    .085       0
 3092.42     .12       0 4884.41    .055       0 5136.79    .075       0
#XS Ineff= 5 ,-1
       0     688     440    1300    4884     430    5137    7516     430
    7516    8432     440    -182       0     445
Permanent Ineff=
       T       F       F       F       F
Bank Sta=4884.41,5136.79
XS Rating Curve= 0 ,0
Exp/Cntr=0.3,0.1

Type RM Length L Ch R = 1 ,32954   ,46,41,52
BEGIN DESCRIPTION:
This cross section corresponds to cross section 32967 of the non-georeferenced CDC model which was the source of this model.
END DESCRIPTION:
XS GIS Cut Line= 6
2438854.218760676972396.93526111 2438900.0395578 6970957.3960968
 2438905.2478808 6969452.1878212 2439173.4770031 6967777.7085586
 2439514.6229743 6966785.5212385 2440441.6494056 6963559.0698902
#Sta/Elev= 30
    4850     444 5842.93  432.96 6605.26  437.01 6665.52  424.79 7101.22  423.86
 7305.64  418.94 8365.91  416.14 8512.22     426 8609.06  425.49 8624.53     414
 8689.68     426    8846  425.97 8903.09     414  9010.2  414.73 9024.68     426
 9082.24     42810175.69  431.2710210.15     406   10273     40110377.47     408
10403.06     41410428.55     43211135.59  429.48 11159.4     41811309.65     432
11840.67     42213588.32  422.0613682.71     43013758.38     44813897.58  443.68
#Mann= 6 ,-1,0
    4850    .085       0 7101.22    .065       0 7305.64    .085       0
 8365.91     .12       010175.69    .055       010428.55    .075       0
#XS Ineff= 4 ,-1
    5308    5983     440   12779   13731     440    6610    9837     430
   10683   12779     430
Permanent Ineff=
       T       F       F       F
#Block Obstruct= 1 ,-1
    8512    8689     426
Bank Sta=10175.69,10428.55
XS Rating Curve= 0 ,0
Exp/Cntr=0.3,0.1

Type RM Length L Ch R = 1 ,32913   ,134,147,196
BEGIN DESCRIPTION:
This cross section corresponds to cross section 32919 of the non-georeferenced CDC model which was the source of this model.
END DESCRIPTION:
XS GIS Cut Line= 6
2438972.929437126972460.76498729 2438975.5604042 6970621.4584485
 2439012.0186646 6969439.1668498  2439212.539589 6967803.7501732
  2439597.956141  6966652.708512 2440465.1437111 6963577.1877601
#Sta/Elev= 30
    -525     442    1279     436    1341     422 2945.45  416.61 3347.44  425.92
 3389.73     414 3484.52  421.11 3522.11     414 3548.44   414.8 3561.24     426
 3698.19     422  3711.7     414 3773.53     428 4872.32  430.88  4894.5  418.94
 4911.08     406  4979.5   400.8 5075.35     410 5097.11     414 5114.63     432
 5831.98  429.35 5849.12     418 6011.78     432 6502.42   429.1 6526.95     422
 6560.82     428 8211.74     422 8372.67     430 8448.03     448 8546.57  445.08
#Mann= 4 ,-1,0
    -525     .12       0 2945.45     .12       0  4894.5    .055       0
 5075.35    .075       0
#XS Ineff= 5 ,-1
    -525     693     440    5114    7482     430    7482    8415     440
    2453    4633     430    1300    2453     430
Permanent Ineff=
       T       F       F       F       T
#Block Obstruct= 1 ,-1
    3347    3561     426
Bank Sta=4872.32,5114.63
XS Rating Curve= 0 ,0
Exp/Cntr=0.3,0.1

Type RM Length L Ch R = 1 ,32766   ,176,103,118
BEGIN DESCRIPTION:
This cross section corresponds to cross section 32814 of the non-georeferenced CDC model which was the source of this model.
END DESCRIPTION:
XS GIS Cut Line= 6
 2439014.77803796972486.83075892 2439069.3102167 6971483.4380237
 2439069.3102167 6969501.6670529 2439254.2061723 6968173.5420845
 2439592.7478181 6967178.7504389 2440522.4352632 6963657.9169294
#Sta/Elev= 30
    -525     442 1317.69  435.99 1776.04  432.08 1861.67  424.11 1933.43  431.17
 2453.98  431.86 2526.28  419.27 2899.42  424.45 2967.76     416 3070.86  420.84
 3087.14   414.3 3174.71  416.07 3236.11     426 3659.15  422.35 3697.63     414
  3724.3  414.18 3750.49     428 4914.83     430 4955.55     406 5005.95   400.6
 5073.61     412 5090.65     432 5822.57  428.22 5837.23     418 5874.99  419.67
 5889.75     428 6019.54     432 6668.99     422 8283.91   422.5 8457.54  447.44
#Mann= 4 ,-1,0
    -525     .12       0 2453.98     .12       0 4914.83    .055       0
 5090.65    .075       0
#XS Ineff= 6 ,-1
       0     692     440 2453.98    4614     430    5322    7377     430
    7377    8408     440    1300 2453.98  431.86    -525       0     445
Permanent Ineff=
       T       F       F       F       T       F
Bank Sta=4914.83,5090.65
XS Rating Curve= 0 ,0
Exp/Cntr=0.3,0.1

Type RM Length L Ch R = 1 ,32663   ,776,628,455
BEGIN DESCRIPTION:
This cross section corresponds to cross section 32718 of the non-georeferenced CDC model which was the source of this model.
END DESCRIPTION:
XS GIS Cut Line= 6
      2439018.98      6972477.57 2439192.3162043 6971998.1794483
 2439159.3300498 6970154.1401574 2439189.7122068 6969225.3204927
 2439228.7744647 6968973.5844477 2440599.9662976 6963593.9700993
#Sta/Elev= 30
    -509     442  849.46  430.85 1645.33  436.67  2037.3  429.85  2146.9  420.04
 2180.41  431.63 2213.04     422  2904.5     426 2953.14     416 3062.87  420.43
 3073.18     412 3282.16     422 3304.16     414  3454.8  414.03 3502.41  426.43
 3539.08     414 3607.21  414.05 3656.02  429.85 4786.47  431.95 4920.76     428
 4972.12     406    5018   400.3  5086.1     412 5099.32     432 5832.82  429.91
  5857.9     418 5986.64     432 8361.98     422 8442.62     446 8529.56  446.34
#Mann= 4 ,-1,0
    -509     .12       0 3656.02    .085       0 4786.47    .055       0
 5099.32    .075       0
#XS Ineff= 5 ,-1
    1874    4500     430    5432    7383     430    7383    8423     440
    -274     725     440    -509    -274     445
Permanent Ineff=
       F       F       F       F       F
#Block Obstruct= 1 ,-1
    2904    3503     426
Bank Sta=4786.47,5099.32
XS Rating Curve= 0 ,0
Exp/Cntr=0.3,0.1

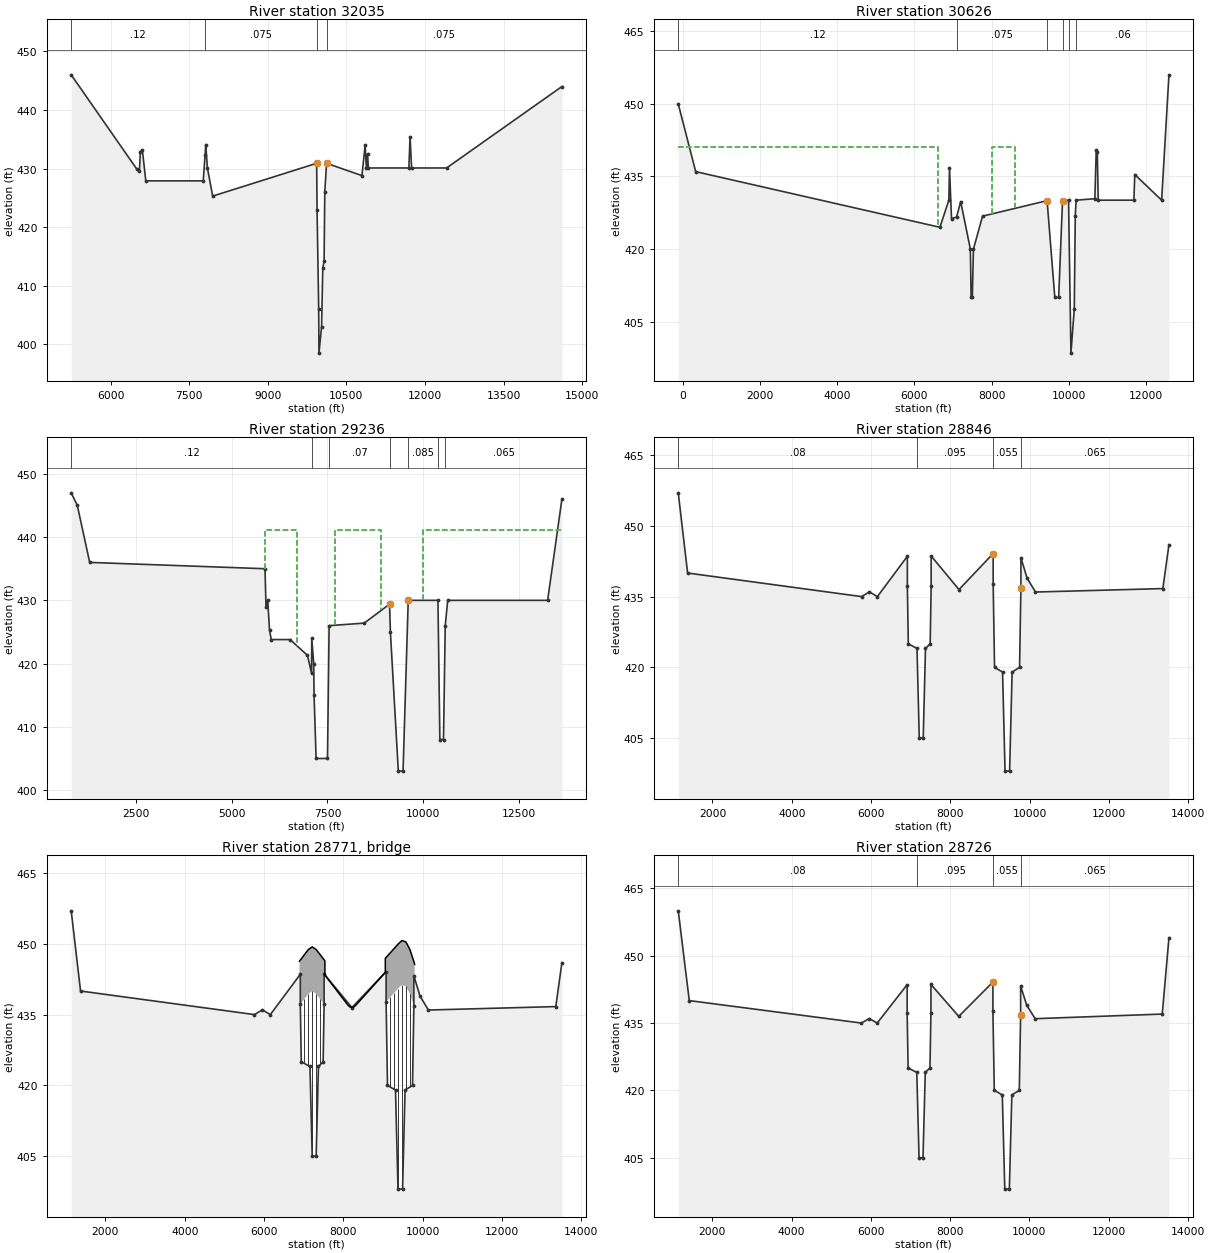
Type RM Length L Ch R = 1 ,32035   ,3250,1410,783
BEGIN DESCRIPTION:
This cross section corresponds to cross section 32042 of the non-georeferenced CDC model which was the source of this model.
END DESCRIPTION:
XS GIS Cut Line= 6
2439658.527059786972060.99871692 2439938.8406298 6969855.1692987
  2440179.903796  6967958.402751 2440408.3026174 6966161.4683527
 2440560.5811842 6964963.5130715 2440839.11548416962772.23042939
#Sta/Elev= 30
    5250     446    6502   429.9    6552   429.6    6569   432.9    6607   433.2
    6673   427.9    7768   427.9    7805   432.4    7816   434.1    7848   430.1
    7949   425.3    9932   430.9    9940   422.9    9971     406    9976   398.5
   10026     403   10049     413   10074   414.2   10087     426   10121   430.9
   10796   428.8   10857     434   10881   430.1   10902   432.5   10919   430.1
   11691   430.1   11714   435.4   11743   430.1   12410   430.1   14610     444
#Mann= 4 ,-1,0
    5250     .12       0    7805    .075       0    9932    .055       0
   10121    .075       0
Bank Sta=9932,10121
XS Rating Curve= 0 ,0
Exp/Cntr=0.3,0.1

Type RM Length L Ch R = 1 ,30626   ,881,1390,1762
BEGIN DESCRIPTION:
This cross section corresponds to cross section 31471 of the non-georeferenced CDC model which was the source of this model.
END DESCRIPTION:
XS GIS Cut Line= 6
     2441304.614      6976140.39 2440544.5814227 6970150.1791222
 2440672.5176402 6968008.9325056 2441328.7016952 6967027.2966736
 2441361.8945423  6966244.823501 2441401.8879891 6963659.1551386
#Sta/Elev= 30
    -125     450     327     436    6660   424.5    6892   430.1    6909   436.8
    6961   426.3    7092   426.6    7199   429.8    7450     420    7470     410
    7500     410    7530     420    7766   426.8    9440     430    9640     410
    9740     410    9840     430    9996   430.1   10058   398.5   10145   407.6
   10171   426.9   10193   430.1   10679   430.4   10714   440.4   10742   440.1
   10765   430.1   11691   430.1   11714   435.4   12410   430.1   12600     456
#Mann= 6 ,-1,0
    -125     .12       0    7092    .075       0    9440    .055       0
    9840    .075       0    9996    .055       0   10193     .06       0
#XS Ineff= 2 ,-1
    -125    6600  441.15    8000    8600  441.15
Permanent Ineff=
       F       F
Bank Sta=9440,9840
XS Rating Curve= 0 ,0
Exp/Cntr=0.3,0.1

Type RM Length L Ch R = 1 ,29236   ,390,390,390
BEGIN DESCRIPTION:
This cross section corresponds to cross section 29040 of the non-georeferenced CDC model which was the source of this model.
END DESCRIPTION:
XS GIS Cut Line= 6
     2441490.812     6976037.525 2441040.2742875 6971030.8631456
 2441035.6173077 6968011.3668839 2441427.7700667 6967740.2296309
 2441743.5768497 6967521.8783616 2441785.6132057 6963652.5172093
#Sta/Elev= 30
     817     447     977     445    1299     436    5870     435    5897   428.9
    5941   430.1    5988   425.3    6033   423.8    6525   423.8    6978   421.3
    7083   418.5    7090     424    7140     420    7150     415    7203     405
    7500     405    7542     426    8458   426.4    9118   429.4    9140     425
    9347     403    9470     403    9605     430   10380     430   10430     408
   10525     408   10570     426   10635     430   13240     430   13612     446
#Mann= 7 ,-1,0
     817     .12       0    7090    .055       0    7542     .07       0
    9140    .055       0    9605    .085       0   10380    .055       0
   10570    .065       0
#XS Ineff= 3 ,-1
    5870    6700  441.15    7700    8900  441.15   10000   13612  441.15
Permanent Ineff=
       F       F       F
Bank Sta=9118,9605
XS Rating Curve= 0 ,0
Exp/Cntr=0.3,0.1

Type RM Length L Ch R = 1 ,28846   ,120,120,120
BEGIN DESCRIPTION:
This cross section corresponds to cross section 28841 of the non-georeferenced CDC model which was the source of this model.
Upstream bounding cross section for Meyers Road/MacArthur Blvd bridge (West Fork Trinity River and Bear Creek bridges modeled).
END DESCRIPTION:
XS GIS Cut Line= 6
     2441699.145      6976044.47  2441744.505981 6971501.2473713
 2441768.6063272 6969341.9049052  2441793.243089 6967134.3607639
 2441795.3976122 6966941.3316224 2441831.9126051 6963667.7350793
#Sta/Elev= 30
    1137     457    1373     440    5760     435    5960     436    6160     435
    6916  443.55    6916  437.15    6940     425    7159     424    7216     405
    7316     405    7373     424  7491.6     425    7516  437.21    7516  443.61
    8218  436.49    9080  444.13    9080  437.72    9115     420    9317     419
    9380     398    9495     398    9558     419    9746     420    9780  436.83
    9780  443.24    9935  438.93   10147  435.97   13360   436.7   13514     446
#Mann= 4 ,-1,0
    1137     .08       0    7159    .095       0    9080    .055       0
    9780    .065       0
#XS Ineff= 2 , 0
       0    5680           10300       0
Permanent Ineff=
       F       F
Bank Sta=9080,9780
XS Rating Curve= 0 ,0
Exp/Cntr=0.3,0.1

Type RM Length L Ch R = 3 ,28771   ,,,
BEGIN DESCRIPTION:
Meyers Road/MacArthur Boulevard
---------------------------------------
CDC DC040803-1 Meyers Road
---------------------------------------
END DESCRIPTION:
Node Name=Meyers Road
Bridge Culvert--1,0,-1,-1, 0
Deck Dist Width WeirC Skew NumUp NumDn MinLoCord MaxHiCord MaxSubmerge Is_Ogee
1,90,2.6,0, 26, 26, , , 0.95, 0, 0,0,,
    6896    6916    7016    7116    7216    7316    7416    7516    7536    7536
    8110    8160    8218    8260    8310    9060    9060    9080    9180    9280
    9380    9480    9580    9680    9780    9800
  446.32  446.55  447.66  448.78  449.36   448.8   447.7  446.61  446.39  443.39
  437.08  436.66  436.49  436.58  436.92  443.94  446.94  447.13  448.05  448.99
  449.92  450.71   450.4  448.82  446.23  445.67
  437.15  437.15  438.26  439.38  439.96   439.4   438.3  437.21  437.21  443.39
  437.08  436.66  436.49  436.58  436.92  443.94  437.72  437.72  438.65  439.59
  440.52  441.31     441  439.42  436.83  436.83
    6896    6916    7016    7116    7216    7316    7416    7516    7536    7536
    8110    8160    8218    8260    8310    9060    9060    9080    9180    9280
    9380    9480    9580    9680    9780    9800
  446.32  446.55  447.66  448.78  449.36   448.8   447.7  446.61  446.39  443.39
  437.08  436.66  436.49  436.58  436.92  443.94  446.94  447.13  448.05  448.99
  449.92  450.71   450.4  448.82  446.23  445.67
  437.15  437.15  438.26  439.38  439.96   439.4   438.3  437.21  437.21  443.39
  437.08  436.66  436.49  436.58  436.92  443.94  437.72  437.72  438.65  439.59
  440.52  441.31     441  439.42  436.83  436.83
Pier Skew, UpSta & Num, DnSta & Num=  ,7016, 2 ,7016, 2 , 0 , 0 , 0 ,,
       3       3
     400     440
       3       3
     400     440
Pier Skew, UpSta & Num, DnSta & Num=  ,7116, 2 ,7116, 2 , 0 , 0 , 0 ,,
       3       3
     400     440
       3       3
     400     440
Pier Skew, UpSta & Num, DnSta & Num=  ,7216, 2 ,7216, 2 , 0 , 0 , 0 ,,
       4       4
     400     440
       4       4
     400     440
Pier Skew, UpSta & Num, DnSta & Num=  ,7316, 2 ,7316, 2 , 0 , 0 , 0 ,,
       4       4
     400     440
       4       4
     400     440
Pier Skew, UpSta & Num, DnSta & Num=  ,7416, 2 ,7416, 2 , 0 , 0 , 0 ,,
       3       3
     400     440
       3       3
     400     440
Pier Skew, UpSta & Num, DnSta & Num=  ,9180, 2 ,9180, 2 , 0 , 0 , 0 ,,
       3       3
     390     445
       3       3
     390     445
Pier Skew, UpSta & Num, DnSta & Num=  ,9280, 2 ,9280, 2 , 0 , 0 , 0 ,,
       3       3
     390     445
       3       3
     390     445
Pier Skew, UpSta & Num, DnSta & Num=  ,9380, 2 ,9380, 2 , 0 , 0 , 0 ,,
       4       4
     390     445
       4       4
     390     445
Pier Skew, UpSta & Num, DnSta & Num=  ,9480, 2 ,9480, 2 , 0 , 0 , 0 ,,
       4       4
     390     445
       4       4
     390     445
Pier Skew, UpSta & Num, DnSta & Num=  ,9580, 2 ,9580, 2 , 0 , 0 , 0 ,,
       3       3
     390     445
       3       3
     390     445
Pier Skew, UpSta & Num, DnSta & Num=  ,9680, 2 ,9680, 2 , 0 , 0 , 0 ,,
       3       3
     390     445
       3       3
     390     445
BR Coef=-1 , 0 , 0 ,, 0 ,,,0.8,-1,,1,
WSPro=,,,, 1 ,,,, 0 ,,,, 0 ,,,,-1 ,-1 ,-1 , 0 , 0 , 0 , 0 , 0
BR Coef=-1 , 0 , 0 ,, 0 ,,,0.8,-1,,1,
WSPro=,,,, 1 ,,,, 0 ,,,, 0 ,,,,-1 ,-1 ,-1 , 0 , 0 , 0 , 0 , 0
BR Coef=-1 , 0 , 0 ,, 0 ,,,0.8,-1,,1,
WSPro=,,,, 1 ,,,, 0 ,,,, 0 ,,,,-1 ,-1 ,-1 , 0 , 0 , 0 , 0 , 0
BR Coef=-1 , 0 , 0 ,, 0 ,,,0.8,-1,,1,
WSPro=,,,, 1 ,,,, 0 ,,,, 0 ,,,,-1 ,-1 ,-1 , 0 , 0 , 0 , 0 , 0
BC Design=,, 0 ,, 0 ,,,,,,
BC HTab HWMax=444.13
BC Use User HTab Curves=0
BC User HTab FreeFlow(D)= 0

Type RM Length L Ch R = 1 ,28726   ,265,264,80
BEGIN DESCRIPTION:
This cross section corresponds to cross section 28749 of the non-georeferenced CDC model which was the source of this model.
Downstream bounding cross-section for Meyers Road/MacArthur Blvd bridge (West Fork Trinity River and Bear Creek bridges modeled).
END DESCRIPTION:
XS GIS Cut Line= 6
     2441796.368     6976051.414  2441901.458751 6971510.9005672
 2441899.2107248 6969683.3090781 2441897.0138788 6967899.9330517
  2441963.557709 6966902.5570937 2442178.6922069 6963677.6408459
#Sta/Elev= 30
    1139     460    1417     440    5760     435    5960     436    6160     435
    6916  443.55    6916  437.15    6940     425    7159     424    7216     405
    7316     405    7373     424  7491.6     425    7516  437.21    7516  443.61
    8218  436.49    9080  444.13    9080  437.72    9115     420    9317     419
    9380     398    9495     398    9558     419    9746     420    9780  436.83
    9780  443.24    9935  438.93   10147  435.97   13354     437   13523     454
#Mann= 4 ,-1,0
    1139     .08       0    7159    .095       0    9080    .055       0
    9780    .065       0
#XS Ineff= 2 , 0
       0    5680           10300       0
Permanent Ineff=
       F       F
Bank Sta=9080,9780
XS Rating Curve= 0 ,0
Exp/Cntr=0.3,0.1

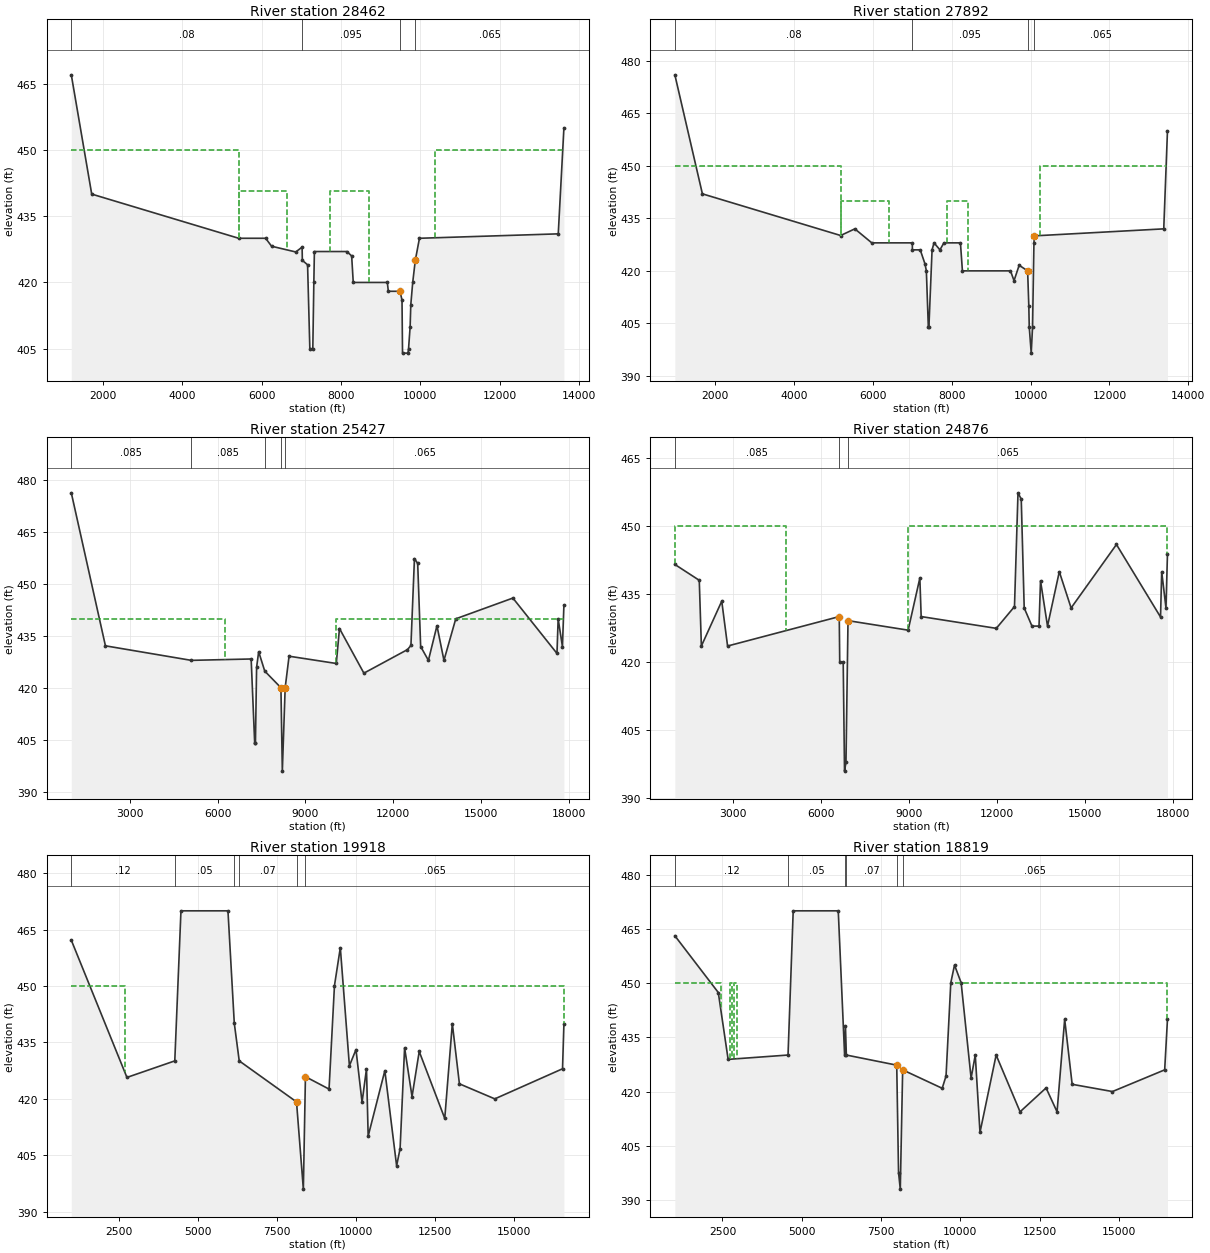
Type RM Length L Ch R = 1 ,28462   ,442,570,241
BEGIN DESCRIPTION:
This cross section corresponds to cross section 28450 of the non-georeferenced CDC model which was the source of this model.
END DESCRIPTION:
XS GIS Cut Line= 6
     2442011.645     6976037.525  2442140.807833 6971816.5667829
 2442159.2472782 6969630.3101683 2442175.1340575 6967746.4979911
 2441975.8631306 6967431.0950786 2441975.8631306 6963672.2279581
#Sta/Elev= 30
    1198     467    1713     440    5420     430    6100     430    6250   428.2
    6860   426.9    7020     428    7026     425    7158     424    7215     405
    7290     405    7316     420    7330     427    8150     427    8270     426
    8310     420    9170     420    9195     418    9490     418    9540     416
    9553     404    9690     404    9705     405    9745     410    9762     415
    9810     420    9875     425    9980     430   13481     431   13624     455
#Mann= 4 ,-1,0
    1198     .08       0    7020    .095       0    9490    .055       0
    9875    .065       0
#XS Ineff= 4 ,-1
    5420    6640   440.6    7720    8700   440.6   10360   13624     450
    1198    5420     450
Permanent Ineff=
       F       F       F       F
Bank Sta=9490,9875
XS Rating Curve= 0 ,0
Exp/Cntr=0.3,0.1

Type RM Length L Ch R = 1 ,27892   ,302,2464,1208
BEGIN DESCRIPTION:
This cross section corresponds to cross section 27882 of the non-georeferenced CDC model which was the source of this model.
END DESCRIPTION:
XS GIS Cut Line= 6
     2442136.645     6976211.137  2442390.208591 6972055.5217222
 2442403.7139809 6970257.8112099 2442415.6841013 6968664.2914311
 2442420.1726094  6968066.721432 2442452.6118165 6963747.6683451
#Sta/Elev= 30
     973     476    1672     442    5180   430.1    5540     432    5970     428
    7000     428    7000     426    7200     426    7320     422    7355     420
    7405     404    7420     404    7500     426    7550     428    7700     426
    7800     428    8220     428    8270     420    9490     420    9580   417.2
    9710   421.6    9925     420    9955     410    9966     404   10016   396.5
   10050     404   10085     428   10099     430   13379     432 13473.6     460
#Mann= 4 ,-1,0
     973     .08       0    7000    .095       0    9925    .055       0
   10099    .065       0
#XS Ineff= 4 ,-1
    5180    6400     440    7870    8400     440   10232 13473.6     450
     973    5180     450
Permanent Ineff=
       F       F       F       F
Bank Sta=9925,10099
XS Rating Curve= 0 ,0
Exp/Cntr=0.3,0.1

Type RM Length L Ch R = 1 ,25427   ,659,551,100
BEGIN DESCRIPTION:
This cross section corresponds to cross section 25434 of the non-georeferenced CDC model which was the source of this model.
LOMR # 16-06-1120P reflected in ROB as inneffective flow area.
END DESCRIPTION:
XS GIS Cut Line= 6
  2442184.330413 6976241.3780159 2442600.5111595  6971410.458839
 2442746.2710386 6969718.6390599 2443087.0049372 6969175.5358154
 2443427.7503187 6968632.43650792443032.110400466959692.26328079
#Sta/Elev= 30
    1000   476.4    2166   432.2    5100     428    7144   428.4    7265     404
    7290     404    7330     426    7401   430.5    7608   424.9    8161   420.1
    8209     396    8306   420.1    8439   429.2   10052   427.1   10161   437.2
   10995   424.3   12482   431.1   12602   432.3   12722   457.4   12833     456
   12934     432   13199     428   13491     438   13730     428   14133     440
   16085     446   17591     430   17631     440   17777     432   17828     444
#Mann= 5 ,-1,0
    1000    .085       0    5100    .085       0    7608    .095       0
    8161    .055       0    8306    .065       0
#XS Ineff= 2 , 0
       0    6250     440   10040       0     440
Permanent Ineff=
       F       F
Bank Sta=8161,8306
XS Rating Curve= 0 ,0
Exp/Cntr=0.3,0.1

Type RM Length L Ch R = 1 ,24876   ,1720,4958,2260
BEGIN DESCRIPTION:
This cross section corresponds to cross section 24882 of the non-georeferenced CDC model which was the source of this model.
LOMR # 16-06-1120P reflected in ROB as inneffective flow area.
END DESCRIPTION:
XS GIS Cut Line= 6
  2442922.173902 6975416.6788449 2443204.8055546 6971933.6290525
 2443479.4099923 6968550.1000584  2443256.811028 6963722.4059736
 2444690.0890013 6960582.4752457  2445378.724107 6959073.9651393
#Sta/Elev= 30
    1000   441.6    1834   438.1    1906   423.6    2602   433.5    2801   423.6
    6616   430.1    6632   420.1    6751   420.1    6796     396    6846     398
    6915   429.2    8969   427.1    9369   438.6    9414   430.1   11981   427.5
   12602   432.3   12722   457.4   12833     456   12934     432   13199     428
   13440     428   13491     438   13730     428   14133     440   14536     432
   16085     446   17591     430   17631     440   17777     432   17828     444
#Mann= 3 ,-1,0
    1000    .085       0    6616    .055       0    6915    .065       0
#XS Ineff= 2 , 0
       0    4800     450    8960       0     450
Permanent Ineff=
       F       F
Bank Sta=6616,6915
XS Rating Curve= 0 ,0
Exp/Cntr=0.3,0.1

Type RM Length L Ch R = 1 ,19918   ,1048,1099,659
BEGIN DESCRIPTION:
This cross section corresponds to cross section 19924 of the non-georeferenced CDC model which was the source of this model.
LOMR # 16-06-1120P reflected in ROB as inneffective flow area.
END DESCRIPTION:
XS GIS Cut Line= 6
  2444136.963139 6975743.7369178 2444690.6339477 6972414.3213326
 2445260.6980963 6968986.9938697 2446155.2074622 6966502.6425391
 2447016.7119727 6964110.3290823 2448218.9280722 6960769.0329434
#Sta/Elev= 30
    1000   462.2    2758   425.7    4270   430.1    4465     470    5950     470
    6150   440.1    6306   430.1    8116   419.2    8332     396    8398   425.9
    9144   422.6    9315   450.1    9500   460.2    9787   428.8    9995   433.1
   10187   419.1   10327     428   10380   410.1   10907   427.5   11279   402.2
   11389   406.8   11531   433.6   11766   420.6   11993   432.6   12800   414.8
   13039     440   13263     424   14381     420   16521     428   16565     440
#Mann= 6 ,-1,0
    1000     .12       0    4270     .05       0    6150     .12       0
    6306     .07       0    8116    .055       0    8398    .065       0
#XS Ineff= 4 ,-1
    1000    2700     450    2700    8116   419.2    8398    9500   425.9
    9500   16565     450
Permanent Ineff=
       F       F       F       F
Bank Sta=8116,8398
XS Rating Curve= 0 ,0
Exp/Cntr=0.3,0.1

Type RM Length L Ch R = 1 ,18819   ,400,684,781
BEGIN DESCRIPTION:
This cross section corresponds to cross section 18823 of the non-georeferenced CDC model which was the source of this model.
LOMR # 16-06-1120P reflected in ROB as inneffective flow area.
END DESCRIPTION:
XS GIS Cut Line= 6
  2444615.869989 6975971.5100843 2445484.6330159 6972693.2394099
 2446302.4450286 6969607.8318668 2446040.9501447 6968615.0891016
 2447811.1880741 6964296.3890777 2449053.0779787 6961269.5168506
#Sta/Elev= 30
    1000   463.1    2369   447.4    2679   428.9    4567   430.1    4730     470
    6150     470    6350   430.1    6377     438    6405   430.1    7993   427.3
    8050   397.6    8105     393    8180     426    9426   420.9    9547   424.3
    9697   450.1    9814     455   10023   450.1   10337   423.7   10468   430.1
   10617   408.7   11126   430.1   11881   414.4   12700     421   13046   414.4
   13286     440   13522     422   14792     420   16438     426   16526     440
#Mann= 6 ,-1,0
    1000     .12       0    4567     .05       0    6350     .12       0
    6405     .07       0    7993    .045       0    8180    .065       0
#XS Ineff= 8 ,-1
    1000    2450     450    2450    2730     425    2730    2800     450
    2800    2870     425    2870    2950     450    2950    7993     425
    8180    9814   425.7    9814   16526     450
Permanent Ineff=
       F       F       F       F       F       F       F       F
Bank Sta=7993,8180
XS Rating Curve= 0 ,0
Exp/Cntr=0.3,0.1

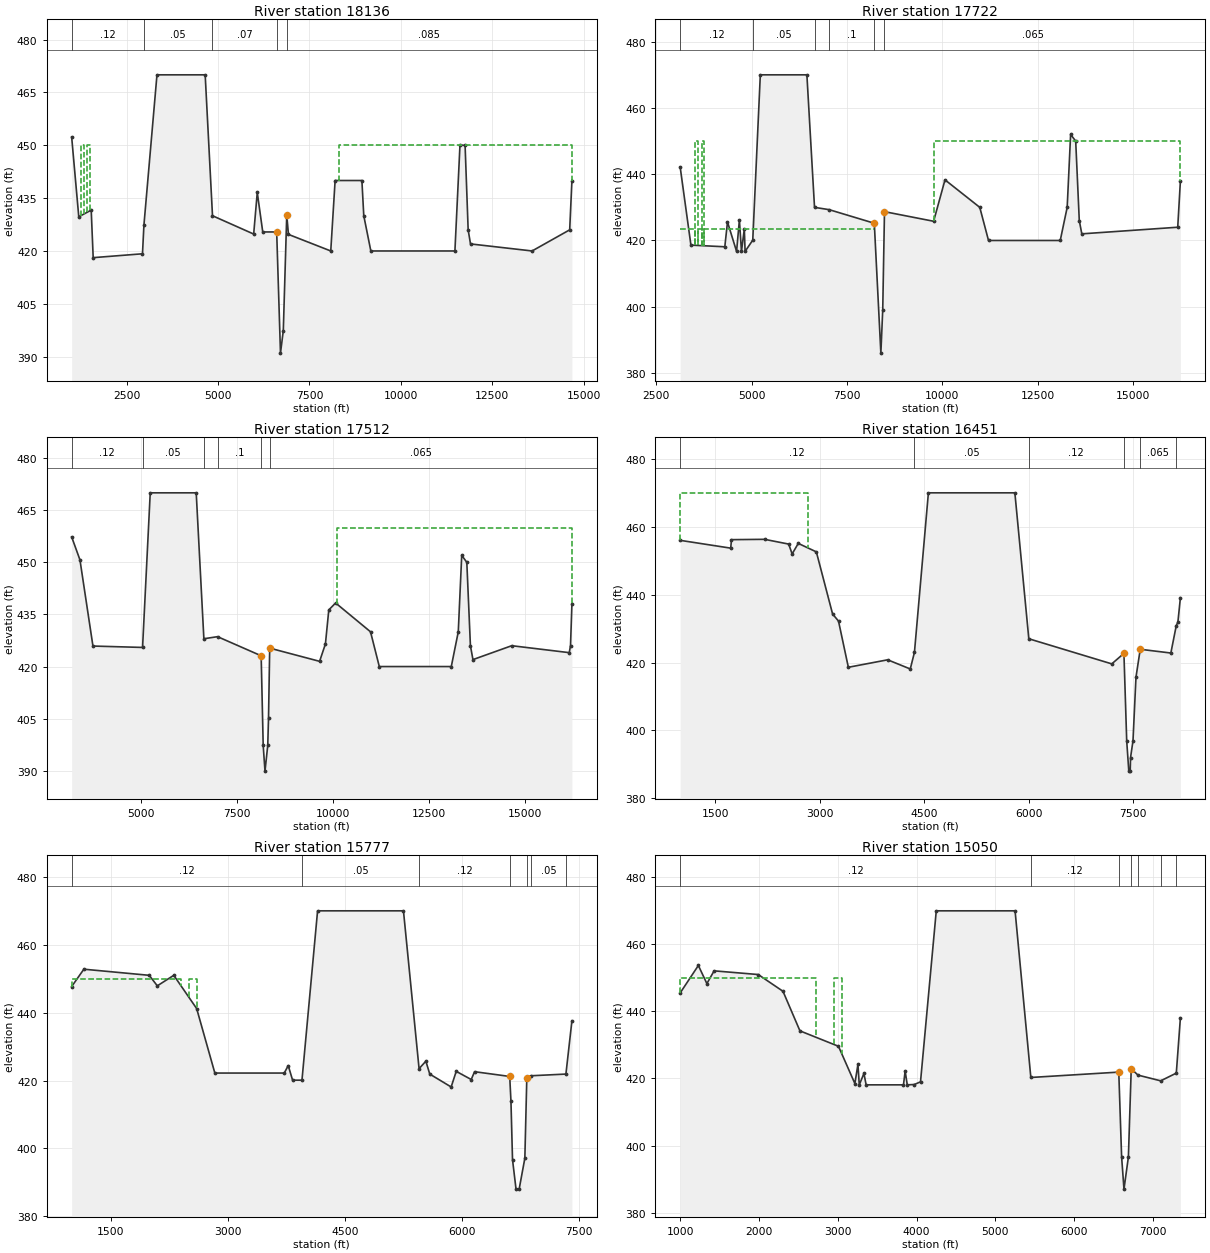
Type RM Length L Ch R = 1 ,18136   ,430,414,500
BEGIN DESCRIPTION:
This cross section corresponds to cross section 18140 of the non-georeferenced CDC model which was the source of this model.
END DESCRIPTION:
XS GIS Cut Line= 6
  2445269.988104 6974552.3088545 2446004.8301382 6972080.7127478
 2446711.5101553 6969704.1948631 2446999.3150259 6968145.0050681
 2447173.3789823 6967928.3499896 2449713.4519861 6961663.0478877
#Sta/Elev= 30
    1000   452.3    1194   429.7    1534   431.6    1588   418.1    2936   419.2
    2975   427.3    3332     470    4650     470    4850     430    5976   424.8
    6074   436.6    6224   425.4    6605   425.4    6709     391    6786   397.4
    6880   430.2    6927   424.7  8083.3     420  8202.6     440  8934.6     440
  8986.2     430  9179.3     420   11478     420   11616     450   11756     450
   11840     426   11904     422   13588     420   14616     426   14677     440
#Mann= 5 ,-1,0
    1000     .12       0    2975     .05       0    4850     .07       0
    6605    .039       0    6880    .085       0
#XS Ineff= 7 ,-1
    1000    1250   425.4    1250    1350     450    1350    1420   425.4
    1420    1500     450    1500    6605   425.4    6880    8300   424.7
    8300   14677     450
Permanent Ineff=
       F       F       F       F       F       F       F
Bank Sta=6605,6880
XS Rating Curve= 0 ,0
Exp/Cntr=0.3,0.1

Type RM Length L Ch R = 1 ,17722   ,197,210,197
BEGIN DESCRIPTION:
This cross section corresponds to cross section 17726 of the non-georeferenced CDC model which was the source of this model.
END DESCRIPTION:
XS GIS Cut Line= 6
  2446711.175223 6974412.5544618 2446891.7358447 6970487.4928372
  2446957.909925 6969941.9440595 2447051.1131507 6969593.9851097
  2447262.373883 6969040.9799822 2450145.1591279 6961928.9981432
#Sta/Elev= 30
    3130   442.2    3412   418.6    4300   418.1    4370   425.6    4608   416.7
    4682   426.2    4736   416.7    4811   423.5    4831   416.7    5032   420.1
    5230     470    6450     470    6650     430    7034   429.3    8216   425.2
    8388     386    8437   399.1    8483   428.7    9770   425.8   10068   438.3
   10979     430   11208     420   13087     420   13269     430   13359     452
   13492     450   13586     426   13652     422   16165     424   16235     438
#Mann= 6 ,-1,0
    3130     .12       0    5032     .05       0    6650     .15       0
    7034      .1       0    8216    .039       0    8483    .065       0
#XS Ineff= 7 ,-1
    3130    3520   423.5    3520    3600     450    3600    3700   423.5
    3700    3750     450    3750    8216   423.5    8483    9770   425.5
    9770   16235     450
Permanent Ineff=
       F       F       F       F       F       F       F
Bank Sta=8216,8483
XS Rating Curve= 0 ,0
Exp/Cntr=0.3,0.1

Type RM Length L Ch R = 1 ,17512   ,850,1062,1060
BEGIN DESCRIPTION:
This cross section corresponds to cross section 17516 of the non-georeferenced CDC model which was the source of this model.
END DESCRIPTION:
XS GIS Cut Line= 6
  2446902.064564 6974364.7472217 2447095.8509221 6970501.4731242
 2447153.6368958 6969979.2251529 2447256.1599847 6969609.5188713
 2447454.9939046 6969093.79483722450362.421485316961924.84744545
#Sta/Elev= 30
    3180   457.3    3396   450.7    3735   425.9    5030   425.5    5230     470
    6430     470    6630     428    6987   428.6    8125   423.1    8178   397.3
    8225   389.9    8297   397.3    8317   405.2    8348   425.3    9650   421.5
    9802   426.5    9890   436.3   10068   438.3   10979     430   11208     420
   13087     420   13269     430   13359     452   13492     450   13586     426
   13652     422   14664     426   16165     424   16198     426   16235     438
#Mann= 6 ,-1,0
    3180     .12       0    5030     .05       0    6630     .15       0
    6987      .1       0    8125    .039       0    8348    .065       0
#XS Ineff= 2 , 0
       0                   10100       0     460
Permanent Ineff=
       F       F
Bank Sta=8125,8348
XS Rating Curve= 0 ,0
Exp/Cntr=0.3,0.1

Type RM Length L Ch R = 1 ,16451   ,630,673,679
BEGIN DESCRIPTION:
This cross section corresponds to cross section 16454 of the non-georeferenced CDC model which was the source of this model.
END DESCRIPTION:
XS GIS Cut Line= 6
   2447066.84409  6976028.362989 2447295.9240128 6974035.9982073
 2447513.5728557 6972143.2539613 2448040.6879432 6970588.7314798
 2448288.7589693 6969857.1945571 2448567.8519151 6969034.2178566
#Sta/Elev= 30
    1000     456    1725   453.7    1736   456.2    2210   456.3    2556   454.9
    2606     452    2694   455.1    2953   452.6    3186   434.3    3271   432.2
    3412   418.6    3976   420.8    4300   418.1    4360     423    4560     470
    5800     470    6000     427    7190   419.6    7364   422.7    7404   396.9
    7434     388    7454     388    7459     392    7494   396.9    7537   415.7
    7598   423.9    8037   422.8    8115   430.9    8138   431.9    8174   439.1
#Mann= 6 ,-1,0
    1000     .12       0    4360     .05       0    6000     .12       0
    7364    .039       0    7598    .065       0    8115     .03       0
#XS Ineff= 3 ,-1
    1000    2830     470    2830    7364   422.7    7598    8174   423.9
Permanent Ineff=
       F       F       F
Bank Sta=7364,7598
XS Rating Curve= 0 ,0
Exp/Cntr=0.3,0.1

Type RM Length L Ch R = 1 ,15777   ,732,727,732
BEGIN DESCRIPTION:
This cross section corresponds to cross section 15780 of the non-georeferenced CDC model which was the source of this model.
END DESCRIPTION:
XS GIS Cut Line= 6
  2447423.560896 6975418.2769388  2447686.750987 6973963.8635091
 2447932.4148657   6972606.41314 2448290.0217621 6971687.1830231
 2448576.1215836 6970951.8019479 2449219.8919496 6969297.2038792
#Sta/Elev= 30
    1000   447.7    1156   452.8    1993     451    2097   447.9    2308     451
    2601   441.2    2834   422.2    3723   422.2    3774   424.4    3830   420.1
    3950   420.1    4150     470    5250     470    5450   423.5    5537   425.7
    5587   421.9    5861   418.1    5926   422.7    6118   420.3    6161   422.6
    6611   421.2    6627   413.9    6647   396.7    6692     388    6732     388
    6805   397.1    6830   420.7    6881   421.4    7331   421.9    7408   437.6
#Mann= 7 ,-1,0
    1000     .12       0    3950     .05       0    5450     .12       0
    6611    .039       0    6830     .15       0    6881     .05       0
    7331     .03       0
#XS Ineff= 5 ,-1
    1000    2400     450    2400    2500   421.2    2500    2600     450
    2600    6611   421.2    6830    7408   420.7
Permanent Ineff=
       F       F       F       F       F
Bank Sta=6611,6830
XS Rating Curve= 0 ,0
Exp/Cntr=0.3,0.1

Type RM Length L Ch R = 1 ,15050   ,718,718,718
BEGIN DESCRIPTION:
This cross section corresponds to cross section 15055 of the non-georeferenced CDC model which was the source of this model.
END DESCRIPTION:
XS GIS Cut Line= 6
  2447591.801045 6975450.3221503 2448126.3550947 6974083.7422063
 2448447.1087183 6973263.7989643 2448767.8777618 6972443.8586751
 2449373.8181509 6970895.0920876 2449908.5178689 6969528.5429834
#Sta/Elev= 30
    1000   445.5    1231   453.7    1339   448.3    1431   452.1    1991     451
    2305     446    2520   434.2    3009   429.6    3217   418.5    3256   424.2
    3273   418.1    3332   421.5    3360   418.1    3834   418.1    3855   422.2
    3882   418.1    3971   418.2    4050     419    4250     470    5250     470
    5450   420.3    6566   421.9    6602   396.6    6632     387    6688   396.6
    6724   422.9    6810     421    7098   419.3    7296   421.6    7348   438.1
#Mann= 7 ,-1,0
    1000     .12       0    5450     .12       0    6566    .039       0
    6724     .15       0    6810     .08       0    7098     .05       0
    7296     .03       0
#XS Ineff= 5 ,-1
    1000    2730     450    2730    2950   421.9    2950    3050     450
    3050    6566   421.9    6724    7348   422.9
Permanent Ineff=
       F       F       F       F       F
Bank Sta=6566,6724
XS Rating Curve= 0 ,0
Exp/Cntr=0.3,0.1