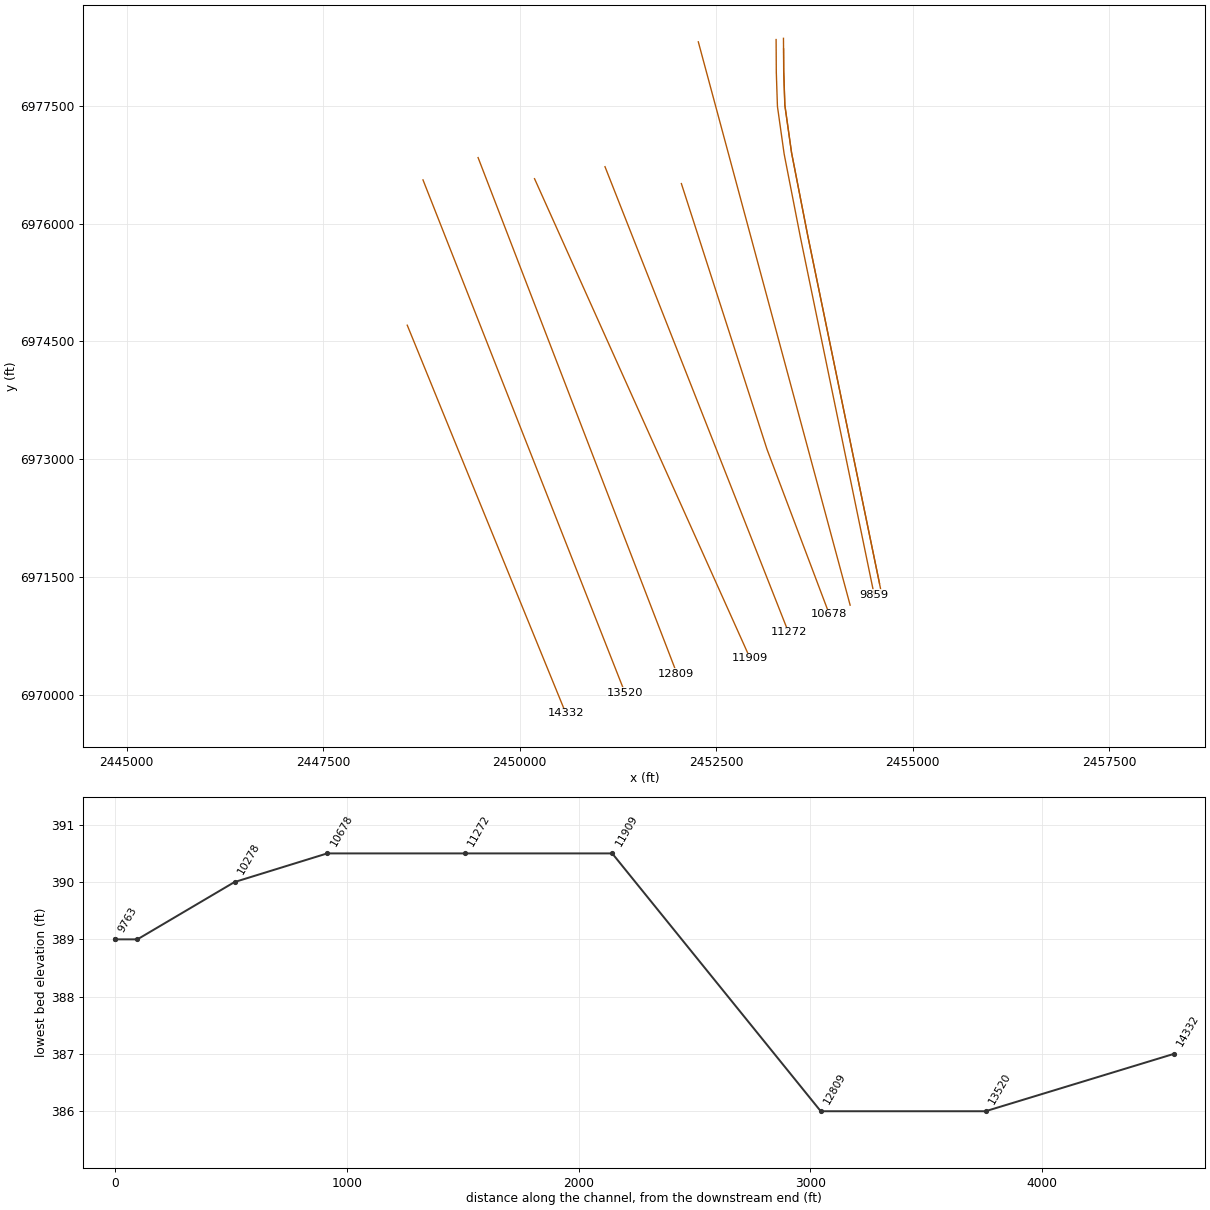
HEC-RAS study CDC_Consolidated_Model.prj: Upper Trinity CDC Consolidated Model

--- CDC_Consolidated_Model.g02 (geometry) --- (continued)

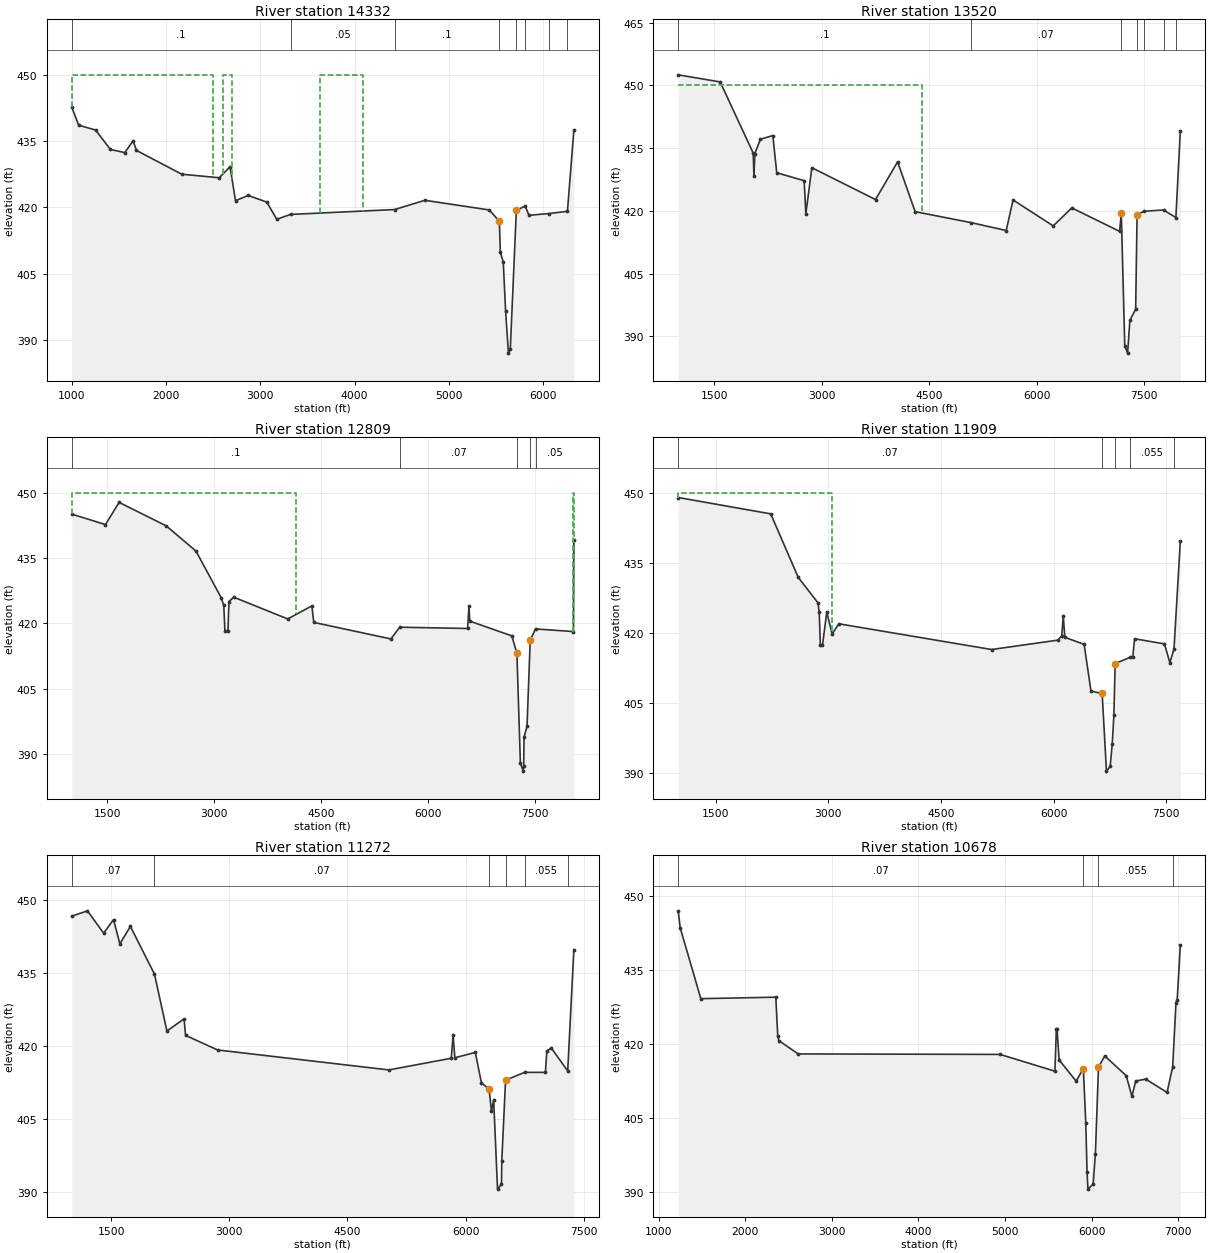
Type RM Length L Ch R = 1 ,14332   ,840,812,812
BEGIN DESCRIPTION:
This cross section corresponds to cross section 14335 of the non-georeferenced CDC model which was the source of this model.
END DESCRIPTION:
XS GIS Cut Line= 6
  2448569.195088 6974705.2590079 2448789.3705009 6974165.9818712
  2449082.948982 6973446.9485324 2449560.0408756 6972278.5246882
 2450073.8695723 6971020.2306168 2450587.7369829 6969761.9450757
#Sta/Elev= 30
    1000   442.7    1073   438.6    1253   437.5    1410   433.1    1563   432.4
    1651   435.1    1685   432.9    2167   427.5    2564   426.7    2679   429.2
    2737   421.5    2871   422.7    3068   421.2    3175   417.3    3321   418.4
    4425   419.5    4745   421.6    5431   419.4    5536   416.8    5546   409.8
    5577   407.7    5602   396.6    5632     387    5652     388    5716   419.3
    5810   420.3    5850   418.2    6063   418.6    6258   419.1    6326   437.4
#Mann= 8 ,-1,0
    1000      .1       0    3321     .05       0    4425      .1       0
    5536    .039       0    5716     .15       0    5810     .08       0
    6063     .05       0    6258     .03       0
#XS Ineff= 7 ,-1
    1000    2500     450    2500    2600   416.8    2600    2700     450
    2700    3635   416.8    3635    4088     450    4088    5536   416.8
    5716    6326   419.3
Permanent Ineff=
       F       F       F       F       F       F       F
Bank Sta=5536,5716
XS Rating Curve= 0 ,0
Exp/Cntr=0.3,0.1

Type RM Length L Ch R = 1 ,13520   ,739,711,709
BEGIN DESCRIPTION:
This cross section corresponds to cross section 13523 of the non-georeferenced CDC model which was the source of this model.
END DESCRIPTION:
XS GIS Cut Line= 6
  2448769.481105 6976555.8999917 2449447.8586853 6974831.8775211
 2450054.8876549 6973289.3435327 2450661.9720707 6971746.8216833
 2451019.1068551 6970839.4616214 2451340.5448605 6970022.8408793
#Sta/Elev= 30
    1000   452.5    1585   450.8    2046   433.8    2056   428.3    2069   433.7
    2146   437.1    2320     438    2374   429.1    2757   427.2    2780   419.3
    2864   430.3    3752   422.7    4060   431.7    4305   419.8    5081   417.2
    5575   415.3    5671   422.6    6231   416.4    6490   420.7    7157   415.1
    7181   419.4    7229   387.8    7269     386    7300   393.8    7381   396.5
    7401   419.1    7500   419.9    7770   420.2    7942   418.4    8004   439.1
#Mann= 7 ,-1,0
    1000      .1       0    5081     .07       0    7181    .039       0
    7401     .15       0    7500     .08       0    7770     .05       0
    7942     .03       0
#XS Ineff= 2 , 0
       0    4400     450               0
Permanent Ineff=
       F       F
Bank Sta=7181,7401
XS Rating Curve= 0 ,0
Exp/Cntr=0.3,0.1

Type RM Length L Ch R = 1 ,12809   ,810,900,920
BEGIN DESCRIPTION:
This cross section corresponds to cross section 12811 of the non-georeferenced CDC model which was the source of this model.
---------------------------------------------------------------------
CDC GP042800-02 West Fork Relief Interceptor WF-1
Cross-section 12811 - 15780
Project located in ROB.
---------------------------------------------------------------------
END DESCRIPTION:
XS GIS Cut Line= 6
  2449470.713954  6976839.625146 2450137.9124233 6975106.7162102
 2450770.0587967 6973465.0265802 2451367.1429044 6971914.5536313
 2451999.4100126 6970272.88893572451993.664301816970267.32168461
#Sta/Elev= 30
    1000   445.1    1473   442.7    1664   447.8    2326   442.4    2743   436.6
    3096   425.9    3133   424.1    3149   418.3    3192   418.3    3205     425
    3273     426    4030     421    4369     424    4396   420.2    5478   416.4
    5602   419.1    6554   418.8    6574     424    6584   420.5    7175   417.1
    7246   413.1    7295   387.8    7335     386    7341   387.2    7346   393.8
    7388   396.3    7433   416.1    7507   418.7    8040   418.1    8045   439.1
#Mann= 5 ,-1,0
    1000      .1       0    5602     .07       0    7246    .039       0
    7433     .15       0    7507     .05       0
#XS Ineff= 2 , 0
       0    4150     450    8040       0     450
Permanent Ineff=
       F       F
Bank Sta=7246,7433
XS Rating Curve= 0 ,0
Exp/Cntr=0.3,0.1

Type RM Length L Ch R = 1 ,11909   ,710,637,600
BEGIN DESCRIPTION:
This cross section corresponds to cross section 11911 of the non-georeferenced CDC model which was the source of this model.
END DESCRIPTION:
XS GIS Cut Line= 6
   2450189.07505 6976570.9688592 2450825.2620984 6975154.2098817
 2451541.0375697  6973560.371862 2452217.1103646  6972055.095345
  2452575.056171 6971258.1901147 2452933.0190378 6970461.2891494
#Sta/Elev= 30
    1000     449    2232   445.5    2599   431.9    2861   426.5    2878   424.5
    2893   417.5    2921   417.4    2979   424.5    3050   419.8    3139     422
    5174   416.5    6055   418.5    6109   419.4    6129   423.7    6150   419.1
    6407   417.6    6498   407.6    6647   407.1    6704   390.5    6754   391.5
    6781   396.3    6803   402.4    6820   413.5    7016   414.8    7054   414.8
    7079   418.8    7477   417.7    7549   413.7    7604   416.6    7688   439.6
#Mann= 5 ,-1,0
    1000     .07       0    6647    .039       0    6820     .09       0
    7016    .055       0    7604     .03       0
#XS Ineff= 2 , 0
       0    3050     450    6820       0   413.5
Permanent Ineff=
       F       F
Bank Sta=6647,6820
XS Rating Curve= 0 ,0
Exp/Cntr=0.3,0.1

Type RM Length L Ch R = 1 ,11272   ,620,593,600
BEGIN DESCRIPTION:
This cross section corresponds to cross section 11274 of the non-georeferenced CDC model which was the source of this model.
END DESCRIPTION:
XS GIS Cut Line= 6
2451085.70544404 6976723.8714473 2451766.0174348 6974996.2551451
 2452305.8880742 6973625.3924012 2452845.8030048 6972254.5391718
  2453133.775526 6971523.4212115 2453421.7608424 6970792.3058758
#Sta/Elev= 30
    1000   446.6    1199   447.7    1405   443.1    1530   445.9    1611   440.9
    1744   444.5    2050   434.7    2208     423    2426   425.5    2445   422.1
    2852   419.1    5027     415    5819   417.4    5842   422.2    5864   417.5
    6124   418.6    6202   412.3    6299   411.1    6329   406.5    6357   408.8
    6406   390.5    6456   391.5    6460   396.3    6508   412.9    6750   414.5
    7014   414.5    7032   418.9    7089   419.5    7297   414.8    7375   439.6
#Mann= 6 ,-1,0
    1000     .07       0    2050     .07       0    6299    .039       0
    6508     .09       0    6750    .055       0    7297     .03       0
Bank Sta=6299,6508
XS Rating Curve= 0 ,0
Exp/Cntr=0.3,0.1

Type RM Length L Ch R = 1 ,10678   ,529,400,404
BEGIN DESCRIPTION:
This cross section corresponds to cross section 10681 of the non-georeferenced CDC model which was the source of this model.
END DESCRIPTION:
XS GIS Cut Line= 6
  2452057.817323 6976508.8306834 2452313.3129281 6975715.2054788
 2452611.1148259 6974790.2178275 2453147.1990556 6973125.2480603
 2453560.7503938 6972029.7315506 2453939.8631527 6971025.5130866
#Sta/Elev= 30
    1226   446.9    1248   443.5    1487   429.1    2353   429.4    2375   421.6
    2388   420.6    2611   417.9    4943   417.8    5577   414.4    5593     423
    5601     423    5625   416.7    5821   412.4    5905   414.9    5933     404
    5948     394    5958   390.5    6018   391.5    6044   397.6    6080   415.2
    6152   417.5    6400   413.5    6466   409.3    6510   412.4    6624   412.8
    6872   410.1    6937   415.3    6975   428.3    6989   428.9    7025   439.9
#Mann= 4 ,-1,0
    1226     .07       0    5905    .039       0    6080    .055       0
    6937     .03       0
Bank Sta=5905,6080
XS Rating Curve= 0 ,0
Exp/Cntr=0.3,0.1

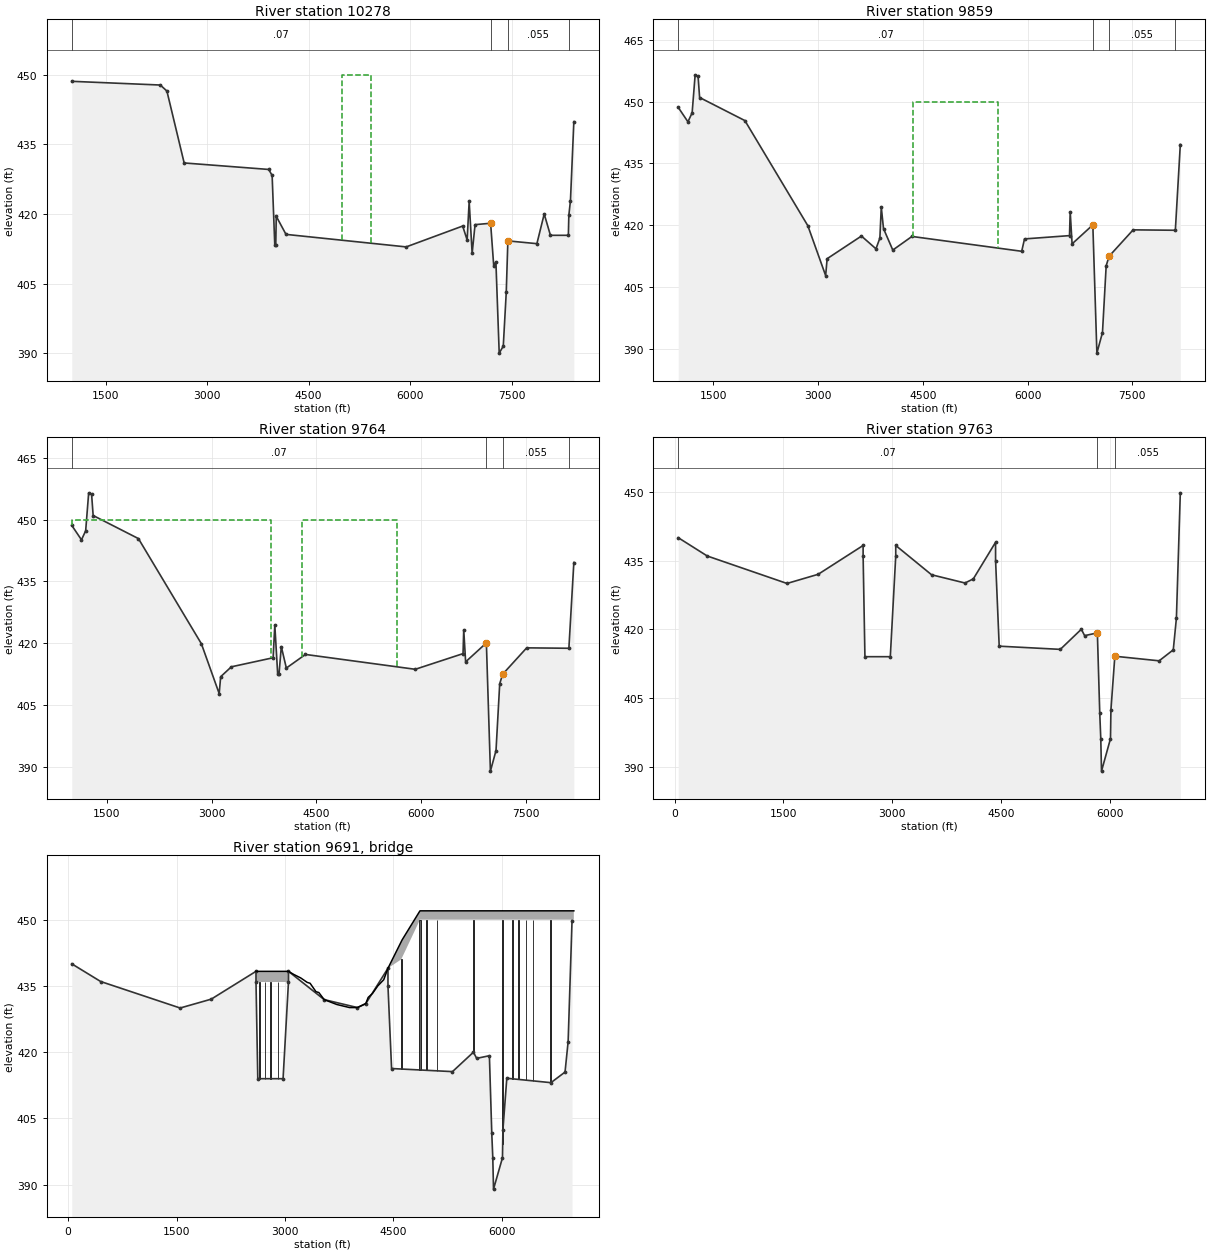
Type RM Length L Ch R = 1 ,10278   ,350,419,300
BEGIN DESCRIPTION:
This cross section corresponds to cross section 10280 of the non-georeferenced CDC model which was the source of this model.
END DESCRIPTION:
XS GIS Cut Line= 6
  2452273.229018 6978313.8298747 2452736.8901649 6976592.1141581
 2453226.3609707 6974774.7555881 2453509.7626349 6973722.6044772
 2453741.6496383 6972861.7554771 2454205.4590782 6971140.0630543
#Sta/Elev= 30
    1000   448.6    2309   447.8    2406   446.5    2661     431    3911   429.6
    3961   428.3    4000   413.4    4015   413.4    4022   419.5    4166   415.6
    5942   412.9    6777   417.4    6843   414.4    6873   422.7    6917   411.5
    6960   417.7    7190     418    7236   408.8    7268   409.7    7317     390
    7377   391.5    7421   403.1    7445   414.2    7874   413.6    7982     420
    8074   415.4    8339   415.4    8346   419.7    8370   422.9    8420   439.9
#Mann= 4 ,-1,0
    1000     .07       0    7190    .039       0    7445    .055       0
    8346     .03       0
#XS Ineff= 1 ,-1
    4990    5420     450
Permanent Ineff=
       F
Bank Sta=7190,7445
XS Rating Curve= 0 ,0
Exp/Cntr=0.3,0.1

Type RM Length L Ch R = 1 ,9859    ,95,95,95
BEGIN DESCRIPTION:
This cross section corresponds to cross section 9861 of the non-georeferenced CDC model which was the source of this model.
END DESCRIPTION:
XS GIS Cut Line= 6
   2453263.27986 6978342.9840159 2453265.7769024 6977926.0721201
 2453280.2880282 6977491.1920843 2453365.6480937 6976885.8921138
 2453572.3409218 6975826.5900986 2454511.7839248 6971270.0529518
#Sta/Elev= 30
    1000   448.6    1139   445.1    1199   447.3    1242   456.5    1284   456.1
    1306     451    1954   445.4    2855   419.9    3110   407.8    3131   411.9
    3622   417.4    3830   414.3    3886   416.9    3906   424.4    3938   419.2
    4071     414    4345   417.3    5916   413.7    5956   416.7    6600   417.5
    6610   423.3    6637   415.5    6934   420.1    6992     389    7072     394
    7125   410.2    7167   412.5    7511   418.9    8115   418.8    8186   439.6
#Mann= 4 ,-1,0
    1000     .07       0    6934    .039       0    7167    .055       0
    8115     .03       0
#XS Ineff= 1 ,-1
    4360    5577     450
Permanent Ineff=
       F
Bank Sta=6934,7167
XS Rating Curve= 0 ,0
Exp/Cntr=0.3,0.1

Type RM Length L Ch R = 1 ,9764    ,1,1,1
BEGIN DESCRIPTION:
This cross section corresponds to cross section 9764 of the non-georeferenced CDC model which was the source of this model.
END DESCRIPTION:
XS GIS Cut Line= 6
  2453357.112677 6978358.5043261   2453359.60972 6977941.5924302
 2453374.1208458 6977506.7123945 2453459.4809113  6976901.412424
 2453666.1737394 6975842.1104087 2454605.6167424  6971285.573262
#Sta/Elev= 30
    1000   448.6    1139   445.1    1199   447.3    1242   456.5    1284   456.1
    1306     451    1954   445.4    2855   419.9    3110   407.8    3131   411.9
    3284   414.3    3882   416.5    3906   424.4    3947   412.6    3966   412.5
    3999   419.2    4071     414    4345   417.3    5916   413.7    6600   417.5
    6610   423.3    6637   415.5    6934   420.1    6992     389    7072     394
    7125   410.2    7167   412.5    7511   418.9    8115   418.8    8186   439.6
#Mann= 4 ,-1,0
    1000     .07       0    6934    .039       0    7167    .055       0
    8115     .03       0
#XS Ineff= 2 ,-1
    4300    5650     450    1000    3850     450
Permanent Ineff=
       F       F
Bank Sta=6934,7167
XS Rating Curve= 0 ,0
Exp/Cntr=0.3,0.1

Type RM Length L Ch R = 1 ,9763    ,145,145,145
BEGIN DESCRIPTION:
This cross section corresponds to cross section 9763 of the non-georeferenced CDC model which was the source of this model.
END DESCRIPTION:
XS GIS Cut Line= 6
  2453358.890887 6978223.6600784 2453360.5795343 6977941.7374431
 2453375.0906602 6977506.8574073 2453460.4507257 6976901.5574368
 2453667.1435537 6975842.2554216 2454579.3246062 6971417.9284863
#Sta/Elev= 30
      50     440     450     436    1550     430    1980     432    2600   438.3
    2600     436    2625     414    2975     414    3050     436    3050   438.3
    3544   431.9    4005   430.1    4120     431    4427     439    4427     435
    4477   416.3    5320   415.6    5610     420    5655   418.6    5831   419.2
    5864   401.6    5878   396.1    5888     389    6012   396.1    6018   402.4
    6072   414.1    6683   413.1    6878   415.5    6921   422.4    6975   449.8
#Mann= 3 ,-1,0
      50     .07       0    5831    .039       0    6072    .055       0
Bank Sta=5831,6072
XS Rating Curve= 0 ,0
Exp/Cntr=0.5,0.3

Type RM Length L Ch R = 3 ,9691    ,,,
BEGIN DESCRIPTION:
Loop 12
END DESCRIPTION:
Node Name=Loop 12
Bridge Culvert--1,0,-1,-1, 0
Deck Dist Width WeirC Skew NumUp NumDn MinLoCord MaxHiCord MaxSubmerge Is_Ogee
0.5,144,2.6,0, 23, 23, , , 0.95, 0, ,,,
    2600    3050    3050    3123    3220    3309    3349    3430    3470    3544
    3718    3895    4005    4120    4153    4213    4286    4368    4427    4610
    4622    4870    7000
   438.3   438.3   438.3   437.6   436.8   435.8   435.6   433.7   433.5   431.9
   430.8   430.1   430.1     431   432.4   433.3     435   436.4     439     445
   445.4     452     452
     436     436   438.3   437.6   436.8   435.8   435.6   433.7   433.5   431.9
   430.8   430.1   430.1     431   432.4   433.3     435   436.4     439     441
   441.4     450     450
    2600    3050    3050    3123    3220    3309    3349    3430    3470    3544
    3718    3895    4005    4120    4153    4213    4286    4368    4427    4610
    4622    4870    7000
   438.3   438.3   438.3   437.6   436.8   435.8   435.6   433.7   433.5   431.9
   430.8   430.1   430.1     431   432.4   433.3     435   436.4     439     445
   445.4     452     452
     436     436   438.3   437.6   436.8   435.8   435.6   433.7   433.5   431.9
   430.8   430.1   430.1     431   432.4   433.3     435   436.4     439     441
   441.4     450     450
Pier Skew, UpSta & Num, DnSta & Num=  ,2647, 2 ,2647, 2 , 0 , 0 , 0 ,,
       4       4
     410     437
       4       4
     410     437
Pier Skew, UpSta & Num, DnSta & Num=  ,2722, 2 ,2722, 2 , 0 , 0 , 0 ,,
       4       4
     410     437
       4       4
     410     437
Pier Skew, UpSta & Num, DnSta & Num=  ,2802, 2 ,2802, 2 , 0 , 0 , 0 ,,
       4       4
     410     437
       4       4
     410     437
Pier Skew, UpSta & Num, DnSta & Num=  ,2902, 2 ,2902, 2 , 0 , 0 , 0 ,,
       4       4
     410     437
       4       4
     410     437
Pier Skew, UpSta & Num, DnSta & Num=  ,4616, 2 ,4616, 2 , 0 , 0 , 0 ,,
      12      12
     415   441.4
      12      12
     415   441.4
Pier Skew, UpSta & Num, DnSta & Num=  ,4870.5, 2 ,4870.5, 2 , 0 , 0 , 0 ,,
      15      15
     415   450.5
      15      15
     415   450.5
Pier Skew, UpSta & Num, DnSta & Num=  ,4954.5, 2 ,4954.5, 2 , 0 , 0 , 0 ,,
      15      15
     415   450.5
      15      15
     415   450.5
Pier Skew, UpSta & Num, DnSta & Num=  ,5102.5, 2 ,5102.5, 2 , 0 , 0 , 0 ,,
       5       5
     415   450.5
       5       5
     415   450.5
Pier Skew, UpSta & Num, DnSta & Num=  ,5613, 2 ,5613, 2 , 0 , 0 , 0 ,,
       6       6
     415   450.5
       6       6
     415   450.5
Pier Skew, UpSta & Num, DnSta & Num=  ,6015, 2 ,6015, 2 , 0 , 0 , 0 ,,
       6       6
     400   450.5
       6       6
     400   450.5
Pier Skew, UpSta & Num, DnSta & Num=  ,6152.5, 2 ,6152.5, 2 , 0 , 0 , 0 ,,
       5       5
     400   450.5
       5       5
     400   450.5
Pier Skew, UpSta & Num, DnSta & Num=  ,6231, 2 ,6231, 2 , 0 , 0 , 0 ,,
       6       6
     400   450.5
       6       6
     400   450.5
Pier Skew, UpSta & Num, DnSta & Num=  ,6337, 2 ,6337, 2 , 0 , 0 , 0 ,,
       6       6
     400   450.5
       6       6
     400   450.5
Pier Skew, UpSta & Num, DnSta & Num=  ,6432, 2 ,6432, 2 , 0 , 0 , 0 ,,
       6       6
     400   450.5
       6       6
     400   450.5
Pier Skew, UpSta & Num, DnSta & Num=  ,6675.5, 2 ,6675.5, 2 , 0 , 0 , 0 ,,
      15      15
     400   450.5
      15      15
     400   450.5
BR Coef= 1 , 0 , 0 ,1.05, 0 ,,,0.8,-1,0.5,1,
WSPro=,,,, 1 ,,,, 0 ,,,, 0 ,,,,-1 ,-1 ,-1 , 0 , 0 , 0 , 0 , 0
BC Design=,, 0 ,, 0 ,,,,,,
BC HTab HWMax=449.8
BC Use User HTab Curves=0
BC User HTab FreeFlow(D)= 0