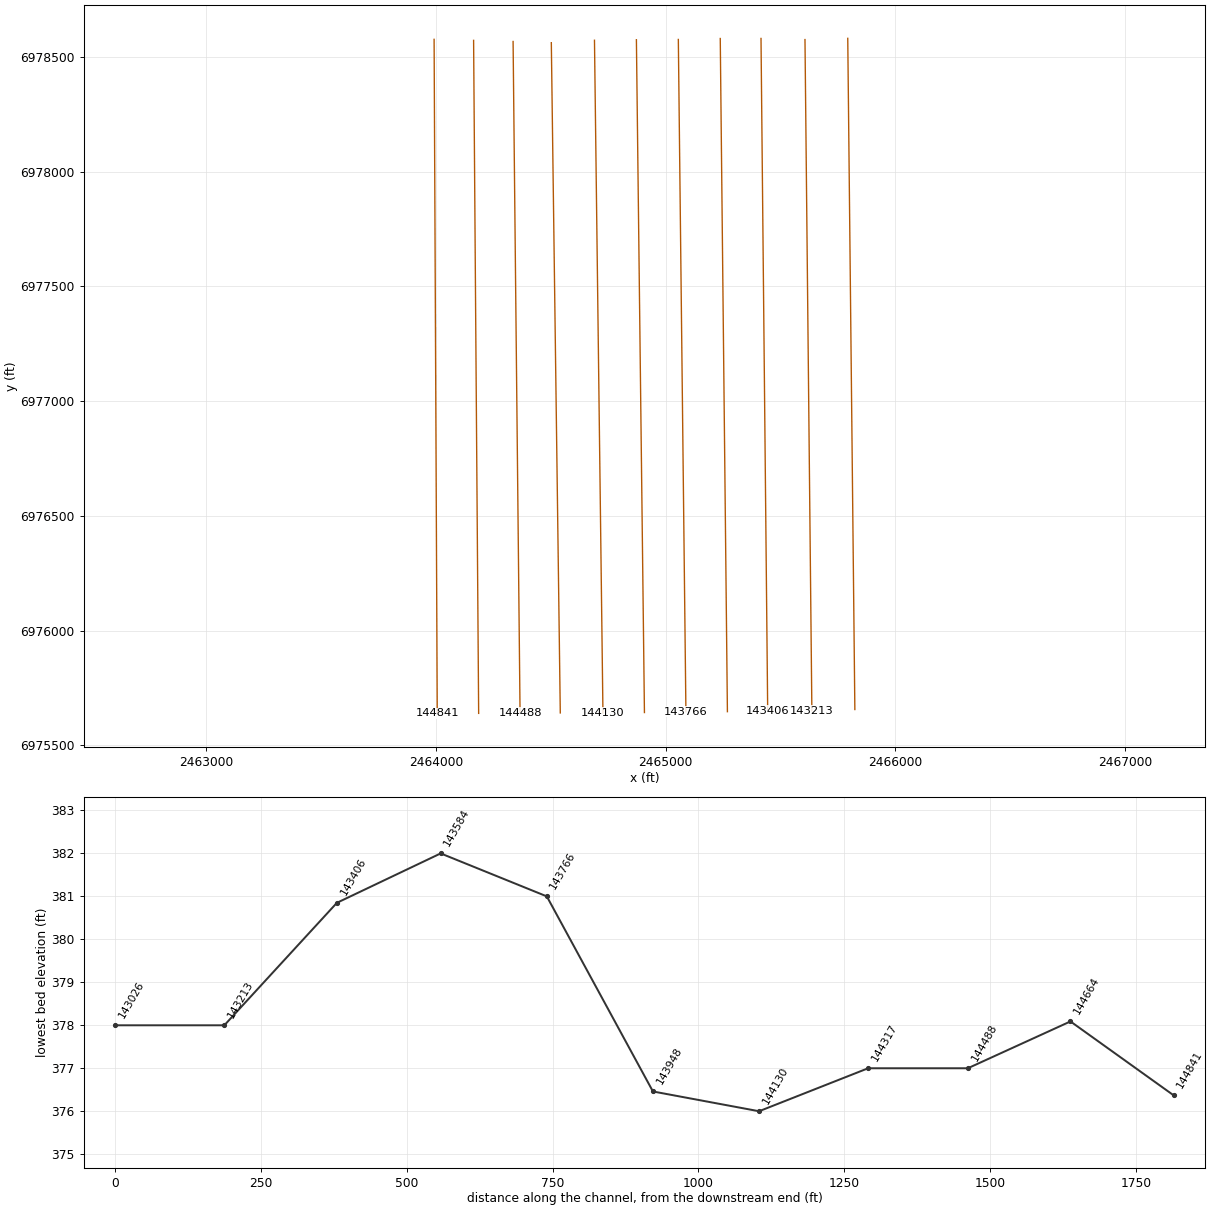
HEC-RAS study CDC_Consolidated_Model.prj: Upper Trinity CDC Consolidated Model

--- CDC_Consolidated_Model.g02 (geometry) --- (continued)

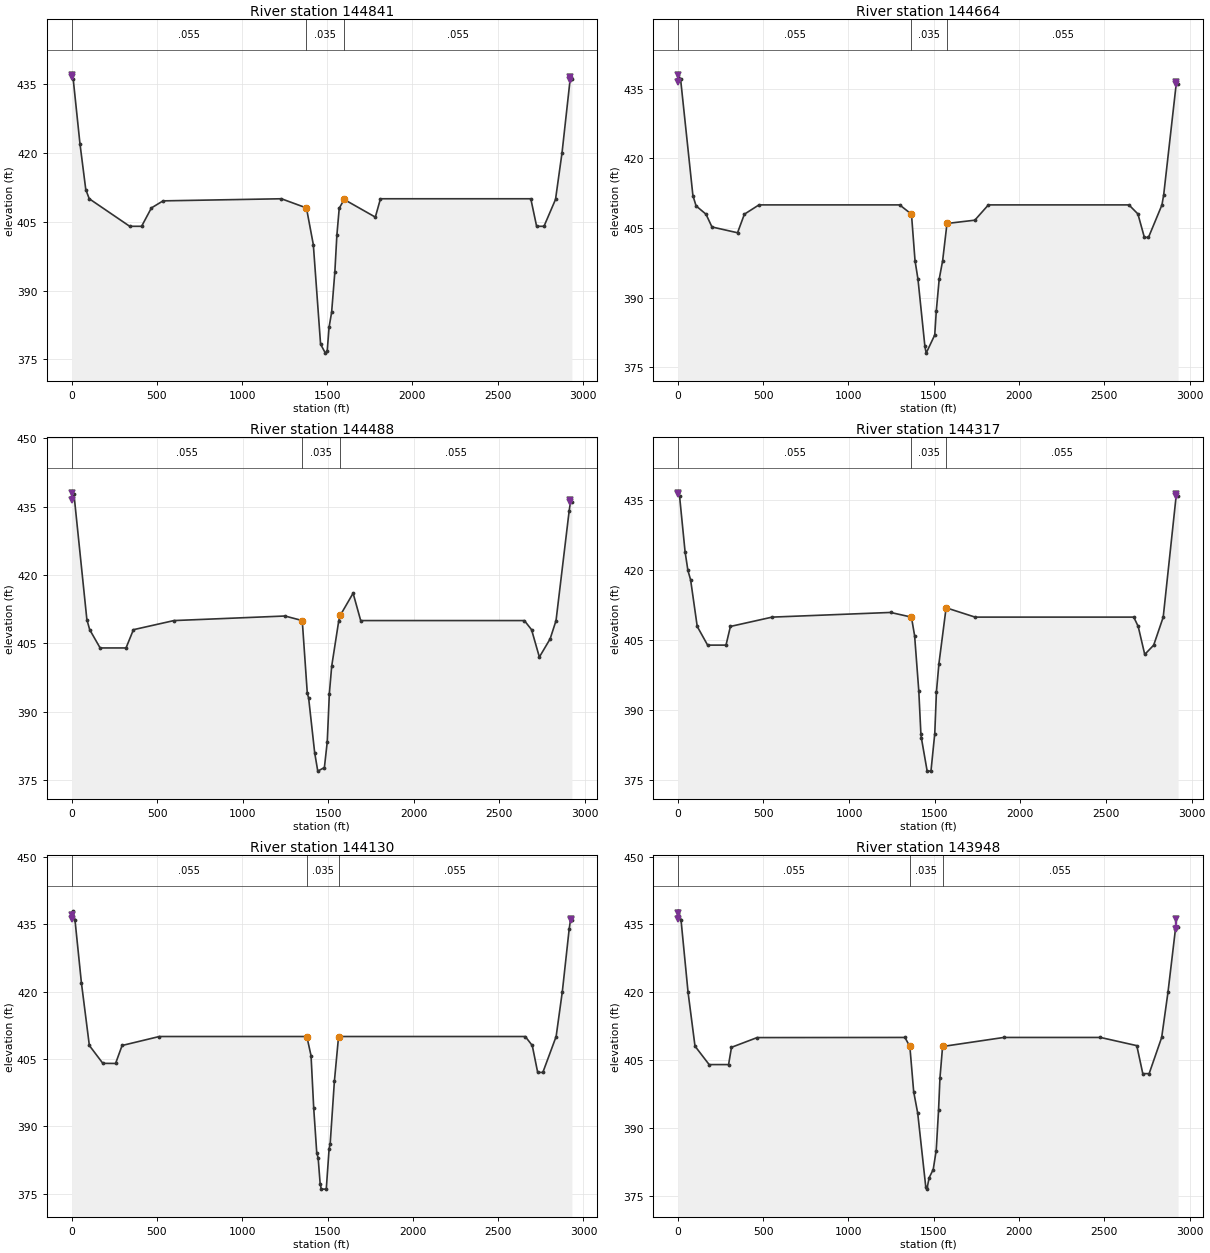
Type RM Length L Ch R = 1 ,144841  ,175,177,177
BEGIN DESCRIPTION:
This cross section corresponds to cross section 144840 of the non-georeferenced CDC model which was the source of this model.
END DESCRIPTION:
XS GIS Cut Line= 2
 2463991.48281056978576.529151222464005.193413026975639.96120547
#Sta/Elev= 30
       0     437    9.18     436   48.61     422   82.79     412  103.14     410
  340.65     404  410.45     404  467.98     408  536.32  409.54 1231.17     410
 1378.13     408 1418.56     400 1461.12  378.33 1489.26  376.37 1500.02  376.79
 1510.94     382 1525.89  385.24 1544.81     394 1556.67     402 1570.55  407.93
 1599.58  409.85 1782.55     406 1812.67     410 2695.19     410  2729.4     404
 2772.64     404 2840.31  409.86 2878.46     420 2925.64  435.85  2936.6     436
#Mann= 3 ,0,0
       0    .055       0 1378.13    .035       0 1599.58    .055       0
Levee=-1,0,436.42,-1,2926,436.42,,
#XS Ineff= 2 , 0
       0 1378.13     408 1599.58       0  409.85
Permanent Ineff=
       F       F
Bank Sta=1378.13,1599.58
XS Rating Curve= 0 ,0
Exp/Cntr=0.3,0.1

Type RM Length L Ch R = 1 ,144664  ,174,176,176
BEGIN DESCRIPTION:
This cross section corresponds to cross section 144664 of the non-georeferenced CDC model which was the source of this model.
END DESCRIPTION:
XS GIS Cut Line= 2
2464163.462781526978572.075091882464185.467330666975639.12754571
#Sta/Elev= 30
       0     438   15.92  437.15   88.38     412  107.02  409.78   165.1     408
  200.11  405.25     350     404  390.23     408  475.65     410 1300.59     410
 1369.85     408 1390.65     398 1407.97     394 1448.51  379.57    1456  378.09
 1506.31     382 1515.33  387.15 1532.34     394 1552.65     398 1578.15     406
 1741.22  406.71 1820.77     410 2644.78     410 2697.48  408.05 2735.41     403
 2759.47     403 2838.47     410 2848.72  412.19 2921.95     436 2933.03     436
#Mann= 3 ,0,0
       0    .055       0 1369.85    .035       0 1578.15    .055       0
Levee=-1,0,436.37,-1,2922,436.37,,
#XS Ineff= 2 , 0
       0 1369.85     408 1578.15       0     406
Permanent Ineff=
       F       F
Bank Sta=1369.85,1578.15
XS Rating Curve= 0 ,0
Exp/Cntr=0.3,0.1

Type RM Length L Ch R = 1 ,144488  ,169,171,171
BEGIN DESCRIPTION:
This cross section corresponds to cross section 144488 of the non-georeferenced CDC model which was the source of this model.
END DESCRIPTION:
XS GIS Cut Line= 2
2464335.404038676978567.13907814 2464365.70253456975642.77583238
#Sta/Elev= 30
       0     438   13.42  437.66   88.82  410.22  105.38     408  166.31     404
  317.72     404  360.96     408  597.74     410 1246.78     411 1347.99     410
 1377.41  394.11 1385.32     393 1420.73     381 1438.73     377 1477.44  377.79
 1494.18  383.45 1506.41     394 1520.11     400 1561.55     410 1571.19  411.21
 1645.26     416 1689.63     410 2646.47     410 2688.58     408 2734.22     402
 2797.26     406 2831.64     410 2908.28     434 2915.84     436 2924.52     436
#Mann= 3 ,0,0
       0    .055       0 1347.99    .035       0 1571.19    .055       0
Levee=-1,0,436.33,-1,2916,436.33,,
#XS Ineff= 2 , 0
       0 1347.99     410 1571.19       0  411.21
Permanent Ineff=
       F       F
Bank Sta=1347.99,1571.19
XS Rating Curve= 0 ,0
Exp/Cntr=0.3,0.1

Type RM Length L Ch R = 1 ,144317  ,186,187,186
BEGIN DESCRIPTION:
This cross section corresponds to cross section 144312 of the non-georeferenced CDC model which was the source of this model.
END DESCRIPTION:
XS GIS Cut Line= 2
2464501.848915766978561.873668722464540.880005666975641.12458897
#Sta/Elev= 30
       0  436.63    9.89     436   42.28     424   58.79     420   74.54     418
  113.24     408  173.84     404  281.22     404  306.97     408  550.86     410
 1242.23     411 1363.98     410 1382.63     406 1407.05  394.14 1419.15     385
 1421.82  384.17 1455.68  377.04 1478.03     377 1500.26  385.06 1510.03     394
 1524.43     400 1566.54     412 1735.59     410 2662.26     410 2688.09     408
 2726.31     402 2778.64     404 2834.22     410 2909.56   435.9 2921.01     436
#Mann= 3 ,0,0
       0    .055       0 1363.98    .035       0 1566.54    .055       0
Levee=-1,0,436.29,-1,2910,436.29,,
#XS Ineff= 2 , 0
       0 1363.98     410 1566.54       0     412
Permanent Ineff=
       F       F
Bank Sta=1363.98,1566.54
XS Rating Curve= 0 ,0
Exp/Cntr=0.3,0.1

Type RM Length L Ch R = 1 ,144130  ,182,182,182
BEGIN DESCRIPTION:
This cross section corresponds to cross section 144129 of the non-georeferenced CDC model which was the source of this model.
END DESCRIPTION:
XS GIS Cut Line= 2
2464689.745849676978572.57049772 2464726.64505416975640.56258221
#Sta/Elev= 30
       0  436.99    5.56     438   19.25     436   56.96     422   103.6     408
  182.73  404.02  257.35     404  295.49     408  513.65     410 1378.34     410
 1403.03  405.74 1418.81     394 1436.68     384 1444.63     383 1456.36  377.22
 1463.31     376 1492.31     376 1508.99     385 1515.03     386 1539.84     400
 1564.38     410 2658.75     410 2699.72     408 2731.58     402 2761.78     402
 2839.68     410 2875.99     420 2916.31     434 2924.16     436 2932.24     436
#Mann= 3 ,0,0
       0    .055       0 1378.34    .035       0 1564.38    .055       0
Levee=-1,0,436.25,-1,2924,436.25,,
#XS Ineff= 2 , 0
       0 1378.34     410 1564.38       0     410
Permanent Ineff=
       F       F
Bank Sta=1378.34,1564.38
XS Rating Curve= 0 ,0
Exp/Cntr=0.3,0.1

Type RM Length L Ch R = 1 ,143948  ,181,182,181
BEGIN DESCRIPTION:
This cross section corresponds to cross section 143947 of the non-georeferenced CDC model which was the source of this model.
END DESCRIPTION:
XS GIS Cut Line= 2
2464872.291088256978574.866424892464907.261818836975642.77484813
#Sta/Elev= 30
       0  437.41    2.71     438   18.64     436   59.86     420  100.61  408.08
  183.48     404  297.44     404  314.54  407.82  464.65  409.97 1331.13     410
 1360.02     408 1382.46     398 1406.02  393.27 1453.14     377 1459.86  376.46
 1473.04  378.97 1496.93   380.8  1514.5     385 1528.36     394 1536.42     401
 1551.89     408 1910.44     410 2477.33     410 2690.24  408.19 2725.47     402
 2762.61     402 2836.09     410 2873.08     420 2916.99     434  2932.3  434.46
#Mann= 3 ,0,0
       0    .055       0 1360.02    .035       0 1551.89    .055       0
Levee=-1,0,436.2,-1,2920,436.2,,
#XS Ineff= 2 , 0
       0 1360.02     408 1551.89       0     408
Permanent Ineff=
       F       F
Bank Sta=1360.02,1551.89
XS Rating Curve= 0 ,0
Exp/Cntr=0.3,0.1

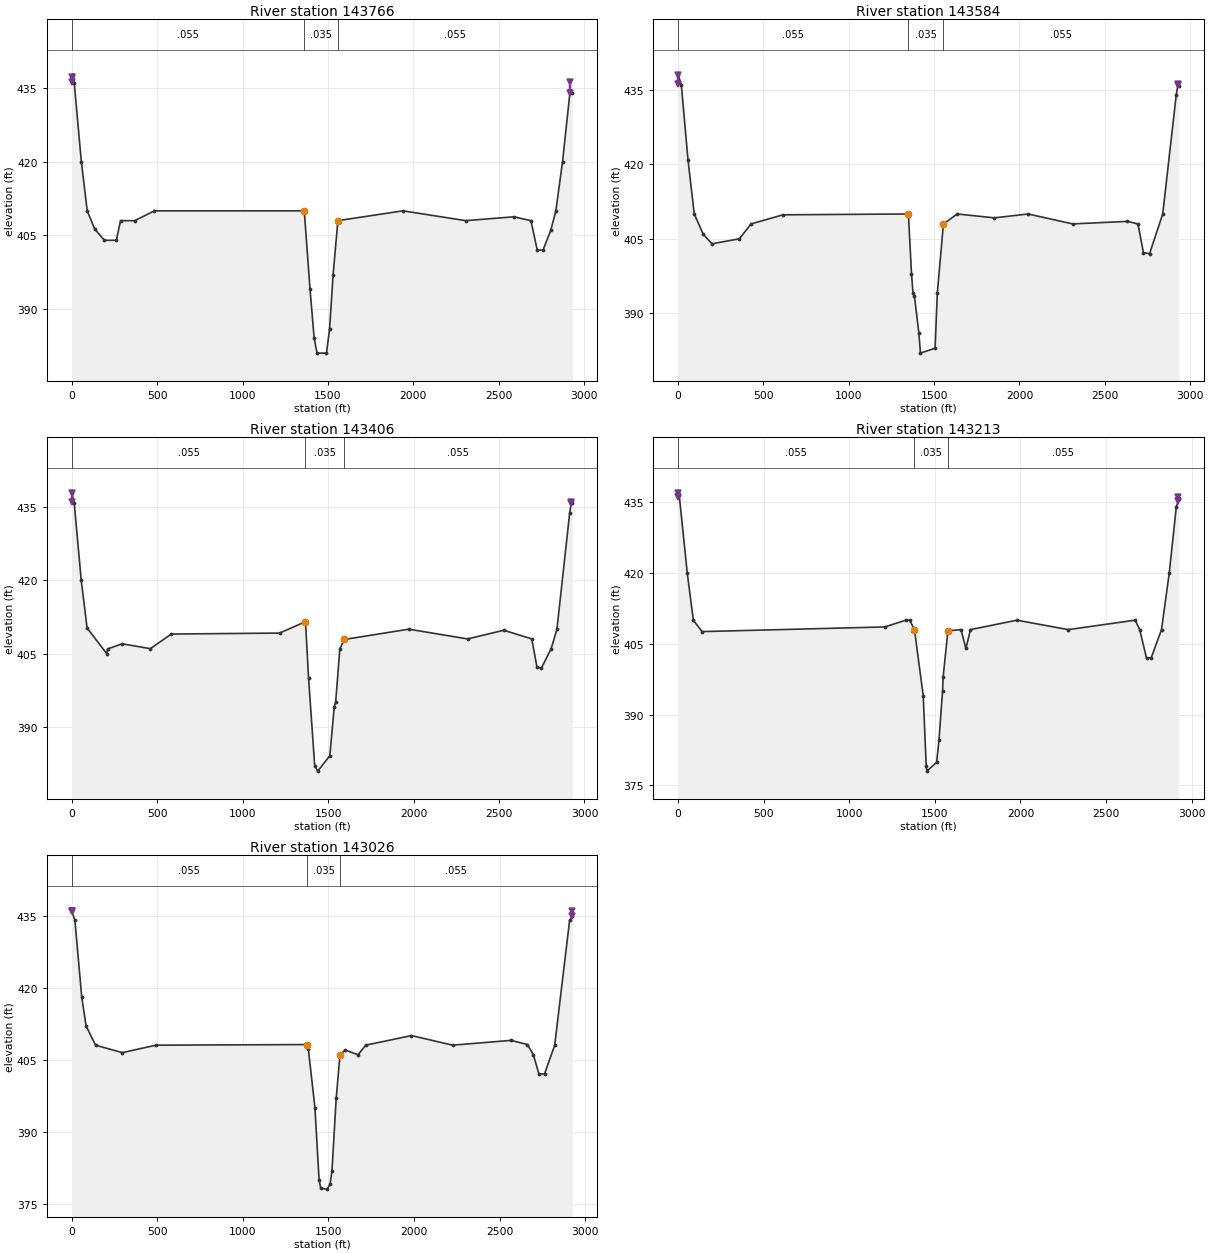
Type RM Length L Ch R = 1 ,143766  ,182,182,182
BEGIN DESCRIPTION:
This cross section corresponds to cross section 143764 of the non-georeferenced CDC model which was the source of this model.
END DESCRIPTION:
XS GIS Cut Line= 2
2465054.850434426978575.97665888  2465087.8644766975646.17280722
#Sta/Elev= 30
       0  437.37    7.15  437.72   15.05     436   56.51     420   90.85     410
  134.88  406.29  191.21     404  261.44     404  285.67     408  368.66     408
  483.95     410 1361.06     410 1394.92     394 1418.93   384.1 1435.69     381
 1491.15     381 1509.39     386 1529.94     397 1557.88     408 1938.89     410
 2305.84     408 2587.43  408.78 2687.91     408  2724.6     402 2758.42     402
 2803.58     406 2833.55     410 2872.68     420 2915.57  433.95 2929.99     434
#Mann= 3 ,0,0
       0    .055       0 1361.06    .035       0 1557.88    .055       0
Levee=-1,0,436.16,-1,2916,436.16,,
#XS Ineff= 2 , 0
       0 1361.06     410 1557.88       0     408
Permanent Ineff=
       F       F
Bank Sta=1361.06,1557.88
XS Rating Curve= 0 ,0
Exp/Cntr=0.3,0.1

Type RM Length L Ch R = 1 ,143584  ,178,178,178
BEGIN DESCRIPTION:
This cross section corresponds to cross section 143582 of the non-georeferenced CDC model which was the source of this model.
END DESCRIPTION:
XS GIS Cut Line= 2
2465237.374675666978580.121007552465268.502238096975646.53599547
#Sta/Elev= 30
       0     438   18.56     436   57.52  420.93   94.13  410.04   145.7     406
  197.39     404  358.41     405   427.3     408  614.08  409.83 1349.23     410
 1367.34     398 1376.33     394 1384.81  393.41 1410.61  386.01 1419.84     382
 1505.82  382.99 1518.48     394  1554.3  407.97 1635.29     410 1852.93  409.22
 2051.17     410 2311.47     408 2632.81  408.51 2694.55     408 2726.44  402.24
 2762.36     402 2839.57     410 2918.91     434 2928.71  435.98 2933.75  435.78
#Mann= 3 ,0,0
       0    .055       0 1349.23    .035       0  1554.3    .055       0
Levee=-1,0,436.11,-1,2929,436.11,,
#XS Ineff= 2 , 0
       0 1349.23     410  1554.3       0  407.97
Permanent Ineff=
       F       F
Bank Sta=1349.23,1554.3
XS Rating Curve= 0 ,0
Exp/Cntr=0.3,0.1

Type RM Length L Ch R = 1 ,143406  ,193,193,193
BEGIN DESCRIPTION:
This cross section corresponds to cross section 143400 of the non-georeferenced CDC model which was the source of this model.
END DESCRIPTION:
XS GIS Cut Line= 2
2465414.819202666978580.362476892465443.876231166975651.63670705
#Sta/Elev= 30
       0     438    14.5     436   55.58  420.13   89.98  410.24  204.76     405
  211.18  405.95  294.47     407  460.42     406  582.48     409  1216.1   409.2
 1367.81  411.54 1385.64     400  1421.6     382 1439.24  380.85 1510.12     384
 1535.71  393.97 1544.22     395 1568.82     406 1595.62  407.89 1972.11     410
 2316.11     408 2528.08  409.78 2691.85     408 2721.91   402.2  2747.6     402
 2804.55  405.95 2838.91     410 2913.12  433.79 2922.99     436 2928.87     436
#Mann= 3 ,0,0
       0    .055       0 1367.81    .035       0 1595.62    .055       0
Levee=-1,0,436.07,-1,2923,436.07,,
#XS Ineff= 2 , 0
       0 1367.81  411.54 1595.62       0  407.89
Permanent Ineff=
       F       F
Bank Sta=1367.81,1595.62
XS Rating Curve= 0 ,0
Exp/Cntr=0.3,0.1

Type RM Length L Ch R = 1 ,143213  ,187,187,187
BEGIN DESCRIPTION:
This cross section corresponds to cross section 143213 of the non-georeferenced CDC model which was the source of this model.
END DESCRIPTION:
XS GIS Cut Line= 2
2465606.275512676978575.489783212465636.285295166975650.50350721
#Sta/Elev= 30
       0     437    6.18  436.52   53.15     420   88.67     410  139.83  407.58
 1207.42  408.57 1329.51     410  1352.6     410 1380.65     408 1431.84     394
 1449.46     379 1453.63     378 1510.42   379.9 1524.11  384.68 1544.85     395
 1548.17  397.96 1576.15  407.75 1652.71     408 1681.12     404 1707.99     408
 1979.21     410 2279.23     408 2670.28     410 2696.71     408 2736.51     402
 2763.55     402 2824.14     408 2869.44     420  2910.5     434 2925.14  435.65
#Mann= 3 ,0,0
       0    .055       0 1380.65    .035       0 1576.15    .055       0
Levee=-1,0,436.02,-1,2922,436.02,,
#XS Ineff= 2 , 0
       0 1380.65     408 1576.15       0  407.75
Permanent Ineff=
       F       F
Bank Sta=1380.65,1576.15
XS Rating Curve= 0 ,0
Exp/Cntr=0.3,0.1

Type RM Length L Ch R = 1 ,143026  ,187,187,187
BEGIN DESCRIPTION:
This cross section corresponds to cross section 143026 of the non-georeferenced CDC model which was the source of this model.
END DESCRIPTION:
XS GIS Cut Line= 2
2465792.505455176978580.898893132465823.413529846975655.92213155
#Sta/Elev= 30
       0     436   18.85     434   58.75     418   84.18     412  139.52     408
  295.77  406.45  492.47     408 1374.61  408.13 1382.55  407.22 1421.18     395
 1445.32     380 1455.19  378.17 1491.35     378 1509.51  378.97 1520.56  381.71
 1545.42  396.94 1567.74     406 1598.14     407 1672.91     406 1718.06     408
 1985.33     410 2225.52     408 2567.05     409 2662.38  408.14 2697.67     406
 2729.97     402 2762.75     402  2822.1     408  2909.3     434 2925.14  434.85
#Mann= 3 ,0,0
       0    .055       0 1374.61    .035       0 1567.74    .055       0
Levee=-1,0,435.98,-1,2925,435.98,,
#XS Ineff= 2 , 0
       0 1374.61  408.13 1567.74       0     406
Permanent Ineff=
       F       F
Bank Sta=1374.61,1567.74
XS Rating Curve= 0 ,0
Exp/Cntr=0.3,0.1