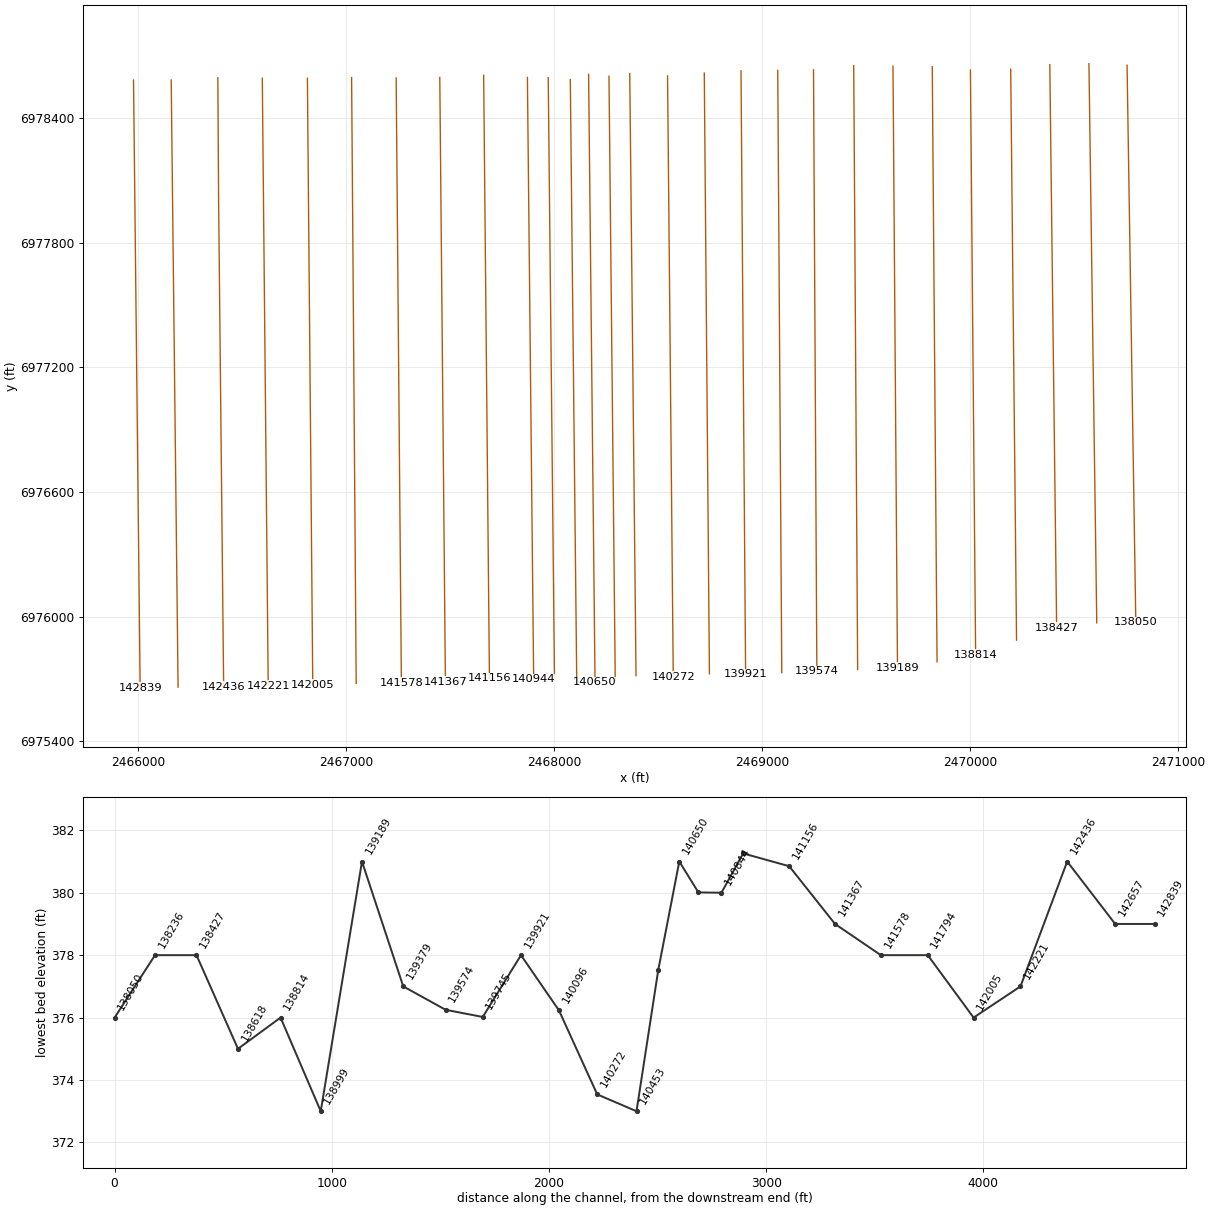
HEC-RAS study CDC_Consolidated_Model.prj: Upper Trinity CDC Consolidated Model

--- CDC_Consolidated_Model.g02 (geometry) --- (continued)

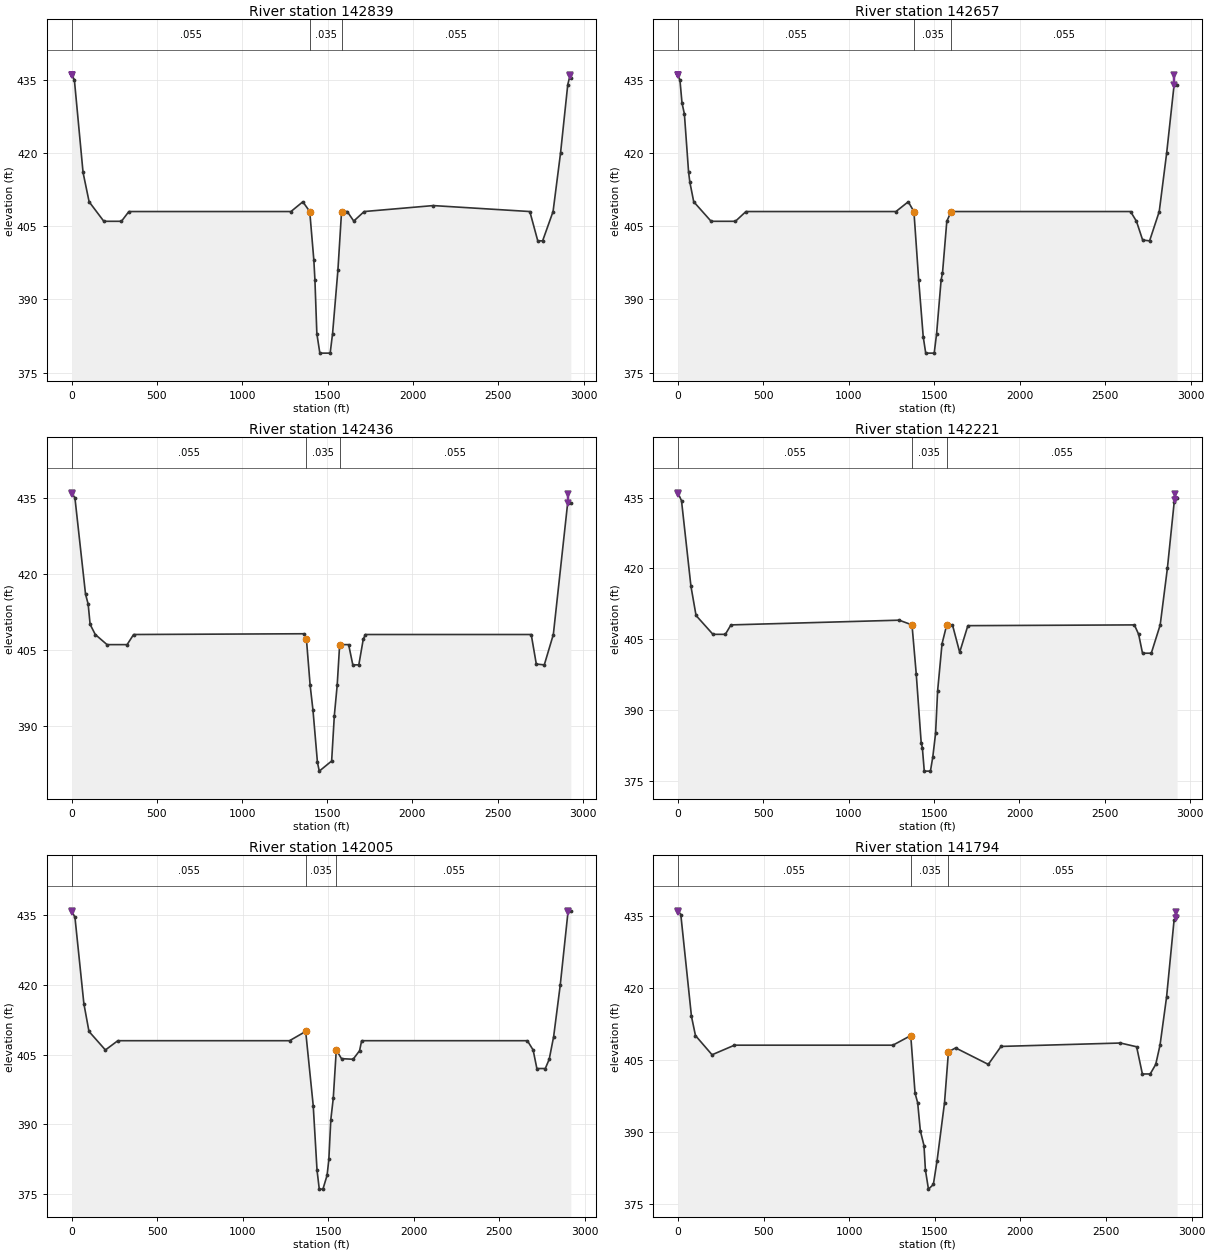
Type RM Length L Ch R = 1 ,142839  ,182,182,182
BEGIN DESCRIPTION:
This cross section corresponds to cross section 142839 of the non-georeferenced CDC model which was the source of this model.
END DESCRIPTION:
XS GIS Cut Line= 2
2465978.775423826978582.307682962466010.582446846975657.34076388
#Sta/Elev= 30
       0     436   16.06     435   66.98     416   102.5     410  188.74     406
  291.88     406  335.46     408  1285.2     408 1354.88     410 1395.25     408
 1419.44     398  1425.6     394 1436.88     383 1454.51     379 1514.92     379
 1529.05     383 1560.34     396 1581.72     408 1614.88     408 1653.08  406.05
 1714.29     408 2118.87  409.22 2684.87     408 2731.39     402 2759.88     402
 2821.03     408 2864.91     420 2907.18     434 2920.48  435.88 2925.14  435.39
#Mann= 3 ,0,0
       0    .055       0 1395.25    .035       0 1581.72    .055       0
Levee=-1,0,435.94,-1,2921,435.94,,
#XS Ineff= 2 , 0
       0 1395.25     408 1581.72       0     408
Permanent Ineff=
       F       F
Bank Sta=1395.25,1581.72
XS Rating Curve= 0 ,0
Exp/Cntr=0.3,0.1

Type RM Length L Ch R = 1 ,142657  ,220,221,220
BEGIN DESCRIPTION:
This cross section corresponds to cross section 142652 of the non-georeferenced CDC model which was the source of this model.
END DESCRIPTION:
XS GIS Cut Line= 2
2466159.834444916978582.615425142466192.884575676975661.38275056
#Sta/Elev= 30
       0     436    12.1  434.84   24.05  430.22   37.92     428   62.46  416.07
   69.95     414   92.59     410   194.4     406  336.44     406   398.2     408
 1276.09     408 1347.95     410 1381.16     408 1409.05     394  1435.6  382.36
 1450.19     379 1499.88     379 1513.93     383 1540.35     394 1548.36  395.37
 1573.61     406 1598.81     408 2649.01     408 2683.55     406 2719.71  402.16
 2760.32     402 2816.78     408 2860.34     420 2903.91     434 2921.42     434
#Mann= 3 ,0,0
       0    .055       0 1381.16    .035       0 1598.81    .055       0
Levee=-1,0,435.89,-1,2904,435.89,,
#XS Ineff= 2 , 0
       0 1381.16     408 1598.81       0     408
Permanent Ineff=
       F       F
Bank Sta=1381.16,1598.81
XS Rating Curve= 0 ,0
Exp/Cntr=0.3,0.1

Type RM Length L Ch R = 1 ,142436  ,214,215,214
BEGIN DESCRIPTION:
This cross section corresponds to cross section 142436 of the non-georeferenced CDC model which was the source of this model.
END DESCRIPTION:
XS GIS Cut Line= 3
2466383.967198766978593.199721552466387.703083666978001.33607589
2466411.909728176975663.65702422
#Sta/Elev= 30
       0     436   19.41     435   81.53     416   97.06     414  108.49     410
  138.79     408   207.9     406  325.56     406  363.72     408  1365.3  408.15
 1377.69  407.19 1399.66     398 1416.56     393 1442.62  382.74 1453.37     381
 1525.97     383 1541.72  391.97 1558.57     398 1572.95     406 1625.65     406
  1650.2     402  1685.5     402  1711.6  407.09 1724.25     408 2697.25     408
    2727  402.16 2773.95     402 2827.02     408 2911.13     434 2929.68     434
#Mann= 3 ,0,0
       0    .055       0 1377.69    .035       0 1572.95    .055       0
Levee=-1,0,435.84,-1,2911,435.84,,
#XS Ineff= 2 , 0
       0 1377.69  407.19 1572.95       0     406
Permanent Ineff=
       F       F
Bank Sta=1377.69,1572.95
XS Rating Curve= 0 ,0
Exp/Cntr=0.3,0.1

Type RM Length L Ch R = 1 ,142221  ,215,216,215
BEGIN DESCRIPTION:
This cross section corresponds to cross section 142220 of the non-georeferenced CDC model which was the source of this model.
END DESCRIPTION:
XS GIS Cut Line= 2
2466597.649186076978591.059305882466626.075966516975668.03759289
#Sta/Elev= 30
       0     436   21.13  434.32   76.22  416.22   106.2     410  205.19     406
  277.68     406  310.54     408 1295.65     409 1370.78     408 1395.42  397.68
 1424.57     383 1431.28     382 1442.66     377 1478.65     377 1492.53     380
 1508.79     385 1520.76     394  1546.6     404 1574.08     408 1607.82     408
 1649.93  402.19 1697.82  407.84 2672.93     408 2697.93     406 2720.57     402
 2771.95     402  2824.1     408 2866.19     420 2905.82  433.95 2923.16     435
#Mann= 3 ,0,0
       0    .055       0 1370.78    .035       0 1574.08    .055       0
Levee=-1,0,435.78,-1,2913,435.78,,
#XS Ineff= 2 , 0
       0 1370.78     408 1574.08       0     408
Permanent Ineff=
       F       F
Bank Sta=1370.78,1574.08
XS Rating Curve= 0 ,0
Exp/Cntr=0.3,0.1

Type RM Length L Ch R = 1 ,142005  ,211,211,211
BEGIN DESCRIPTION:
This cross section corresponds to cross section 142004 of the non-georeferenced CDC model which was the source of this model.
END DESCRIPTION:
XS GIS Cut Line= 2
2466814.435497916978590.682338132466840.237939756975673.41651914
#Sta/Elev= 30
       0     436   19.47   434.6   71.53     416  101.38     410  197.33     406
  269.96     408 1273.56     408 1367.82     410 1411.93     394 1434.12  380.09
 1447.28     376 1468.64     376 1492.96  378.99  1503.2  382.41 1514.74     391
 1529.04  395.58 1546.68     406 1577.15  404.13 1645.03     404 1682.84  405.85
 1694.85     408 2663.41     408 2697.02     406 2718.95     402 2768.07     402
 2791.06     404 2816.92  408.88 2855.53     420  2901.5     436 2917.38     436
#Mann= 3 ,0,0
       0    .055       0 1367.82    .035       0 1546.68    .055       0
Levee=-1,0,435.73,-1,2902,435.73,,
#XS Ineff= 2 , 0
       0 1367.82     410 1546.68       0     406
Permanent Ineff=
       F       F
Bank Sta=1367.82,1546.68
XS Rating Curve= 0 ,0
Exp/Cntr=0.3,0.1

Type RM Length L Ch R = 1 ,141794  ,215,216,215
BEGIN DESCRIPTION:
This cross section corresponds to cross section 141789 of the non-georeferenced CDC model which was the source of this model.
END DESCRIPTION:
XS GIS Cut Line= 2
2467026.870112426978594.102934972467048.915343916975678.89649504
#Sta/Elev= 30
       0     436   16.92  435.23   79.07  414.02  102.58     410  199.39     406
   330.3     408 1255.62     408 1359.76     410 1384.89     398 1400.19     396
 1415.71  390.16 1437.04  387.08 1445.35     382 1463.14     378 1491.83  378.97
 1513.44  383.91  1556.9  395.99 1579.87  406.62 1621.79  407.43  1812.6     404
 1887.01  407.74 2584.32  408.45 2678.82  407.67 2712.43     402 2758.17     402
 2790.45     404 2815.45     408 2853.64     418 2897.33     434 2915.29     435
#Mann= 3 ,0,0
       0    .055       0 1359.76    .035       0 1579.87    .055       0
Levee=-1,0,435.68,-1,2907,435.68,,
#XS Ineff= 2 , 0
       0 1359.76     410 1579.87       0  406.62
Permanent Ineff=
       F       F
Bank Sta=1359.76,1579.87
XS Rating Curve= 0 ,0
Exp/Cntr=0.3,0.1

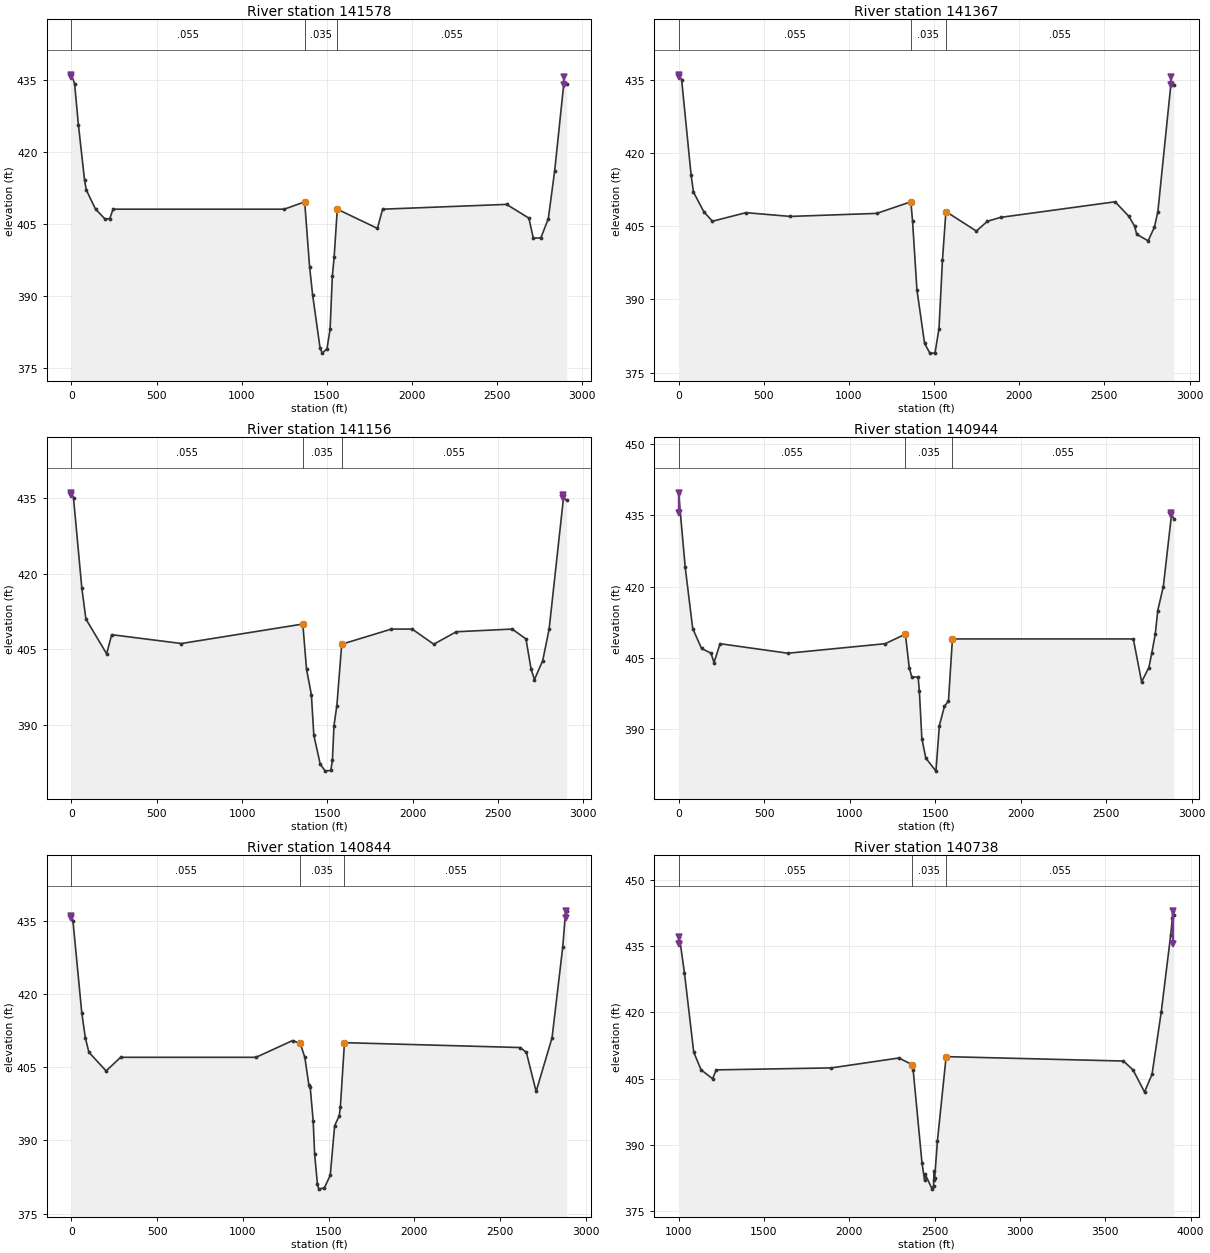
Type RM Length L Ch R = 1 ,141578  ,211,211,211
BEGIN DESCRIPTION:
This cross section corresponds to cross section 141576 of the non-georeferenced CDC model which was the source of this model.
END DESCRIPTION:
XS GIS Cut Line= 2
2467241.035038416978592.463174462467266.061891266975682.98080447
#Sta/Elev= 30
       0     436   18.58  434.17   40.95   425.6   77.34     414   87.41     412
  141.75     408  196.12     406  225.18     406  244.46     408 1250.74     408
 1370.36  409.53 1399.26     396 1417.22  390.09 1461.08     379 1474.05     378
 1501.53  378.92  1519.8     383 1532.73  393.97 1543.41  397.97 1561.96     408
 1797.72     404 1828.28     408 2556.51     409 2687.46  406.14  2713.5     402
 2757.65     402 2801.73     406 2839.13     416  2892.4     434 2909.59     434
#Mann= 3 ,0,0
       0    .055       0 1370.36    .035       0 1561.96    .055       0
Levee=-1,0,435.63,-1,2892,435.63,,
#XS Ineff= 2 , 0
       0 1370.36  409.53 1561.96       0     408
Permanent Ineff=
       F       F
Bank Sta=1370.36,1561.96
XS Rating Curve= 0 ,0
Exp/Cntr=0.3,0.1

Type RM Length L Ch R = 1 ,141367  ,212,211,212
BEGIN DESCRIPTION:
This cross section corresponds to cross section 141364 of the non-georeferenced CDC model which was the source of this model.
END DESCRIPTION:
XS GIS Cut Line= 2
2467450.691115176978594.968418812467477.716323586975687.50408939
#Sta/Elev= 30
       0     436   17.93     435   73.71   415.4   87.27     412  147.44     408
  198.35  406.01  395.34  407.77  655.49     407 1163.77  407.62 1363.69     410
 1373.59  406.08 1399.27     392 1444.31     381 1475.33     379 1505.36     379
 1528.86     384 1549.19     398 1569.58     408  1748.5     404 1812.71     406
 1890.05   406.8  2562.8     410 2644.09     407 2677.41     405 2689.68  403.35
 2756.91     402 2794.13  404.85 2814.01     408  2890.2     434 2907.59     434
#Mann= 3 ,0,0
       0    .055       0 1363.69    .035       0 1569.58    .055       0
Levee=-1,0,435.58,-1,2890,435.58,,
#XS Ineff= 2 , 0
       0 1363.69     410 1569.58       0     408
Permanent Ineff=
       F       F
Bank Sta=1363.69,1569.58
XS Rating Curve= 0 ,0
Exp/Cntr=0.3,0.1

Type RM Length L Ch R = 1 ,141156  ,212,212,212
BEGIN DESCRIPTION:
This cross section corresponds to cross section 141152 of the non-georeferenced CDC model which was the source of this model.
END DESCRIPTION:
XS GIS Cut Line= 2
2467661.556507086978605.269579312467689.257895266975703.52210197
#Sta/Elev= 30
       0     436   12.17     435    60.8  417.17   84.72     411  206.43  404.09
  235.74  407.89  644.36  406.14 1355.77     410 1377.79     401 1406.03     396
 1420.25     388  1458.2  382.18 1488.23  380.85 1519.91     381 1529.29     383
 1538.37  389.85 1555.43  393.84 1583.77     406 1875.21     409  1996.8     409
 2123.04     406 2255.16  408.47 2582.46     409 2663.35  407.05 2693.81     401
 2713.32     399 2761.71  402.77 2798.98  408.96 2883.33     435 2901.88   434.5
#Mann= 3 ,0,0
       0    .055       0 1355.77    .035       0 1583.77    .055       0
Levee=-1,0,435.52,-1,2883,435.52,,
#XS Ineff= 2 , 0
       0 1355.77     410 1583.77       0     406
Permanent Ineff=
       F       F
Bank Sta=1355.77,1583.77
XS Rating Curve= 0 ,0
Exp/Cntr=0.3,0.1

Type RM Length L Ch R = 1 ,140944  ,100,100,100
BEGIN DESCRIPTION:
This cross section corresponds to cross section 140940 of the non-georeferenced CDC model which was the source of this model.
END DESCRIPTION:
XS GIS Cut Line= 2
  2467871.8195386978594.781411312467901.872299436975699.21732055
#Sta/Elev= 30
       0  439.66   38.88     424   82.64  411.17  134.33     407  189.66     406
  207.12  404.04  242.71     408   639.1     406 1207.89     408 1326.21     410
 1348.49     403  1363.8     401 1400.74     401 1407.92     398 1422.51  388.09
 1445.52     384 1504.81  381.26 1524.76   390.8 1554.61  394.86 1578.12     396
 1601.21     409 2659.04     409 2707.41     400 2750.05     403 2766.77     406
 2787.13     410  2801.9  414.96 2834.34     420 2882.07     435 2895.72  434.27
#Mann= 3 ,0,0
       0    .055       0 1326.21    .035       0 1601.21    .055       0
Levee=-1,0,435.47,-1,2882,435.47,,
#XS Ineff= 2 , 0
       0 1326.21     410 1601.21       0     409
Permanent Ineff=
       F       F
Bank Sta=1326.21,1601.21
XS Rating Curve= 0 ,0
Exp/Cntr=0.3,0.1

Type RM Length L Ch R = 1 ,140844  ,106,106,106
BEGIN DESCRIPTION:
This cross section corresponds to cross section 140840 of the non-georeferenced CDC model which was the source of this model.
END DESCRIPTION:
XS GIS Cut Line= 2
 2467971.84919366978593.88147871 2468001.84125966975706.11724113
#Sta/Elev= 30
       0     436    8.74     435   60.73     416   81.07     411  101.88  408.04
  202.11  404.21  286.88     407 1076.51     407 1289.86  410.43 1334.14  409.84
 1360.97     407 1384.55  401.34 1392.15     401  1409.7     394 1418.42  387.15
 1434.57     381 1442.45     380 1475.13  380.28 1509.47  382.84 1534.93     393
 1561.62     395 1568.27   396.8  1592.2     410 2616.91     409 2652.96     408
 2709.94     400 2802.74     411 2865.05  429.58 2882.02     437 2887.92     437
#Mann= 3 ,0,0
       0    .055       0 1334.14    .035       0  1592.2    .055       0
Levee=-1,0,435.45,-1,2882,435.45,,
#XS Ineff= 2 , 0
       0 1334.14  409.84  1592.2       0     410
Permanent Ineff=
       F       F
Bank Sta=1334.14,1592.2
XS Rating Curve= 0 ,0
Exp/Cntr=0.3,0.1

Type RM Length L Ch R = 1 ,140738  ,88,88,88
BEGIN DESCRIPTION:
This cross section corresponds to cross section 140734 of the non-georeferenced CDC model which was the source of this model.
END DESCRIPTION:
XS GIS Cut Line= 2
2468077.969060096978585.032086972468108.966701516975683.96800722
#Sta/Elev= 30
    1000     437 1008.92     436 1034.21     429 1088.75     411 1132.01     407
 1199.26     405  1220.3     407 1894.56  407.45 2290.78  409.69 2368.01  408.19
 2374.15     407  2425.8     386 2441.46     382 2444.92  383.36 2485.59  380.01
 2493.62  380.78 2496.21     384 2497.58     382  2500.4  382.61 2516.55     391
 2567.45     410 3606.18     409 3662.13     407 3729.62     402 3773.65     406
 3827.28     420 3882.96  437.54 3892.98  441.48 3893.93     443 3901.23  442.02
#Mann= 3 ,0,0
    1000    .055       0 2368.01    .035       0 2567.45    .055       0
Levee=-1,1000,435.42,-1,3894,435.42,,
#XS Ineff= 2 , 0
    1000 2368.01  408.19 2567.45    1000     410
Permanent Ineff=
       F       F
Bank Sta=2368.01,2567.45
XS Rating Curve= 0 ,0
Exp/Cntr=0.3,0.1

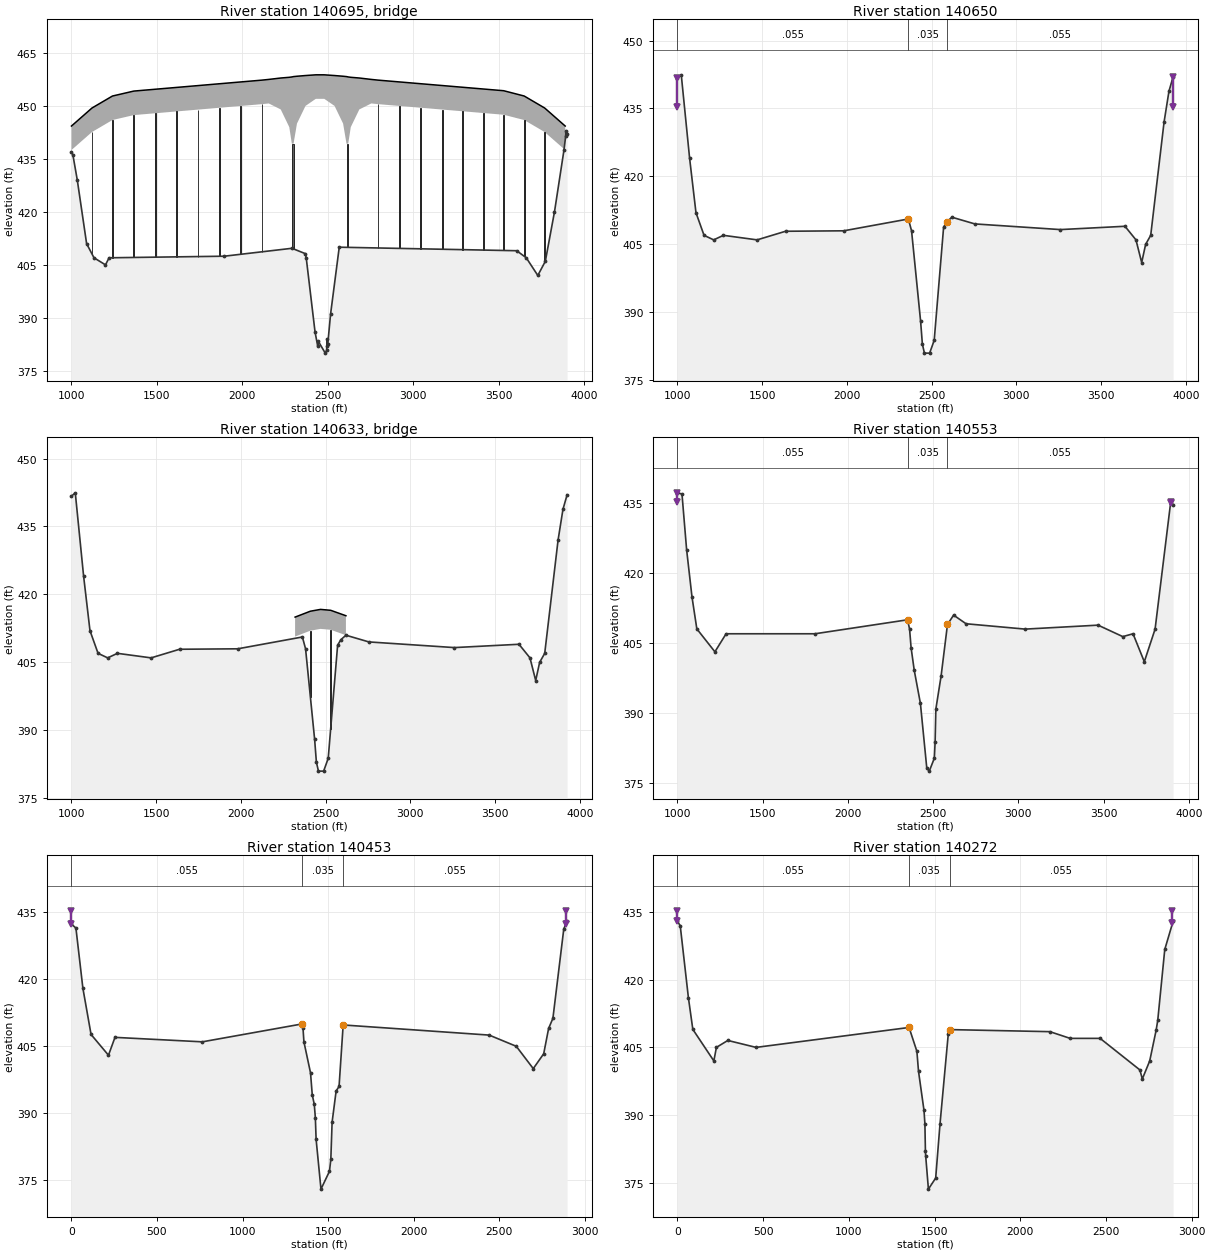
Type RM Length L Ch R = 3 ,140695  ,,,
BEGIN DESCRIPTION:
140690  Westmoreland Road
END DESCRIPTION:
Node Name=Westmoreland Roa
Bridge Culvert--1,0,-1,-1, 0
Deck Dist Width WeirC Skew NumUp NumDn MinLoCord MaxHiCord MaxSubmerge Is_Ogee
1,84,2.6,0, 26, 26, , , 0.95, 0, ,,,
    1000    1120    1240    1365    2115    2155    2225    2275    2290    2300
    2320    2370    2430    2480    2540    2590    2610    2620    2635    2685
    2755    2795    3530    3650    3770    3890
   444.3   449.4   452.8   454.2   457.3   457.5   457.9   458.1   458.2   458.3
   458.4   458.6   458.8   458.8   458.6   458.4   458.3   458.2   458.1   457.9
   457.5   457.3   454.3   452.8   449.4   444.3
   437.5   442.6     446   447.4   450.5   450.7     449     444   439.3   439.3
     445     450     452     452     450     445   439.3   439.3     444     449
   450.7   450.5   447.5     446   442.6   437.5
    1000    1120    1240    1365    2115    2155    2225    2275    2290    2300
    2320    2370    2430    2480    2540    2590    2610    2620    2635    2685
    2755    2795    3530    3650    3770    3890
   444.3   449.4   452.8   454.2   457.3   457.5   457.9   458.1   458.2   458.3
   458.4   458.6   458.8   458.8   458.6   458.4   458.3   458.2   458.1   457.9
   457.5   457.3   454.3   452.8   449.4   444.3
   437.5   442.6     446   447.4   450.5   450.7     449     444   439.3   439.3
     445     450     452     452     450     445   439.3   439.3     444     449
   450.7   450.5   447.5     446   442.6   437.5
Pier Skew, UpSta & Num, DnSta & Num=  ,1120, 2 ,1120, 2 , 0 , 0 , 0 ,,
       4       4
       0     450
       4       4
       0     450
Pier Skew, UpSta & Num, DnSta & Num=  ,1240, 2 ,1240, 2 , 0 , 0 , 0 ,,
       4       4
       0     450
       4       4
       0     450
Pier Skew, UpSta & Num, DnSta & Num=  ,1365, 2 ,1365, 2 , 0 , 0 , 0 ,,
       4       4
       0     450
       4       4
       0     450
Pier Skew, UpSta & Num, DnSta & Num=  ,1490, 2 ,1490, 2 , 0 , 0 , 0 ,,
       4       4
       0     450
       4       4
       0     450
Pier Skew, UpSta & Num, DnSta & Num=  ,1615, 2 ,1615, 2 , 0 , 0 , 0 ,,
       4       4
       0     450
       4       4
       0     450
Pier Skew, UpSta & Num, DnSta & Num=  ,1740, 2 ,1740, 2 , 0 , 0 , 0 ,,
       4       4
       0     455
       4       4
       0     455
Pier Skew, UpSta & Num, DnSta & Num=  ,1865, 2 ,1865, 2 , 0 , 0 , 0 ,,
       4       4
       0     455
       4       4
       0     455
Pier Skew, UpSta & Num, DnSta & Num=  ,1990, 2 ,1990, 2 , 0 , 0 , 0 ,,
       4       4
       0     455
       4       4
       0     455
Pier Skew, UpSta & Num, DnSta & Num=  ,2115, 2 ,2115, 2 , 0 , 0 , 0 ,,
       4       4
       0     455
       4       4
       0     455
Pier Skew, UpSta & Num, DnSta & Num=  ,2295, 2 ,2295, 2 , 0 , 0 , 0 ,,
      10      10
       0     455
      10      10
       0     455
Pier Skew, UpSta & Num, DnSta & Num=  ,2615, 2 ,2615, 2 , 0 , 0 , 0 ,,
      10      10
       0     455
      10      10
       0     455
Pier Skew, UpSta & Num, DnSta & Num=  ,2795, 2 ,2795, 2 , 0 , 0 , 0 ,,
       4       4
       0     455
       4       4
       0     455
Pier Skew, UpSta & Num, DnSta & Num=  ,2920, 2 ,2920, 2 , 0 , 0 , 0 ,,
       4       4
       0     455
       4       4
       0     455
Pier Skew, UpSta & Num, DnSta & Num=  ,3045, 2 ,3045, 2 , 0 , 0 , 0 ,,
       4       4
       0     455
       4       4
       0     455
Pier Skew, UpSta & Num, DnSta & Num=  ,3170, 2 ,3170, 2 , 0 , 0 , 0 ,,
       4       4
       0     455
       4       4
       0     455
Pier Skew, UpSta & Num, DnSta & Num=  ,3290, 2 ,3290, 2 , 0 , 0 , 0 ,,
       4       4
       0     455
       4       4
       0     455
Pier Skew, UpSta & Num, DnSta & Num=  ,3410, 2 ,3410, 2 , 0 , 0 , 0 ,,
       4       4
       0     455
       4       4
       0     455
Pier Skew, UpSta & Num, DnSta & Num=  ,3530, 2 ,3530, 2 , 0 , 0 , 0 ,,
       4       4
       0     450
       4       4
       0     450
Pier Skew, UpSta & Num, DnSta & Num=  ,3650, 2 ,3650, 2 , 0 , 0 , 0 ,,
       4       4
       0     450
       4       4
       0     450
Pier Skew, UpSta & Num, DnSta & Num=  ,3770, 2 ,3770, 2 , 0 , 0 , 0 ,,
       4       4
       0     450
       4       4
       0     450
BR Coef= 1 , 0 , 0 ,1.05, 0 ,,,0.8,-1,1.2,1,
WSPro=,,,, 1 ,,,, 0 ,,,, 0 ,,,,-1 ,-1 ,-1 , 0 , 0 , 0 , 0 , 0
BC Design=,, 0 ,, 0 ,,,,,,
BC HTab HWMax=441
BC Use User HTab Curves=0
BC User HTab FreeFlow(D)= 0

Type RM Length L Ch R = 1 ,140650  ,97,97,97
BEGIN DESCRIPTION:
This cross section corresponds to cross section 140646 of the non-georeferenced CDC model which was the source of this model.
END DESCRIPTION:
XS GIS Cut Line= 2
2468165.901298916978609.637352722468196.886801246975684.36170721
#Sta/Elev= 30
    1000  441.69 1022.58  442.43 1071.86     424 1109.39     412 1157.05     407
 1213.89     406  1271.3     407  1470.2     406 1638.14   407.9 1981.43     408
 2362.99  410.61 2381.77     408 2435.27     388  2445.6     383 2457.73     381
 2488.36     381 2515.42  383.82 2570.96   408.8 2589.87     410    2620     411
 2755.34  409.52 3259.97  408.27 3641.35     409 3706.22     406 3739.98     401
 3763.19     405 3793.24     407 3872.07     432 3900.94   438.8 3925.44     442
#Mann= 3 ,0,0
    1000    .055       0 2362.99    .035       0 2589.87    .055       0
Levee=-1,1000,435.4,-1,3925,435.4,,
#XS Ineff= 2 , 0
       0 2362.99  410.61 2589.87       0     410
Permanent Ineff=
       F       F
Bank Sta=2362.99,2589.87
XS Rating Curve= 0 ,0
Exp/Cntr=0.3,0.1

Type RM Length L Ch R = 3 ,140633  ,,,
BEGIN DESCRIPTION:
140629  channel bridge
END DESCRIPTION:
Node Name=channel bridge
Bridge Culvert--1,0,-1,-1, 0
Deck Dist Width WeirC Skew NumUp NumDn MinLoCord MaxHiCord MaxSubmerge Is_Ogee
2,30,2.6,0, 5, 5, , , 0.95, 0, 0,0,,
    2320    2410    2470    2530    2620
     415   416.3   416.7   416.5   415.3
   410.7     412   412.4   412.2     411
    2320    2410    2470    2530    2620
     415   416.3   416.7   416.5   415.3
   410.7     412   412.4   412.2     411
Pier Skew, UpSta & Num, DnSta & Num=  ,2410, 2 ,2410, 2 , 0 , 0 , 0 ,,
       3       3
       0     414
       3       3
       0     414
Pier Skew, UpSta & Num, DnSta & Num=  ,2530, 2 ,2530, 2 , 0 , 0 , 0 ,,
       3       3
       0     414
       3       3
       0     414
BR Coef=-1 , 1 , 1 ,1.25, 0 ,,,0.8,-1,2,1,
WSPro=,,,, 1 ,,,, 0 ,,,, 0 ,,,,-1 ,-1 ,-1 , 0 , 0 , 0 , 0 , 0
BC Design=,, 0 ,, 0 ,,,,,,
BC HTab HWMax=442.43
BC Use User HTab Curves=0
BC User HTab FreeFlow(D)= 0

Type RM Length L Ch R = 1 ,140553  ,100,100,100
BEGIN DESCRIPTION:
This cross section corresponds to cross section 140548 of the non-georeferenced CDC model which was the source of this model.
END DESCRIPTION:
XS GIS Cut Line= 2
2468263.801365586978600.696425722468293.99684325 6975693.3029623
#Sta/Elev= 30
    1000  437.25 1026.64     437 1053.94     425 1085.28  414.93 1113.75  408.05
 1219.78  403.13 1285.44     407 1806.81     407 2349.99     410 2361.71     408
  2370.6     404 2388.98  399.18 2425.26  392.05 2462.56   378.2 2477.38  377.52
  2506.9   380.3 2511.56  383.81 2515.91  390.85 2546.77  397.98 2584.06     409
    2620     411 2692.97  409.15 3039.91     408 3467.48  408.85 3612.45  406.39
 3672.45     407 3738.64     401 3801.85     408 3892.55     435 3907.55  434.57
#Mann= 3 ,0,0
    1000    .055       0 2349.99    .035       0 2584.06    .055       0
Levee=-1,1000,435.38,-1,3893,435.38,,
#XS Ineff= 2 , 0
       0 2349.99     410 2584.06       0     409
Permanent Ineff=
       F       F
Bank Sta=2349.99,2584.06
XS Rating Curve= 0 ,0
Exp/Cntr=0.3,0.1

Type RM Length L Ch R = 1 ,140453  ,181,181,181
BEGIN DESCRIPTION:
This cross section corresponds to cross section 140448 of the non-georeferenced CDC model which was the source of this model.
END DESCRIPTION:
XS GIS Cut Line= 2
2468363.703396776978613.530717632468393.827024166975716.46728605
#Sta/Elev= 30
       0  432.38   26.15  431.49   66.87     418  114.63  407.65  216.43     403
  254.37     407  764.98     406 1346.96     410 1353.56     409 1358.79     406
 1397.39  399.05 1407.55  394.11 1419.32     392 1425.65     389 1430.04  384.16
 1458.53     373 1508.18     377 1516.08  379.69 1523.53     388 1547.09     395
 1564.24     396 1588.19  409.78 2441.62  407.51 2600.08     405  2699.3     400
 2760.35  403.33 2789.04     409 2814.13  411.26 2877.75   431.3 2897.22     433
#Mann= 3 ,0,0
       0    .055       0 1346.96    .035       0 1588.19    .055       0
Levee=-1,0,435.35,-1,2891,435.35,,
#XS Ineff= 2 , 0
       0 1346.96     410 1588.19       0  409.78
Permanent Ineff=
       F       F
Bank Sta=1346.96,1588.19
XS Rating Curve= 0 ,0
Exp/Cntr=0.3,0.1

Type RM Length L Ch R = 1 ,140272  ,176,176,176
BEGIN DESCRIPTION:
This cross section corresponds to cross section 140272 of the non-georeferenced CDC model which was the source of this model.
END DESCRIPTION:
XS GIS Cut Line= 2
2468545.414975586978601.908365552468572.809933936975710.20811221
#Sta/Elev= 30
       0     433   16.31     432   64.05     416   89.73     409  212.41     402
  227.39     405  293.93  406.54  458.71     405 1351.36  409.42 1397.01  404.12
 1406.48  399.68 1438.53     391 1443.76  388.02 1446.74     382 1448.15     381
 1464.19  373.54 1506.65     376 1531.87     388 1580.16     408 1587.49  408.95
 2173.03  408.49 2291.09     407 2466.02     407 2697.89     400 2712.26     398
 2755.36     402 2792.63  408.77  2802.2     411 2843.15  426.73 2891.83     433
#Mann= 3 ,0,0
       0    .055       0 1351.36    .035       0 1587.49    .055       0
Levee=-1,0,435.31,-1,2888,435.31,,
#XS Ineff= 2 , 0
       0 1351.36  409.42 1587.49       0  408.95
Permanent Ineff=
       F       F
Bank Sta=1351.36,1587.49
XS Rating Curve= 0 ,0
Exp/Cntr=0.3,0.1

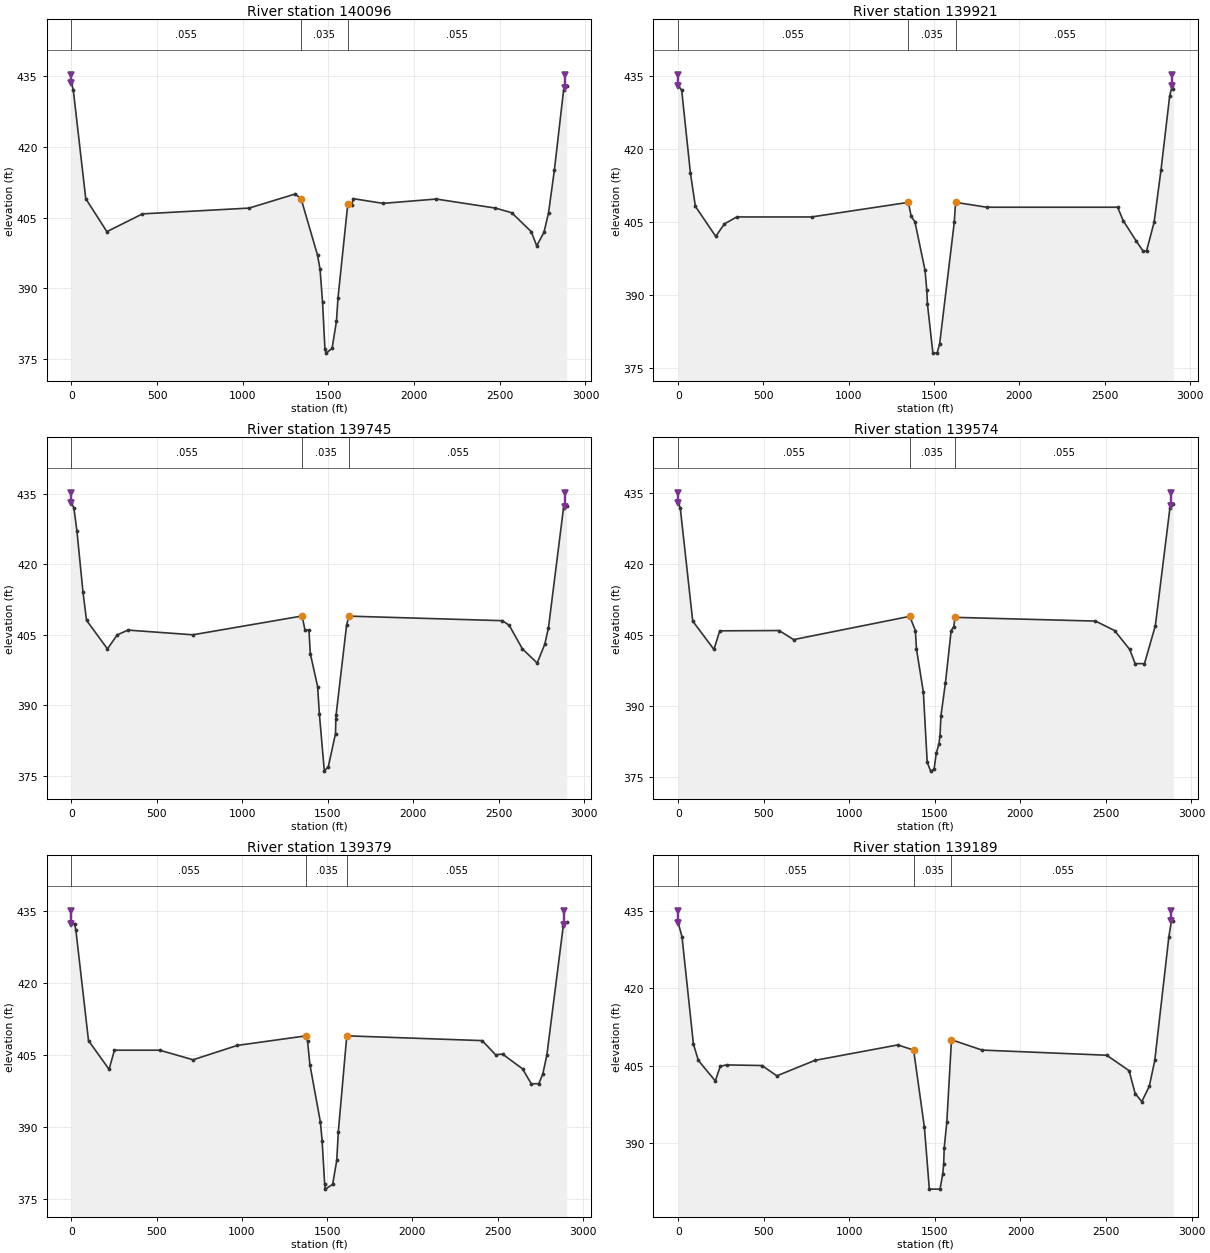
Type RM Length L Ch R = 1 ,140096  ,175,175,175
BEGIN DESCRIPTION:
This cross section corresponds to cross section 140096 of the non-georeferenced CDC model which was the source of this model.
END DESCRIPTION:
XS GIS Cut Line= 2
2468721.880501936978615.703613552468746.573693996975725.68905239
#Sta/Elev= 30
       0  433.62      11     432    83.6     409     207     402  414.43  405.77
  1037.1     407 1305.23  409.98 1340.09     409 1436.34     397 1450.96     394
 1465.66     387 1479.62     377 1487.16  376.23 1521.28  377.27 1546.81     383
 1555.78     388 1612.87  407.84 1634.52  407.64 1645.41     409  1818.6     408
 2128.75  408.92 2474.77     407 2569.54  406.01 2683.53     402 2715.42     399
  2757.6  401.83  2784.4     406 2818.27  414.99 2872.27  432.04 2890.12  432.91
#Mann= 3 ,0,0
       0    .055       0 1340.09    .035       0 1612.87    .055       0
Levee=-1,0,435.27,-1,2880,435.27,,
#XS Ineff= 2 , 0
       0 1340.09     409 1612.87       0  407.84
Permanent Ineff=
       F       F
Bank Sta=1340.09,1612.87
XS Rating Curve= 0 ,0
Exp/Cntr=0.3,0.1

Type RM Length L Ch R = 1 ,139921  ,176,176,176
BEGIN DESCRIPTION:
This cross section corresponds to cross section 139920 of the non-georeferenced CDC model which was the source of this model.
END DESCRIPTION:
XS GIS Cut Line= 2
2468898.38507017 6978626.68882782468920.487716266975723.98301905
#Sta/Elev= 30
       0     433   20.51  432.07   71.47   415.1  100.67  408.19  220.09     402
  270.49  404.56  343.16     406  782.01     406 1349.18     409 1365.75  406.12
  1387.7     405 1447.11     395 1456.88     391 1461.28     388 1492.96     378
 1517.66     378 1532.66  379.93 1618.39  404.91  1625.8     409 1808.28     408
 2575.75     408 2608.39  405.25 2685.64     401  2724.8     399 2745.23     399
 2789.66  404.92 2830.34  415.74 2880.75  430.85  2895.7     433 2902.79  432.24
#Mann= 3 ,0,0
       0    .055       0 1349.18    .035       0  1625.8    .055       0
Levee=-1,0,435.22,-1,2896,435.22,,
#XS Ineff= 2 , 0
       0 1349.18     409  1625.8       0     409
Permanent Ineff=
       F       F
Bank Sta=1349.18,1625.8
XS Rating Curve= 0 ,0
Exp/Cntr=0.3,0.1

Type RM Length L Ch R = 1 ,139745  ,171,171,171
BEGIN DESCRIPTION:
This cross section corresponds to cross section 139744 of the non-georeferenced CDC model which was the source of this model.
END DESCRIPTION:
XS GIS Cut Line= 2
2469074.957879756978628.97195971 2469094.33316916975730.97677146
#Sta/Elev= 30
       0     433   14.31     432   32.36     427   67.91     414   88.44  408.08
  210.82     402  268.44     405  331.31     406  710.37     405 1350.02     409
 1366.79     406 1390.05     406 1397.94     401 1440.77     394 1451.07  388.12
 1480.05  376.02 1503.49     377  1545.4     384  1547.2     387 1548.93     388
 1610.12     407 1622.96  408.97 2522.53     408 2562.23     407 2639.17     402
 2725.66     399    2770     403 2791.44  406.45 2879.83     432 2898.06  432.48
#Mann= 3 ,0,0
       0    .055       0 1350.02    .035       0 1622.96    .055       0
Levee=-1,0,435.18,-1,2888,435.18,,
#XS Ineff= 2 , 0
       0 1350.02     409 1622.96       0  408.97
Permanent Ineff=
       F       F
Bank Sta=1350.02,1622.96
XS Rating Curve= 0 ,0
Exp/Cntr=0.3,0.1

Type RM Length L Ch R = 1 ,139574  ,195,195,195
BEGIN DESCRIPTION:
This cross section corresponds to cross section 139569 of the non-georeferenced CDC model which was the source of this model.
END DESCRIPTION:
XS GIS Cut Line= 2
2469246.91357258 6978631.25771632469262.932569416975736.74217989
#Sta/Elev= 30
       0     433   11.98     432   84.92     408     209     402  242.97  405.94
     590     406  674.44  404.08 1353.45     409 1386.33     406 1392.88  402.05
    1433     393 1455.57   378.1 1475.84  376.25 1495.75  376.65 1508.11     380
 1524.06     382 1530.45  383.76 1535.68  387.93 1562.15  394.97 1595.57     406
 1610.31  406.81 1618.66  408.79 2439.14     408  2550.6     406 2639.17     402
 2670.84     399 2725.32     399 2788.85     407 2874.36     432 2894.56   432.7
#Mann= 3 ,0,0
       0    .055       0 1353.45    .035       0 1618.66    .055       0
Levee=-1,0,435.14,-1,2882,435.14,,
#XS Ineff= 2 , 0
       0 1353.45     409 1618.66       0  408.79
Permanent Ineff=
       F       F
Bank Sta=1353.45,1618.66
XS Rating Curve= 0 ,0
Exp/Cntr=0.3,0.1

Type RM Length L Ch R = 1 ,139379  ,190,190,190
BEGIN DESCRIPTION:
This cross section corresponds to cross section 139379 of the non-georeferenced CDC model which was the source of this model.
END DESCRIPTION:
XS GIS Cut Line= 2
2469440.118238666978651.492583962469458.975484436975746.05384105
#Sta/Elev= 30
       0  432.27   18.04  432.42   26.33     431  100.19     408  220.93     402
  252.29     406  518.13     406  713.38     404  973.48     407 1377.86     409
 1385.11     408 1399.14     403  1460.7     391 1470.85  387.11 1485.77     378
 1489.75     377 1532.58     378  1556.7     383 1565.88     389 1615.57     409
 2410.04     408 2488.71  405.04 2529.46  405.19 2647.11   402.1 2697.66     399
 2741.77     399 2765.32     401 2789.47     405 2885.85     432  2905.5   432.7
#Mann= 3 ,0,0
       0    .055       0 1377.86    .035       0 1615.57    .055       0
Levee=-1,0,435.09,-1,2892,435.09,,
#XS Ineff= 2 , 0
       0 1377.86     409 1615.57       0     409
Permanent Ineff=
       F       F
Bank Sta=1377.86,1615.57
XS Rating Curve= 0 ,0
Exp/Cntr=0.3,0.1

Type RM Length L Ch R = 1 ,139189  ,190,190,190
BEGIN DESCRIPTION:
This cross section corresponds to cross section 139189 of the non-georeferenced CDC model which was the source of this model.
END DESCRIPTION:
XS GIS Cut Line= 2
2469628.852769356978648.788849222469650.451479446975755.42947847
#Sta/Elev= 30
       0  432.74   22.36     430   88.89  409.19   117.7     406     217     402
  245.86  404.87  283.46  405.12  489.62     405  576.65     403  798.64     406
 1283.08     409 1375.68     408 1438.55     393  1467.4     381 1530.04     381
 1545.85     384 1551.25   385.9 1554.25     389  1569.5     394 1596.78     410
 1775.88     408 2503.76     407 2634.59     404 2670.04  399.55 2708.68     398
 2752.49  400.97 2784.61     406 2866.88     430 2881.55     433 2893.44     433
#Mann= 3 ,0,0
       0    .055       0 1375.68    .035       0 1596.78    .055       0
Levee=-1,0,435.04,-1,2882,435.04,,
#XS Ineff= 2 , 0
       0 1375.68     408 1596.78       0     410
Permanent Ineff=
       F       F
Bank Sta=1375.68,1596.78
XS Rating Curve= 0 ,0
Exp/Cntr=0.3,0.1

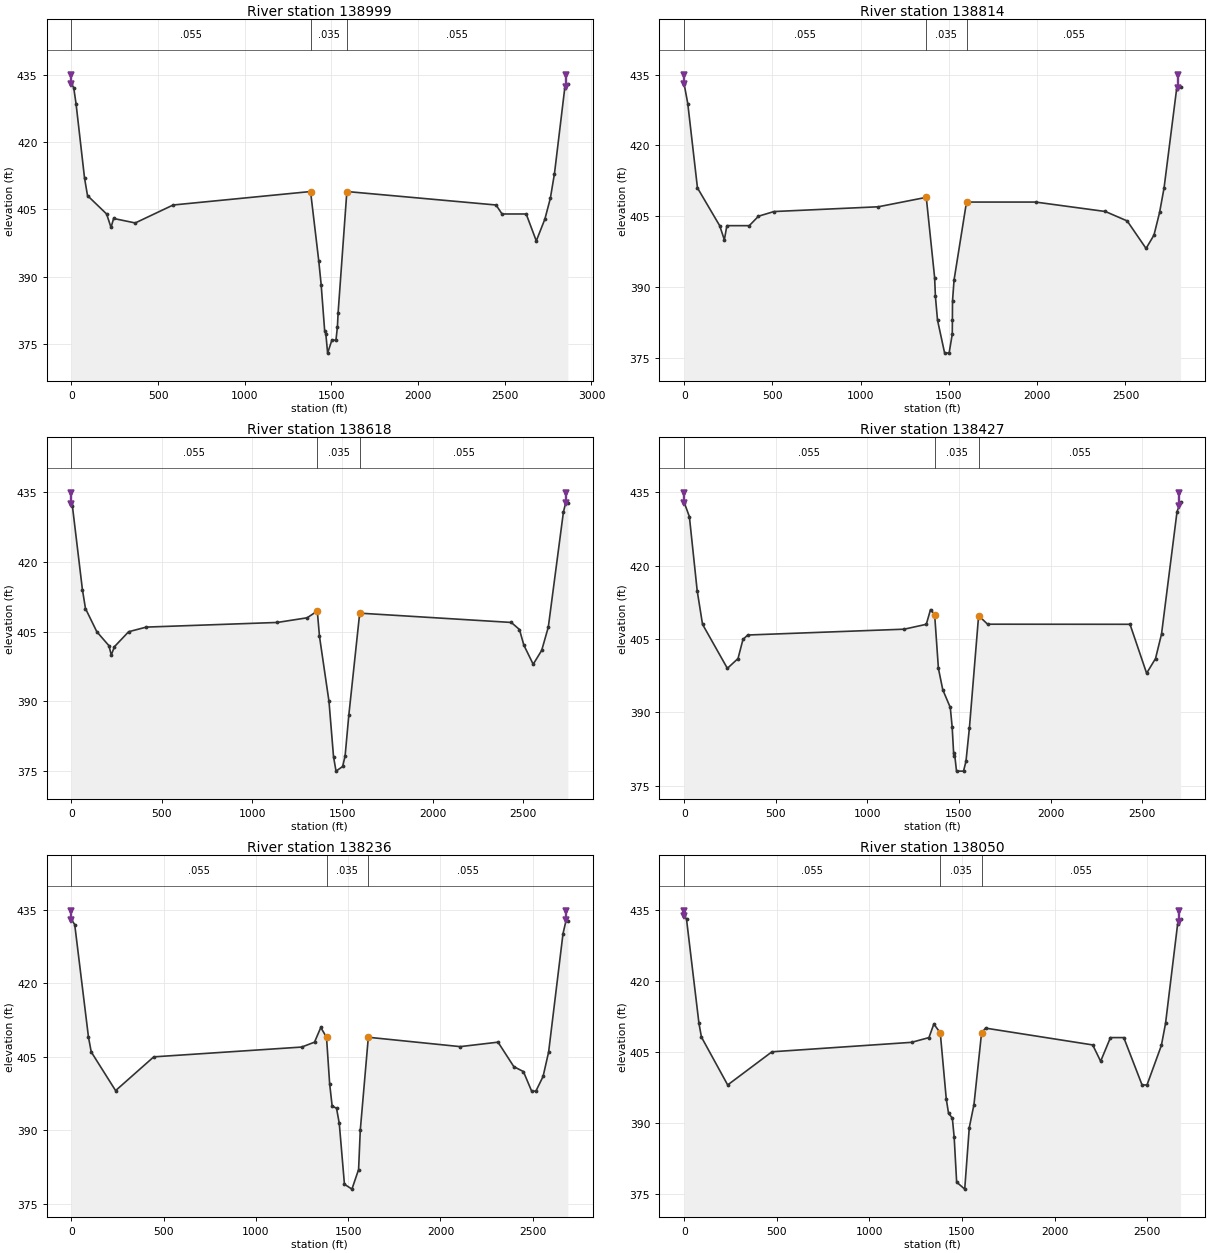
Type RM Length L Ch R = 1 ,138999  ,185,185,185
BEGIN DESCRIPTION:
This cross section corresponds to cross section 138999 of the non-georeferenced CDC model which was the source of this model.
END DESCRIPTION:
XS GIS Cut Line= 2
2469817.596158276978646.412869722469840.628920586975782.60527714
#Sta/Elev= 30
       0     433   12.94  432.11   26.33  428.57   75.31     412   92.51  408.09
  202.59     404  228.17     401  243.06     403  367.76     402  586.47     406
 1379.33     409 1426.61  393.56 1440.45  388.27 1460.68     378 1467.61  377.27
 1477.74     373 1502.51  375.93 1525.82  375.87 1534.33  378.86 1538.31     382
 1588.79     409 2449.54     406 2484.11     404 2623.44     404 2681.75     398
  2731.4  402.88 2762.83   407.5 2786.58     413 2845.81     432  2863.9     433
#Mann= 3 ,0,0
       0    .055       0 1379.33    .035       0 1588.79    .055       0
Levee=-1,0,435,-1,2852,435,,
#XS Ineff= 2 , 0
       0 1379.33     409 1588.79       0     409
Permanent Ineff=
       F       F
Bank Sta=1379.33,1588.79
XS Rating Curve= 0 ,0
Exp/Cntr=0.3,0.1

Type RM Length L Ch R = 1 ,138814  ,195,196,195
BEGIN DESCRIPTION:
This cross section corresponds to cross section 138809 of the non-georeferenced CDC model which was the source of this model.
END DESCRIPTION:
XS GIS Cut Line= 2
2470000.999662856978630.03429355  2470026.0002696975817.96577072
#Sta/Elev= 30
       0  432.93   20.22  428.85   75.05     411  200.89     403  227.44     400
   241.7     403  368.58     403  420.65     405  508.34  405.99 1099.55     407
 1371.32     409 1418.68     392 1423.13     388 1435.01     383 1474.87  376.09
 1500.66     376 1518.58     380 1519.34     383 1519.94     387 1528.78  391.49
 1599.31     408 1990.25     408 2386.08     406 2509.63     404 2616.49  398.17
 2661.34     401 2693.08  405.79 2718.54     411 2789.79     432 2812.18   432.4
#Mann= 3 ,0,0
       0    .055       0 1371.32    .035       0 1599.31    .055       0
Levee=-1,0,434.95,-1,2798,434.95,,
#XS Ineff= 2 , 0
       0 1371.32     409 1599.31       0     408
Permanent Ineff=
       F       F
Bank Sta=1371.32,1599.31
XS Rating Curve= 0 ,0
Exp/Cntr=0.3,0.1

Type RM Length L Ch R = 1 ,138618  ,190,191,190
BEGIN DESCRIPTION:
This cross section corresponds to cross section 138618 of the non-georeferenced CDC model which was the source of this model.
END DESCRIPTION:
XS GIS Cut Line= 2
2470194.587858356978634.829559552470222.725597356975887.25368989
#Sta/Elev= 30
       0  432.54    5.28     432   60.45  414.09   77.44     410  140.32     405
  207.28     402  220.27     400  238.09   401.8  316.23     405  413.99     406
 1139.13     407 1304.31     408 1360.69  409.45 1372.79     404 1425.39     390
 1450.55   378.1  1464.3     375 1501.06     376 1514.76  378.32 1535.07     387
 1595.34     409 2434.57     407 2479.72  405.48 2504.03  402.12  2555.8     398
 2602.88     401 2639.44     406 2723.19   430.8 2735.99  432.78 2747.72  432.74
#Mann= 3 ,0,0
       0    .055       0 1360.69    .035       0 1595.34    .055       0
Levee=-1,0,434.9,-1,2736,434.9,,
#XS Ineff= 2 , 0
       0 1360.69  409.45 1595.34       0     409
Permanent Ineff=
       F       F
Bank Sta=1360.69,1595.34
XS Rating Curve= 0 ,0
Exp/Cntr=0.3,0.1

Type RM Length L Ch R = 1 ,138427  ,190,191,190
BEGIN DESCRIPTION:
This cross section corresponds to cross section 138427 of the non-georeferenced CDC model which was the source of this model.
END DESCRIPTION:
XS GIS Cut Line= 2
2470382.504477266978656.669738962470415.412547926975946.75947638
#Sta/Elev= 30
       0  432.88   28.18     430   70.93  414.83   99.97     408  235.62     399
  293.76     401  320.72   404.9  346.82  405.81 1201.22     407 1321.78     408
 1344.67     411 1367.25     410 1387.86     399 1411.53  394.64 1452.71     391
 1462.96     387 1471.83   381.1 1475.47  381.76 1486.68     378 1524.93     378
 1538.32     380 1557.21  386.87 1607.36  409.76 1656.34  408.02 2433.89     408
 2524.59     398 2573.18     401 2605.98     406 2690.62     431 2710.11     433
#Mann= 3 ,0,0
       0    .055       0 1367.25    .035       0 1607.36    .055       0
Levee=-1,0,434.86,-1,2703,434.86,,
#XS Ineff= 2 , 0
       0 1367.25     410 1607.36       0  409.76
Permanent Ineff=
       F       F
Bank Sta=1367.25,1607.36
XS Rating Curve= 0 ,0
Exp/Cntr=0.3,0.1

Type RM Length L Ch R = 1 ,138236  ,186,186,186
BEGIN DESCRIPTION:
This cross section corresponds to cross section 138236 of the non-georeferenced CDC model which was the source of this model.
END DESCRIPTION:
XS GIS Cut Line= 2
2470570.618602346978660.729770212470608.248776446975970.60326071
#Sta/Elev= 30
       0     433   17.55     432   92.16     409  107.15     406  239.11  398.11
  445.85     405  1247.7     407 1317.19     408 1351.19     411 1382.27     409
 1399.17  399.53 1412.66     395 1436.55  394.49 1451.34  391.44 1479.41     379
 1520.01     378 1556.08     382 1565.22     390 1608.86     409 2106.59  407.09
 2311.84     408 2397.51     403 2449.39     402 2494.13     398 2516.98     398
 2556.02     401  2586.1     406 2664.14  430.17  2681.4  432.98 2690.39  432.64
#Mann= 3 ,0,0
       0    .055       0 1382.27    .035       0 1608.86    .055       0
Levee=-1,0,434.81,-1,2681,434.81,,
#XS Ineff= 2 , 0
       0 1382.27     409 1608.86       0     409
Permanent Ineff=
       F       F
Bank Sta=1382.27,1608.86
XS Rating Curve= 0 ,0
Exp/Cntr=0.3,0.1

Type RM Length L Ch R = 1 ,138050  ,227,229,227
BEGIN DESCRIPTION:
This cross section corresponds to cross section 138046 of the non-georeferenced CDC model which was the source of this model.
END DESCRIPTION:
XS GIS Cut Line= 2
2470753.838380256978653.624469462470795.851747666975973.37359639
#Sta/Elev= 30
       0  433.71   12.45  433.01   79.64     411   93.03  408.11  234.73     398
  473.75     405 1227.93     407 1321.64     408 1348.09  410.87 1382.75     409
 1415.25     395 1427.52     392 1447.95     391 1457.77     387 1471.24  377.48
  1514.8     376 1539.47     389 1564.74  393.86 1605.78     409 1627.47     410
  2205.9  406.45 2248.79     403  2301.8     408 2373.72     408 2472.53     398
  2499.2     398 2576.86  406.35 2599.26     411  2664.6     432 2680.58     433
#Mann= 3 ,0,0
       0    .055       0 1382.75    .035       0 1605.78    .055       0
Levee=-1,0,434.77,-1,2671,434.77,,
#XS Ineff= 2 , 0
       0 1382.75     409 1605.78       0     409
Permanent Ineff=
       F       F
Bank Sta=1382.75,1605.78
XS Rating Curve= 0 ,0
Exp/Cntr=0.3,0.1