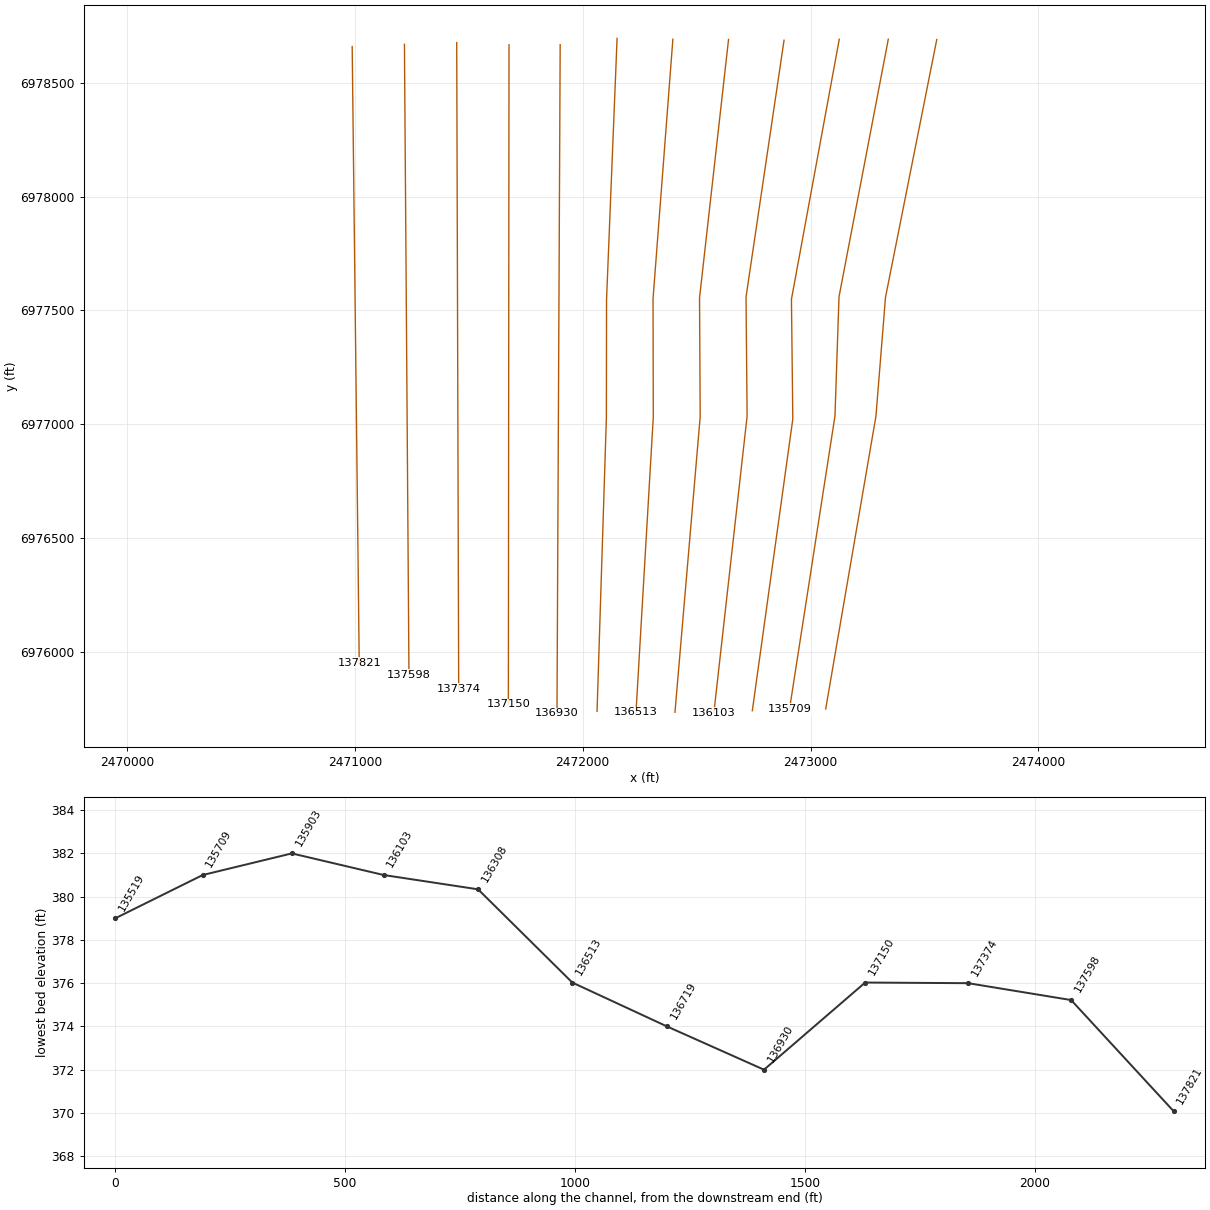
HEC-RAS study CDC_Consolidated_Model.prj: Upper Trinity CDC Consolidated Model

--- CDC_Consolidated_Model.g02 (geometry) --- (continued)

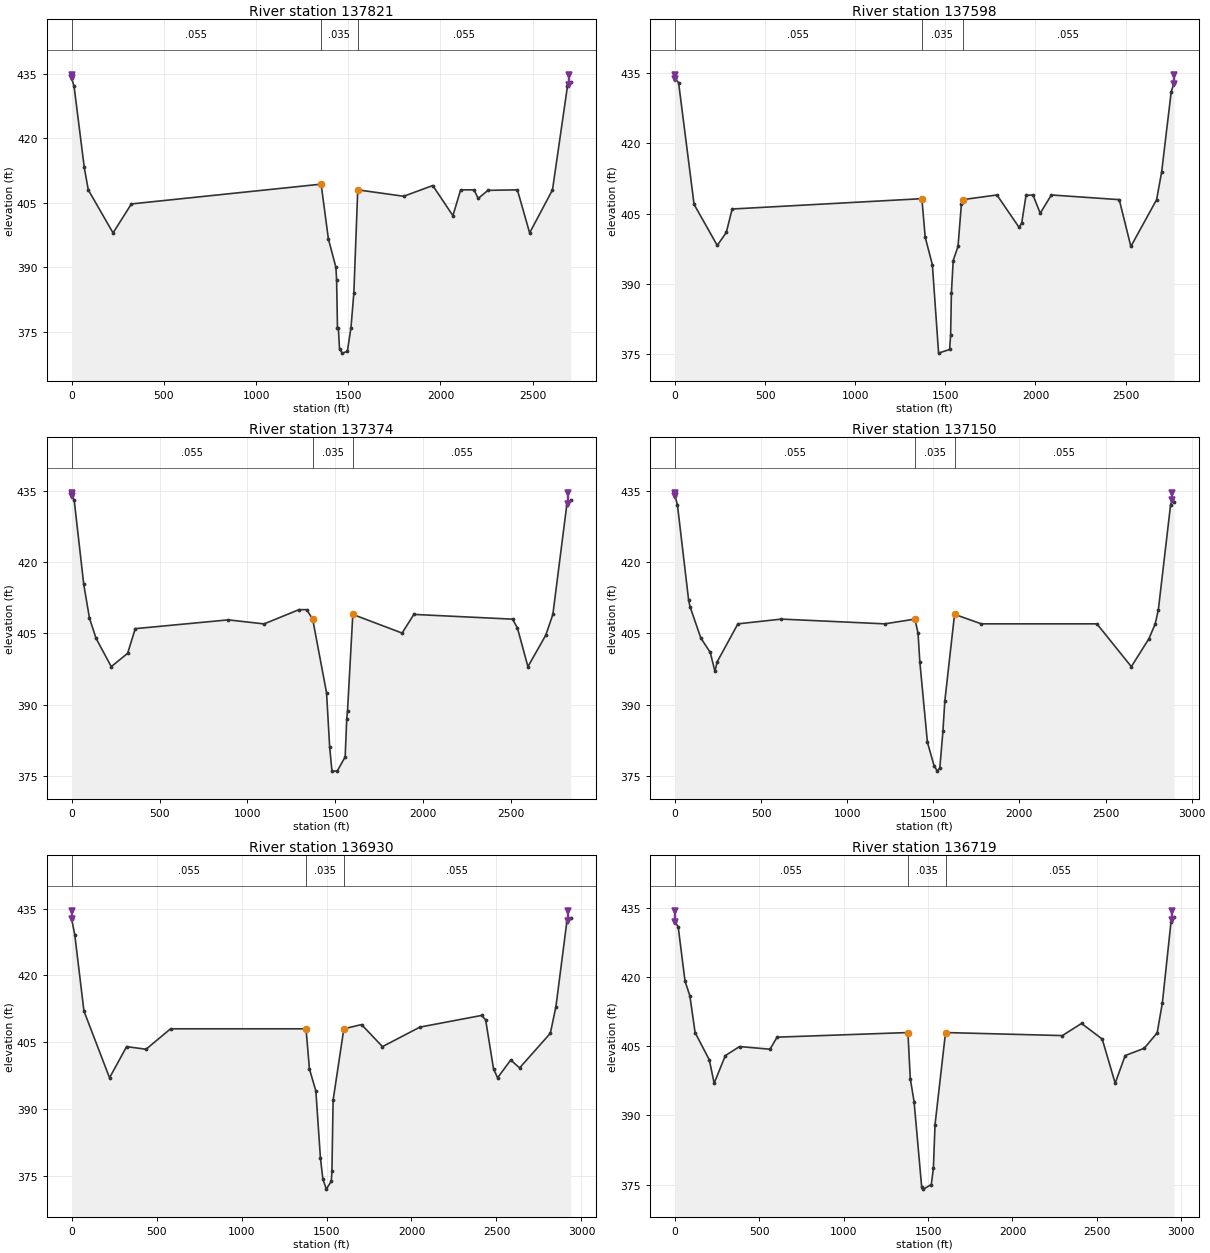
Type RM Length L Ch R = 1 ,137821  ,221,223,221
BEGIN DESCRIPTION:
This cross section corresponds to cross section 137822 of the non-georeferenced CDC model which was the source of this model.
END DESCRIPTION:
XS GIS Cut Line= 2
2470988.226362916978659.057529462471019.093755256975952.44352013
#Sta/Elev= 30
       0     434    13.4     432   68.62  413.19   90.24     408  224.62     398
  324.15  404.73  1352.9  409.32 1392.25  396.63 1433.14     390 1436.95     387
 1441.55     376 1446.38  375.89  1452.8     371 1468.35  370.08 1495.24  370.49
 1514.76     376 1530.36     384  1551.5     408 1800.39  406.51 1958.44     409
 2067.42     402 2109.63     408  2181.9     408 2204.81     406 2257.34  407.88
 2417.25     408 2483.58     398 2607.57     408 2688.55     432 2706.79     433
#Mann= 3 ,0,0
       0    .055       0  1352.9    .035       0  1551.5    .055       0
Levee=-1,0,434.71,-1,2695,434.71,,
#XS Ineff= 2 , 0
       0  1352.9  409.32  1551.5       0     408
Permanent Ineff=
       F       F
Bank Sta=1352.9,1551.5
XS Rating Curve= 0 ,0
Exp/Cntr=0.3,0.1

Type RM Length L Ch R = 1 ,137598  ,222,224,222
BEGIN DESCRIPTION:
This cross section corresponds to cross section 137598 of the non-georeferenced CDC model which was the source of this model.
END DESCRIPTION:
XS GIS Cut Line= 2
2471217.55234784 6978669.0627588 2471237.3935155 6975900.4639653
#Sta/Elev= 30
       0  433.86   20.47     433  106.32     407  234.96  398.22  285.12     401
  317.65     406 1369.98  408.21 1388.26     400 1428.08  394.11 1462.59  375.22
 1523.66     376 1529.34     379 1533.61     388 1543.63     395 1570.28     398
    1589     407 1595.75     408 1786.19     409 1908.65   402.1 1923.66     403
 1947.54  408.91 1985.91     409 2026.33  405.11 2088.26     409 2464.63     408
 2529.09     398 2671.81     408 2699.61  413.86 2752.63  430.96 2768.67     433
#Mann= 3 ,0,0
       0    .055       0 1369.98    .035       0 1595.75    .055       0
Levee=-1,0,434.66,-1,2766,434.66,,
#XS Ineff= 2 , 0
       0 1369.98  408.21 1595.75       0     408
Permanent Ineff=
       F       F
Bank Sta=1369.98,1595.75
XS Rating Curve= 0 ,0
Exp/Cntr=0.3,0.1

Type RM Length L Ch R = 1 ,137374  ,222,224,222
BEGIN DESCRIPTION:
This cross section corresponds to cross section 137374 of the non-georeferenced CDC model which was the source of this model.
END DESCRIPTION:
XS GIS Cut Line= 2
2471446.975773516978676.649029722471455.633892696975836.90208454
#Sta/Elev= 30
       0     434    14.8     433      69  415.32  101.36  408.25  138.49     404
   225.5     398  318.82  400.82  361.98     406  891.19  407.85 1094.75     407
 1293.39     410 1337.01     410 1371.34     408  1450.3  392.49 1468.09     381
 1481.09     376 1510.85     376 1556.17     379 1565.11     387 1569.48  388.62
 1599.63     409 1880.04  405.07 1947.01     409 2508.54     408  2535.9  406.18
 2595.91     398 2697.44  404.63 2737.74     409  2816.8     432 2839.76     433
#Mann= 3 ,0,0
       0    .055       0 1371.34    .035       0 1599.63    .055       0
Levee=-1,0,434.6,-1,2823,434.6,,
#XS Ineff= 2 , 0
       0 1371.34     408 1599.63       0     409
Permanent Ineff=
       F       F
Bank Sta=1371.34,1599.63
XS Rating Curve= 0 ,0
Exp/Cntr=0.3,0.1

Type RM Length L Ch R = 1 ,137150  ,219,220,219
BEGIN DESCRIPTION:
This cross section corresponds to cross section 137150 of the non-georeferenced CDC model which was the source of this model.
END DESCRIPTION:
XS GIS Cut Line= 2
2471676.451364436978666.767487792471673.68923083 6975768.8087168
#Sta/Elev= 30
       0  433.98   14.81     432   79.67     412   87.96   410.6   150.8     404
  205.21     401  232.53     397  245.12     399  365.82     407  618.14     408
 1218.73     407 1393.77     408 1411.71     405 1422.01     399 1466.02  382.11
 1504.71  377.17 1523.48  376.03  1538.1  376.71 1556.14  384.44 1567.12  390.77
 1623.55     409 1779.34     407    2450     407 2649.86     398 2752.09  403.88
 2788.71     407 2806.84     410 2877.59  431.97 2886.31  432.99 2897.96   432.6
#Mann= 3 ,0,0
       0    .055       0 1393.77    .035       0 1623.55    .055       0
Levee=-1,0,434.55,-1,2886,434.55,,
#XS Ineff= 2 , 0
       0 1393.77     408 1623.55       0     409
Permanent Ineff=
       F       F
Bank Sta=1393.77,1623.55
XS Rating Curve= 0 ,0
Exp/Cntr=0.3,0.1

Type RM Length L Ch R = 1 ,136930  ,211,211,211
BEGIN DESCRIPTION:
This cross section corresponds to cross section 136927 of the non-georeferenced CDC model which was the source of this model.
END DESCRIPTION:
XS GIS Cut Line= 2
 2471901.0224376 6978667.20843182471887.003764846975729.79206255
#Sta/Elev= 30
       0  432.68   18.42  429.15   72.47     412  223.12     397  323.45     404
  437.78  403.41  582.32     408 1379.45     408 1399.36     399 1437.26  394.02
 1464.11     379 1478.34   374.3 1499.04     372 1527.94  373.78 1531.78     376
  1538.7  391.95 1601.93     408 1706.19  408.95 1829.13     404 2049.58  408.38
 2412.14     411 2436.43     410  2482.8     399  2506.6     397 2584.02     401
 2636.19  399.22 2817.13     407 2850.03     413 2914.05     432 2937.45  432.95
#Mann= 3 ,0,0
       0    .055       0 1379.45    .035       0 1601.93    .055       0
Levee=-1,0,434.49,-1,2921,434.49,,
#XS Ineff= 2 , 0
       0 1379.45     408 1601.93       0     408
Permanent Ineff=
       F       F
Bank Sta=1379.45,1601.93
XS Rating Curve= 0 ,0
Exp/Cntr=0.3,0.1

Type RM Length L Ch R = 1 ,136719  ,206,206,206
BEGIN DESCRIPTION:
This cross section corresponds to cross section 136721 of the non-georeferenced CDC model which was the source of this model.
END DESCRIPTION:
XS GIS Cut Line= 4
2472150.775875096978695.21657789 2472104.52399916977547.86519805
2472103.815010996977029.416103722472062.886615196975739.17819864
#Sta/Elev= 30
       0     432   19.42     431   60.16  419.15   88.55     416  119.73     408
  203.87  402.07  232.68     397  298.98     403  383.12  404.96  563.52  404.38
  605.43     407 1380.73     408 1394.72     398 1417.17     393 1462.47  374.37
  1472.6     374 1519.31     375  1531.7  378.58 1541.31     388 1603.56     408
 2295.83  407.34 2409.44  409.98 2531.96  406.58 2608.74     397 2667.91     403
 2781.31  404.59 2857.67  407.95 2888.47  414.47 2939.41     432 2957.62     433
#Mann= 3 ,0,0
       0    .055       0 1380.73    .035       0 1603.56    .055       0
Levee=-1,0,434.43,-1,2947,434.43,,
#XS Ineff= 2 , 0
       0 1380.73     408 1603.56       0     408
Permanent Ineff=
       F       F
Bank Sta=1380.73,1603.56
XS Rating Curve= 0 ,0
Exp/Cntr=0.3,0.1

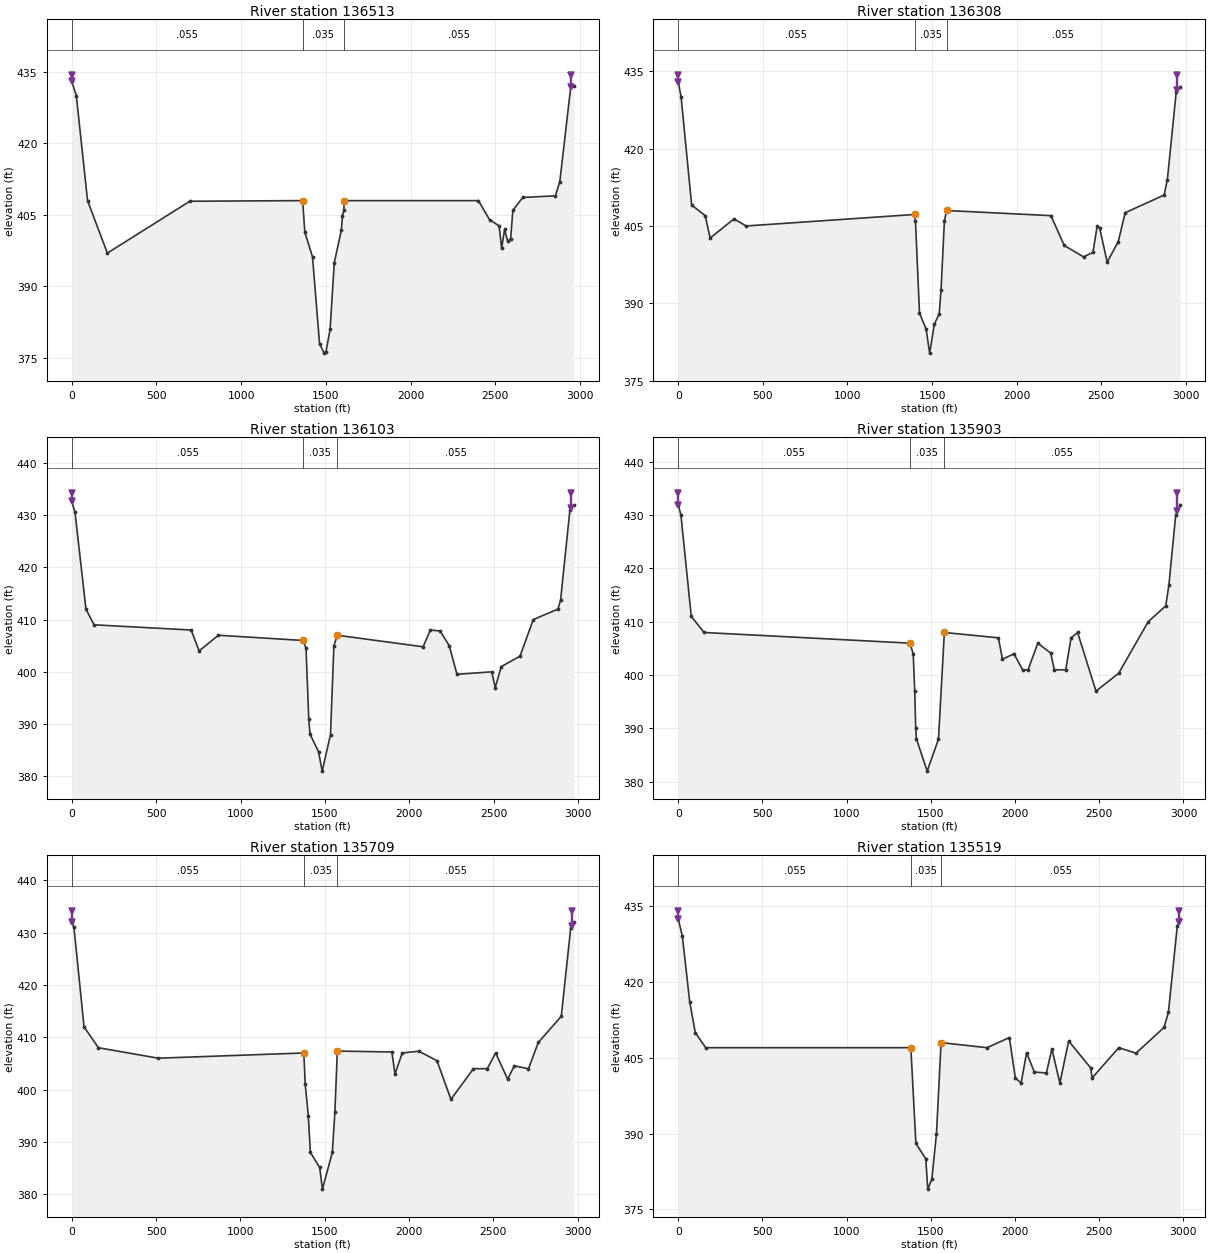
Type RM Length L Ch R = 1 ,136513  ,206,205,206
BEGIN DESCRIPTION:
This cross section corresponds to cross section 136515 of the non-georeferenced CDC model which was the source of this model.
END DESCRIPTION:
XS GIS Cut Line= 4
2472395.642839436978691.362911052472308.582974176977551.52103063
2472309.668929996977031.354091972472233.732073996975733.77400997
#Sta/Elev= 30
       0     433    26.9     430   93.14     408     210     397  696.87  407.87
 1362.41     408  1375.5  401.38 1420.83  396.21 1462.41     378 1489.68  376.03
 1500.34  376.35 1524.52     381 1549.25     395 1590.79  401.76 1597.52  404.82
  1606.1     406 1607.73     408    2400     408 2465.63     404 2522.06   402.7
 2537.07     398 2554.38     402 2572.72  399.47 2590.04     400  2603.1  405.94
 2661.43  408.66 2854.09     409  2880.3     412  2945.4     432 2963.13     432
#Mann= 3 ,0,0
       0    .055       0 1362.41    .035       0 1607.73    .055       0
Levee=-1,0,434.37,-1,2945,434.37,,
#XS Ineff= 2 , 0
       0 1362.41     408 1607.73       0     408
Permanent Ineff=
       F       F
Bank Sta=1362.41,1607.73
XS Rating Curve= 0 ,0
Exp/Cntr=0.3,0.1

Type RM Length L Ch R = 1 ,136308  ,205,205,205
BEGIN DESCRIPTION:
This cross section corresponds to cross section 136310 of the non-georeferenced CDC model which was the source of this model.
END DESCRIPTION:
XS GIS Cut Line= 4
2472639.935657926978690.246115392472512.64194927 6977555.1771913
2472515.522848996977033.29208022 2472404.82031456975734.68969055
#Sta/Elev= 30
       0     433   17.04     430   79.24  409.06  159.42     407   188.6  402.66
  329.49  406.37  401.67     405 1397.13  407.23 1402.13     406 1425.85   388.1
 1465.07     385 1486.02  380.34 1513.82  385.95 1542.52     388 1553.13  392.53
 1573.01  405.91 1585.74     408 2202.78     407  2281.3  401.22 2395.52     399
 2451.18  399.88 2476.14     405 2491.06  404.56  2535.1     398 2600.51  401.94
  2641.4  407.56 2871.66     411  2890.9     414 2943.25     431 2967.39     432
#Mann= 3 ,0,0
       0    .055       0 1397.13    .035       0 1585.74    .055       0
Levee=-1,0,434.31,-1,2950,434.31,,
#XS Ineff= 2 , 0
       0 1397.13  407.23 1585.74       0     408
Permanent Ineff=
       F       F
Bank Sta=1397.13,1585.74
XS Rating Curve= 0 ,0
Exp/Cntr=0.3,0.1

Type RM Length L Ch R = 1 ,136103  ,201,200,201
BEGIN DESCRIPTION:
This cross section corresponds to cross section 136104 of the non-georeferenced CDC model which was the source of this model.
END DESCRIPTION:
XS GIS Cut Line= 4
2472883.536220586978686.750715552472716.700924346977558.83302388
2472721.376111846977035.23105271  2472575.5581626975732.07650679
#Sta/Elev= 30
       0  432.62   19.31   430.5   84.07     412  131.74     409  707.49     408
  754.59     404  868.78     407    1372     406 1388.13  404.48  1404.3     391
 1411.72  388.07 1462.39  384.69 1483.75     381 1533.17     388 1553.17     405
 1573.52     407 2081.67  404.79 2124.91     408 2182.44  407.82 2236.83     405
 2282.44  399.53 2488.67     400 2509.24     397    2545     401 2656.28     403
 2734.74     410 2880.61     412 2896.28  413.67 2951.86     431  2975.1  431.85
#Mann= 3 ,0,0
       0    .055       0    1372    .035       0 1573.52    .055       0
Levee=-1,0,434.25,-1,2959,434.25,,
#XS Ineff= 2 , 0
       0    1372     405 1559.29       0  405.56
Permanent Ineff=
       F       F
Bank Sta=1372,1573.52
XS Rating Curve= 0 ,0
Exp/Cntr=0.3,0.1

Type RM Length L Ch R = 1 ,135903  ,194,194,194
BEGIN DESCRIPTION:
This cross section corresponds to cross section 135899 of the non-georeferenced CDC model which was the source of this model.
END DESCRIPTION:
XS GIS Cut Line= 4
2473125.89039466 6978691.28515532472916.00006643 6977549.0000383
2472922.000054426977023.000106052472744.31077725 6975741.4524723
#Sta/Elev= 30
       0     432   16.09     430   77.24  411.04  153.27     408 1375.52     406
 1395.23     404 1404.35     397 1410.03     390 1414.24  388.06 1478.17     382
  1545.3     388 1580.14     408 1901.03     407 1925.09     403 1993.57     404
 2044.92     401 2077.25     401 2134.98     406 2212.02  404.13 2233.16     401
 2300.82     401 2332.65     407 2371.31     408 2480.55     397 2615.36  400.36
 2790.27     410 2894.81     413 2913.33  416.85 2953.79     430 2981.25     432
#Mann= 3 ,0,0
       0    .055       0 1375.52    .035       0 1580.14    .055       0
Levee=-1,0,434.19,-1,2964,434.19,,
#XS Ineff= 2 , 0
       0 1375.52     406 1580.14       0     408
Permanent Ineff=
       F       F
Bank Sta=1375.52,1580.14
XS Rating Curve= 0 ,0
Exp/Cntr=0.3,0.1

Type RM Length L Ch R = 1 ,135709  ,191,190,191
BEGIN DESCRIPTION:
This cross section corresponds to cross section 135709 of the non-georeferenced CDC model which was the source of this model.
END DESCRIPTION:
XS GIS Cut Line= 4
2473341.083861926978691.360942542473124.752929756977559.91012147
 2473107.03183666977036.14509289 2472907.63656616975749.28218105
#Sta/Elev= 30
       0     432   12.93     431   72.73     412  157.97     408  513.19     406
 1376.58     407 1384.88     401 1403.04     395 1415.38     388 1470.43  385.14
 1486.93     381 1545.44     388 1560.98  395.82  1575.2  407.36 1898.79  407.19
  1917.2     403 1960.38     407 2058.82  407.33 2166.46  405.52 2249.12  398.15
 2382.91     404 2464.65     404 2514.36     407 2585.48     402 2625.12  404.55
 2708.98  403.98 2767.35     409 2903.75     414 2959.68  430.88 2978.23     432
#Mann= 3 ,0,0
       0    .055       0 1376.58    .035       0  1575.2    .055       0
Levee=-1,0,434.14,-1,2965,434.14,,
#XS Ineff= 2 , 0
       0 1376.58     407  1575.2       0  407.36
Permanent Ineff=
       F       F
Bank Sta=1376.58,1575.2
XS Rating Curve= 0 ,0
Exp/Cntr=0.3,0.1

Type RM Length L Ch R = 1 ,135519  ,190,190,190
BEGIN DESCRIPTION:
This cross section corresponds to cross section 135520 of the non-georeferenced CDC model which was the source of this model.
END DESCRIPTION:
XS GIS Cut Line= 4
2473553.79144177 6978689.87570932473328.745960096977557.33007413
2473286.83298618 6977035.12114482473066.306524346975748.93638122
#Sta/Elev= 30
       0   432.5   24.47  429.08   68.45     416  101.26     410  163.31     407
 1382.24     407 1412.28  388.06 1471.06     385 1482.83     379 1507.32     381
 1534.53     390 1561.87     408 1834.93     407 1967.77     409 2003.23     401
 2037.43     400 2070.13     406 2116.08  402.18 2187.75     402 2220.41  406.77
 2267.75     400 2320.17  408.32 2450.87     403 2459.34     401 2617.63     407
 2720.53  405.91 2886.53     411  2912.9     414 2965.15     431 2983.53   432.5
#Mann= 3 ,0,0
       0    .055       0 1382.24    .035       0 1561.87    .055       0
Levee=-1,0,434.09,-1,2977,434.09,,
#XS Ineff= 2 , 0
       0 1382.24     407 1561.87       0     408
Permanent Ineff=
       F       F
Bank Sta=1382.24,1561.87
XS Rating Curve= 0 ,0
Exp/Cntr=0.3,0.1