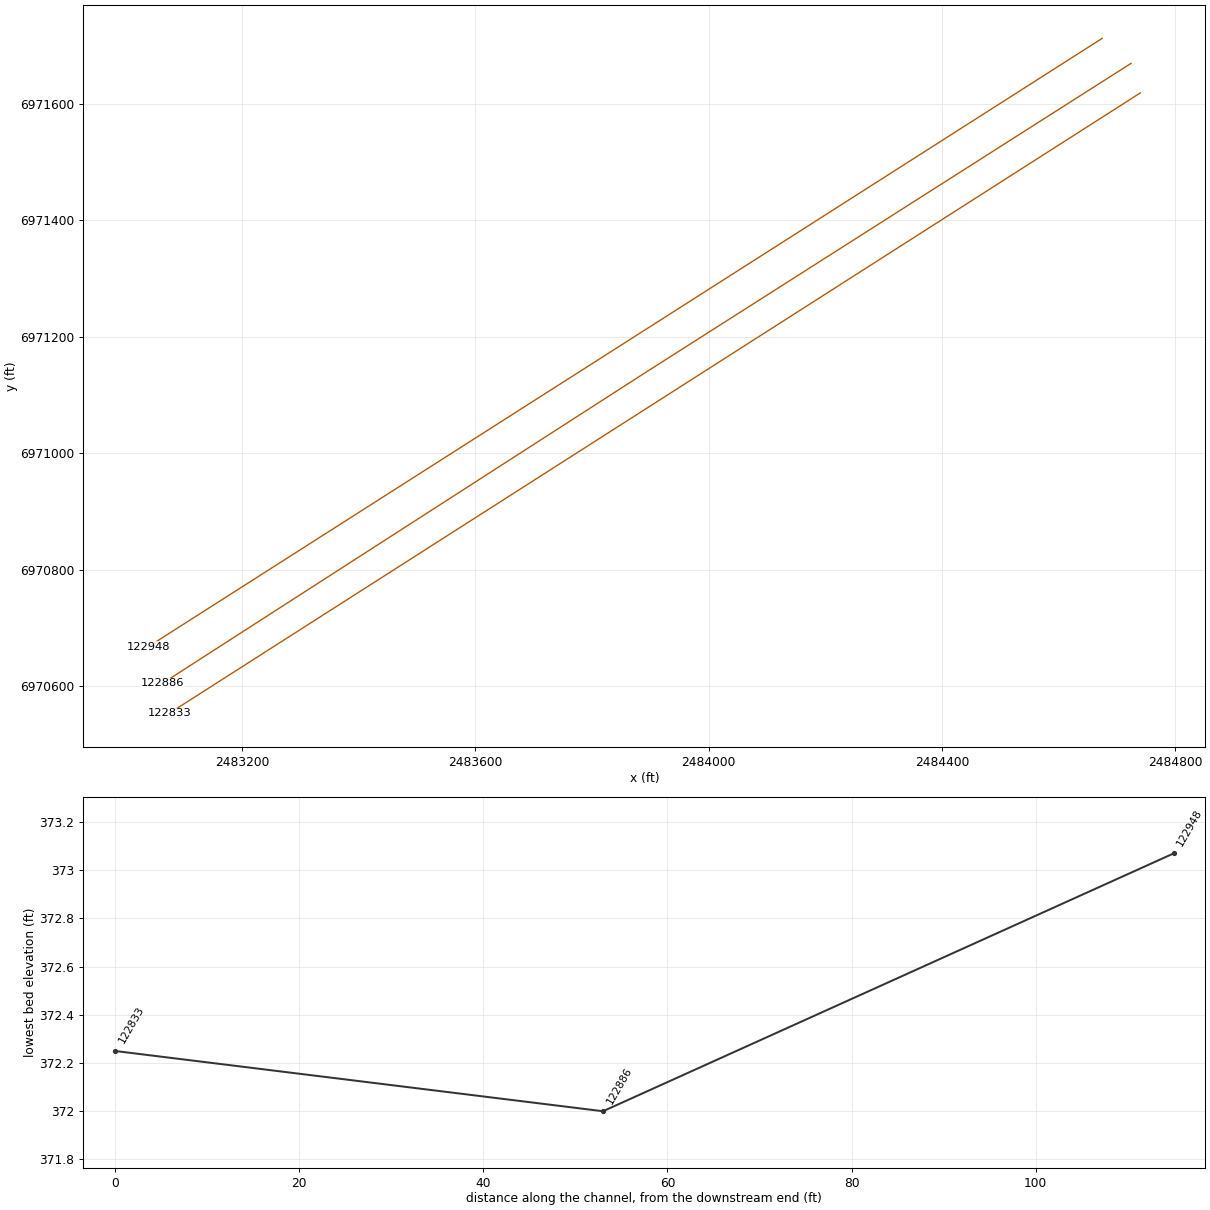
HEC-RAS study CDC_Consolidated_Model.prj: Upper Trinity CDC Consolidated Model

--- CDC_Consolidated_Model.g02 (geometry) --- (continued)

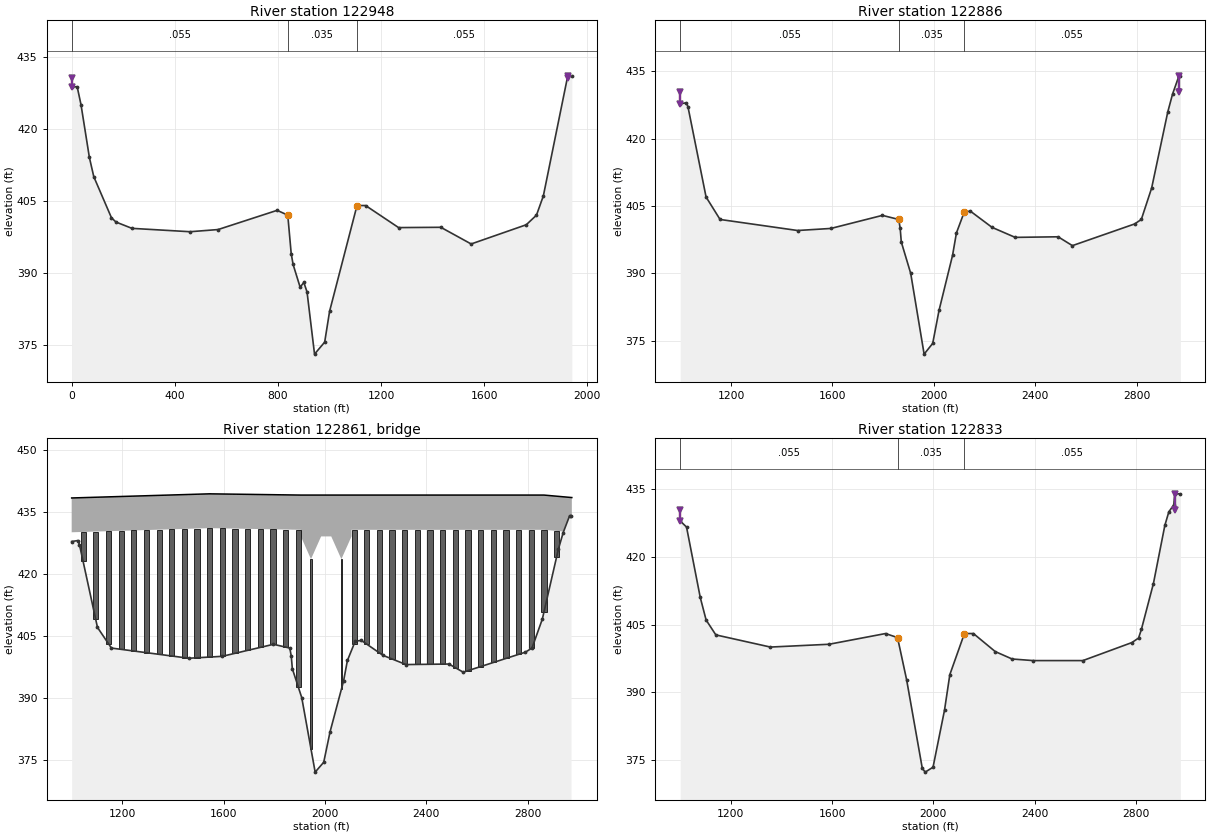
Type RM Length L Ch R = 1 ,122948  ,62,62,62
BEGIN DESCRIPTION:
This cross section corresponds to cross section 122961 of the non-georeferenced CDC model which was the source of this model.
END DESCRIPTION:
XS GIS Cut Line= 2
2484674.958175756971712.272866642483039.899109936970668.48919305
#Sta/Elev= 30
       0  428.71   21.36  428.73   36.18     425   68.72     414   85.77     410
  154.34  401.45  171.91  400.56   233.9  399.25  459.03  398.55  567.73     399
  796.81     403  838.09     402  851.41     394  858.76  391.74  886.07     387
  900.42     388  912.88     386  941.92  373.07  981.26  375.57 1000.35     382
 1106.63     404 1139.99     404  1267.9  399.41 1431.71  399.47 1549.36     396
 1763.13     400 1802.71     402 1829.32     406 1924.05     431 1939.82     431
#Mann= 3 ,0,0
       0    .055       0  838.09    .035       0 1106.63    .055       0
Levee=-1,0,430.51,-1,1924,430.51,,
#XS Ineff= 2 , 0
       0  838.09     402 1106.63       0     404
Permanent Ineff=
       F       F
Bank Sta=838.09,1106.63
XS Rating Curve= 0 ,0
Exp/Cntr=0.3,0.1

Type RM Length L Ch R = 1 ,122886  ,53,53,53
BEGIN DESCRIPTION:
This cross section corresponds to cross section 122886 of the non-georeferenced CDC model which was the source of this model.
END DESCRIPTION:
XS GIS Cut Line= 3
2484724.366213416971669.354973472483889.88559893 6971137.4951448
2483064.119205836970605.48111697
#Sta/Elev= 30
    1000  427.77 1024.62     428  1030.8     427 1101.83     407 1156.98     402
 1462.67  399.54 1593.93     400 1796.95  402.91 1861.45     402 1867.17     400
 1871.39     397 1908.54     390 1961.47     372 1995.29  374.39 2020.29  381.75
 2073.53     394 2088.85     399 2119.76  403.67 2143.92  403.85 2229.23  400.24
  2320.5  398.01 2489.74  398.14 2546.06  396.17  2791.3     401 2817.74     402
 2858.48     409  2922.1  425.96 2940.95  429.94 2966.27     434 2971.87     434
#Mann= 3 ,0,0
    1000    .055       0 1861.45    .035       0 2119.76    .055       0
Levee=-1,1000,430.48,-1,2966,430.48,,
#XS Ineff= 2 , 0
       0 1861.45     402 2119.76       0  403.67
Permanent Ineff=
       F       F
Bank Sta=1861.45,2119.76
XS Rating Curve= 0 ,0
Exp/Cntr=0.3,0.1

Type RM Length L Ch R = 3 ,122861  ,,,
BEGIN DESCRIPTION:
122860  Continental Avenue
END DESCRIPTION:
Node Name=Continental Ave.
Bridge Culvert--1,0,-1,-1, 0
Deck Dist Width WeirC Skew NumUp NumDn MinLoCord MaxHiCord MaxSubmerge Is_Ogee
1.5,48,2.6,0, 12, 12, , , 0.95, 0, ,,,
    1000    1545    1905    1905    1945    1985    2025    2065    2105    2105
    2865    2975
   438.3   439.3     439     439     439     439     439     439     439     439
     439   438.4
     430     431   430.6     429   423.5     429     429   423.5     429   430.6
   430.6     430
    1000    1545    1905    1905    1945    1985    2025    2065    2105    2105
    2865    2975
   438.3   439.3     439     439     439     439     439     439     439     439
     439   438.4
     430     431   430.6     429   423.5     429     429   423.5     429   430.6
   430.6     430
Pier Skew, UpSta & Num, DnSta & Num=  ,1045, 5 ,1045, 5 , 3 , 3 , 0 ,,
     5.5     2.5     3.5     3.5      20
     390     426     426   427.6   430.2
     5.5     2.5     3.5     3.5      20
     390     426     426   427.6   430.2
Pier Skew, UpSta & Num, DnSta & Num=  ,1095, 5 ,1095, 5 , 3 , 3 , 0 ,,
     5.5     2.5     3.5     3.5      20
   390.1   426.1   426.1   427.7   430.3
     5.5     2.5     3.5     3.5      20
   390.1   426.1   426.1   427.7   430.3
Pier Skew, UpSta & Num, DnSta & Num=  ,1145, 5 ,1145, 5 , 3 , 3 , 0 ,,
     5.5     2.5     3.5     3.5      20
   390.2   426.2   426.2   427.8   430.4
     5.5     2.5     3.5     3.5      20
   390.2   426.2   426.2   427.8   430.4
Pier Skew, UpSta & Num, DnSta & Num=  ,1195, 5 ,1195, 5 , 3 , 3 , 0 ,,
     5.5     2.5     3.5     3.5      20
   390.3   426.3   426.3   427.9   430.5
     5.5     2.5     3.5     3.5      20
   390.3   426.3   426.3   427.9   430.5
Pier Skew, UpSta & Num, DnSta & Num=  ,1245, 5 ,1245, 5 , 3 , 3 , 0 ,,
     5.5     2.5     3.5     3.5      20
   390.4   426.4   426.4     428   430.6
     5.5     2.5     3.5     3.5      20
   390.4   426.4   426.4     428   430.6
Pier Skew, UpSta & Num, DnSta & Num=  ,1295, 5 ,1295, 5 , 3 , 3 , 0 ,,
     5.5     2.5     3.5     3.5      20
   390.4   426.4   426.4     428   430.6
     5.5     2.5     3.5     3.5      20
   390.4   426.4   426.4     428   430.6
Pier Skew, UpSta & Num, DnSta & Num=  ,1345, 5 ,1345, 5 , 3 , 3 , 0 ,,
     5.5     2.5     3.5     3.5      20
   390.5   426.5   426.5   428.1   430.7
     5.5     2.5     3.5     3.5      20
   390.5   426.5   426.5   428.1   430.7
Pier Skew, UpSta & Num, DnSta & Num=  ,1395, 5 ,1395, 5 , 3 , 3 , 0 ,,
     5.5     2.5     3.5     3.5      20
   390.6   426.6   426.6   428.2   430.8
     5.5     2.5     3.5     3.5      20
   390.6   426.6   426.6   428.2   430.8
Pier Skew, UpSta & Num, DnSta & Num=  ,1445, 5 ,1445, 5 , 3 , 3 , 0 ,,
     5.5     2.5     3.5     3.5      20
   390.7   426.7   426.7   428.3   430.9
     5.5     2.5     3.5     3.5      20
   390.7   426.7   426.7   428.3   430.9
Pier Skew, UpSta & Num, DnSta & Num=  ,1495, 5 ,1495, 5 , 3 , 3 , 0 ,,
     5.5     2.5     3.5     3.5      20
   390.8   426.8   426.8   428.4     431
     5.5     2.5     3.5     3.5      20
   390.8   426.8   426.8   428.4     431
Pier Skew, UpSta & Num, DnSta & Num=  ,1545, 5 ,1545, 5 , 3 , 3 , 0 ,,
     5.5     2.5     3.5     3.5      20
   390.9   426.9   426.9   428.5   431.1
     5.5     2.5     3.5     3.5      20
   390.9   426.9   426.9   428.5   431.1
Pier Skew, UpSta & Num, DnSta & Num=  ,1595, 5 ,1595, 5 , 3 , 3 , 0 ,,
     5.5     2.5     3.5     3.5      20
   390.8   426.8   426.8   428.4     431
     5.5     2.5     3.5     3.5      20
   390.8   426.8   426.8   428.4     431
Pier Skew, UpSta & Num, DnSta & Num=  ,1645, 5 ,1645, 5 , 3 , 3 , 0 ,,
     5.5     2.5     3.5     3.5      20
   390.8   426.8   426.8   428.4     431
     5.5     2.5     3.5     3.5      20
   390.8   426.8   426.8   428.4     431
Pier Skew, UpSta & Num, DnSta & Num=  ,1695, 5 ,1695, 5 , 3 , 3 , 0 ,,
     5.5     2.5     3.5     3.5      20
   390.7   426.7   426.7   428.3   430.9
     5.5     2.5     3.5     3.5      20
   390.7   426.7   426.7   428.3   430.9
Pier Skew, UpSta & Num, DnSta & Num=  ,1745, 5 ,1745, 5 , 3 , 3 , 0 ,,
     5.5     2.5     3.5     3.5      20
   390.7   426.7   426.7   428.3   430.9
     5.5     2.5     3.5     3.5      20
   390.7   426.7   426.7   428.3   430.9
Pier Skew, UpSta & Num, DnSta & Num=  ,1795, 5 ,1795, 5 , 3 , 3 , 0 ,,
     5.5     2.5     3.5     3.5      20
   390.6   426.6   426.6   428.2   430.8
     5.5     2.5     3.5     3.5      20
   390.6   426.6   426.6   428.2   430.8
Pier Skew, UpSta & Num, DnSta & Num=  ,1845, 5 ,1845, 5 , 3 , 3 , 0 ,,
     5.5     2.5     3.5     3.5      20
   390.6   426.6   426.6   428.2   430.8
     5.5     2.5     3.5     3.5      20
   390.6   426.6   426.6   428.2   430.8
Pier Skew, UpSta & Num, DnSta & Num=  ,1895, 5 ,1895, 5 , 3 , 3 , 0 ,,
     5.5     2.5     3.5     3.5      20
   390.5   426.5   426.5   428.1   430.7
     5.5     2.5     3.5     3.5      20
   390.5   426.5   426.5   428.1   430.7
Pier Skew, UpSta & Num, DnSta & Num=  ,1945, 6 ,1945, 6 , 5 , 5 , 0 ,,
       6       6    5.25     2.5     3.5     3.5
     370   387.5   387.5   420.5   420.5     425
       6       6    5.25     2.5     3.5     3.5
     370   387.5   387.5   420.5   420.5     425
Pier Skew, UpSta & Num, DnSta & Num=  ,2065, 6 ,2065, 6 , 5 , 5 , 0 ,,
       6       6    5.25     2.5     3.5     3.5
     370   387.5   387.5   420.5   420.5     425
       6       6    5.25     2.5     3.5     3.5
     370   387.5   387.5   420.5   420.5     425
Pier Skew, UpSta & Num, DnSta & Num=  ,2115, 5 ,2115, 5 , 3 , 3 , 0 ,,
     5.5     2.5     3.5     3.5      20
   390.5   426.5   426.5   428.1   430.7
     5.5     2.5     3.5     3.5      20
   390.5   426.5   426.5   428.1   430.7
Pier Skew, UpSta & Num, DnSta & Num=  ,2165, 5 ,2165, 5 , 3 , 3 , 0 ,,
     5.5     2.5     3.5     3.5      20
   390.5   426.5   426.5   428.1   430.7
     5.5     2.5     3.5     3.5      20
   390.5   426.5   426.5   428.1   430.7
Pier Skew, UpSta & Num, DnSta & Num=  ,2215, 5 ,2215, 5 , 3 , 3 , 0 ,,
     5.5     2.5     3.5     3.5      20
   390.5   426.5   426.5   428.1   430.7
     5.5     2.5     3.5     3.5      20
   390.5   426.5   426.5   428.1   430.7
Pier Skew, UpSta & Num, DnSta & Num=  ,2265, 5 ,2265, 5 , 3 , 3 , 0 ,,
     5.5     2.5     3.5     3.5      20
   390.5   426.5   426.5   428.1   430.7
     5.5     2.5     3.5     3.5      20
   390.5   426.5   426.5   428.1   430.7
Pier Skew, UpSta & Num, DnSta & Num=  ,2315, 5 ,2315, 5 , 3 , 3 , 0 ,,
     5.5     2.5     3.5     3.5      20
   390.5   426.5   426.5   428.1   430.7
     5.5     2.5     3.5     3.5      20
   390.5   426.5   426.5   428.1   430.7
Pier Skew, UpSta & Num, DnSta & Num=  ,2365, 5 ,2365, 5 , 3 , 3 , 0 ,,
     5.5     2.5     3.5     3.5      20
   390.5   426.5   426.5   428.1   430.7
     5.5     2.5     3.5     3.5      20
   390.5   426.5   426.5   428.1   430.7
Pier Skew, UpSta & Num, DnSta & Num=  ,2415, 5 ,2415, 5 , 3 , 3 , 0 ,,
     5.5     2.5     3.5     3.5      20
   390.5   426.5   426.5   428.1   430.7
     5.5     2.5     3.5     3.5      20
   390.5   426.5   426.5   428.1   430.7
Pier Skew, UpSta & Num, DnSta & Num=  ,2465, 5 ,2465, 5 , 3 , 3 , 0 ,,
     5.5     2.5     3.5     3.5      20
   390.5   426.5   426.5   428.1   430.7
     5.5     2.5     3.5     3.5      20
   390.5   426.5   426.5   428.1   430.7
Pier Skew, UpSta & Num, DnSta & Num=  ,2515, 5 ,2515, 5 , 3 , 3 , 0 ,,
     5.5     2.5     3.5     3.5      20
   390.5   426.5   426.5   428.1   430.7
     5.5     2.5     3.5     3.5      20
   390.5   426.5   426.5   428.1   430.7
Pier Skew, UpSta & Num, DnSta & Num=  ,2565, 5 ,2565, 5 , 3 , 3 , 0 ,,
     5.5     2.5     3.5     3.5      20
   390.5   426.5   426.5   428.1   430.7
     5.5     2.5     3.5     3.5      20
   390.5   426.5   426.5   428.1   430.7
Pier Skew, UpSta & Num, DnSta & Num=  ,2615, 5 ,2615, 5 , 3 , 3 , 0 ,,
     5.5     2.5     3.5     3.5      20
   390.5   426.5   426.5   428.1   430.7
     5.5     2.5     3.5     3.5      20
   390.5   426.5   426.5   428.1   430.7
Pier Skew, UpSta & Num, DnSta & Num=  ,2665, 5 ,2665, 5 , 3 , 3 , 0 ,,
     5.5     2.5     3.5     3.5      20
   390.5   426.5   426.5   428.1   430.7
     5.5     2.5     3.5     3.5      20
   390.5   426.5   426.5   428.1   430.7
Pier Skew, UpSta & Num, DnSta & Num=  ,2715, 5 ,2715, 5 , 3 , 3 , 0 ,,
     5.5     2.5     3.5     3.5      20
   390.5   426.5   426.5   428.1   430.7
     5.5     2.5     3.5     3.5      20
   390.5   426.5   426.5   428.1   430.7
Pier Skew, UpSta & Num, DnSta & Num=  ,2765, 5 ,2765, 5 , 3 , 3 , 0 ,,
     5.5     2.5     3.5     3.5      20
   390.5   426.5   426.5   428.1   430.7
     5.5     2.5     3.5     3.5      20
   390.5   426.5   426.5   428.1   430.7
Pier Skew, UpSta & Num, DnSta & Num=  ,2815, 5 ,2815, 5 , 3 , 3 , 0 ,,
     5.5     2.5     3.5     3.5      20
   390.5   426.5   426.5   428.1   430.7
     5.5     2.5     3.5     3.5      20
   390.5   426.5   426.5   428.1   430.7
Pier Skew, UpSta & Num, DnSta & Num=  ,2865, 5 ,2865, 5 , 3 , 3 , 0 ,,
     5.5     2.5     3.5     3.5      20
   390.5   426.5   426.5   428.1   430.7
     5.5     2.5     3.5     3.5      20
   390.5   426.5   426.5   428.1   430.7
Pier Skew, UpSta & Num, DnSta & Num=  ,2915, 5 ,2915, 5 , 3 , 3 , 0 ,,
     5.5     2.5     3.5     3.5      20
   390.3   426.3   426.3   427.9   430.5
     5.5     2.5     3.5     3.5      20
   390.3   426.3   426.3   427.9   430.5
BR Coef= 1 , 1 , 1 ,0.9, 0 ,,,0.8,-1,0.33,1,
WSPro=,,,, 1 ,,,, 0 ,,,, 0 ,,,,-1 ,-1 ,-1 , 0 , 0 , 0 , 0 , 0
BC Design=,, 0 ,, 0 ,,,,,,
BC HTab HWMax=432
BC Use User HTab Curves=0
BC User HTab FreeFlow(D)= 0

Type RM Length L Ch R = 1 ,122833  ,86,86,86
BEGIN DESCRIPTION:
This cross section corresponds to cross section 122834 of the non-georeferenced CDC model which was the source of this model.
END DESCRIPTION:
XS GIS Cut Line= 2
2484740.22707409 6971618.61426132483075.269446026970553.79716522
#Sta/Elev= 30
    1000  427.97 1024.84  426.63  1079.1     411 1102.22     406 1140.66   402.7
 1356.11     400 1587.92  400.62 1811.19     403 1858.61   402.1 1894.47  392.75
 1956.41   373.1 1967.82  372.25 1998.86  373.34 2044.21     386 2065.27  393.89
 2122.85     403 2158.44     403 2244.62     399 2311.43  397.35 2394.45     397
 2591.01     397 2784.71     401 2811.03     402 2822.12   403.9 2869.72   414.1
 2914.87     427 2930.58     430 2949.98  431.54 2954.24     434 2976.34     434
#Mann= 3 ,0,0
    1000    .055       0 1858.61    .035       0 2122.85    .055       0
Levee=-1,1000,430.46,-1,2954,430.46,,
#XS Ineff= 2 , 0
       0 1858.61   402.1 2122.85       0     403
Permanent Ineff=
       F       F
Bank Sta=1858.61,2122.85
XS Rating Curve= 0 ,0
Exp/Cntr=0.3,0.1