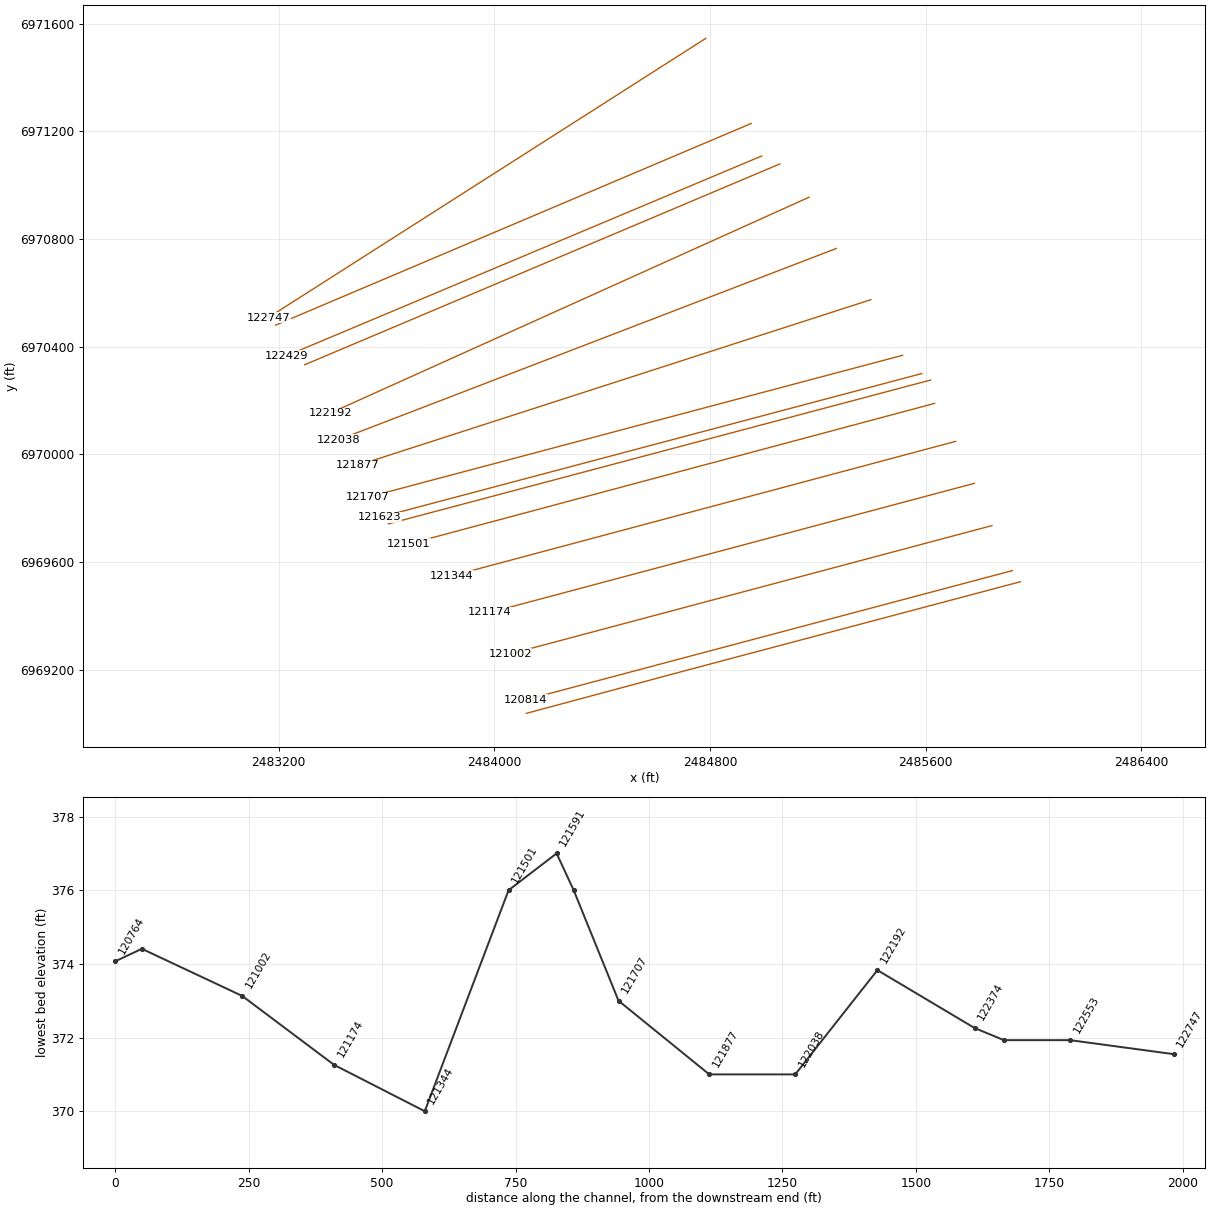
HEC-RAS study CDC_Consolidated_Model.prj: Upper Trinity CDC Consolidated Model

--- CDC_Consolidated_Model.g02 (geometry) --- (continued)

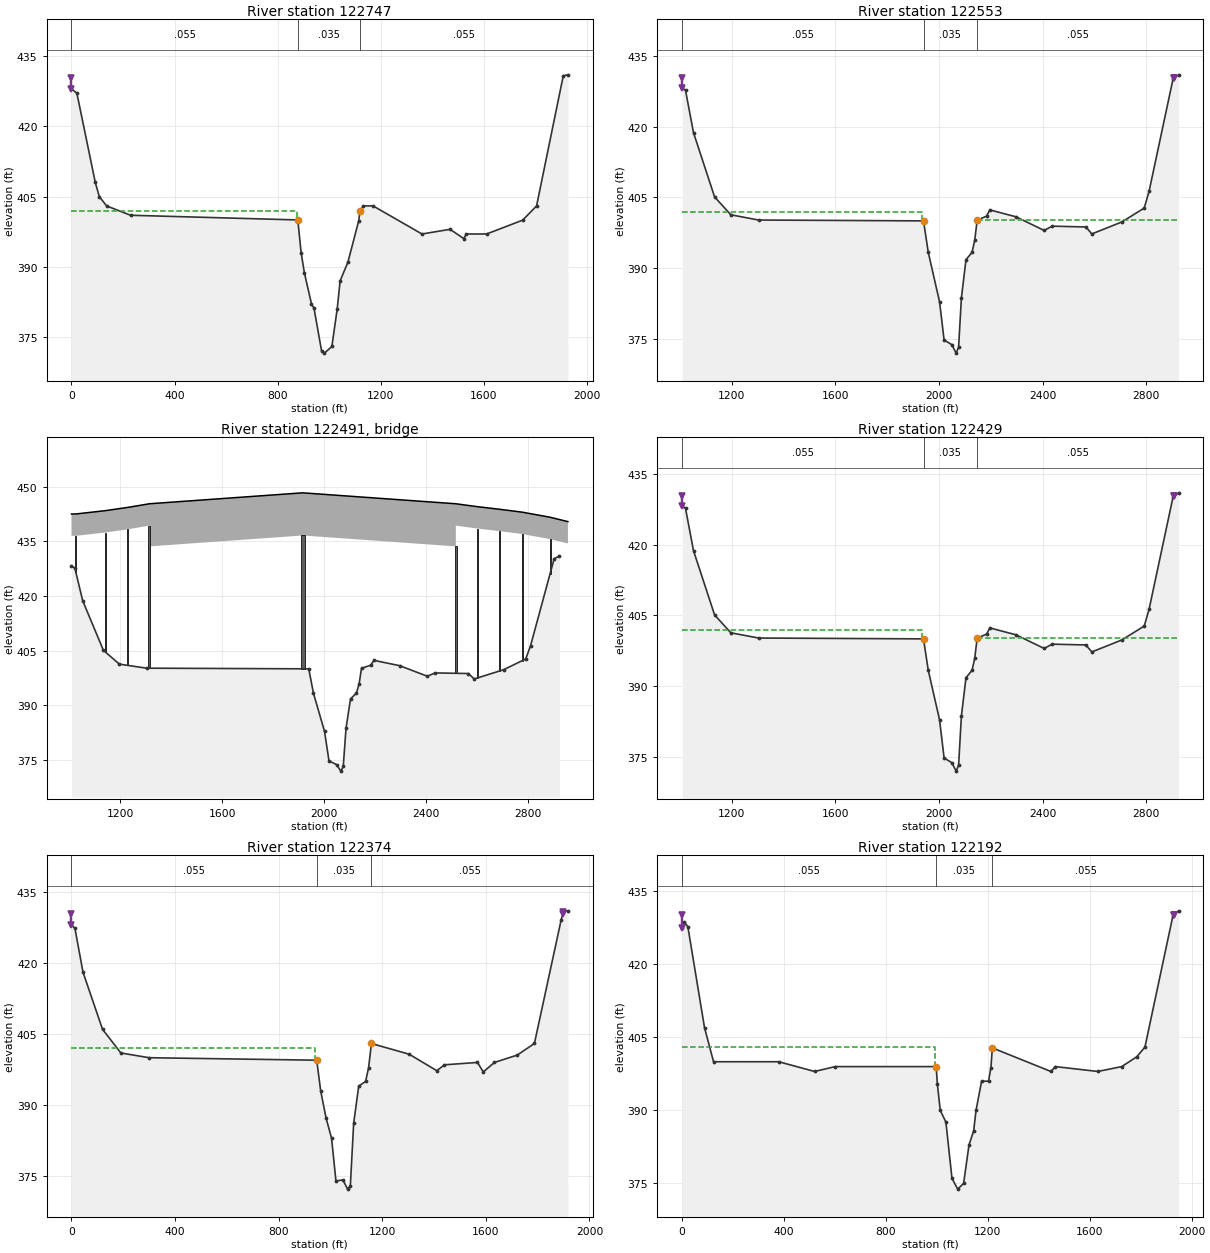
Type RM Length L Ch R = 1 ,122747  ,255,194,137
BEGIN DESCRIPTION:
This cross section corresponds to cross section 122760 of the non-georeferenced CDC model which was the source of this model.
END DESCRIPTION:
XS GIS Cut Line= 2
2484784.139387856971545.035340222483161.140993426970508.11779463
#Sta/Elev= 30
       0     428   20.88  427.08   92.37     408  107.86     405   136.2     403
  229.15     401  878.01     400   890.9     393  903.76  388.64  930.98   382.1
  941.03  381.09  970.32     372  981.58  371.55 1010.24  372.98 1030.93     381
 1042.29     387 1072.54     391 1114.49  399.85 1119.01  401.86 1132.56     403
 1169.92     403 1359.72     397 1468.86     398 1522.36     396 1531.54     397
  1610.6     397 1750.44  399.96 1804.38     403 1907.95   430.8 1925.96     431
#Mann= 3 ,0,0
       0    .055       0  878.01    .035       0 1119.01    .055       0
Levee=-1,0,430.42,-1,1926,430.42,,
#XS Ineff= 2 , 0
       0     873     402 1119.01       0  401.86
Permanent Ineff=
       F       F
Bank Sta=878.01,1119.01
XS Rating Curve= 0 ,0
Exp/Cntr=0.3,0.1

Type RM Length L Ch R = 1 ,122553  ,124,124,124
BEGIN DESCRIPTION:
This cross section corresponds to cross section 122562 of the non-georeferenced CDC model which was the source of this model.
--------------------------------------------------------------------
CDC DAL051805-1 Woodall Rogers Extension (Margaret Hunt Hill Bridge)
--------------------------------------------------------------------
END DESCRIPTION:
XS GIS Cut Line= 2
     2484952.587     6971229.092     2483188.578      6970480.22
#Sta/Elev= 30
    1009  428.17 1022.05   427.7 1052.84  418.72 1134.25  405.08 1196.96  401.29
    1304  400.18 1940.35     400 1958.72  393.32 2002.27  382.81 2019.78  374.72
 2049.41  373.73 2066.38  371.93 2075.75  373.21 2086.59  383.66 2104.25  391.76
 2127.69  393.34  2137.9  395.86 2147.41  400.14  2183.7  401.01 2196.13  402.33
 2296.92  400.87 2405.91  397.97 2436.36  398.88 2566.83  398.71  2589.9  397.23
 2705.59  399.77 2792.02  402.72 2810.77  406.29 2903.41  430.18 2924.53     431
#Mann= 3 ,0,0
    1009    .055       0 1940.35    .035       0 2147.41    .055       0
Levee=-1,1009,430.25,-1,2907,430.25,,
#XS Ineff= 2 , 0
         1934.17401.7998 2147.41        400.1407
Permanent Ineff=
       F       F
Bank Sta=1940.35,2147.41
XS Rating Curve= 0 ,0
Exp/Cntr=0.3,0.1

Type RM Length L Ch R = 3 ,122491  ,,,
BEGIN DESCRIPTION:
122500  Woodall Rodgers Freeway
-----------------------------------------------------------------------
CDC DAL051805-1 Woodall Rogers Extension (Margaret Hunt Hill Bridge)
-----------------------------------------------------------------------
END DESCRIPTION:
Node Name=Woodall Rogers
Bridge Culvert--1,0,-1,-1, 0
Deck Dist Width WeirC Skew NumUp NumDn MinLoCord MaxHiCord MaxSubmerge Is_Ogee
2,120,2.6,0, 14, 14, , , 0.95, 0, 0,0,,
    1009    1026    1141    1230    1315    1315  1916.3  2517.6  2517.6  2602.6
  2687.6  2777.6  2887.6  2957.6
   442.5   442.5   443.4   444.3   445.3   445.3   448.3   445.3   445.3   444.5
   443.8     443   441.6   440.4
   436.5   436.5   437.4   438.3   439.3   433.6   436.6   433.6   439.3   438.5
   437.8     437   435.6   434.4
    1009    1026    1141    1230    1315    1315  1916.3  2517.6  2517.6  2602.6
  2687.6  2777.6  2887.6  2957.6
   442.5   442.5   443.4   444.3   445.3   445.3   448.3   445.3   445.3   444.5
   443.8     443   441.6   440.4
   436.5   436.5   437.4   438.3   439.3   433.6   436.6   433.6   439.3   438.5
   437.8     437   435.6   434.4
Pier Skew, UpSta & Num, DnSta & Num=  ,1026, 2 ,1026, 2 , 0 , 0 , 0 ,,
     3.5     3.5
       0     440
     3.5     3.5
       0     440
Pier Skew, UpSta & Num, DnSta & Num=  ,1141, 2 ,1141, 2 , 0 , 0 , 0 ,,
     3.5     3.5
       0     440
     3.5     3.5
       0     440
Pier Skew, UpSta & Num, DnSta & Num=  ,1230, 2 ,1230, 2 , 0 , 0 , 0 ,,
     3.5     3.5
       0     440
     3.5     3.5
       0     440
Pier Skew, UpSta & Num, DnSta & Num=  ,1315, 2 ,1315, 2 , 0 , 0 , 0 ,,
       8       8
       0     440
       8       8
       0     440
Pier Skew, UpSta & Num, DnSta & Num=  ,1916.3, 2 ,1916.3, 2 , 0 , 0 , 0 ,,
      16      16
       0     440
      16      16
       0     440
Pier Skew, UpSta & Num, DnSta & Num=  ,2517.6, 2 ,2517.6, 2 , 0 , 0 , 0 ,,
       8       8
       0     440
       8       8
       0     440
Pier Skew, UpSta & Num, DnSta & Num=  ,2602.6, 2 ,2602.6, 2 , 0 , 0 , 0 ,,
     3.5     3.5
       0     440
     3.5     3.5
       0     440
Pier Skew, UpSta & Num, DnSta & Num=  ,2687.6, 2 ,2687.6, 2 , 0 , 0 , 0 ,,
     3.5     3.5
       0     440
     3.5     3.5
       0     440
Pier Skew, UpSta & Num, DnSta & Num=  ,2777.6, 2 ,2777.6, 2 , 0 , 0 , 0 ,,
     3.5     3.5
       0     440
     3.5     3.5
       0     440
Pier Skew, UpSta & Num, DnSta & Num=  ,2887.6, 2 ,2887.6, 2 , 0 , 0 , 0 ,,
     3.5     3.5
       0     440
     3.5     3.5
       0     440
BR Coef=-1 , 1 , 1 ,1.05, 0 ,,,0.8,-1,1.2,1,
WSPro=,,,, 1 ,,,, 0 ,,,, 0 ,,,,-1 ,-1 ,-1 , 0 , 0 , 0 , 0 , 0
BC Design=,, 0 ,, 0 ,,,,,,
BC Use User HTab Curves=0
BC User HTab FreeFlow(D)= 0

Type RM Length L Ch R = 1 ,122429  ,29,55,81
BEGIN DESCRIPTION:
This cross section corresponds to cross section 122438 of the non-georeferenced CDC model which was the source of this model.
---------------------------------------------------------------------
CDC DAL051805-1 Woodall Rogers Extension (Margaret Hunt Hill Bridge)
---------------------------------------------------------------------
END DESCRIPTION:
XS GIS Cut Line= 2
     2484991.108     6971108.173     2483229.875     6970366.883
#Sta/Elev= 30
    1009  428.17 1022.05   427.7 1052.84  418.72 1134.25  405.08 1196.96  401.29
    1304  400.18 1940.35     400 1958.72  393.32 2002.27  382.81 2019.78  374.72
 2049.41  373.73 2066.38  371.93 2075.75  373.21 2086.59  383.66 2104.25  391.76
 2127.69  393.34  2137.9  395.86 2147.41  400.14  2183.7  401.01 2196.13  402.33
 2296.92  400.87 2405.91  397.97 2436.36  398.88 2566.83  398.71  2589.9  397.23
 2705.59  399.77 2792.02  402.72 2810.77  406.29 2903.41  430.18 2924.53     431
#Mann= 3 ,0,0
    1009    .055       0 1940.35    .035       0 2147.41    .055       0
Levee=-1,1009,430.25,-1,2907,430.25,,
#XS Ineff= 2 , 0
         1934.17401.7998 2147.41        400.1407
Permanent Ineff=
       F       F
Bank Sta=1940.35,2147.41
XS Rating Curve= 0 ,0
Exp/Cntr=0.3,0.1

Type RM Length L Ch R = 1 ,122374  ,201,182,168
BEGIN DESCRIPTION:
This cross section corresponds to cross section 122390 of the non-georeferenced CDC model which was the source of this model.
END DESCRIPTION:
XS GIS Cut Line= 2
     2485058.354     6971078.629     2483296.379     6970333.178
#Sta/Elev= 30
       0     428   13.24  427.33   44.47  418.04  119.83     406  190.68     401
  299.26     400  946.94  399.47  962.23     393  983.05  387.25 1004.24     383
 1021.14     374 1048.35   374.2  1066.1  372.26 1076.74  372.93 1089.58  386.14
 1109.12     394 1135.73     395 1147.34  397.91 1158.14     403 1304.12  400.73
 1410.54  397.26 1440.27   398.5 1567.66     399 1590.19     397 1633.22     399
 1721.26  400.55 1787.53     403 1890.44     429 1899.58  430.93 1916.91     431
#Mann= 3 ,0,0
       0    .055       0  946.94    .035       0 1158.14    .055       0
Levee=-1,0,430.23,-1,1899,430.23,,
#XS Ineff= 2 , 0
       0  938.54  402.08 1158.14       0     403
Permanent Ineff=
       F       F
Bank Sta=946.94,1158.14
XS Rating Curve= 0 ,0
Exp/Cntr=0.3,0.1

Type RM Length L Ch R = 1 ,122192  ,179,154,137
BEGIN DESCRIPTION:
This cross section corresponds to cross section 122206 of the non-georeferenced CDC model which was the source of this model.
END DESCRIPTION:
XS GIS Cut Line= 2
2485166.659620176970954.970575472483390.683841416970153.37080072
#Sta/Elev= 30
       0  427.43    8.47  428.72   22.46  427.73   87.84     407  123.25     400
  379.15     400  519.95     398  601.04     399     997     399 1001.99  395.33
 1013.11     390 1035.27   387.6 1059.04  376.06 1081.55  373.83 1104.84     375
 1125.92  382.89 1144.34  385.83 1153.51     390 1175.38     396 1202.55     396
 1211.98   398.8 1217.55  402.84 1447.39     398  1464.9     399 1631.46     398
 1725.26     399 1784.13     401 1816.42     403 1926.28  429.98  1948.5     431
#Mann= 3 ,0,0
       0    .055       0     997    .035       0 1217.55    .055       0
Levee=-1,0,430.13,-1,1931,430.13,,
#XS Ineff= 2 , 0
       0  993.03     403 1217.55       0  402.84
Permanent Ineff=
       F       F
Bank Sta=997,1217.55
XS Rating Curve= 0 ,0
Exp/Cntr=0.3,0.1

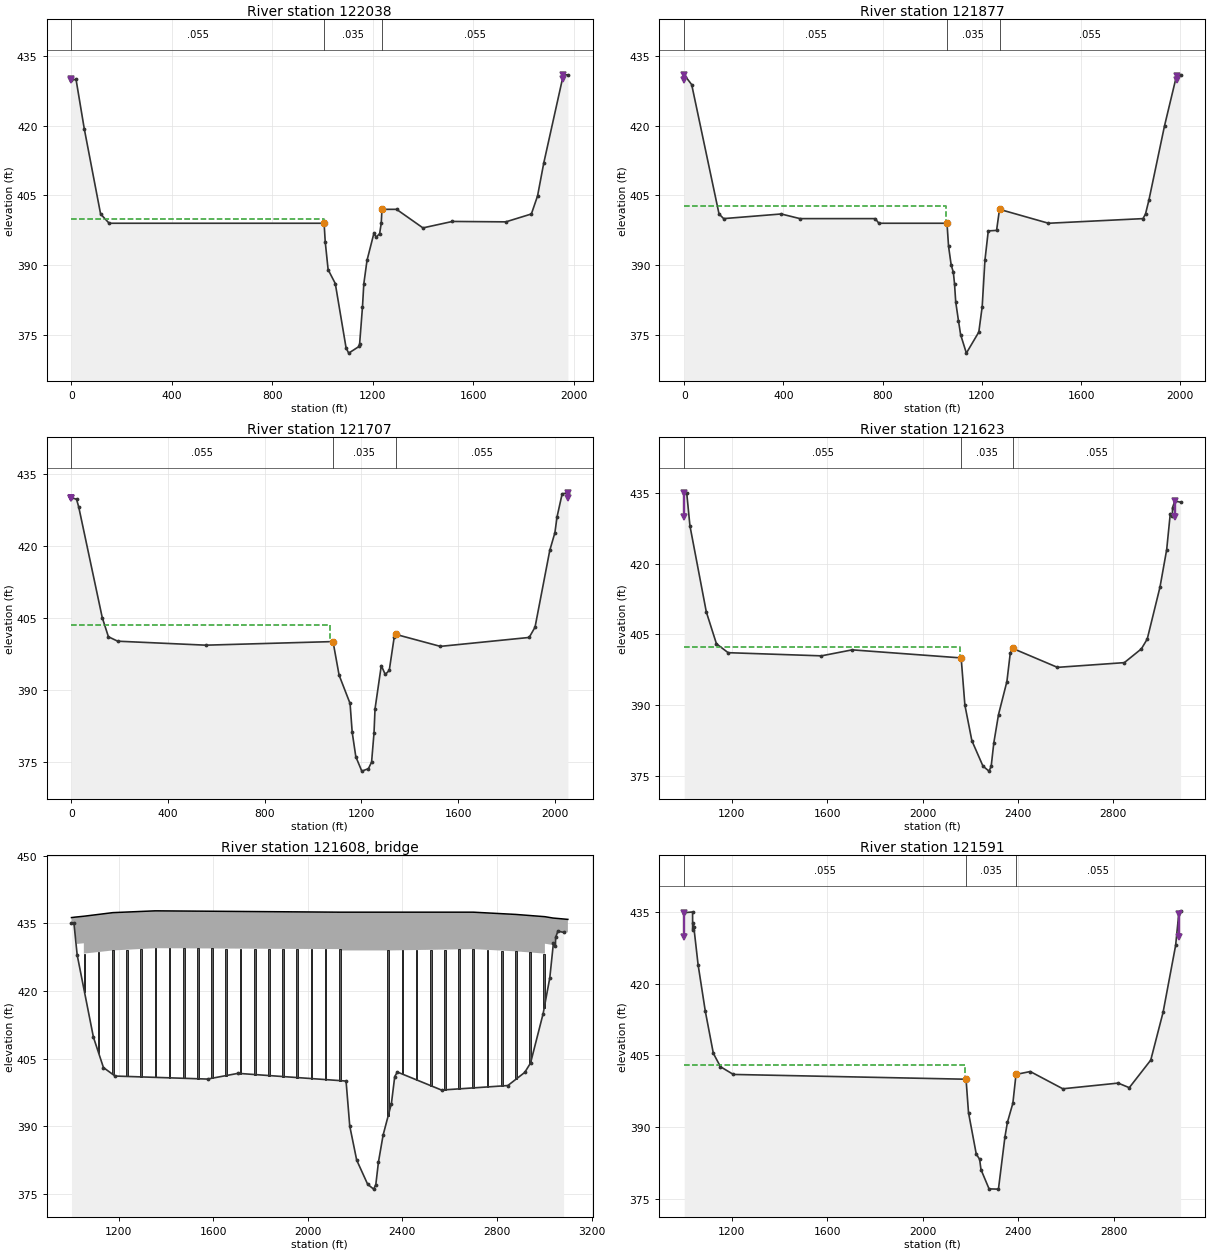
Type RM Length L Ch R = 1 ,122038  ,187,161,144
BEGIN DESCRIPTION:
This cross section corresponds to cross section 122045 of the non-georeferenced CDC model which was the source of this model.
END DESCRIPTION:
XS GIS Cut Line= 2
2485267.943538346970764.867609222483422.764485936970054.74173288
#Sta/Elev= 30
       0   429.9    18.2     430   50.89  419.38  115.93     401     150     399
 1006.15     399 1010.65     395 1022.17     389 1050.72     386 1093.72  372.12
  1104.1     371 1145.39  372.44 1147.66     373 1159.09     381 1164.32  385.94
  1177.1     391 1204.37  396.81 1213.43     396 1227.39  396.77 1233.73     399
 1236.57     402 1294.76     402 1399.84     398 1517.43  399.39  1729.9   399.3
 1831.74     401 1856.32  404.89 1881.11     412 1959.09     431 1977.11     431
#Mann= 3 ,0,0
       0    .055       0 1006.15    .035       0 1236.57    .055       0
Levee=-1,0,430.03,-1,1959,430.03,,
#XS Ineff= 2 , 0
       0 1005.13     400 1236.57       0     402
Permanent Ineff=
       F       F
Bank Sta=1006.15,1236.57
XS Rating Curve= 0 ,0
Exp/Cntr=0.3,0.1

Type RM Length L Ch R = 1 ,121877  ,197,170,151
BEGIN DESCRIPTION:
This cross section corresponds to cross section 121884 of the non-georeferenced CDC model which was the source of this model.
END DESCRIPTION:
XS GIS Cut Line= 2
2485396.303845916970574.726913382483491.89623743 6969959.2652178
#Sta/Elev= 30
       0     431   30.15  428.89  140.45     401  159.13     400  391.05     401
  466.82     400     770     400     785     399 1059.57     399 1065.88     394
 1076.43     390 1085.12  388.44  1089.8     386 1094.78     382 1105.68  378.03
 1114.41     375 1137.64     371  1187.8  375.54 1201.42     381 1212.47     391
 1225.95  397.35 1259.45  397.46 1271.26     402 1468.78     399 1849.86     400
  1859.9     401 1873.69     404 1936.56     420 1985.86     431 2001.39     431
#Mann= 3 ,0,0
       0    .055       0 1059.57    .035       0 1271.26    .055       0
Levee=-1,0,429.93,-1,1985,429.93,,
#XS Ineff= 2 , 0
       0 1055.09  402.73 1271.26       0     402
Permanent Ineff=
       F       F
Bank Sta=1059.57,1271.26
XS Rating Curve= 0 ,0
Exp/Cntr=0.3,0.1

Type RM Length L Ch R = 1 ,121707  ,84,84,84
BEGIN DESCRIPTION:
This cross section corresponds to cross section 121723 of the non-georeferenced CDC model which was the source of this model.
END DESCRIPTION:
XS GIS Cut Line= 2
 2485513.56607866970368.026211312483528.103842176969840.84091397
#Sta/Elev= 30
       0     430   21.01  429.65   30.17     428  127.29     405  152.83     401
  191.26  400.08  555.91  399.25 1082.36     400  1107.5     393 1152.88   387.1
 1161.63  381.12 1176.68     376 1201.46     373 1228.82  373.51 1241.95  374.89
 1252.04     381 1256.14  385.96 1282.11     395 1298.47  393.14 1315.09     394
 1335.75     401 1341.41  401.51  1526.6     399 1894.11  400.86 1918.35     403
 1979.35     419 2000.59   422.7 2009.46     426 2030.58  430.79 2054.26     431
#Mann= 3 ,0,0
       0    .055       0 1082.36    .035       0 1341.41    .055       0
Levee=-1,0,429.83,-1,2054,429.83,,
#XS Ineff= 2 , 0
       0  1070.6  403.49 1341.41       0  401.51
Permanent Ineff=
       F       F
Bank Sta=1082.36,1341.41
XS Rating Curve= 0 ,0
Exp/Cntr=0.3,0.1

Type RM Length L Ch R = 1 ,121623  ,32,32,32
BEGIN DESCRIPTION:
This cross section corresponds to cross section 121639 of the non-georeferenced CDC model which was the source of this model.
END DESCRIPTION:
XS GIS Cut Line= 2
  2485584.9770256970300.325887382483572.689054856969766.23738863
#Sta/Elev= 30
    1000     435 1010.47     435 1024.07     428 1092.75  409.75 1135.19     403
 1184.24  401.11 1575.47  400.44 1704.48  401.71 2161.61     400 2177.23     390
 2206.55  382.45 2253.03  377.07 2278.37     376 2287.46     377  2298.6     382
 2318.31     388 2353.45     395 2367.54     401 2378.65     402 2565.48     398
 2845.96     399 2917.49  401.92 2942.04     404 2995.46     415 3023.62  422.96
 3038.72   430.6 3047.41     430 3048.23  431.88 3057.79  433.28 3081.96  433.01
#Mann= 3 ,0,0
    1000    .055       0 2161.61    .035       0 2378.65    .055       0
Levee=-1,1000,429.78,-1,3058,429.78,,
#XS Ineff= 2 , 0
       0 2154.78  402.31 2378.65       0     402
Permanent Ineff=
       F       F
Bank Sta=2161.61,2378.65
XS Rating Curve= 0 ,0
Exp/Cntr=0.3,0.1

Type RM Length L Ch R = 3 ,121608  ,,,
BEGIN DESCRIPTION:
121623  Union Pacific Railroad
END DESCRIPTION:
Node Name=UP Railroad
Bridge Culvert--1,0,-1,-1, 0
Deck Dist Width WeirC Skew NumUp NumDn MinLoCord MaxHiCord MaxSubmerge Is_Ogee
1,28,2.6,0, 16, 16, , , 0.95, 0, ,,,
    1000    1015 1052.25 1052.25    1175    1355    2135    2135    2340    2700
    2880 3002.75 3002.75    3037    3037    3100
   436.3   436.4   436.6   436.6   437.4   437.8   437.5   437.5   437.5   437.5
     437   436.5   436.5   436.2   436.2   435.9
   430.2   430.4   430.6   428.3     429   429.5   429.3     429     429   429.3
   428.8   428.3   430.5   430.2     405     405
    1000    1015 1052.25 1052.25    1175    1355    2135    2135    2340    2700
    2880 3002.75 3002.75    3037    3037    3100
   436.3   436.4   436.6   436.6   437.4   437.8   437.5   437.5   437.5   437.5
     437   436.5   436.5   436.2   436.2   435.9
   430.2   430.4   430.6   428.3     429   429.5   429.3     429     429   429.3
   428.8   428.3   430.5   430.2     405     405
Pier Skew, UpSta & Num, DnSta & Num=  ,1055, 4 ,1055, 4 , 3 , 3 , 0 ,,
       7     4.7     5.5     5.5
   397.6   425.2   425.2     435
       7     4.7     5.5     5.5
   397.6   425.2   425.2     435
Pier Skew, UpSta & Num, DnSta & Num=  ,1115, 4 ,1115, 4 , 3 , 3 , 0 ,,
       7     4.7     5.5     5.5
   397.9   425.5   425.5     432
       7     4.7     5.5     5.5
   397.9   425.5   425.5     432
Pier Skew, UpSta & Num, DnSta & Num=  ,1175, 4 ,1175, 4 , 3 , 3 , 0 ,,
       7     4.7     5.5     5.5
   398.4     426     426     432
       7     4.7     5.5     5.5
   398.4     426     426     432
Pier Skew, UpSta & Num, DnSta & Num=  ,1235, 4 ,1235, 4 , 3 , 3 , 0 ,,
       7     4.7     5.5     5.5
   398.4     426     426     432
       7     4.7     5.5     5.5
   398.4     426     426     432
Pier Skew, UpSta & Num, DnSta & Num=  ,1295, 4 ,1295, 4 , 3 , 3 , 0 ,,
       7     4.7     5.5     5.5
   398.6   426.2   426.2     432
       7     4.7     5.5     5.5
   398.6   426.2   426.2     432
Pier Skew, UpSta & Num, DnSta & Num=  ,1355, 4 ,1355, 4 , 3 , 3 , 0 ,,
       7     4.7     5.5     5.5
   398.8   426.4   426.4     432
       7     4.7     5.5     5.5
   398.8   426.4   426.4     432
Pier Skew, UpSta & Num, DnSta & Num=  ,1415, 4 ,1415, 4 , 3 , 3 , 0 ,,
       7     4.7     5.5     5.5
   398.8   426.4   426.4     432
       7     4.7     5.5     5.5
   398.8   426.4   426.4     432
Pier Skew, UpSta & Num, DnSta & Num=  ,1475, 4 ,1475, 4 , 3 , 3 , 0 ,,
       7     4.7     5.5     5.5
   398.8   426.4   426.4     432
       7     4.7     5.5     5.5
   398.8   426.4   426.4     432
Pier Skew, UpSta & Num, DnSta & Num=  ,1535, 4 ,1535, 4 , 3 , 3 , 0 ,,
       7     4.7     5.5     5.5
   398.8   426.4   426.4     432
       7     4.7     5.5     5.5
   398.8   426.4   426.4     432
Pier Skew, UpSta & Num, DnSta & Num=  ,1595, 4 ,1595, 4 , 3 , 3 , 0 ,,
       7     4.7     5.5     5.5
   398.8   426.4   426.4     432
       7     4.7     5.5     5.5
   398.8   426.4   426.4     432
Pier Skew, UpSta & Num, DnSta & Num=  ,1655, 4 ,1655, 4 , 3 , 3 , 0 ,,
       7     4.7     5.5     5.5
   398.8   426.4   426.4     432
       7     4.7     5.5     5.5
   398.8   426.4   426.4     432
Pier Skew, UpSta & Num, DnSta & Num=  ,1715, 4 ,1715, 4 , 3 , 3 , 0 ,,
       7     4.7     5.5     5.5
   398.8   426.4   426.4     432
       7     4.7     5.5     5.5
   398.8   426.4   426.4     432
Pier Skew, UpSta & Num, DnSta & Num=  ,1775, 4 ,1775, 4 , 3 , 3 , 0 ,,
       7     4.7     5.5     5.5
   398.8   426.4   426.4     432
       7     4.7     5.5     5.5
   398.8   426.4   426.4     432
Pier Skew, UpSta & Num, DnSta & Num=  ,1835, 4 ,1835, 4 , 3 , 3 , 0 ,,
       7     4.7     5.5     5.5
   398.8   426.4   426.4     432
       7     4.7     5.5     5.5
   398.8   426.4   426.4     432
Pier Skew, UpSta & Num, DnSta & Num=  ,1895, 4 ,1895, 4 , 3 , 3 , 0 ,,
       7     4.7     5.5     5.5
   398.8   426.4   426.4     432
       7     4.7     5.5     5.5
   398.8   426.4   426.4     432
Pier Skew, UpSta & Num, DnSta & Num=  ,1955, 4 ,1955, 4 , 3 , 3 , 0 ,,
       7     4.7     5.5     5.5
   398.8   426.4   426.4     432
       7     4.7     5.5     5.5
   398.8   426.4   426.4     432
Pier Skew, UpSta & Num, DnSta & Num=  ,2015, 4 ,2015, 4 , 3 , 3 , 0 ,,
       7     4.7     5.5     5.5
   398.8   426.4   426.4     432
       7     4.7     5.5     5.5
   398.8   426.4   426.4     432
Pier Skew, UpSta & Num, DnSta & Num=  ,2075, 4 ,2075, 4 , 3 , 3 , 0 ,,
       7     4.7     5.5     5.5
   398.8   426.4   426.4     432
       7     4.7     5.5     5.5
   398.8   426.4   426.4     432
Pier Skew, UpSta & Num, DnSta & Num=  ,2135, 4 ,2135, 4 , 3 , 3 , 0 ,,
      10     7.7     8.5     8.5
   394.4     422     422     432
      10     7.7     8.5     8.5
   394.4     422     422     432
Pier Skew, UpSta & Num, DnSta & Num=  ,2340, 4 ,2340, 4 , 3 , 3 , 0 ,,
      10     7.7     8.5     8.5
   394.4     422     422     432
      10     7.7     8.5     8.5
   394.4     422     422     432
Pier Skew, UpSta & Num, DnSta & Num=  ,2400, 4 ,2400, 4 , 3 , 3 , 0 ,,
       7     4.7     5.5     5.5
   398.7   426.3   426.3     432
       7     4.7     5.5     5.5
   398.7   426.3   426.3     432
Pier Skew, UpSta & Num, DnSta & Num=  ,2460, 4 ,2460, 4 , 3 , 3 , 0 ,,
       7     4.7     5.5     5.5
   398.7   426.3   426.3     432
       7     4.7     5.5     5.5
   398.7   426.3   426.3     432
Pier Skew, UpSta & Num, DnSta & Num=  ,2520, 4 ,2520, 4 , 3 , 3 , 0 ,,
       7     4.7     5.5     5.5
   398.7   426.3   426.3     432
       7     4.7     5.5     5.5
   398.7   426.3   426.3     432
Pier Skew, UpSta & Num, DnSta & Num=  ,2580, 4 ,2580, 4 , 3 , 3 , 0 ,,
       7     4.7     5.5     5.5
   398.7   426.3   426.3     432
       7     4.7     5.5     5.5
   398.7   426.3   426.3     432
Pier Skew, UpSta & Num, DnSta & Num=  ,2640, 4 ,2640, 4 , 3 , 3 , 0 ,,
       7     4.7     5.5     5.5
   398.7   426.3   426.3     432
       7     4.7     5.5     5.5
   398.7   426.3   426.3     432
Pier Skew, UpSta & Num, DnSta & Num=  ,2700, 4 ,2700, 4 , 3 , 3 , 0 ,,
       7     4.7     5.5     5.5
   398.7   426.3   426.3     432
       7     4.7     5.5     5.5
   398.7   426.3   426.3     432
Pier Skew, UpSta & Num, DnSta & Num=  ,2760, 4 ,2760, 4 , 3 , 3 , 0 ,,
       7     4.7     5.5     5.5
   398.5   426.1   426.1     432
       7     4.7     5.5     5.5
   398.5   426.1   426.1     432
Pier Skew, UpSta & Num, DnSta & Num=  ,2820, 4 ,2820, 4 , 3 , 3 , 0 ,,
       7     4.7     5.5     5.5
   398.4     426     426     432
       7     4.7     5.5     5.5
   398.4     426     426     432
Pier Skew, UpSta & Num, DnSta & Num=  ,2880, 4 ,2880, 4 , 3 , 3 , 0 ,,
       7     4.7     5.5     5.5
   398.2   425.8   425.8     432
       7     4.7     5.5     5.5
   398.2   425.8   425.8     432
Pier Skew, UpSta & Num, DnSta & Num=  ,2940, 4 ,2940, 4 , 3 , 3 , 0 ,,
       7     4.7     5.5     5.5
   397.9   425.5   425.5     432
       7     4.7     5.5     5.5
   397.9   425.5   425.5     432
Pier Skew, UpSta & Num, DnSta & Num=  ,3000, 4 ,3000, 4 , 3 , 3 , 0 ,,
       7     4.7     5.5     5.5
   397.6   425.2   425.2     435
       7     4.7     5.5     5.5
   397.6   425.2   425.2     435
BR Coef= 1 , 1 , 1 ,0.9, 0 ,,,0.8,0,1.2,1,
WSPro=,,,, 1 ,,,, 0 ,,,, 0 ,,,,-1 ,-1 ,-1 , 0 , 0 , 0 , 0 , 0
BC Design=,, 0 ,, 0 ,,,,,,
BC HTab HWMax=430.2
BC Use User HTab Curves=0
BC User HTab FreeFlow(D)= 0

Type RM Length L Ch R = 1 ,121591  ,90,90,90
BEGIN DESCRIPTION:
This cross section corresponds to cross section 121607 of the non-georeferenced CDC model which was the source of this model.
END DESCRIPTION:
XS GIS Cut Line= 2
2485617.802418686970276.276066722483606.862870996969742.28861763
#Sta/Elev= 30
    1000  434.85  1035.1     435 1035.38  431.32 1037.76  432.61 1040.26  431.88
 1058.13     424 1088.53   414.2 1122.14  405.42  1151.9  402.62 1206.05     401
 2181.36     400 2191.68     393  2224.2  384.33 2238.23  383.25 2243.95  381.09
 2277.91  377.05 2317.17     377 2344.54     388 2354.87     391 2377.68     395
 2390.73     401 2450.41  401.61 2586.98     398  2818.9  399.19 2865.53  398.23
  2955.5     404 3007.18     414 3059.82     428 3073.83     435 3080.63  435.24
#Mann= 3 ,0,0
    1000    .055       0 2181.36    .035       0 2390.73    .055       0
Levee=-1,1000,429.76,-1,3073,429.76,,
#XS Ineff= 2 , 0
       0  2177.7     403 2390.73       0     401
Permanent Ineff=
       F       F
Bank Sta=2181.36,2390.73
XS Rating Curve= 0 ,0
Exp/Cntr=0.3,0.1

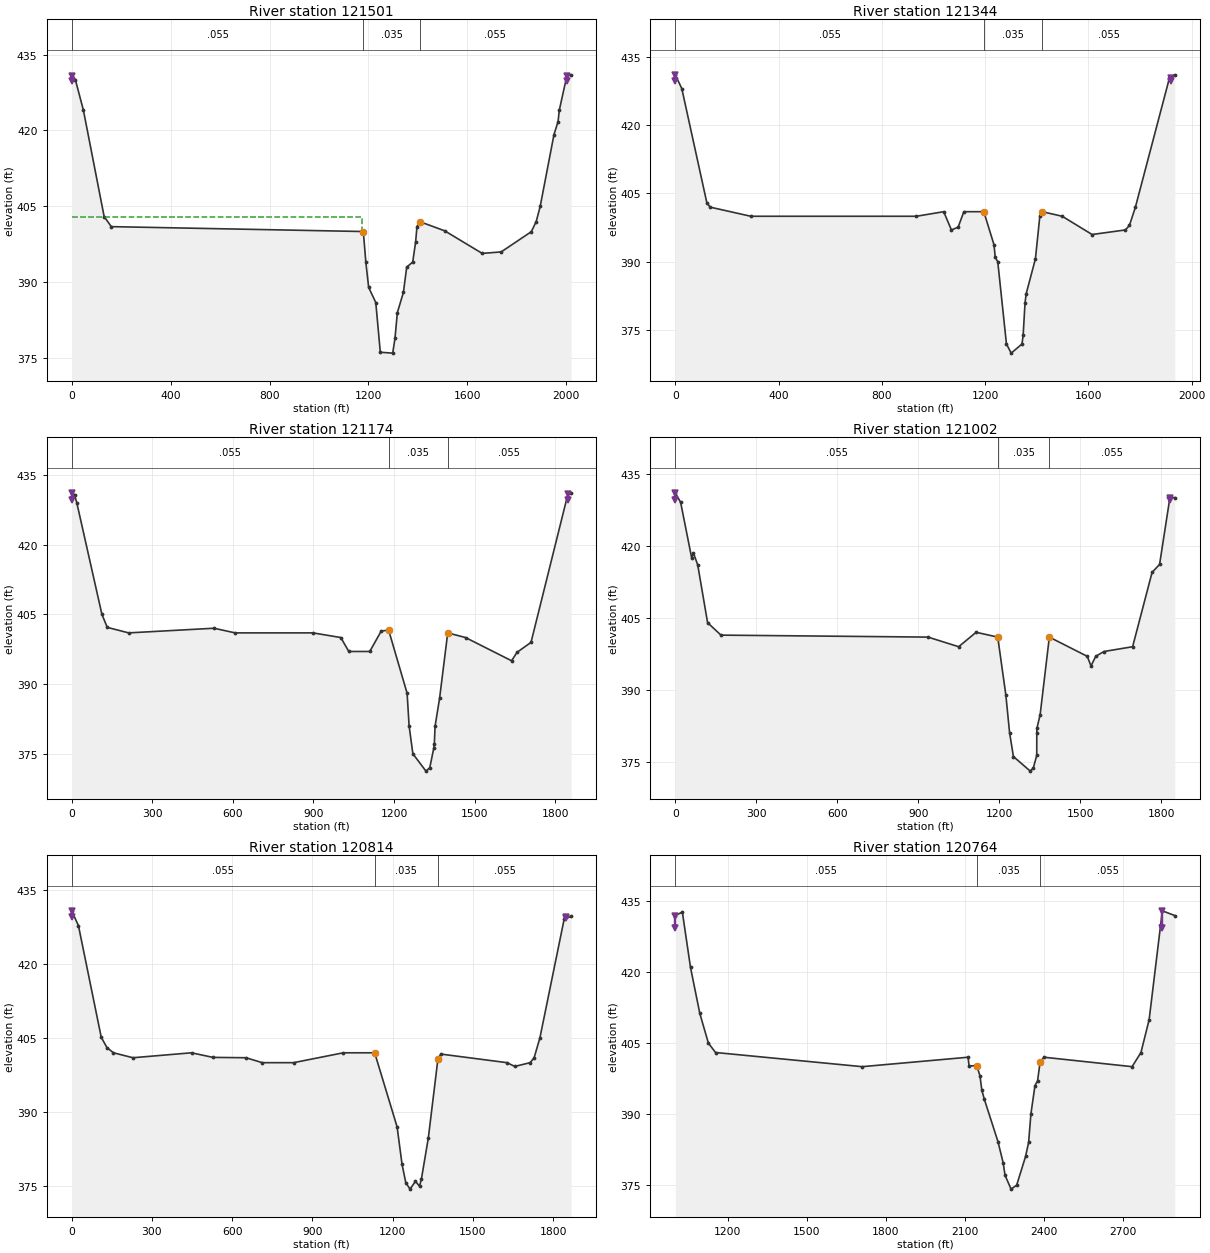
Type RM Length L Ch R = 1 ,121501  ,159,157,159
BEGIN DESCRIPTION:
This cross section corresponds to cross section 121517 of the non-georeferenced CDC model which was the source of this model.
END DESCRIPTION:
XS GIS Cut Line= 2
2485632.313544516970189.548877972483681.686212186969667.45149697
#Sta/Elev= 30
       0  430.71   15.24     430   47.56     424  131.34     403  160.29     401
 1179.17  400.03 1189.26     394  1200.7     389 1229.51     386 1247.86  376.17
 1297.94     376 1307.26  378.94 1316.68     384 1341.19     388 1354.57     393
 1378.85     394 1390.68     398 1396.01     401 1406.62     402 1508.18  400.17
 1659.67  395.71 1736.36     396 1858.35     400 1878.01     402 1894.19     405
 1949.96   419.2 1966.49  421.77 1971.34     424 2002.93     431 2019.29     431
#Mann= 3 ,0,0
       0    .055       0 1179.17    .035       0 1406.62    .055       0
Levee=-1,0,429.73,-1,2002,429.73,,
#XS Ineff= 2 , 0
       0 1174.65     403 1406.62       0     402
Permanent Ineff=
       F       F
Bank Sta=1179.17,1406.62
XS Rating Curve= 0 ,0
Exp/Cntr=0.3,0.1

Type RM Length L Ch R = 1 ,121344  ,174,170,174
BEGIN DESCRIPTION:
This cross section corresponds to cross section 121345 of the non-georeferenced CDC model which was the source of this model.
END DESCRIPTION:
XS GIS Cut Line= 2
2485710.568965446970048.576718972483841.74297866 6969549.1065893
#Sta/Elev= 30
       0     431   25.19     428  122.05     403  135.08     402  292.21     400
  933.89     400 1039.55     401 1069.35     397 1095.29   397.6 1117.63     401
  1194.8     401 1234.47  393.73 1239.02     391 1248.86  390.04 1282.54     372
 1300.85     370 1342.79     372 1347.27     374 1354.47     381  1358.9     383
 1394.71  390.67 1411.81     400 1421.12     401 1498.49     400 1614.15     396
 1743.11     397 1758.76     398 1781.64  401.93 1912.38     430 1934.42     431
#Mann= 3 ,0,0
       0    .055       0  1194.8    .035       0 1421.12    .055       0
Levee=-1,0,429.65,-1,1919,429.65,,
#XS Ineff= 2 , 0
       0  1194.8     401 1421.12       0     401
Permanent Ineff=
       F       F
Bank Sta=1194.8,1421.12
XS Rating Curve= 0 ,0
Exp/Cntr=0.3,0.1

Type RM Length L Ch R = 1 ,121174  ,175,172,175
BEGIN DESCRIPTION:
This cross section corresponds to cross section 121174 of the non-georeferenced CDC model which was the source of this model.
END DESCRIPTION:
XS GIS Cut Line= 2
2485779.53601909 6969892.60590232483983.392957846969413.32208396
#Sta/Elev= 30
       0     431   11.39  430.56   19.14     429  112.55  405.02  132.46  402.19
  212.19     401  529.64     402  608.53     401  898.03     401 1001.61     400
 1031.54     397 1109.54     397 1152.33  401.41 1179.89  401.57 1248.54     388
 1255.92     381 1269.93     375 1318.69  371.26 1332.83     372 1348.08  376.29
 1349.77     377 1352.49  380.88 1369.54     387 1399.66     401 1465.87     400
 1637.31     395 1657.66  396.82 1709.65  398.96 1847.57     431 1858.99  431.13
#Mann= 3 ,0,0
       0    .055       0 1179.89    .035       0 1399.66    .055       0
Levee=-1,0,429.58,-1,1847,429.58,,
#XS Ineff= 2 , 0
       0 1179.89  401.57 1399.66       0     401
Permanent Ineff=
       F       F
Bank Sta=1179.89,1399.66
XS Rating Curve= 0 ,0
Exp/Cntr=0.3,0.1

Type RM Length L Ch R = 1 ,121002  ,193,188,193
BEGIN DESCRIPTION:
This cross section corresponds to cross section 121002 of the non-georeferenced CDC model which was the source of this model.
END DESCRIPTION:
XS GIS Cut Line= 2
2485845.35380083 6969735.79125532484057.748452196969259.30303505
#Sta/Elev= 30
       0     431   19.91     429   60.86  417.42   67.08  418.52   83.16     416
  119.69     404  169.23  401.41  936.15     401 1049.51     399 1114.29     402
 1194.32     401 1224.24     389 1238.23   381.1 1252.39  376.16 1314.81  373.13
  1326.1  373.79 1338.75  376.41 1338.97     381 1339.33     382 1351.33  384.86
 1385.42     401 1525.92     397 1539.74     395 1557.26     397 1587.45     398
 1693.88     399  1765.9  414.45 1793.75  416.12 1831.98     430 1850.02     430
#Mann= 3 ,0,0
       0    .055       0 1194.32    .035       0 1385.42    .055       0
Levee=-1,0,429.51,-1,1832,429.51,,
#XS Ineff= 2 , 0
       0 1194.32     401 1385.42       0     401
Permanent Ineff=
       F       F
Bank Sta=1194.32,1385.42
XS Rating Curve= 0 ,0
Exp/Cntr=0.3,0.1

Type RM Length L Ch R = 1 ,120814  ,50,50,50
BEGIN DESCRIPTION:
This cross section corresponds to cross section 120831 of the non-georeferenced CDC model which was the source of this model.
END DESCRIPTION:
XS GIS Cut Line= 2
2485920.959292686969568.774528972484116.033440596969088.93362513
#Sta/Elev= 30
       0  430.73   25.41  427.74  110.61  405.16  131.82  403.06   156.4     402
  229.22     401  448.25     402   528.5  401.07   651.9     401  712.73     400
  829.76     400  1015.7     402 1133.02     402 1216.91     387  1235.3  379.46
 1249.46   375.7 1265.42  374.41 1285.36     376 1300.79     375 1307.86  376.49
 1333.64  384.76 1369.58  400.77 1380.72  401.74 1628.04     400 1656.88  399.24
 1714.17     400 1729.27     401 1750.72     405 1841.35     429 1867.62  429.61
#Mann= 3 ,0,0
       0    .055       0 1133.02    .035       0 1369.58    .055       0
Levee=-1,0,429.44,-1,1849,429.44,,
#XS Ineff= 2 , 0
       0 1133.02     402 1369.58       0  400.77
Permanent Ineff=
       F       F
Bank Sta=1133.02,1369.58
XS Rating Curve= 0 ,0
Exp/Cntr=0.3,0.1

Type RM Length L Ch R = 1 ,120764  ,76,76,76
BEGIN DESCRIPTION:
This cross section corresponds to cross section 120765 of the non-georeferenced CDC model which was the source of this model.
END DESCRIPTION:
XS GIS Cut Line= 3
2485951.338825086969527.540359472484709.564405776969197.79298747
2484118.11119235 6969038.6489488
#Sta/Elev= 30
    1000     432 1026.88  432.74 1057.86     421  1093.2  411.27 1125.67     405
 1152.91     403 1709.91     400 2112.15     402 2115.92  400.17 2145.42   400.2
 2157.26  398.07 2164.48     395 2174.13  393.06 2225.66  384.14 2245.68  379.59
 2252.57     377 2275.45  374.07 2296.66   374.9 2330.61     381 2342.19     384
 2350.83     390 2366.26     396 2376.02  396.98 2385.87     401 2400.61     402
 2735.14     400 2768.84     403  2799.9  409.95 2850.04     433  2897.3     432
#Mann= 3 ,0,0
    1000    .055       0 2145.42    .035       0 2385.87    .055       0
Levee=-1,1000,429.41,-1,2850,429.41,,
#XS Ineff= 2 , 0
       0 2145.42   400.2 2385.87       0     401
Permanent Ineff=
       F       F
Bank Sta=2145.42,2385.87
XS Rating Curve= 0 ,0
Exp/Cntr=0.3,0.1