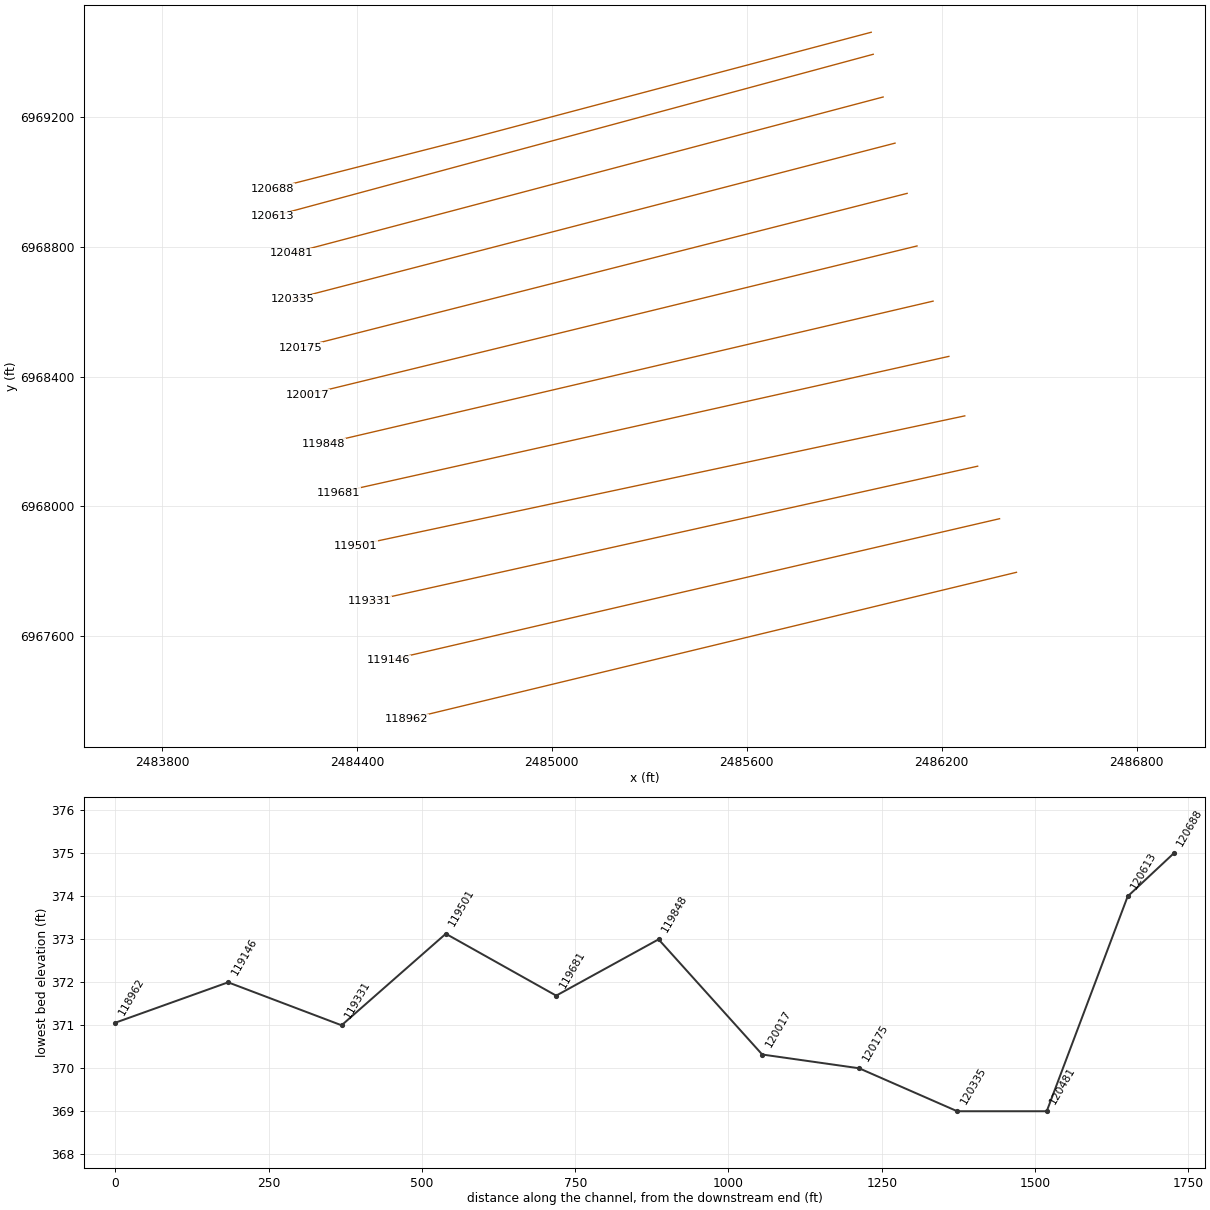
HEC-RAS study CDC_Consolidated_Model.prj: Upper Trinity CDC Consolidated Model

--- CDC_Consolidated_Model.g02 (geometry) --- (continued)

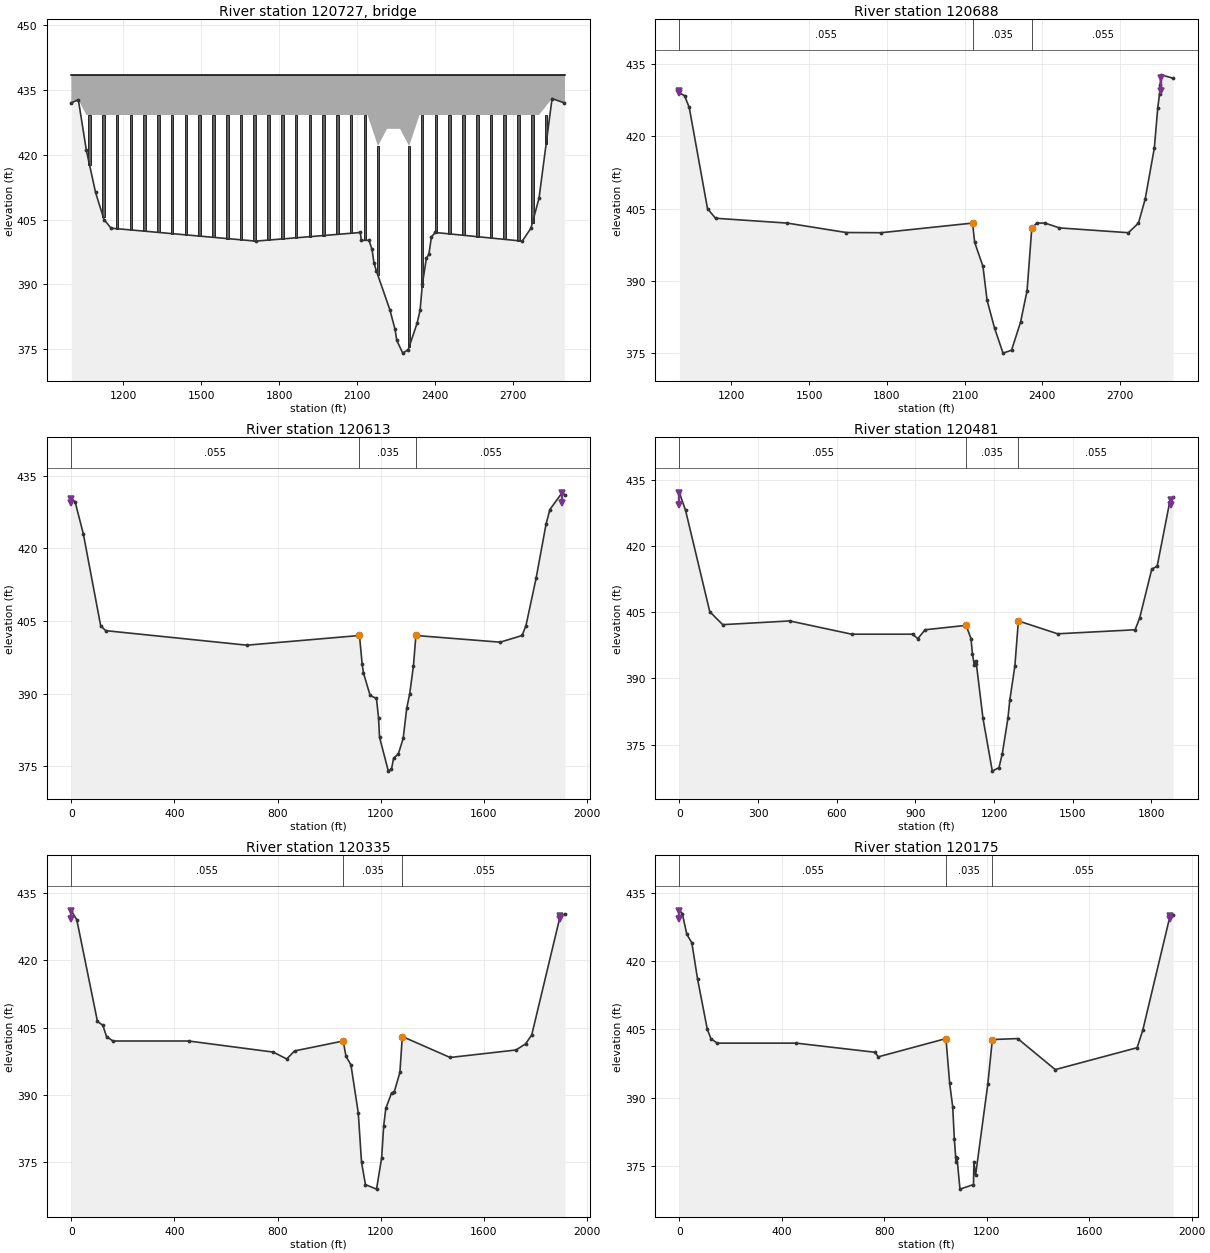
Type RM Length L Ch R = 3 ,120727  ,,,
BEGIN DESCRIPTION:
120729  Commerce Street
END DESCRIPTION:
Node Name=Commerce Street
Bridge Culvert--1,0,-1,-1, 0
Deck Dist Width WeirC Skew NumUp NumDn MinLoCord MaxHiCord MaxSubmerge Is_Ogee
3,68,2.6,0, 8, 8, , , 0.95, 0, ,,,
    1000    2140    2180    2215    2265    2300    2340    2900
   438.5   438.5   438.5   438.5   438.5   438.5   438.5   438.5
   429.2   429.2     422     426     426     422   429.2   429.2
    1000    2140    2180    2215    2265    2300    2340    2900
   438.5   438.5   438.5   438.5   438.5   438.5   438.5   438.5
   429.2   429.2     422     426     426     422   429.2   429.2
Pier Skew, UpSta & Num, DnSta & Num=  ,1070, 5 ,1070, 5 , 3 , 3 , 0 ,,
       5     2.5     3.7     3.7      10
   395.5   425.5   425.5     427   429.5
       5     2.5     3.7     3.7      10
   395.5   425.5   425.5     427   429.5
Pier Skew, UpSta & Num, DnSta & Num=  ,1123, 5 ,1123, 5 , 3 , 3 , 0 ,,
       5     2.5     3.7     3.7      10
   395.5   425.5   425.5     427   429.5
       5     2.5     3.7     3.7      10
   395.5   425.5   425.5     427   429.5
Pier Skew, UpSta & Num, DnSta & Num=  ,1176, 5 ,1176, 5 , 3 , 3 , 0 ,,
       5     2.5     3.7     3.7      10
   395.5   425.5   425.5     427   429.5
       5     2.5     3.7     3.7      10
   395.5   425.5   425.5     427   429.5
Pier Skew, UpSta & Num, DnSta & Num=  ,1229, 5 ,1229, 5 , 3 , 3 , 0 ,,
       5     2.5     3.7     3.7      10
   395.5   425.5   425.5     427   429.5
       5     2.5     3.7     3.7      10
   395.5   425.5   425.5     427   429.5
Pier Skew, UpSta & Num, DnSta & Num=  ,1282, 5 ,1282, 5 , 3 , 3 , 0 ,,
       5     2.5     3.7     3.7      10
   395.5   425.5   425.5     427   429.5
       5     2.5     3.7     3.7      10
   395.5   425.5   425.5     427   429.5
Pier Skew, UpSta & Num, DnSta & Num=  ,1335, 5 ,1335, 5 , 3 , 3 , 0 ,,
       5     2.5     3.7     3.7      10
   395.5   425.5   425.5     427   429.5
       5     2.5     3.7     3.7      10
   395.5   425.5   425.5     427   429.5
Pier Skew, UpSta & Num, DnSta & Num=  ,1388, 5 ,1388, 5 , 3 , 3 , 0 ,,
       5     2.5     3.7     3.7      10
   395.5   425.5   425.5     427   429.5
       5     2.5     3.7     3.7      10
   395.5   425.5   425.5     427   429.5
Pier Skew, UpSta & Num, DnSta & Num=  ,1441, 5 ,1441, 5 , 3 , 3 , 0 ,,
       5     2.5     3.7     3.7      10
   395.5   425.5   425.5     427   429.5
       5     2.5     3.7     3.7      10
   395.5   425.5   425.5     427   429.5
Pier Skew, UpSta & Num, DnSta & Num=  ,1494, 5 ,1494, 5 , 3 , 3 , 0 ,,
       5     2.5     3.7     3.7      10
   395.5   425.5   425.5     427   429.5
       5     2.5     3.7     3.7      10
   395.5   425.5   425.5     427   429.5
Pier Skew, UpSta & Num, DnSta & Num=  ,1547, 5 ,1547, 5 , 3 , 3 , 0 ,,
       5     2.5     3.7     3.7      10
   395.5   425.5   425.5     427   429.5
       5     2.5     3.7     3.7      10
   395.5   425.5   425.5     427   429.5
Pier Skew, UpSta & Num, DnSta & Num=  ,1600, 5 ,1600, 5 , 3 , 3 , 0 ,,
       5     2.5     3.7     3.7      10
   395.5   425.5   425.5     427   429.5
       5     2.5     3.7     3.7      10
   395.5   425.5   425.5     427   429.5
Pier Skew, UpSta & Num, DnSta & Num=  ,1653, 5 ,1653, 5 , 3 , 3 , 0 ,,
       5     2.5     3.7     3.7      10
   395.5   425.5   425.5     427   429.5
       5     2.5     3.7     3.7      10
   395.5   425.5   425.5     427   429.5
Pier Skew, UpSta & Num, DnSta & Num=  ,1706, 5 ,1706, 5 , 3 , 3 , 0 ,,
       5     2.5     3.7     3.7      10
   395.5   425.5   425.5     427   429.5
       5     2.5     3.7     3.7      10
   395.5   425.5   425.5     427   429.5
Pier Skew, UpSta & Num, DnSta & Num=  ,1759, 5 ,1759, 5 , 3 , 3 , 0 ,,
       5     2.5     3.7     3.7      10
   395.5   425.5   425.5     427   429.5
       5     2.5     3.7     3.7      10
   395.5   425.5   425.5     427   429.5
Pier Skew, UpSta & Num, DnSta & Num=  ,1812, 5 ,1812, 5 , 3 , 3 , 0 ,,
       5     2.5     3.7     3.7      10
   395.5   425.5   425.5     427   429.5
       5     2.5     3.7     3.7      10
   395.5   425.5   425.5     427   429.5
Pier Skew, UpSta & Num, DnSta & Num=  ,1865, 5 ,1865, 5 , 3 , 3 , 0 ,,
       5     2.5     3.7     3.7      10
   395.5   425.5   425.5     427   429.5
       5     2.5     3.7     3.7      10
   395.5   425.5   425.5     427   429.5
Pier Skew, UpSta & Num, DnSta & Num=  ,1918, 5 ,1918, 5 , 3 , 3 , 0 ,,
       5     2.5     3.7     3.7      10
   395.5   425.5   425.5     427   429.5
       5     2.5     3.7     3.7      10
   395.5   425.5   425.5     427   429.5
Pier Skew, UpSta & Num, DnSta & Num=  ,1971, 5 ,1971, 5 , 3 , 3 , 0 ,,
       5     2.5     3.7     3.7      10
   395.5   425.5   425.5     427   429.5
       5     2.5     3.7     3.7      10
   395.5   425.5   425.5     427   429.5
Pier Skew, UpSta & Num, DnSta & Num=  ,2024, 5 ,2024, 5 , 3 , 3 , 0 ,,
       5     2.5     3.7     3.7      10
   395.5   425.5   425.5     427   429.5
       5     2.5     3.7     3.7      10
   395.5   425.5   425.5     427   429.5
Pier Skew, UpSta & Num, DnSta & Num=  ,2077, 5 ,2077, 5 , 3 , 3 , 0 ,,
       5     2.5     3.7     3.7      10
   395.5   425.5   425.5     427   429.5
       5     2.5     3.7     3.7      10
   395.5   425.5   425.5     427   429.5
Pier Skew, UpSta & Num, DnSta & Num=  ,2130, 5 ,2130, 5 , 3 , 3 , 0 ,,
       5     2.5     3.7     3.7      10
   395.5   425.5   425.5     427   429.5
       5     2.5     3.7     3.7      10
   395.5   425.5   425.5     427   429.5
Pier Skew, UpSta & Num, DnSta & Num=  ,2180, 6 ,2180, 6 , 5 , 5 , 0 ,,
       8       8       6     3.4       5       5
     370     388     388     419     419     425
       8       8       6     3.4       5       5
     370     388     388     419     419     425
Pier Skew, UpSta & Num, DnSta & Num=  ,2300, 6 ,2300, 6 , 5 , 5 , 0 ,,
       8       8       6     3.4       5       5
     370     388     388     419     419     425
       8       8       6     3.4       5       5
     370     388     388     419     419     425
Pier Skew, UpSta & Num, DnSta & Num=  ,2350, 5 ,2350, 5 , 3 , 3 , 0 ,,
       5     2.5     3.7     3.7      10
   395.5   425.5   425.5     427   429.5
       5     2.5     3.7     3.7      10
   395.5   425.5   425.5     427   429.5
Pier Skew, UpSta & Num, DnSta & Num=  ,2403, 5 ,2403, 5 , 3 , 3 , 0 ,,
       5     2.5     3.7     3.7      10
   395.5   425.5   425.5     427   429.5
       5     2.5     3.7     3.7      10
   395.5   425.5   425.5     427   429.5
Pier Skew, UpSta & Num, DnSta & Num=  ,2456, 5 ,2456, 5 , 3 , 3 , 0 ,,
       5     2.5     3.7     3.7      10
   395.5   425.5   425.5     427   429.5
       5     2.5     3.7     3.7      10
   395.5   425.5   425.5     427   429.5
Pier Skew, UpSta & Num, DnSta & Num=  ,2509, 5 ,2509, 5 , 3 , 3 , 0 ,,
       5     2.5     3.7     3.7      10
   395.5   425.5   425.5     427   429.5
       5     2.5     3.7     3.7      10
   395.5   425.5   425.5     427   429.5
Pier Skew, UpSta & Num, DnSta & Num=  ,2562, 5 ,2562, 5 , 3 , 3 , 0 ,,
       5     2.5     3.7     3.7      10
   395.5   425.5   425.5     427   429.5
       5     2.5     3.7     3.7      10
   395.5   425.5   425.5     427   429.5
Pier Skew, UpSta & Num, DnSta & Num=  ,2615, 5 ,2615, 5 , 3 , 3 , 0 ,,
       5     2.5     3.7     3.7      10
   395.5   425.5   425.5     427   429.5
       5     2.5     3.7     3.7      10
   395.5   425.5   425.5     427   429.5
Pier Skew, UpSta & Num, DnSta & Num=  ,2668, 5 ,2668, 5 , 3 , 3 , 0 ,,
       5     2.5     3.7     3.7      10
   395.5   425.5   425.5     427   429.5
       5     2.5     3.7     3.7      10
   395.5   425.5   425.5     427   429.5
Pier Skew, UpSta & Num, DnSta & Num=  ,2721, 5 ,2721, 5 , 3 , 3 , 0 ,,
       5     2.5     3.7     3.7      10
   395.5   425.5   425.5     427   429.5
       5     2.5     3.7     3.7      10
   395.5   425.5   425.5     427   429.5
Pier Skew, UpSta & Num, DnSta & Num=  ,2774, 5 ,2774, 5 , 3 , 3 , 0 ,,
       5     2.5     3.7     3.7      10
   395.5   425.5   425.5     427   429.5
       5     2.5     3.7     3.7      10
   395.5   425.5   425.5     427   429.5
Pier Skew, UpSta & Num, DnSta & Num=  ,2827, 5 ,2827, 5 , 3 , 3 , 0 ,,
       5     2.5     3.7     3.7      10
   395.5   425.5   425.5     427   429.5
       5     2.5     3.7     3.7      10
   395.5   425.5   425.5     427   429.5
Pier Skew, UpSta & Num, DnSta & Num=  ,2847, 2 ,2847, 2 , 0 , 0 , 0 ,,
     3.5     3.5
       0     430
     3.5     3.5
       0     430
Pier Skew, UpSta & Num, DnSta & Num=  ,2867, 2 ,2867, 2 , 0 , 0 , 0 ,,
     3.5     3.5
       0     430
     3.5     3.5
       0     430
BR Coef= 1 , 1 , 1 ,0.9, 0 ,,,0.8,0,1.33,1,
WSPro=,,,, 1 ,,,, 0 ,,,, 0 ,,,,-1 ,-1 ,-1 , 0 , 0 , 0 , 0 , 0
BC Design=,, 0 ,, 0 ,,,,,,
BC HTab HWMax=430.6
BC Use User HTab Curves=0
BC User HTab FreeFlow(D)= 0

Type RM Length L Ch R = 1 ,120688  ,75,75,75
BEGIN DESCRIPTION:
This cross section corresponds to cross section 120693 of the non-georeferenced CDC model which was the source of this model.
END DESCRIPTION:
XS GIS Cut Line= 3
2485983.205231166969459.677962382484749.045954086969132.97520372
2484140.537984766968978.00733779
#Sta/Elev= 30
    1000     429 1019.79  428.46 1037.81  426.01 1108.32     405 1139.22     403
 1415.63     402 1643.53  400.04 1778.07     400 2130.77     402 2139.03     398
 2171.02     393 2186.78     386 2215.84  380.18 2248.46     375 2281.21   375.6
  2316.2  381.46 2341.22     388 2359.35  400.95 2378.33     402 2410.22     402
 2466.25     401 2732.05     400 2770.98     402 2796.84     407 2832.16  417.59
 2845.43  425.95 2852.28  428.82 2854.06  430.57 2858.47  432.78  2904.6  432.07
#Mann= 3 ,0,0
    1000    .055       0 2130.77    .035       0 2359.35    .055       0
Levee=-1,1000,429.39,-1,2857,429.39,,
#XS Ineff= 2 , 0
       0 2130.77     402 2359.35       0  400.95
Permanent Ineff=
       F       F
Bank Sta=2130.77,2359.35
XS Rating Curve= 0 ,0
Exp/Cntr=0.3,0.1

Type RM Length L Ch R = 1 ,120613  ,133,132,127
BEGIN DESCRIPTION:
This cross section corresponds to cross section 120629 of the non-georeferenced CDC model which was the source of this model.
END DESCRIPTION:
XS GIS Cut Line= 2
2485989.374182086969391.878229222484140.178405436968892.95403022
#Sta/Elev= 30
       0  430.14   14.53   429.6   46.41     423  113.73  404.02  133.02     403
  680.96     400 1117.82     402 1128.18  396.11 1133.32  394.26 1159.14  389.62
  1183.8     389 1191.71     385 1195.62     381 1229.79     374 1241.99   374.4
 1250.09  376.63  1268.8  377.58 1287.47  380.78 1301.12  386.97 1312.81     390
 1327.25  395.78 1336.75     402 1663.85  400.62 1748.67     402 1763.53     404
 1803.15  413.85  1841.7     425 1856.55     428 1903.44  431.45 1915.32     431
#Mann= 3 ,0,0
       0    .055       0 1117.82    .035       0 1336.75    .055       0
Levee=-1,0,429.36,-1,1903,429.36,,
#XS Ineff= 2 , 0
       0 1117.82     402 1336.75       0     402
Permanent Ineff=
       F       F
Bank Sta=1117.82,1336.75
XS Rating Curve= 0 ,0
Exp/Cntr=0.3,0.1

Type RM Length L Ch R = 1 ,120481  ,147,146,140
BEGIN DESCRIPTION:
This cross section corresponds to cross section 120483 of the non-georeferenced CDC model which was the source of this model.
END DESCRIPTION:
XS GIS Cut Line= 2
2486019.86854368 6969260.38078882484199.405321096968779.40373239
#Sta/Elev= 30
       0     432    23.5     428  115.71   405.1  165.07  402.16  420.81     403
  656.72     400  888.94     400  909.06     399  937.11     401 1093.25     402
 1112.08     399 1117.48   395.6 1124.58     393 1129.22     394 1132.78  393.17
 1157.61     381 1193.34     369 1218.72   369.8 1231.39  372.94    1253     381
 1259.87     385 1279.39   392.8 1292.76     403 1442.45  400.09 1737.97     401
 1755.37  403.67 1801.57  414.73 1822.14  415.39 1870.17     430 1882.93     431
#Mann= 3 ,0,0
       0    .055       0 1093.25    .035       0 1292.76    .055       0
Levee=-1,0,429.31,-1,1876,429.31,,
#XS Ineff= 2 , 0
       0 1093.25     402 1292.76       0     403
Permanent Ineff=
       F       F
Bank Sta=1093.25,1292.76
XS Rating Curve= 0 ,0
Exp/Cntr=0.3,0.1

Type RM Length L Ch R = 1 ,120335  ,162,160,154
BEGIN DESCRIPTION:
This cross section corresponds to cross section 120337 of the non-georeferenced CDC model which was the source of this model.
END DESCRIPTION:
XS GIS Cut Line= 2
2486056.52857533 6969118.34563982484202.34232309 6968637.9804588
#Sta/Elev= 30
       0     431   21.19     429  101.28  406.36  122.24   405.5  136.38     403
  161.48     402  454.85     402  783.17  399.53  835.63     398  866.07  399.79
 1054.81     402 1065.54  398.57 1084.72   396.7 1113.16     386  1125.8     375
 1141.06     370 1184.07     369 1203.95     376 1211.87  383.15 1220.07     387
 1242.19  390.39 1252.99   390.7 1274.66     395 1284.03     403 1469.49  398.33
 1725.12     400 1762.22  401.36  1786.2  403.36 1897.26     430  1915.4  430.23
#Mann= 3 ,0,0
       0    .055       0 1054.81    .035       0 1284.03    .055       0
Levee=-1,0,429.25,-1,1897,429.25,,
#XS Ineff= 2 , 0
       0 1054.81     402 1284.03       0     403
Permanent Ineff=
       F       F
Bank Sta=1054.81,1284.03
XS Rating Curve= 0 ,0
Exp/Cntr=0.3,0.1

Type RM Length L Ch R = 1 ,120175  ,164,158,152
BEGIN DESCRIPTION:
This cross section corresponds to cross section 120192 of the non-georeferenced CDC model which was the source of this model.
END DESCRIPTION:
XS GIS Cut Line= 2
2486093.731256846968963.693718142484225.652972016968489.22977205
#Sta/Elev= 30
       0     431   11.18  430.41   28.86  425.85    48.4     424   70.93     416
  108.63   405.1  122.78     403  147.32     402  456.25     402  763.22     400
  776.39     399 1040.55     403    1055  393.21 1066.97     388 1073.23     381
 1079.95     376 1080.59     377 1083.83  376.73 1095.25     370 1147.96     371
 1149.64     376 1156.06     373 1203.93     393 1221.62  402.79  1320.5     403
 1467.32   396.2 1786.84     401 1808.85  404.82 1915.85     430 1927.39     430
#Mann= 3 ,0,0
       0    .055       0 1040.55    .035       0 1221.62    .055       0
Levee=-1,0,429.2,-1,1915,429.2,,
#XS Ineff= 2 , 0
       0 1040.55     403 1221.62       0  402.79
Permanent Ineff=
       F       F
Bank Sta=1040.55,1221.62
XS Rating Curve= 0 ,0
Exp/Cntr=0.3,0.1

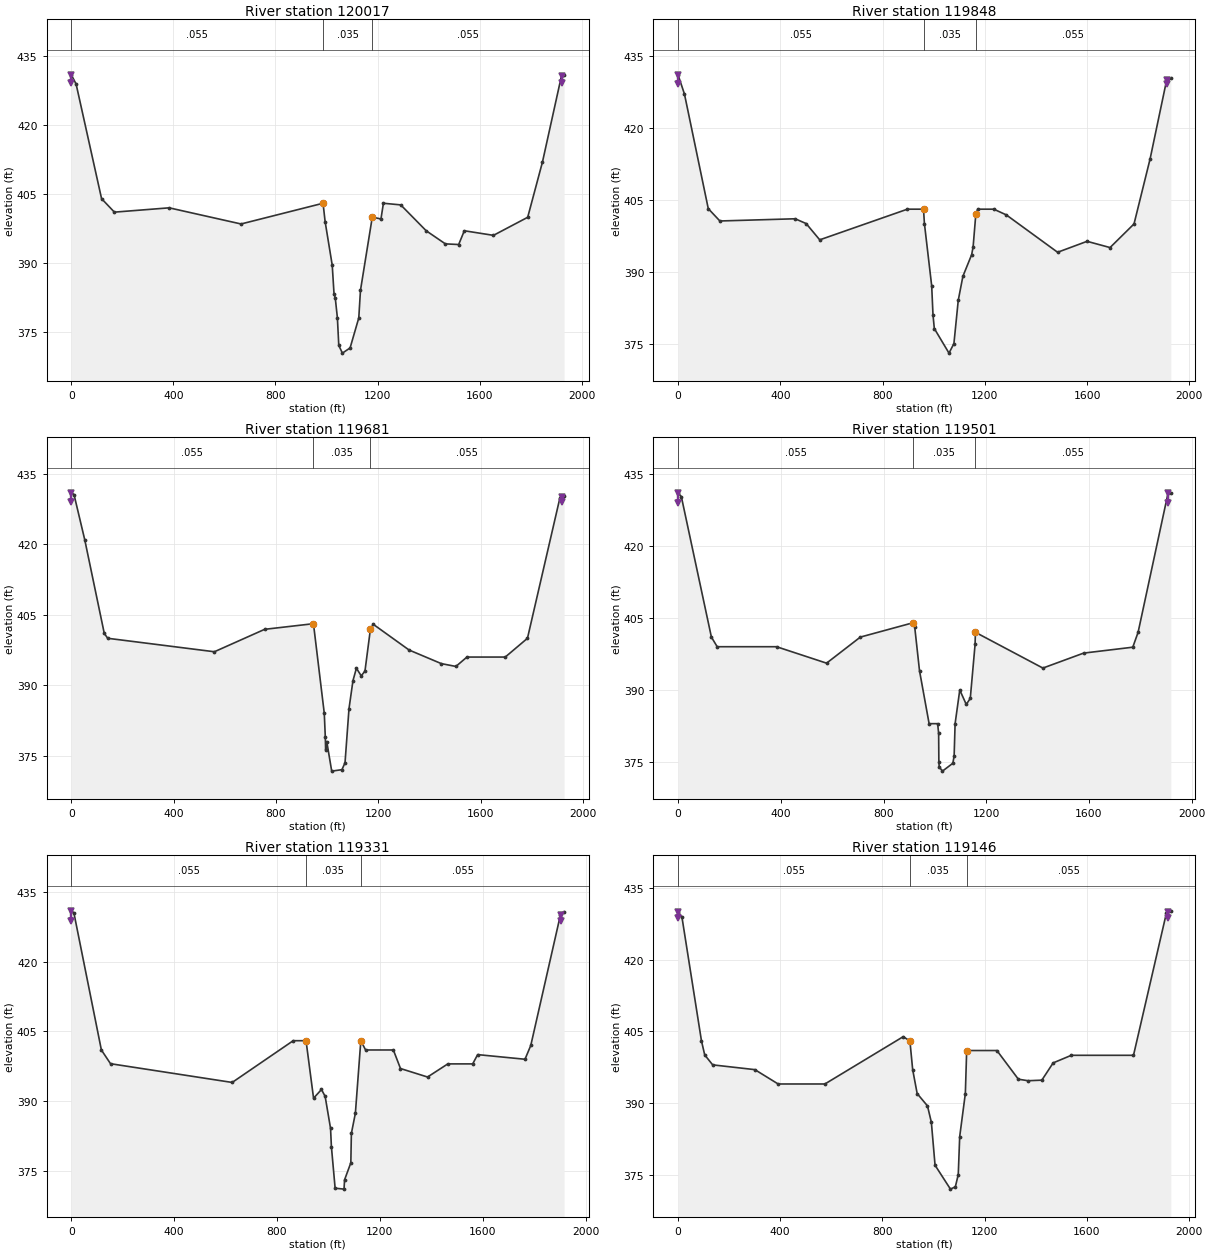
Type RM Length L Ch R = 1 ,120017  ,176,169,164
BEGIN DESCRIPTION:
This cross section corresponds to cross section 120023 of the non-georeferenced CDC model which was the source of this model.
END DESCRIPTION:
XS GIS Cut Line= 2
2486124.209870436968801.863661212484248.318937186968344.54928714
#Sta/Elev= 30
       0     431   18.77     429   118.6     404  168.81  401.06   383.5     402
  665.14  398.48  986.47     403  994.56     399 1022.42   389.5 1029.46  383.24
 1034.36  382.32 1042.68     378 1048.08     372 1062.28  370.32  1092.4  371.45
 1126.46     378 1133.08     384 1179.43     400 1213.32  399.56 1222.98     403
 1290.88  402.64 1390.61     397 1465.81  394.14 1517.89     394 1540.02     397
 1654.18     396 1788.38  399.94 1846.25     412 1921.56  430.98 1930.83     431
#Mann= 3 ,0,0
       0    .055       0  986.47    .035       0 1179.43    .055       0
Levee=-1,0,429.13,-1,1921,429.13,,
#XS Ineff= 2 , 0
       0  986.47     403 1179.43       0     400
Permanent Ineff=
       F       F
Bank Sta=986.47,1179.43
XS Rating Curve= 0 ,0
Exp/Cntr=0.3,0.1

Type RM Length L Ch R = 1 ,119848  ,172,167,160
BEGIN DESCRIPTION:
This cross section corresponds to cross section 119855 of the non-georeferenced CDC model which was the source of this model.
END DESCRIPTION:
XS GIS Cut Line= 2
 2486173.58444366968632.007701712484296.600008586968193.53088838
#Sta/Elev= 30
       0     431   24.99     427  118.19  403.11   163.6  400.54  458.09     401
  501.11     400  554.18  396.61  897.12     403  960.13     403  963.67     400
  992.17     387  997.19     381 1002.39  378.13 1059.81     373  1079.1     375
 1096.02     384 1114.15     389 1148.41  393.51 1154.19  395.15 1164.68  401.92
  1172.1     403 1235.19     403 1283.96  401.81 1484.68  394.02 1599.93   396.3
 1689.79     395 1783.63  399.93 1846.52  413.49  1911.6     430 1927.52  430.26
#Mann= 3 ,0,0
       0    .055       0  960.13    .035       0 1164.68    .055       0
Levee=-1,0,429.07,-1,1911,429.07,,
#XS Ineff= 2 , 0
       0  960.13     403 1164.68       0  401.92
Permanent Ineff=
       F       F
Bank Sta=960.13,1164.68
XS Rating Curve= 0 ,0
Exp/Cntr=0.3,0.1

Type RM Length L Ch R = 1 ,119681  ,188,180,174
BEGIN DESCRIPTION:
This cross section corresponds to cross section 119686 of the non-georeferenced CDC model which was the source of this model.
END DESCRIPTION:
XS GIS Cut Line= 2
2486222.250356766968461.946362052484343.134692436968042.82088797
#Sta/Elev= 30
       0     431   10.57  430.63   52.51     421  128.89  401.03  142.29     400
     559  397.13  755.47  401.91  946.14  403.11  988.45     384  992.44   378.9
  993.74  376.19   998.1     378 1017.45  371.69 1057.41     372 1069.48  373.47
 1084.98  384.99 1100.52  390.97 1113.93  393.62 1132.73     392 1147.37     393
  1168.8     402 1180.12  402.97 1319.78   397.5 1445.89   394.6  1502.7     394
 1545.81     396 1695.57     396  1782.3     400 1909.41     430 1925.29  430.43
#Mann= 3 ,0,0
       0    .055       0  946.14    .035       0  1168.8    .055       0
Levee=-1,0,429,-1,1917,429,,
#XS Ineff= 2 , 0
       0  946.14  403.11  1168.8       0     402
Permanent Ineff=
       F       F
Bank Sta=946.14,1168.8
XS Rating Curve= 0 ,0
Exp/Cntr=0.3,0.1

Type RM Length L Ch R = 1 ,119501  ,166,170,176
BEGIN DESCRIPTION:
This cross section corresponds to cross section 119518 of the non-georeferenced CDC model which was the source of this model.
END DESCRIPTION:
XS GIS Cut Line= 2
2486271.157083096968278.820744052484394.622778426967879.26576889
#Sta/Elev= 30
       0     431   12.82   430.2  129.83     401  152.35     399  383.47     399
  578.26  395.58  709.66     401  916.11     404  921.65     403  940.13     394
   977.5     383  1010.7     383 1014.59     381 1015.48     375 1016.85     374
 1029.46  373.13 1069.96  374.77 1074.95   376.3 1078.69     383 1096.86     390
 1122.16     387 1137.79  388.26 1156.53   399.5 1157.73     402 1420.52  394.56
 1579.02  397.67 1770.52   398.9 1791.23     402 1908.09     431  1918.6     431
#Mann= 3 ,0,0
       0    .055       0  916.11    .035       0 1157.73    .055       0
Levee=-1,0,428.94,-1,1908,428.94,,
#XS Ineff= 2 , 0
       0  916.11     404 1157.73       0     402
Permanent Ineff=
       F       F
Bank Sta=916.11,1157.73
XS Rating Curve= 0 ,0
Exp/Cntr=0.3,0.1

Type RM Length L Ch R = 1 ,119331  ,181,185,191
BEGIN DESCRIPTION:
This cross section corresponds to cross section 119334 of the non-georeferenced CDC model which was the source of this model.
END DESCRIPTION:
XS GIS Cut Line= 2
2486310.874195256968123.94835038  2484440.1052996967708.10305347
#Sta/Elev= 30
       0     431   10.29  430.49  116.97     401  152.55  398.04  625.72     394
  863.05     403  912.93     403  942.19   390.6  972.96  392.48  987.22     391
 1008.22  384.11 1011.59  380.15 1026.07   371.2 1060.69     371 1062.74     373
 1087.16  376.68 1089.25     383 1104.81  387.35    1126     403 1144.53     401
 1252.53     401 1280.27     397 1385.51  395.17 1464.32     398 1561.12     398
 1580.36     400 1764.49     399 1786.98  401.97 1901.88     430 1916.43  430.79
#Mann= 3 ,0,0
       0    .055       0  912.93    .035       0    1126    .055       0
Levee=-1,0,428.88,-1,1903,428.88,,
#XS Ineff= 2 , 0
       0  912.93     403    1126       0     403
Permanent Ineff=
       F       F
Bank Sta=912.93,1126
XS Rating Curve= 0 ,0
Exp/Cntr=0.3,0.1

Type RM Length L Ch R = 1 ,119146  ,180,184,190
BEGIN DESCRIPTION:
This cross section corresponds to cross section 119150 of the non-georeferenced CDC model which was the source of this model.
END DESCRIPTION:
XS GIS Cut Line= 2
2486378.220517256967962.264290562484498.580575766967526.63983372
#Sta/Elev= 30
       0     430   14.95     429    91.7     403   104.4  400.08  135.54     398
  300.83     397  391.89     394  575.03     394  881.66   403.9  907.82     403
  918.69     397  936.23     392  976.64  389.41  991.79     386  1006.3     377
 1066.58     372 1085.79  372.49 1097.19  375.05  1102.8     383 1124.92     392
 1130.13     401  1248.5     401  1332.5     395  1370.6  394.68 1424.41   394.8
 1468.74  398.41 1539.85     400 1783.33     400 1912.52  429.83 1929.46  430.23
#Mann= 3 ,0,0
       0    .055       0  907.82    .035       0 1130.13    .055       0
Levee=-1,0,428.82,-1,1920,428.82,,
#XS Ineff= 2 , 0
       0  907.82     403 1130.13       0     401
Permanent Ineff=
       F       F
Bank Sta=907.82,1130.13
XS Rating Curve= 0 ,0
Exp/Cntr=0.3,0.1

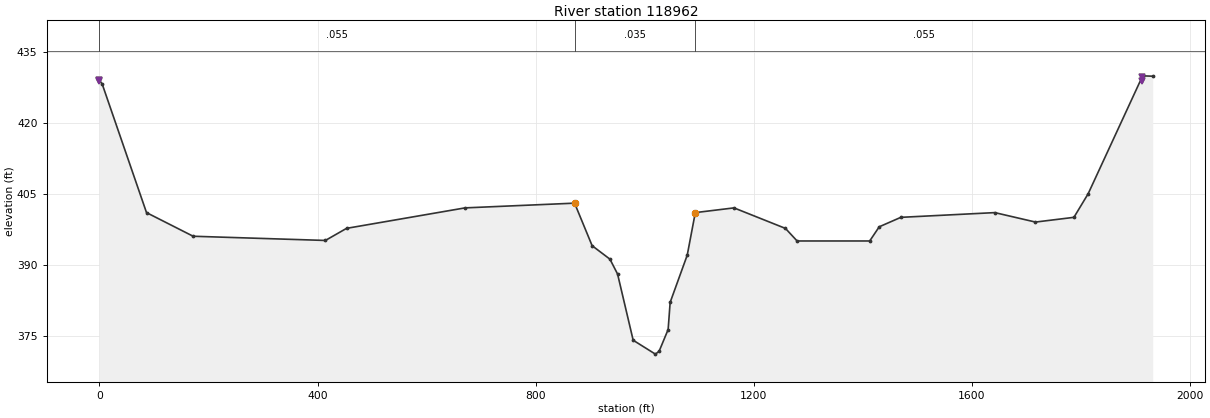
Type RM Length L Ch R = 1 ,118962  ,192,196,203
BEGIN DESCRIPTION:
This cross section corresponds to cross section 118966 of the non-georeferenced CDC model which was the source of this model.
END DESCRIPTION:
XS GIS Cut Line= 2
2486430.278484026967797.283321312484552.779614336967344.30686505
#Sta/Elev= 30
       0     429    5.13  428.24   86.49     401  172.01     396  414.46  395.11
  453.27  397.67  670.45     402  871.35     403  903.51     394  936.19  391.15
  950.17     388  978.76     374 1019.48  371.06 1026.31  371.66 1042.87  376.27
 1046.55     382 1077.88     392 1092.67     401  1163.6     402 1257.94  397.66
 1279.32     395 1412.44     395 1429.89     398 1469.53     400 1641.83     401
  1716.4     399 1786.84     400    1813     405 1912.86  429.94 1931.37  429.86
#Mann= 3 ,0,0
       0    .055       0  871.35    .035       0 1092.67    .055       0
Levee=-1,0,428.76,-1,1912,428.76,,
#XS Ineff= 2 , 0
       0  871.35     403 1092.67       0     401
Permanent Ineff=
       F       F
Bank Sta=871.35,1092.67
XS Rating Curve= 0 ,0
Exp/Cntr=0.3,0.1