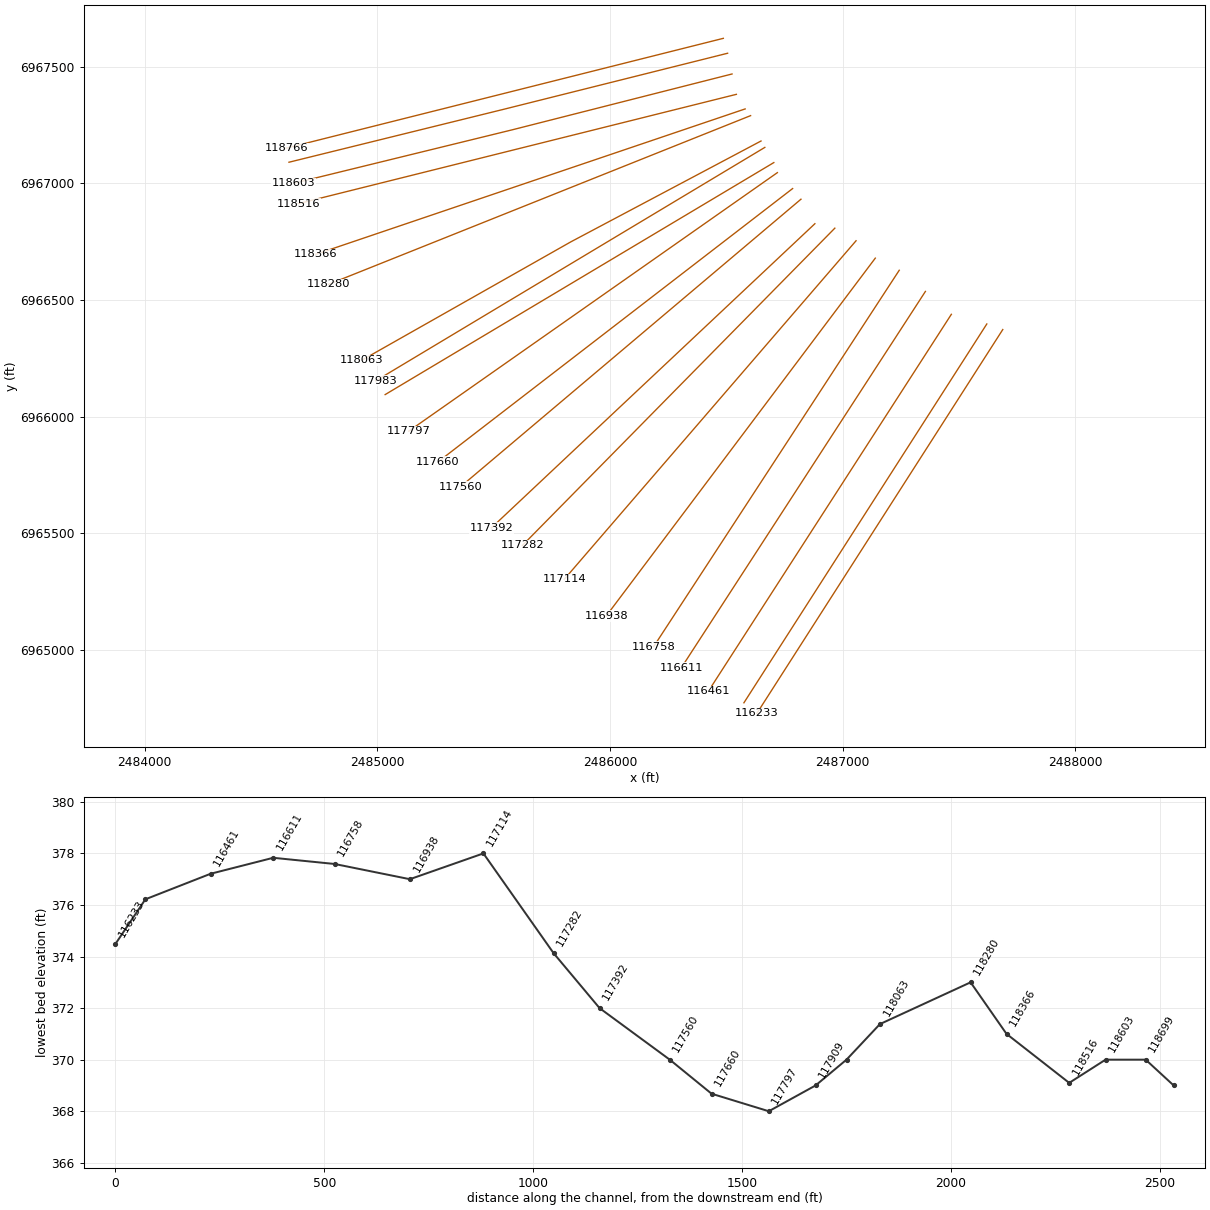
HEC-RAS study CDC_Consolidated_Model.prj: Upper Trinity CDC Consolidated Model

--- CDC_Consolidated_Model.g02 (geometry) --- (continued)

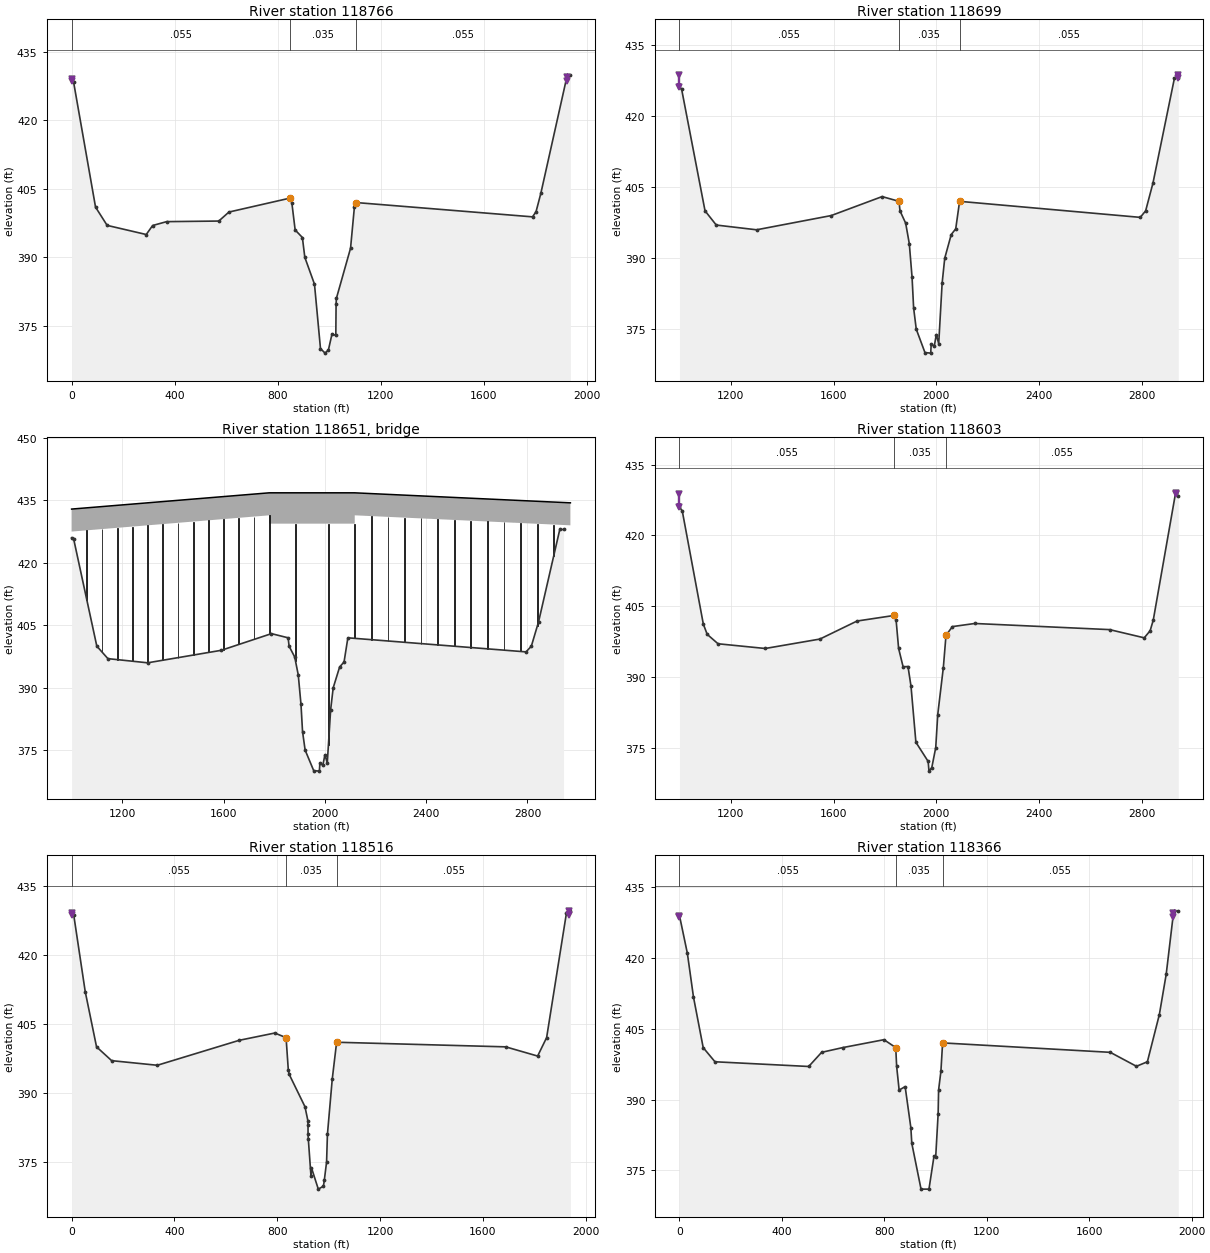
Type RM Length L Ch R = 1 ,118766  ,67,67,67
BEGIN DESCRIPTION:
This cross section corresponds to cross section 118782 of the non-georeferenced CDC model which was the source of this model.
END DESCRIPTION:
XS GIS Cut Line= 2
2486486.841691086967620.720682292484607.959293996967150.00082321
#Sta/Elev= 30
       0     429    7.97  428.33   92.96     401  137.99     397   289.8     395
  314.63  396.97     369  397.82  571.56  397.95  610.94  399.92  849.71     403
  855.15     402  868.09     396  896.21  394.34  905.64     390  943.18  384.11
  966.46     370  984.23     369  997.24  369.68  1011.3  373.21 1026.03  372.87
 1027.09  379.76 1028.26     381 1083.27     392 1098.15     401 1105.76     402
 1789.86  398.87 1803.59     400 1822.12     404 1925.09     430 1936.95     430
#Mann= 3 ,0,0
       0    .055       0  849.71    .035       0 1105.76    .055       0
Levee=-1,0,428.7,-1,1923,428.7,,
#XS Ineff= 2 , 0
       0  849.71     403 1105.76       0     402
Permanent Ineff=
       F       F
Bank Sta=849.71,1105.76
XS Rating Curve= 0 ,0
Exp/Cntr=0.3,0.1

Type RM Length L Ch R = 1 ,118699  ,96,96,96
BEGIN DESCRIPTION:
This cross section corresponds to cross section 118703 of the non-georeferenced CDC model which was the source of this model.
END DESCRIPTION:
XS GIS Cut Line= 3
2486505.268163416967556.82415655 2485541.73728216967316.33808896
2484619.903495856967089.75816154
#Sta/Elev= 30
    1000     426 1008.54   425.6 1099.55     400 1143.31     397 1300.31     396
  1590.9     399 1789.14     403 1855.04     402 1858.71     400 1880.92  397.39
 1895.01  393.08 1905.76     386 1911.86  379.51 1922.09  375.05 1955.96  370.12
  1978.4     370  1980.3  371.91 1992.21  371.44 2000.14   373.9 2009.57     372
 2022.88  384.76 2032.98     390 2058.33     395 2075.81   396.2 2090.86     402
 2794.45  398.62 2815.41     400 2843.94  405.86 2927.65     428 2942.36     428
#Mann= 3 ,0,0
    1000    .055       0 1855.04    .035       0 2090.86    .055       0
Levee=-1,1000,428.67,-1,2942,428.67,,
#XS Ineff= 2 , 0
       0 1855.04     402 2090.86       0     402
Permanent Ineff=
       F       F
Bank Sta=1855.04,2090.86
XS Rating Curve= 0 ,0
Exp/Cntr=0.3,0.1

Type RM Length L Ch R = 3 ,118651  ,,,
BEGIN DESCRIPTION:
118657  IH 30
END DESCRIPTION:
Node Name=IH 30
Bridge Culvert--1,0,-1,-1, 0
Deck Dist Width WeirC Skew NumUp NumDn MinLoCord MaxHiCord MaxSubmerge Is_Ogee
4,88,2.6,0, 6, 6, , , 0.95, 0, ,,,
    1000    1780    1780    2118    2118  2969.5
   432.9   436.8   436.8   436.8   436.8   434.4
   427.5   431.4   429.4   429.4   431.4     429
    1000    1780    1780    2118    2118  2969.5
   432.9   436.8   436.8   436.8   436.8   434.4
   427.5   431.4   429.4   429.4   431.4     429
Pier Skew, UpSta & Num, DnSta & Num=  ,1060, 2 ,1060, 2 , 0 , 0 , 0 ,,
       3       3
     380   431.5
       3       3
     380   431.5
Pier Skew, UpSta & Num, DnSta & Num=  ,1120, 2 ,1120, 2 , 0 , 0 , 0 ,,
       3       3
       0     432
       3       3
       0     432
Pier Skew, UpSta & Num, DnSta & Num=  ,1180, 2 ,1180, 2 , 0 , 0 , 0 ,,
       3       3
       0   431.5
       3       3
       0   431.5
Pier Skew, UpSta & Num, DnSta & Num=  ,1240, 2 ,1240, 2 , 0 , 0 , 0 ,,
       3       3
       0   431.5
       3       3
       0   431.5
Pier Skew, UpSta & Num, DnSta & Num=  ,1300, 2 ,1300, 2 , 0 , 0 , 0 ,,
       3       3
       0   431.5
       3       3
       0   431.5
Pier Skew, UpSta & Num, DnSta & Num=  ,1360, 2 ,1360, 2 , 0 , 0 , 0 ,,
       3       3
       0   431.5
       3       3
       0   431.5
Pier Skew, UpSta & Num, DnSta & Num=  ,1420, 2 ,1420, 2 , 0 , 0 , 0 ,,
       3       3
       0   431.5
       3       3
       0   431.5
Pier Skew, UpSta & Num, DnSta & Num=  ,1480, 2 ,1480, 2 , 0 , 0 , 0 ,,
       3       3
       0   431.5
       3       3
       0   431.5
Pier Skew, UpSta & Num, DnSta & Num=  ,1540, 2 ,1540, 2 , 0 , 0 , 0 ,,
       3       3
       0   431.5
       3       3
       0   431.5
Pier Skew, UpSta & Num, DnSta & Num=  ,1600, 2 ,1600, 2 , 0 , 0 , 0 ,,
       3       3
       0   431.5
       3       3
       0   431.5
Pier Skew, UpSta & Num, DnSta & Num=  ,1660, 2 ,1660, 2 , 0 , 0 , 0 ,,
       3       3
       0   431.5
       3       3
       0   431.5
Pier Skew, UpSta & Num, DnSta & Num=  ,1720, 2 ,1720, 2 , 0 , 0 , 0 ,,
       3       3
       0   431.5
       3       3
       0   431.5
Pier Skew, UpSta & Num, DnSta & Num=  ,1780, 2 ,1780, 2 , 0 , 0 , 0 ,,
       3       3
       0   431.5
       3       3
       0   431.5
Pier Skew, UpSta & Num, DnSta & Num=  ,1884, 2 ,1884, 2 , 0 , 0 , 0 ,,
       4       4
       0   431.5
       4       4
       0   431.5
Pier Skew, UpSta & Num, DnSta & Num=  ,2014, 2 ,2014, 2 , 0 , 0 , 0 ,,
       4       4
       0   431.5
       4       4
       0   431.5
Pier Skew, UpSta & Num, DnSta & Num=  ,2118, 2 ,2118, 2 , 0 , 0 , 0 ,,
       3       3
       0   431.5
       3       3
       0   431.5
Pier Skew, UpSta & Num, DnSta & Num=  ,2183.5, 2 ,2183.5, 2 , 0 , 0 , 0 ,,
       3       3
       0   431.5
       3       3
       0   431.5
Pier Skew, UpSta & Num, DnSta & Num=  ,2249, 2 ,2249, 2 , 0 , 0 , 0 ,,
       3       3
       0   431.5
       3       3
       0   431.5
Pier Skew, UpSta & Num, DnSta & Num=  ,2314.5, 2 ,2314.5, 2 , 0 , 0 , 0 ,,
       3       3
       0   431.5
       3       3
       0   431.5
Pier Skew, UpSta & Num, DnSta & Num=  ,2380, 2 ,2380, 2 , 0 , 0 , 0 ,,
       3       3
       0   431.5
       3       3
       0   431.5
Pier Skew, UpSta & Num, DnSta & Num=  ,2445.5, 2 ,2445.5, 2 , 0 , 0 , 0 ,,
       3       3
       0   431.5
       3       3
       0   431.5
Pier Skew, UpSta & Num, DnSta & Num=  ,2511, 2 ,2511, 2 , 0 , 0 , 0 ,,
       3       3
       0   431.5
       3       3
       0   431.5
Pier Skew, UpSta & Num, DnSta & Num=  ,2576.5, 2 ,2576.5, 2 , 0 , 0 , 0 ,,
       3       3
       0   431.5
       3       3
       0   431.5
Pier Skew, UpSta & Num, DnSta & Num=  ,2642, 2 ,2642, 2 , 0 , 0 , 0 ,,
       3       3
       0   431.5
       3       3
       0   431.5
Pier Skew, UpSta & Num, DnSta & Num=  ,2707.5, 2 ,2707.5, 2 , 0 , 0 , 0 ,,
       3       3
       0   431.5
       3       3
       0   431.5
Pier Skew, UpSta & Num, DnSta & Num=  ,2773, 2 ,2773, 2 , 0 , 0 , 0 ,,
       3       3
       0   431.5
       3       3
       0   431.5
Pier Skew, UpSta & Num, DnSta & Num=  ,2838.5, 2 ,2838.5, 2 , 0 , 0 , 0 ,,
       3       3
       0   431.5
       3       3
       0   431.5
Pier Skew, UpSta & Num, DnSta & Num=  ,2904, 2 ,2904, 2 , 0 , 0 , 0 ,,
       3       3
       0   431.5
       3       3
       0   431.5
BR Coef= 1 , 1 , 1 ,1.05, 0 ,,,0.8,-1,1.2,1,
WSPro=,,,, 1 ,,,, 0 ,,,, 0 ,,,,-1 ,-1 ,-1 , 0 , 0 , 0 , 0 , 0
BC Design=,, 0 ,, 0 ,,,,,,
BC HTab HWMax=431
BC Use User HTab Curves=0
BC User HTab FreeFlow(D)= 0

Type RM Length L Ch R = 1 ,118603  ,87,87,87
BEGIN DESCRIPTION:
This cross section corresponds to cross section 118611 of the non-georeferenced CDC model which was the source of this model.
END DESCRIPTION:
XS GIS Cut Line= 3
2486524.275999436967467.967706962485581.777228276967229.20867005
2484640.08422977 6966999.3538148
#Sta/Elev= 30
    1000     426 1010.89  425.16  1092.9  401.17  1107.9     399 1150.16     397
 1333.92     396 1546.73     398 1691.27  401.82 1835.14     403 1843.32     402
 1853.07  396.01  1870.5  392.13 1889.64  392.17 1901.31     388 1920.37  376.12
  1968.1  372.05 1971.25     370 1982.26  370.76 1997.59     375 2005.39     382
  2027.2  391.96 2037.53  398.79 2062.46  400.64 2149.59   401.3 2674.44     400
 2809.19  398.26 2832.16  399.76 2844.29     402 2931.32     429 2941.61  428.37
#Mann= 3 ,0,0
    1000    .055       0 1835.14    .035       0 2037.53    .055       0
Levee=-1,1000,428.65,-1,2931,428.65,,
#XS Ineff= 2 , 0
       0 1835.14     403 2037.53       0  398.79
Permanent Ineff=
       F       F
Bank Sta=1835.14,2037.53
XS Rating Curve= 0 ,0
Exp/Cntr=0.3,0.1

Type RM Length L Ch R = 1 ,118516  ,136,150,196
BEGIN DESCRIPTION:
This cross section corresponds to cross section 118533 of the non-georeferenced CDC model which was the source of this model.
END DESCRIPTION:
XS GIS Cut Line= 2
2486542.889479256967380.72378697 2484660.11076456966912.27656113
#Sta/Elev= 30
       0     429    8.37  428.61   52.96     412   96.99     400  155.78     397
  333.45     396  651.98  401.42  790.28     403  834.24     402  842.91     395
  845.99  394.07  907.74     387  918.92     384  919.54   383.1  919.74     381
  920.74     380  931.08     372  932.79  373.77  959.61   369.1  979.62  369.75
  982.94     371  991.83     375  995.11     381 1013.87     393 1030.88     401
 1688.51     400 1812.74     398 1847.73     402  1924.7     429 1940.18  429.54
#Mann= 3 ,0,0
       0    .055       0  834.24    .035       0 1030.88    .055       0
Levee=-1,0,428.63,-1,1936,428.63,,
#XS Ineff= 2 , 0
       0  834.24     402 1030.88       0     401
Permanent Ineff=
       F       F
Bank Sta=834.24,1030.88
XS Rating Curve= 0 ,0
Exp/Cntr=0.3,0.1

Type RM Length L Ch R = 1 ,118366  ,64,86,116
BEGIN DESCRIPTION:
This cross section corresponds to cross section 118381 of the non-georeferenced CDC model which was the source of this model.
END DESCRIPTION:
XS GIS Cut Line= 2
2486580.577067916967318.21406947 2484735.38259566966695.15297963
#Sta/Elev= 30
       0     429   30.83     421   54.73  411.72   92.64     401  138.64     398
  504.62     397  555.07     400  637.14     401  798.45  402.68  844.47  401.01
  848.04     397  857.72     392  881.19  392.73  903.53     384  907.09  380.73
  943.24     371  974.22     371  993.91     378 1000.45  377.77 1010.02  386.98
  1011.8     392 1020.85     396 1027.41     402  1682.2     400 1784.33  397.04
 1827.01     398 1873.69  407.99 1900.52  416.55 1929.91     430 1947.55     430
#Mann= 3 ,0,0
       0    .055       0  844.47    .035       0 1027.41    .055       0
Levee=-1,0,428.6,-1,1929,428.6,,
#XS Ineff= 2 , 0
       0  844.47  401.01 1027.41       0     402
Permanent Ineff=
       F       F
Bank Sta=844.47,1027.41
XS Rating Curve= 0 ,0
Exp/Cntr=0.3,0.1

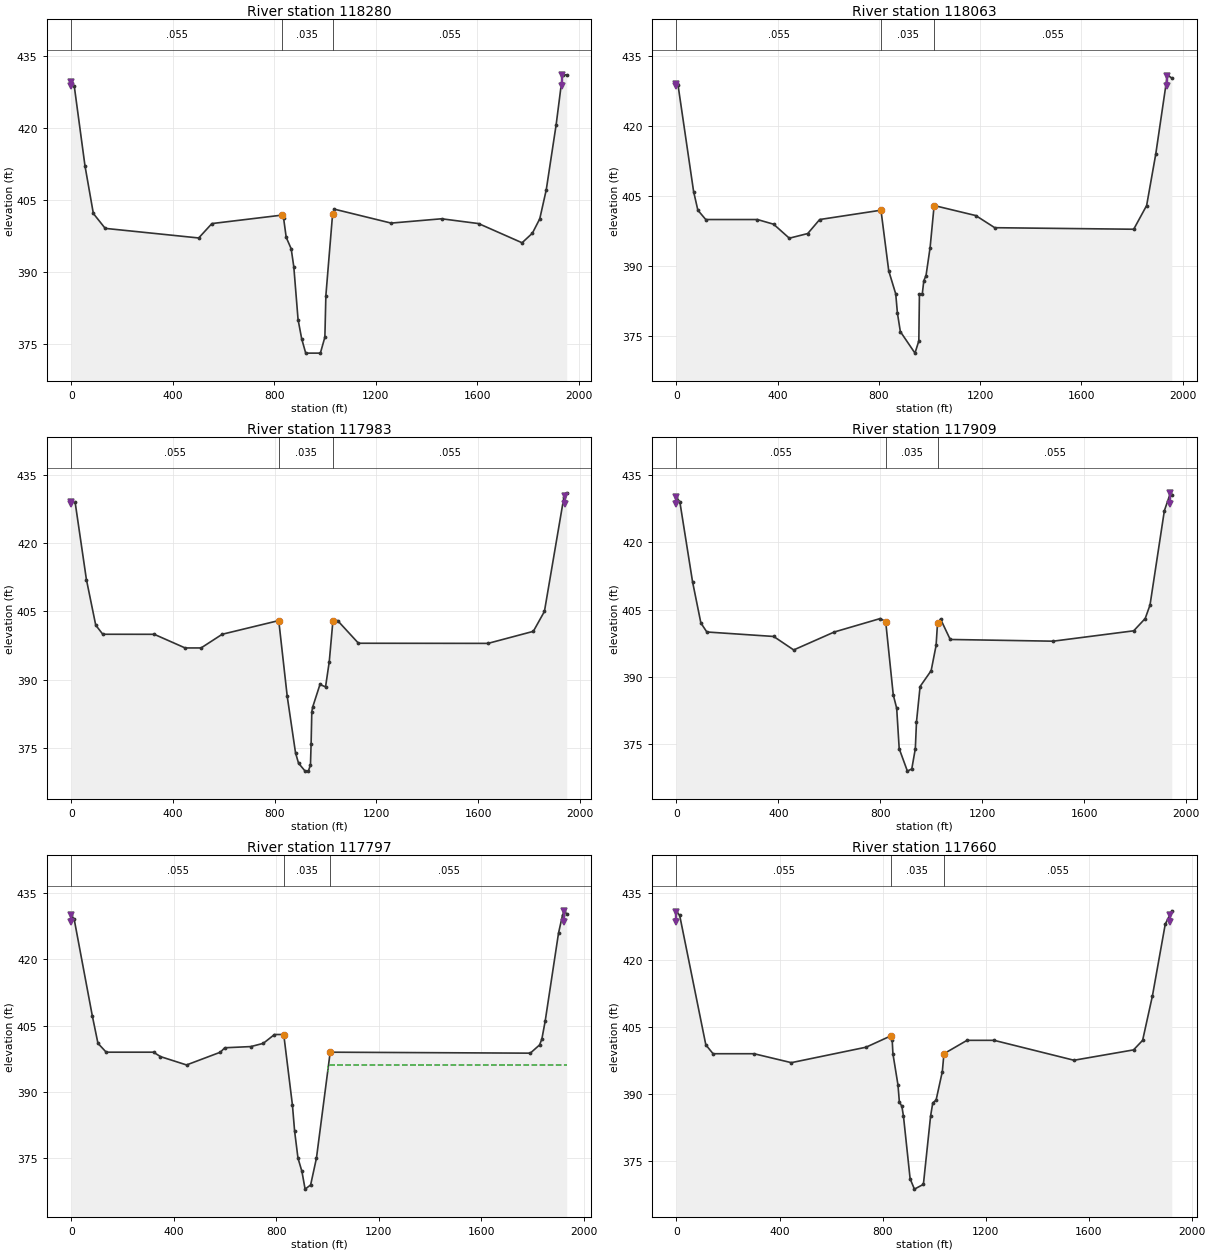
Type RM Length L Ch R = 1 ,118280  ,167,217,255
BEGIN DESCRIPTION:
This cross section corresponds to cross section 118283 of the non-georeferenced CDC model which was the source of this model.
END DESCRIPTION:
XS GIS Cut Line= 2
2486604.002546016967289.436567962484790.028811756966566.40750222
#Sta/Elev= 30
       0  429.52   11.08  428.69   53.53     412   86.46   402.1  133.16     399
  501.81     397  553.82     400  831.22  401.77  836.32  401.21  846.82  397.13
  866.44  394.75  876.75     391  893.55     380   907.8     376  923.74     373
  981.52     373   999.3  376.34 1003.21     385 1029.59  401.91 1036.86     403
 1260.55   400.1 1459.32     401 1605.26     400 1776.79     396 1817.49     398
 1846.55     401    1872     407 1911.08  420.58 1936.22     431 1952.76     431
#Mann= 3 ,0,0
       0    .055       0  831.22    .035       0 1029.59    .055       0
Levee=-1,0,428.58,-1,1936,428.58,,
#XS Ineff= 2 , 0
       0  831.22  401.77 1029.59       0  401.91
Permanent Ineff=
       F       F
Bank Sta=831.22,1029.59
XS Rating Curve= 0 ,0
Exp/Cntr=0.3,0.1

Type RM Length L Ch R = 1 ,118063  ,56,80,99
BEGIN DESCRIPTION:
This cross section corresponds to cross section 118075 of the non-georeferenced CDC model which was the source of this model.
END DESCRIPTION:
XS GIS Cut Line= 3
2486648.866629516967180.767165882485830.942740416966748.30083922
2484932.639746996966240.97376989
#Sta/Elev= 30
       0     429    6.11   428.8   67.63     406   84.43     402  115.66     400
  319.64     400  383.65     399  445.79     396  518.56     397  565.67     400
  807.94     402  838.63     389  866.28  384.06  872.83     380  884.43     376
  942.28  371.38  957.48     374  959.88     384  971.04     384  977.19  386.89
  985.95     388 1002.06     394 1017.97     403 1182.54  400.85 1257.47  398.25
 1806.53  397.92 1857.58     403 1893.57     414 1939.64     431 1956.88  430.29
#Mann= 3 ,0,0
       0    .055       0  807.94    .035       0 1017.97    .055       0
Levee=-1,0,428.53,-1,1939,428.53,,
#XS Ineff= 2 , 0
       0  807.94     402 1017.97       0     403
Permanent Ineff=
       F       F
Bank Sta=807.94,1017.97
XS Rating Curve= 0 ,0
Exp/Cntr=0.3,0.1

Type RM Length L Ch R = 1 ,117983  ,62,74,83
BEGIN DESCRIPTION:
This cross section corresponds to cross section 118000 of the non-georeferenced CDC model which was the source of this model.
END DESCRIPTION:
XS GIS Cut Line= 2
2486665.166465676967153.278047642484992.99658167 6966152.9893658
#Sta/Elev= 30
       0     429    14.4     429   58.92     412   95.61     402  123.35     400
  325.76  399.99  447.34     397  509.99     397  593.24     400  815.63     403
  849.05  386.36  881.68     374   893.5  371.74  919.47     370  932.09     370
   940.4  371.36  942.94     376  945.71     383  948.89     384  977.83     389
  999.74  388.46 1014.39     394 1028.83     403 1047.19     403 1129.27  398.03
 1638.91     398  1817.2  400.64 1860.83     405 1937.31     430 1948.52     431
#Mann= 3 ,0,0
       0    .055       0  815.63    .035       0 1028.83    .055       0
Levee=-1,0,428.51,-1,1941,428.51,,
#XS Ineff= 2 , 0
       0  815.63     403 1028.83       0     403
Permanent Ineff=
       F       F
Bank Sta=815.63,1028.83
XS Rating Curve= 0 ,0
Exp/Cntr=0.3,0.1

Type RM Length L Ch R = 1 ,117909  ,81,112,129
BEGIN DESCRIPTION:
This cross section corresponds to cross section 117920 of the non-georeferenced CDC model which was the source of this model.
END DESCRIPTION:
XS GIS Cut Line= 2
2486703.848474926967088.27784956 2485033.33278716966093.95962821
#Sta/Elev= 30
       0     430   13.18     429   63.01   411.2   95.76     402  119.05     400
  381.52     399  460.04     396  619.57     400  800.31     403  821.16  402.29
  850.84     386  864.33     383  874.18     374  906.37     369  923.59   369.5
  937.48     374  942.07     380  956.17  387.85  999.58  391.38 1018.98     397
 1024.64     402 1036.52  402.87 1074.48  398.33 1478.29  397.95 1794.64  400.26
 1839.73     403 1858.65     406 1914.93     427 1939.03     431 1944.04  430.43
#Mann= 3 ,0,0
       0    .055       0  821.16    .035       0 1024.64    .055       0
Levee=-1,0,428.5,-1,1939,428.5,,
#XS Ineff= 2 , 0
       0  821.16  402.29 1024.64       0     402
Permanent Ineff=
       F       F
Bank Sta=821.16,1024.64
XS Rating Curve= 0 ,0
Exp/Cntr=0.3,0.1

Type RM Length L Ch R = 1 ,117797  ,106,137,156
BEGIN DESCRIPTION:
This cross section corresponds to cross section 117801 of the non-georeferenced CDC model which was the source of this model.
END DESCRIPTION:
XS GIS Cut Line= 2
2486719.061042936967045.14834264  2485134.8991856965937.22240888
#Sta/Elev= 30
       0     430    10.8  429.08   81.49  407.23  103.56     401  135.78     399
   320.4     399  347.51     398   449.3  396.11  581.44     399  598.43     400
  700.42  400.27  748.71     401  792.56     403  828.71     403  862.66     387
  871.18  381.09  884.23  375.03  899.67     372  912.09     368  933.63  368.95
  956.31     375    1010     399 1791.01  398.78 1827.19  400.64 1836.24     402
 1849.02  405.99 1901.31     426 1916.82     430 1924.13     431 1933.15  430.25
#Mann= 3 ,0,0
       0    .055       0  828.71    .035       0    1010    .055       0
Levee=-1,0,428.47,-1,1924,428.47,,
#XS Ineff= 2 , 0
       0  828.71     403  999.76       0     396
Permanent Ineff=
       F       F
Bank Sta=828.71,1010
XS Rating Curve= 0 ,0
Exp/Cntr=0.3,0.1

Type RM Length L Ch R = 1 ,117660  ,78,100,114
BEGIN DESCRIPTION:
This cross section corresponds to cross section 117672 of the non-georeferenced CDC model which was the source of this model.
END DESCRIPTION:
XS GIS Cut Line= 2
2486784.62423199 6966976.85582832485260.233579996965805.33159655
#Sta/Elev= 30
       0   430.8   12.31     430  113.85     401  141.97     399  301.06     399
  445.86     397  735.73  400.46  832.15     403  837.38     402  840.15     399
  859.79     392  865.19  388.18  874.89  387.23  881.11     385  906.92     371
   923.6  368.68  958.44  369.75  986.48  385.09  994.87     388 1007.67  388.61
 1031.91     395  1038.2     399 1127.77     402 1232.82     402 1543.02  397.54
 1774.19  399.86 1809.44     402 1847.64     412 1897.22     428 1922.56     431
#Mann= 3 ,0,0
       0    .055       0  832.15    .035       0  1038.2    .055       0
Levee=-1,0,428.44,-1,1915,428.44,,
#XS Ineff= 2 , 0
       0  832.15     403  1038.2       0     399
Permanent Ineff=
       F       F
Bank Sta=832.15,1038.2
XS Rating Curve= 0 ,0
Exp/Cntr=0.3,0.1

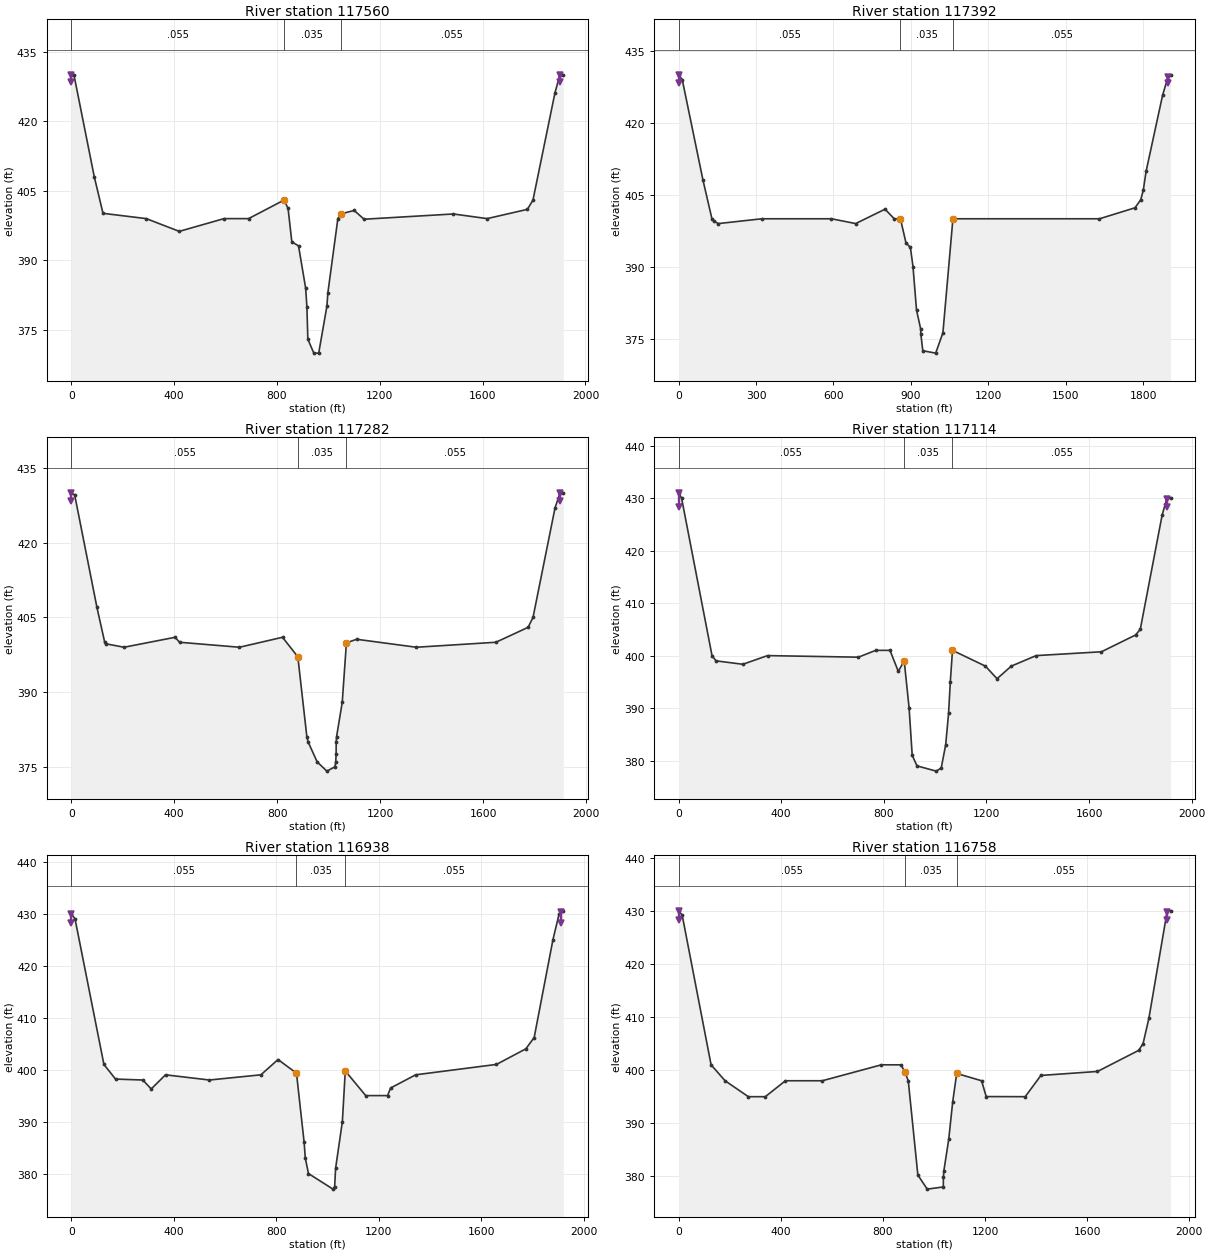
Type RM Length L Ch R = 1 ,117560  ,130,168,191
BEGIN DESCRIPTION:
This cross section corresponds to cross section 117572 of the non-georeferenced CDC model which was the source of this model.
END DESCRIPTION:
XS GIS Cut Line= 2
2486820.520157586966931.338858962485356.777350166965698.54473664
#Sta/Elev= 30
       0     430   10.35     430   89.56     408  123.46  400.14  291.66     399
  420.13  396.25     594     399  689.64     399  827.74     403  843.31  401.19
  857.85     394  883.97  393.12  911.68     384  916.47     380   920.2     373
  943.46     370  962.46     370  994.35  380.13  998.07     383 1036.95     399
 1047.23     400 1100.45  400.76 1138.83  398.87  1486.4     400 1617.53     399
 1774.21     401 1795.83     403  1880.9     426 1900.49     430 1913.72     430
#Mann= 3 ,0,0
       0    .055       0  827.74    .035       0 1047.23    .055       0
Levee=-1,0,428.42,-1,1900,428.42,,
#XS Ineff= 2 , 0
       0  827.74     403 1047.23       0     400
Permanent Ineff=
       F       F
Bank Sta=827.74,1047.23
XS Rating Curve= 0 ,0
Exp/Cntr=0.3,0.1

Type RM Length L Ch R = 1 ,117392  ,84,110,122
BEGIN DESCRIPTION:
This cross section corresponds to cross section 117403 of the non-georeferenced CDC model which was the source of this model.
END DESCRIPTION:
XS GIS Cut Line= 2
2486880.365510346966826.290840722485489.452609756965522.35250372
#Sta/Elev= 30
       0     430   14.15     429   94.72     408   129.2     400  138.21  399.46
  154.21     399  322.52     400  592.44     400  686.19     399  799.93     402
  835.68     400  859.57     400  881.04     395  898.27  394.02   908.3  390.05
  921.93     381  938.19     377  938.65     376  946.28   372.5  996.23     372
 1024.22  376.23    1063     400    1631     400  1768.6  402.29 1791.13     404
 1800.81     406 1811.52  409.87 1875.59  425.77 1897.69  429.75 1906.54     430
#Mann= 3 ,0,0
       0    .055       0  859.57    .035       0    1063    .055       0
Levee=-1,0,428.38,-1,1897,428.38,,
#XS Ineff= 2 , 0
       0  859.57     400    1063       0     400
Permanent Ineff=
       F       F
Bank Sta=859.57,1063
XS Rating Curve= 0 ,0
Exp/Cntr=0.3,0.1

Type RM Length L Ch R = 1 ,117282  ,139,168,199
BEGIN DESCRIPTION:
This cross section corresponds to cross section 117294 of the non-georeferenced CDC model which was the source of this model.
END DESCRIPTION:
XS GIS Cut Line= 2
2486966.092701086966807.221981212485623.040597176965447.35396604
#Sta/Elev= 30
       0     430   13.25  429.58   99.72     407   129.9     400  135.79  399.68
  205.17     399  403.32     401  420.75     400  653.33     399  820.57     401
  880.13  397.08  915.21     381  920.07     380  955.02     376  992.88  374.13
 1024.39     375 1027.34     376 1028.78  377.48 1029.19     380 1030.49     381
 1052.61  387.94 1068.83  399.88 1108.52   400.6 1340.49     399 1649.51     400
 1774.67     403  1793.8     405 1879.34     427 1898.94     430 1911.29     430
#Mann= 3 ,0,0
       0    .055       0  880.13    .035       0 1068.83    .055       0
Levee=-1,0,428.36,-1,1899,428.36,,
#XS Ineff= 2 , 0
       0  880.13  397.08 1068.83       0  399.88
Permanent Ineff=
       F       F
Bank Sta=880.13,1068.83
XS Rating Curve= 0 ,0
Exp/Cntr=0.3,0.1

Type RM Length L Ch R = 1 ,117114  ,146,176,209
BEGIN DESCRIPTION:
This cross section corresponds to cross section 117118 of the non-georeferenced CDC model which was the source of this model.
END DESCRIPTION:
XS GIS Cut Line= 2
2487057.26968408 6966753.1751733 2485803.18164116965302.39625071
#Sta/Elev= 30
       0     431   11.58     430   130.3     400  145.91     399  250.45  398.35
  346.85     400  700.98   399.7  768.33     401  823.95     401  856.26     397
  879.43  398.98   898.5     390  910.57     381   929.3     379 1004.15     378
 1023.73  378.61 1040.98     383 1052.28     389 1059.09  395.01 1067.52     401
 1195.76     398  1241.2   395.6  1296.8     398 1393.62     400 1647.98  400.73
 1780.94  403.92 1799.47     405 1884.78  426.79 1903.82     430 1917.68     430
#Mann= 3 ,0,0
       0    .055       0  879.43    .035       0 1067.52    .055       0
Levee=-1,0,428.32,-1,1903,428.32,,
#XS Ineff= 2 , 0
       0  879.43  398.98 1067.52       0     401
Permanent Ineff=
       F       F
Bank Sta=879.43,1067.52
XS Rating Curve= 0 ,0
Exp/Cntr=0.3,0.1

Type RM Length L Ch R = 1 ,116938  ,152,180,218
BEGIN DESCRIPTION:
This cross section corresponds to cross section 116942 of the non-georeferenced CDC model which was the source of this model.
END DESCRIPTION:
XS GIS Cut Line= 2
2487139.975883516966678.745204052485983.411595586965145.08915064
#Sta/Elev= 30
       0     430   14.73     429  127.45     401  172.76  398.18  279.26     398
  312.16  396.28   367.9     399  539.24     398  740.38     399  807.25  401.94
  876.71  399.41  879.98     399  909.13     386  913.66     383  925.93     380
 1021.78     377 1028.32  377.49 1031.99     381 1058.43     390 1069.75  399.75
 1149.51     395 1234.88     395 1246.73  396.46 1344.52     399 1660.03     401
  1774.7     404 1807.27  406.18 1880.51     425  1904.7     430 1920.87  430.56
#Mann= 3 ,0,0
       0    .055       0  876.71    .035       0 1069.75    .055       0
Levee=-1,0,428.28,-1,1912,428.28,,
#XS Ineff= 2 , 0
       0  876.71  399.41 1069.75       0  399.75
Permanent Ineff=
       F       F
Bank Sta=876.71,1069.75
XS Rating Curve= 0 ,0
Exp/Cntr=0.3,0.1

Type RM Length L Ch R = 1 ,116758  ,142,147,146
BEGIN DESCRIPTION:
This cross section corresponds to cross section 116766 of the non-georeferenced CDC model which was the source of this model.
END DESCRIPTION:
XS GIS Cut Line= 2
2487242.895625176966626.792880132486187.660530926965014.40076372
#Sta/Elev= 30
       0     430    14.1  429.18  127.27     401  182.05     398  273.18     395
  339.66     395  418.54     398  562.95     398  794.19     401  871.27     401
  885.84  399.68  899.52     398   937.1  380.25  973.81  377.59 1036.81     378
 1037.15  379.83 1038.84     381  1058.1     387  1073.5     394 1089.25  399.37
 1186.65     398 1204.78  395.02 1357.58     395    1419     399 1640.63  399.75
 1801.98  403.72 1819.21     405 1842.06  409.78 1913.63  429.94    1927     430
#Mann= 3 ,0,0
       0    .055       0  885.84    .035       0 1089.25    .055       0
Levee=-1,0,428.24,-1,1913,428.24,,
#XS Ineff= 2 , 0
       0  885.84  399.68 1089.25       0  399.37
Permanent Ineff=
       F       F
Bank Sta=885.84,1089.25
XS Rating Curve= 0 ,0
Exp/Cntr=0.3,0.1

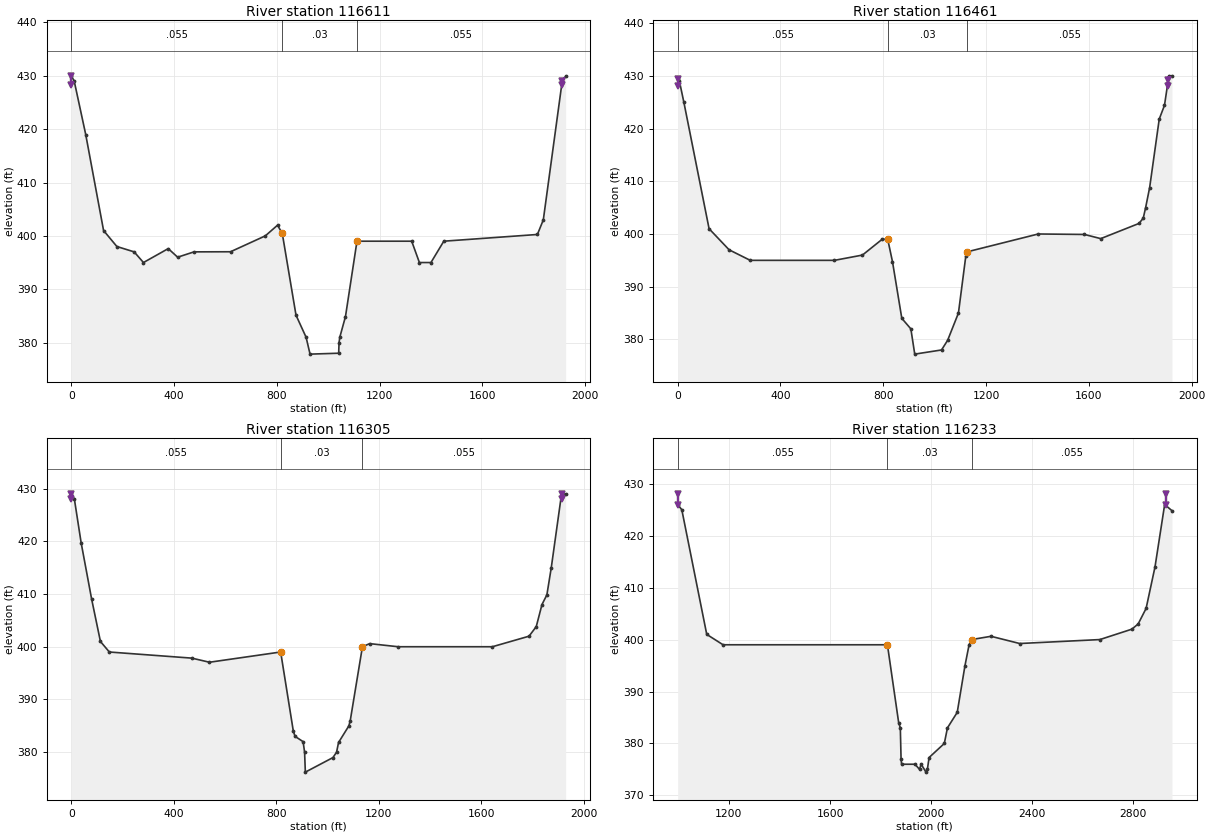
Type RM Length L Ch R = 1 ,116611  ,146,150,149
BEGIN DESCRIPTION:
This cross section corresponds to cross section 116615 of the non-georeferenced CDC model which was the source of this model.
END DESCRIPTION:
XS GIS Cut Line= 2
2487355.378996016966536.099163892486305.956554176964922.83992322
#Sta/Elev= 30
       0     430    11.1     429   55.84     419  125.34     401  177.21     398
  244.38     397  280.63     395  377.13  397.61  413.76     396  477.46     397
  619.61  397.02  755.11     400  802.66     402  821.14  400.45  874.59  385.13
   913.8     381  929.28  377.83 1040.73     378 1042.14     380  1045.1     381
 1067.22  384.88 1111.96     399    1325     399    1355     395    1400     395
    1450     399 1814.48  400.26 1837.48     403 1911.03     429 1924.55  429.92
#Mann= 3 ,0,0
       0    .055       0  821.14     .03       0 1111.96    .055       0
Levee=-1,0,428.19,-1,1911,428.19,,
#XS Ineff= 2 , 0
       0  821.14  400.45 1111.96       0     399
Permanent Ineff=
       F       F
Bank Sta=821.14,1111.96
XS Rating Curve= 0 ,0
Exp/Cntr=0.3,0.1

Type RM Length L Ch R = 1 ,116461  ,152,156,156
BEGIN DESCRIPTION:
This cross section corresponds to cross section 116464 of the non-georeferenced CDC model which was the source of this model.
END DESCRIPTION:
XS GIS Cut Line= 2
2487466.889927836966437.993717042486422.710913846964823.03828555
#Sta/Elev= 30
       0  429.42    6.74     429    24.1     425  122.24     401  200.18     397
  282.39     395  610.15     395  718.93     396  795.78     399  817.23     399
  835.79  394.75  872.06     384   907.3     382  922.39  377.21 1026.64     378
 1050.36  379.83  1092.4     385    1121  395.79  1126.8  396.62 1403.02     400
 1582.61  399.91 1646.05  399.12 1794.88     402 1811.44     403 1820.67     405
 1836.34  408.81 1873.67   421.8 1894.03   424.4 1911.22     430 1923.12     430
#Mann= 3 ,0,0
       0    .055       0  817.23     .03       0  1126.8    .055       0
Levee=-1,0,428.14,-1,1909,428.14,,
#XS Ineff= 2 , 0
       0  817.23     399  1126.8       0  396.62
Permanent Ineff=
       F       F
Bank Sta=817.23,1126.8
XS Rating Curve= 0 ,0
Exp/Cntr=0.3,0.1

Type RM Length L Ch R = 1 ,116305  ,72,72,72
BEGIN DESCRIPTION:
This cross section corresponds to cross section 116314 of the non-georeferenced CDC model which was the source of this model.
END DESCRIPTION:
XS GIS Cut Line= 2
 2487619.2626546 6966396.62667382486575.310674256964773.14829347
#Sta/Elev= 30
       0     429   11.73     428   38.17   419.7   79.21     409  113.43     401
  148.24     399   470.3  397.84  539.25  397.06  817.23     399  866.63     384
  873.46     383  904.87     382  910.66     380  913.57  376.22 1021.39  378.98
 1035.46     380 1043.24  381.84 1083.61     385 1088.97     386 1136.48     400
 1164.77  400.59 1276.08     400 1643.88     400 1787.08     402 1815.27  403.82
 1837.58     408 1856.76  409.84 1873.77  414.95 1914.15     429 1930.16     429
#Mann= 3 ,0,0
       0    .055       0  817.23     .03       0 1136.48    .055       0
Levee=-1,0,428.08,-1,1914,428.08,,
#XS Ineff= 2 , 0
       0  817.23     399 1136.48       0     400
Permanent Ineff=
       F       F
Bank Sta=817.23,1136.48
XS Rating Curve= 0 ,0
Exp/Cntr=0.3,0.1

Type RM Length L Ch R = 1 ,116233  ,59,59,59
BEGIN DESCRIPTION:
This cross section corresponds to cross section 116243 of the non-georeferenced CDC model which was the source of this model.
END DESCRIPTION:
XS GIS Cut Line= 2
2487687.88226801 6966372.72711532486630.955904196964727.81078571
#Sta/Elev= 30
   997.2     426 1013.62     425 1112.25     401 1176.73     399 1826.91     399
 1871.43     384 1877.95     383  1880.9     377 1883.04     376 1935.75     376
 1953.88  375.02 1960.31     376 1979.46  374.48 1984.92     375 1991.73  377.29
 2051.96     380 2064.37     383 2103.08  385.99 2133.59  394.96 2149.96     399
 2159.77     400 2236.67  400.63 2350.13  399.24 2667.07     400 2793.68     402
 2818.63     403 2850.17     406  2885.4     414 2923.56     426 2952.41  424.82
#Mann= 3 ,0,0
   997.2    .055       0 1826.91     .03       0 2159.77    .055       0
Levee=-1,997.2,428.06,-1,2927,428.06,,
#XS Ineff= 2 , 0
       0 1826.91     399 2159.77       0     400
Permanent Ineff=
       F       F
Bank Sta=1826.91,2159.77
XS Rating Curve= 0 ,0
Exp/Cntr=0.3,0.1

Type RM Length L Ch R = 3 ,116204  ,,,
BEGIN DESCRIPTION:
116214  Houston Street
END DESCRIPTION:
Node Name=Houston Street
Bridge Culvert--1,0,-1,-1, 0
Deck Dist Width WeirC Skew NumUp NumDn MinLoCord MaxHiCord MaxSubmerge Is_Ogee
1.5,56,2.6,0, 480, 480, , , 0.95, 0, ,,,
   997.2  1005.2  1013.2  1013.2  1024.7  1024.7  1027.7  1027.7  1034.1  1034.1
  1036.6  1036.6  1053.4  1053.4  1055.9  1055.9  1062.3  1062.3  1065.3  1065.3
  1076.8  1076.8  1084.8  1092.7  1092.7  1104.2  1104.2  1107.2  1107.2  1113.6
  1113.6  1116.1  1116.1  1132.9  1132.9  1135.4  1135.4  1141.8  1141.8  1144.8
  1144.8  1156.3  1156.3  1164.3  1172.2  1172.2  1183.7  1183.7  1186.7  1186.7
  1193.1  1193.1  1195.6  1195.6  1212.4  1212.4  1214.9  1214.9  1221.3  1221.3
  1224.3  1224.3  1235.8  1235.8  1243.8  1251.7  1251.7  1263.2  1263.2  1266.2
  1266.2  1272.6  1272.6  1275.1  1275.1  1291.9  1291.9  1294.4  1294.4  1300.8
  1300.8  1303.8  1303.8  1315.3  1315.3  1323.3  1331.2  1331.2  1342.7  1342.7
  1345.7  1345.7  1352.1  1352.1  1354.6  1354.6  1371.4  1371.4  1373.9  1373.9
  1380.3  1380.3  1383.3  1383.3  1394.8  1394.8  1402.8  1410.7  1410.7  1422.2
  1422.2  1425.2  1425.2  1431.6  1431.6  1434.1  1434.1  1450.9  1450.9  1453.4
  1453.4  1459.8  1459.8  1462.8  1462.8  1474.3  1474.3  1482.3  1490.2  1490.2
  1501.7  1501.7  1504.7  1504.7  1511.1  1511.1  1513.6  1513.6  1530.4  1530.4
  1532.9  1532.9  1539.3  1539.3  1542.3  1542.3  1553.8  1553.8  1561.8  1569.7
  1569.7  1581.2  1581.2  1584.2  1584.2  1590.6  1590.6  1593.1  1593.1  1609.9
  1609.9  1612.4  1612.4  1618.8  1618.8  1621.8  1621.8  1633.3  1633.3  1641.3
  1649.2  1649.2  1660.7  1660.7  1663.7  1663.7  1670.1  1670.1  1672.6  1672.6
  1689.4  1689.4  1691.9  1691.9  1698.3  1698.3  1701.3  1701.3  1712.8  1712.8
  1720.8  1728.7  1728.7  1740.2  1740.2  1740.2  1743.2  1743.2  1749.6  1749.6
  1752.1  1752.1  1768.9  1768.9  1771.4  1771.4  1777.8  1777.8  1780.8  1780.8
  1792.3  1792.3  1800.3  1808.2  1808.2  1819.7  1819.7  1822.7  1822.7  1829.1
  1829.1  1831.6  1831.6  1848.4  1848.4  1850.9  1850.9  1857.3  1857.3  1860.3
  1860.3  1871.8  1871.8  1879.8  1887.7  1887.7  1899.2  1899.2  1902.2  1902.2
  1908.6  1908.6  1911.1  1911.1  1927.9  1927.9  1930.4  1930.4  1936.8  1936.8
  1939.8  1939.8  1951.3  1951.3  1959.3  1967.2  1967.2  1978.7  1978.7  1981.7
  1981.7  1988.1  1988.1  1990.6  1990.6  2007.4  2007.4  2009.9  2009.9  2016.3
  2016.3  2019.3  2019.3  2030.8  2030.8  2038.8  2046.7  2046.7  2058.2  2058.2
  2061.2  2061.2  2067.6  2067.6  2070.1  2070.1  2086.9  2086.9  2089.4  2089.4
  2095.8  2095.8  2098.8  2098.8  2110.3  2110.3  2118.3  2126.2  2126.2  2137.7
  2137.7  2140.7  2140.7  2147.1  2147.1  2149.6  2149.6  2166.4  2166.4  2168.9
  2168.9  2175.3  2175.3  2178.3  2178.3  2189.8  2189.8  2197.8  2205.7  2205.7
  2217.2  2217.2  2220.2  2220.2  2226.6  2226.6  2229.1  2229.1  2245.9  2245.9
  2248.4  2248.4  2254.8  2254.8  2257.8  2257.8  2269.3  2269.3  2277.3  2285.2
  2285.2  2296.7  2296.7  2299.7  2299.7  2306.1  2306.1  2308.6  2308.6  2325.4
  2325.4  2327.9  2327.9  2334.3  2334.3  2337.3  2337.3  2348.8  2348.8  2356.8
  2364.7  2364.7  2376.2  2376.2  2379.2  2379.2  2385.6  2385.6  2388.1  2388.1
  2404.9  2404.9  2407.4  2407.4  2413.8  2413.8  2416.8  2416.8  2428.3  2428.3
  2436.3  2444.2  2444.2  2455.7  2455.7  2458.7  2458.7  2465.1  2465.1  2467.6
  2467.6  2484.4  2484.4  2486.9  2486.9  2493.3  2493.3  2496.3  2496.3  2507.8
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Pier Skew, UpSta & Num, DnSta & Num=  ,1045, 5 ,1045, 5 , 0 , 0 , 0 ,,
       9       8       8       4       4
   392.1   416.1   425.4   425.4     438
       9       8       8       4       4
   392.1   416.1   425.4   425.4     438
Pier Skew, UpSta & Num, DnSta & Num=  ,1124.5, 5 ,1124.5, 5 , 0 , 0 , 0 ,,
       9       8       8       4       4
   391.5   415.5   424.8   424.8   437.5
       9       8       8       4       4
   391.5   415.5   424.8   424.8   437.5
Pier Skew, UpSta & Num, DnSta & Num=  ,1204, 5 ,1204, 5 , 0 , 0 , 0 ,,
       9       8       8       4       4
   390.8   414.8   424.1   424.1   436.8
       9       8       8       4       4
   390.8   414.8   424.1   424.1   436.8
Pier Skew, UpSta & Num, DnSta & Num=  ,1283.5, 5 ,1283.5, 5 , 0 , 0 , 0 ,,
      20       8       8       4       4
   390.2   414.2   423.5   423.5   436.2
      20       8       8       4       4
   390.2   414.2   423.5   423.5   436.2
Pier Skew, UpSta & Num, DnSta & Num=  ,1363, 5 ,1363, 5 , 0 , 0 , 0 ,,
       9       8       8       4       4
   389.6   413.6   422.9   422.9   435.6
       9       8       8       4       4
   389.6   413.6   422.9   422.9   435.6
Pier Skew, UpSta & Num, DnSta & Num=  ,1442.5, 5 ,1442.5, 5 , 0 , 0 , 0 ,,
       9       8       8       4       4
     389     413   422.3   422.3     435
       9       8       8       4       4
     389     413   422.3   422.3     435
Pier Skew, UpSta & Num, DnSta & Num=  ,1522, 5 ,1522, 5 , 0 , 0 , 0 ,,
       9       8       8       4       4
   388.4   412.4   421.7   421.7   434.4
       9       8       8       4       4
   388.4   412.4   421.7   421.7   434.4
Pier Skew, UpSta & Num, DnSta & Num=  ,1601.5, 5 ,1601.5, 5 , 0 , 0 , 0 ,,
       9       8       8       4       4
   387.2   411.8   421.1   421.1   433.8
       9       8       8       4       4
   387.2   411.8   421.1   421.1   433.8
Pier Skew, UpSta & Num, DnSta & Num=  ,1681, 5 ,1681, 5 , 0 , 0 , 0 ,,
      20       8       8       4       4
   387.2   411.2   420.5   420.5   433.2
      20       8       8       4       4
   387.2   411.2   420.5   420.5   433.2
Pier Skew, UpSta & Num, DnSta & Num=  ,1760.5, 5 ,1760.5, 5 , 0 , 0 , 0 ,,
       9       8       8       4       4
   386.6   410.6   419.9   419.9   432.6
       9       8       8       4       4
   386.6   410.6   419.9   419.9   432.6
Pier Skew, UpSta & Num, DnSta & Num=  ,1840, 5 ,1840, 5 , 0 , 0 , 0 ,,
       9       8       8       4       4
   386.1   410.1   419.4   419.4   432.1
       9       8       8       4       4
   386.1   410.1   419.4   419.4   432.1
Pier Skew, UpSta & Num, DnSta & Num=  ,1919.5, 8 ,1919.5, 8 , 0 , 0 , 0 ,,
      28      18      10      10       8       8       4       4
   373.9   388.9   388.9   409.5   409.5   418.8   418.8   431.5
      28      18      10      10       8       8       4       4
   373.9   388.9   388.9   409.5   409.5   418.8   418.8   431.5
Pier Skew, UpSta & Num, DnSta & Num=  ,1999, 8 ,1999, 8 , 0 , 0 , 0 ,,
      28      18      10      10       8       8       4       4
   373.5   388.5   388.5     409     409   418.3   418.3     431
      28      18      10      10       8       8       4       4
   373.5   388.5   388.5     409     409   418.3   418.3     431
Pier Skew, UpSta & Num, DnSta & Num=  ,2078.5, 7 ,2078.5, 7 , 0 , 0 , 0 ,,
    31.5    31.5      15       8       8       4       4
     370     395     395   408.5   417.8   417.8   430.5
    31.5    31.5      15       8       8       4       4
     370     395     395   408.5   417.8   417.8   430.5
Pier Skew, UpSta & Num, DnSta & Num=  ,2158, 5 ,2158, 5 , 0 , 0 , 0 ,,
       9       8       8       4       4
   383.9   407.9   417.2   417.2   429.9
       9       8       8       4       4
   383.9   407.9   417.2   417.2   429.9
Pier Skew, UpSta & Num, DnSta & Num=  ,2237.5, 5 ,2237.5, 5 , 0 , 0 , 0 ,,
       9       8       8       4       4
   383.4   407.4   416.7   416.7   429.4
       9       8       8       4       4
   383.4   407.4   416.7   416.7   429.4
Pier Skew, UpSta & Num, DnSta & Num=  ,2317, 5 ,2317, 5 , 0 , 0 , 0 ,,
       9       8       8       4       4
   382.9   406.9   416.2   416.2   428.9
       9       8       8       4       4
   382.9   406.9   416.2   416.2   428.9
Pier Skew, UpSta & Num, DnSta & Num=  ,2396.5, 5 ,2396.5, 5 , 0 , 0 , 0 ,,
       9       8       8       4       4
   382.3   406.3   415.6   415.6   428.3
       9       8       8       4       4
   382.3   406.3   415.6   415.6   428.3
Pier Skew, UpSta & Num, DnSta & Num=  ,2476, 5 ,2476, 5 , 0 , 0 , 0 ,,
      20       8       8       4       4
   381.6   405.6   414.9   414.9   427.6
      20       8       8       4       4
   381.6   405.6   414.9   414.9   427.6
Pier Skew, UpSta & Num, DnSta & Num=  ,2555.5, 5 ,2555.5, 5 , 0 , 0 , 0 ,,
       9       8       8       4       4
     381     405   414.3   414.3     427
       9       8       8       4       4
     381     405   414.3   414.3     427
Pier Skew, UpSta & Num, DnSta & Num=  ,2635, 5 ,2635, 5 , 0 , 0 , 0 ,,
       9       8       8       4       4
   380.5   404.5   413.8   413.8   426.5
       9       8       8       4       4
   380.5   404.5   413.8   413.8   426.5
Pier Skew, UpSta & Num, DnSta & Num=  ,2714.5, 5 ,2714.5, 5 , 0 , 0 , 0 ,,
       9       8       8       4       4
     380     404   413.3   413.3     426
       9       8       8       4       4
     380     404   413.3   413.3     426
Pier Skew, UpSta & Num, DnSta & Num=  ,2794, 5 ,2794, 5 , 0 , 0 , 0 ,,
       9       8       8       4       4
   379.5   403.5   412.8   412.8   425.5
       9       8       8       4       4
   379.5   403.5   412.8   412.8   425.5
Pier Skew, UpSta & Num, DnSta & Num=  ,2829, 2 ,2829, 2 , 0 , 0 , 0 ,,
       2       2
     390     421
       2       2
     390     421
Pier Skew, UpSta & Num, DnSta & Num=  ,2859, 2 ,2859, 2 , 0 , 0 , 0 ,,
       2       2
     390     421
       2       2
     390     421
Pier Skew, UpSta & Num, DnSta & Num=  ,2889, 2 ,2889, 2 , 0 , 0 , 0 ,,
       2       2
     390     421
       2       2
     390     421
Pier Skew, UpSta & Num, DnSta & Num=  ,2919, 2 ,2919, 2 , 0 , 0 , 0 ,,
       2       2
     390     421
       2       2
     390     421
BR Coef= 1 , 1 , 1 ,1.25, 0 ,,,0.8,-1,2,1,
WSPro=,,,, 1 ,,,, 0 ,,,, 0 ,,,,-1 ,-1 ,-1 , 0 , 0 , 0 , 0 , 0
BC Design=,, 0 ,, 0 ,,,,,,
BC HTab HWMax=436.7
BC Use User HTab Curves=0
BC User HTab FreeFlow(D)= 0