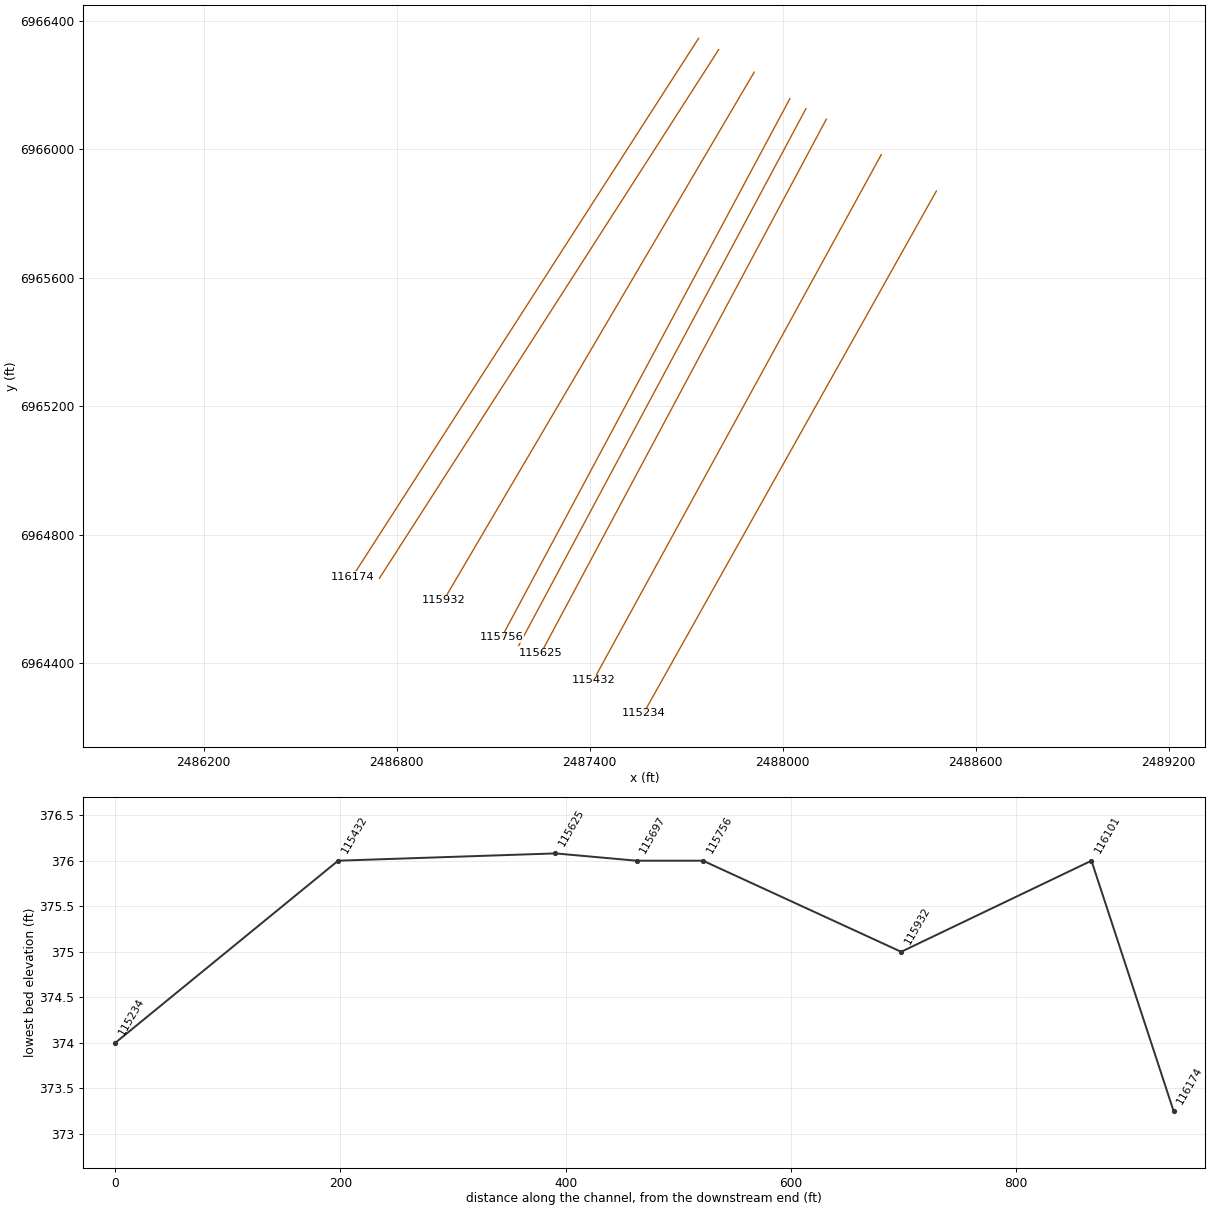
HEC-RAS study CDC_Consolidated_Model.prj: Upper Trinity CDC Consolidated Model

--- CDC_Consolidated_Model.g02 (geometry) --- (continued)

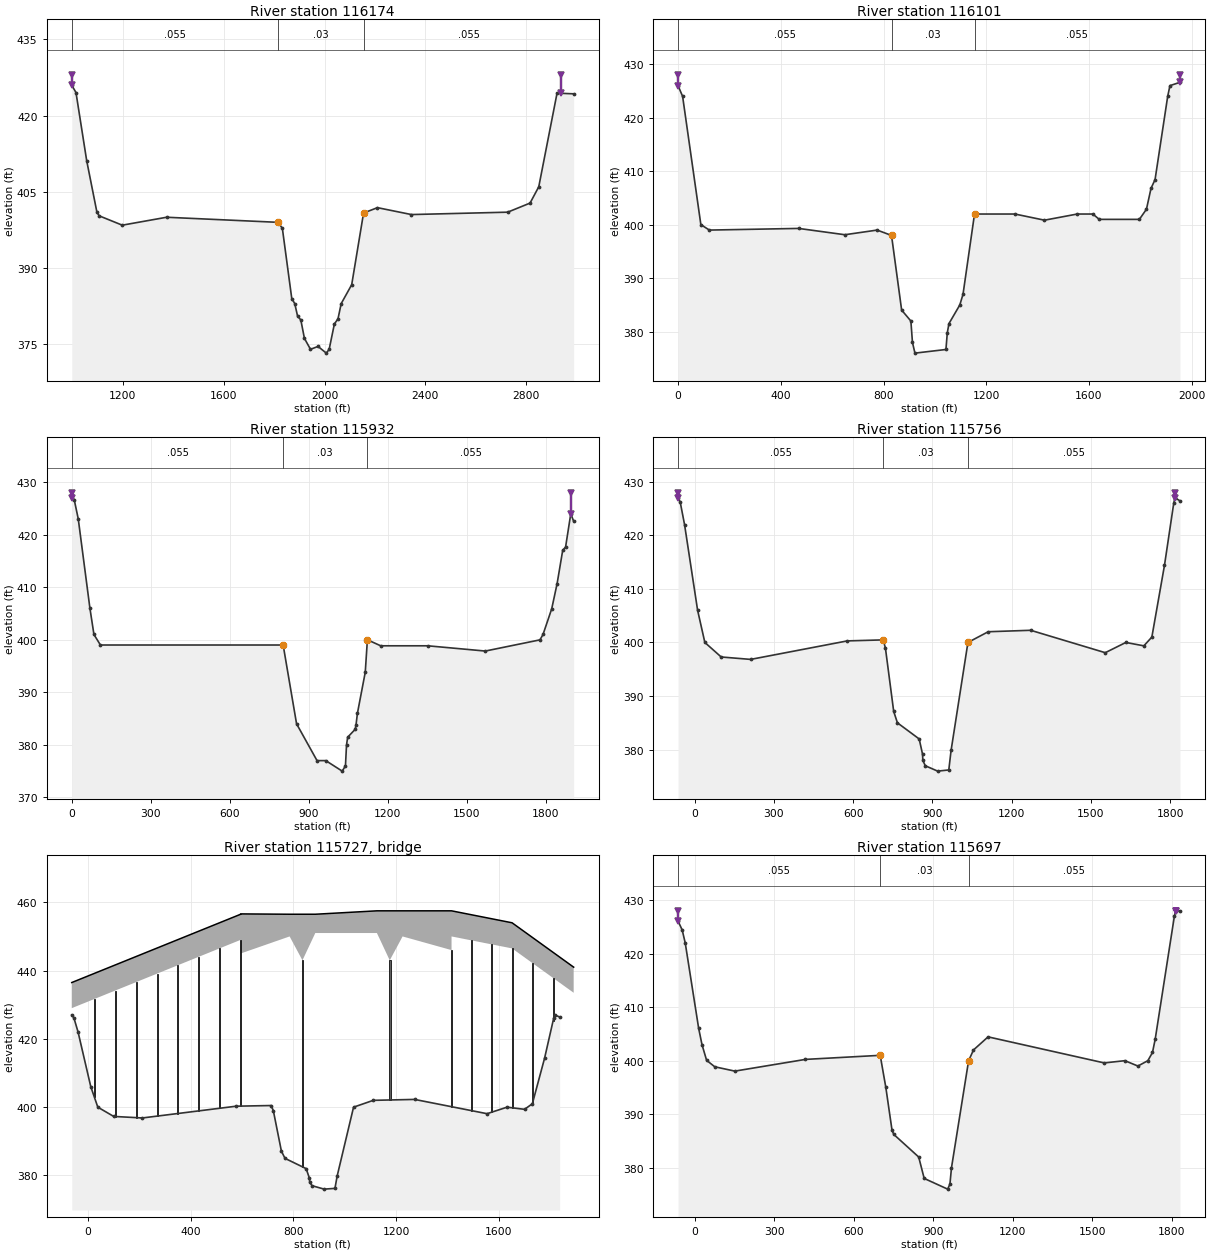
Type RM Length L Ch R = 1 ,116174  ,73,73,73
BEGIN DESCRIPTION:
This cross section corresponds to cross section 116185 of the non-georeferenced CDC model which was the source of this model.
END DESCRIPTION:
XS GIS Cut Line= 2
2487738.970748516966344.800990052486662.882677586964669.72691238
#Sta/Elev= 30
   997.2     426 1013.96  424.55 1056.37  411.15 1096.95     401 1105.95  400.28
 1197.52  398.44 1373.44     400 1815.37     399 1832.55  397.83  1869.9     384
 1881.75     383  1892.9  380.55 1905.84  379.78 1920.09  376.16 1944.17     374
 1974.15  374.57 2006.88  373.25 2018.26     374 2038.99     379 2053.26     380
 2065.97     383 2107.64  386.72 2154.71  400.83 2209.78  401.89 2344.61  400.53
 2726.43     401 2815.12  402.79 2849.68     406  2922.2  424.43 2988.14   424.3
#Mann= 3 ,0,0
   997.2    .055       0 1815.37     .03       0 2154.71    .055       0
Levee=-1,997.2,428.04,-1,2936,428.04,,
#XS Ineff= 2 , 0
       0 1815.37     399 2154.71       0  400.83
Permanent Ineff=
       F       F
Bank Sta=1815.37,2154.71
XS Rating Curve= 0 ,0
Exp/Cntr=0.3,0.1

Type RM Length L Ch R = 1 ,116101  ,155,169,184
BEGIN DESCRIPTION:
This cross section corresponds to cross section 116111 of the non-georeferenced CDC model which was the source of this model.
END DESCRIPTION:
XS GIS Cut Line= 2
2487801.524101086966309.857490382486746.872667076964664.56156838
#Sta/Elev= 30
       0     426   17.75     424   88.82  400.02  121.96     399  469.47  399.31
   649.6  398.13  775.21     399  831.24     398  870.59  384.05  906.58     382
  912.74     378  922.42     376 1043.13  376.68 1048.35  379.79 1054.87  381.52
 1097.07     385 1109.64     387 1154.38     402 1311.74     402 1426.87  400.85
 1554.37     402 1615.02     402 1640.18     401 1796.23     401 1823.79  402.89
 1841.75  406.82 1857.35  408.43 1906.56     424 1915.35     426  1954.3  426.62
#Mann= 3 ,0,0
       0    .055       0  831.24     .03       0 1154.38    .055       0
Levee=-1,0,428.02,-1,1954,428.02,,
#XS Ineff= 2 , 0
       0  831.24     398 1154.38       0     402
Permanent Ineff=
       F       F
Bank Sta=831.24,1154.38
XS Rating Curve= 0 ,0
Exp/Cntr=0.3,0.1

Type RM Length L Ch R = 1 ,115932  ,163,176,194
BEGIN DESCRIPTION:
This cross section corresponds to cross section 115937 of the non-georeferenced CDC model which was the source of this model.
END DESCRIPTION:
XS GIS Cut Line= 2
2487911.852292516966239.621738462486946.21970934 6964595.6283073
#Sta/Elev= 30
       0     427    9.69  426.57   24.66     423   68.96     406   84.25     401
  108.88     399     803     399     854     384  931.71     377  964.95     377
  1027.3     375 1039.71     376 1043.75     380  1048.2  381.46  1076.5  382.95
 1079.61   383.7 1085.14     386 1114.91  393.82 1123.03     400  1173.5  398.85
 1352.26  398.85 1570.98  397.85 1778.58  399.98 1790.14     401 1823.21  405.89
  1843.7  410.68 1864.91     417 1875.97  417.67 1895.69     424 1906.61  422.54
#Mann= 3 ,0,0
       0    .055       0     803     .03       0 1123.03    .055       0
Levee=-1,0,427.96,-1,1896,427.96,,
#XS Ineff= 2 , 0
       0     803     399 1123.03       0     399
Permanent Ineff=
       F       F
Bank Sta=803,1123.03
XS Rating Curve= 0 ,0
Exp/Cntr=0.3,0.1

Type RM Length L Ch R = 1 ,115756  ,59,59,59
BEGIN DESCRIPTION:
This cross section corresponds to cross section 115764 of the non-georeferenced CDC model which was the source of this model.
END DESCRIPTION:
XS GIS Cut Line= 2
2488022.687372686966156.803334552487126.722957256964480.84474422
#Sta/Elev= 30
     -63     427  -54.84  426.19   -38.4     422   11.08     406    38.5     400
  100.35  397.29  211.98  396.84  577.79  400.29  713.47  400.48   722.1     399
  753.56  387.13  767.64  385.01  850.05     382  862.75  379.17  863.91     378
  873.21     377  920.02     376  962.17  376.22  970.87  379.87 1034.62     400
 1111.44     402 1272.26  402.27 1554.63  398.09 1632.52     400 1700.73  399.37
 1731.03     401 1778.75  414.36 1813.97     426 1818.67     427 1837.43  426.41
#Mann= 3 ,0,0
     -63    .055       0  713.47     .03       0 1034.62    .055       0
Levee=-1,-63,427.91,-1,1818,427.91,,
#XS Ineff= 2 , 0
       0  713.47  400.48 1034.62       0     400
Permanent Ineff=
       F       F
Bank Sta=713.47,1034.62
XS Rating Curve= 0 ,0
Exp/Cntr=0.3,0.1

Type RM Length L Ch R = 3 ,115727  ,,,
BEGIN DESCRIPTION:
115734.5  Jefferson Boulevard
END DESCRIPTION:
Node Name=Jefferson Blvd.
Bridge Culvert--1,0,-1,-1, 0
Deck Dist Width WeirC Skew NumUp NumDn MinLoCord MaxHiCord MaxSubmerge Is_Ogee
1,57,2.6,0, 13, 13, , , 0.95, 0, 0,0,,
     -63   594.8   594.8   785.6   835.6   885.6  1125.6  1175.6  1225.6  1416.3
  1416.3    1652    1892
   436.5   456.5   456.6   456.5   456.5   456.5   457.5   457.5   457.5   457.5
   457.5     454     441
     429     449     445     450     443     451     451     443     450     446
     450   446.5   433.5
     -63   594.8   594.8   785.6   835.6   885.6  1125.6  1175.6  1225.6  1416.3
  1416.3    1652    1892
   436.5   456.5   456.6   456.5   456.5   456.5   457.5   457.5   457.5   457.5
   457.5     454     441
     429     449     445     450     443     451     451     443     450     446
     450   446.5   433.5
Pier Skew, UpSta & Num, DnSta & Num=  ,25, 2 ,25, 2 , 0 , 0 , 0 ,,
       4       4
     370     438
       4       4
     370     438
Pier Skew, UpSta & Num, DnSta & Num=  ,106.4, 2 ,106.4, 2 , 0 , 0 , 0 ,,
       4       4
     370     440
       4       4
     370     440
Pier Skew, UpSta & Num, DnSta & Num=  ,187.8, 2 ,187.8, 2 , 0 , 0 , 0 ,,
       4       4
     370     442
       4       4
     370     442
Pier Skew, UpSta & Num, DnSta & Num=  ,269.2, 2 ,269.2, 2 , 0 , 0 , 0 ,,
       4       4
     370     443
       4       4
     370     443
Pier Skew, UpSta & Num, DnSta & Num=  ,350.6, 2 ,350.6, 2 , 0 , 0 , 0 ,,
       4       4
     370     447
       4       4
     370     447
Pier Skew, UpSta & Num, DnSta & Num=  ,432, 2 ,432, 2 , 0 , 0 , 0 ,,
       4       4
     370     449
       4       4
     370     449
Pier Skew, UpSta & Num, DnSta & Num=  ,513.4, 2 ,513.4, 2 , 0 , 0 , 0 ,,
       4       4
     370     452
       4       4
     370     452
Pier Skew, UpSta & Num, DnSta & Num=  ,594.8, 2 ,594.8, 2 , 0 , 0 , 0 ,,
       4       4
     370     453
       4       4
     370     453
Pier Skew, UpSta & Num, DnSta & Num=  ,835.6, 2 ,835.6, 2 , 0 , 0 , 0 ,,
       6       6
     370     454
       6       6
     370     454
Pier Skew, UpSta & Num, DnSta & Num=  ,1175.6, 2 ,1175.6, 2 , 0 , 0 , 0 ,,
       6       6
     370     454
       6       6
     370     454
Pier Skew, UpSta & Num, DnSta & Num=  ,1416.3, 2 ,1416.3, 2 , 0 , 0 , 0 ,,
       4       4
     370     454
       4       4
     370     454
Pier Skew, UpSta & Num, DnSta & Num=  ,1494.15, 2 ,1494.15, 2 , 0 , 0 , 0 ,,
       4       4
     370     452
       4       4
     370     452
Pier Skew, UpSta & Num, DnSta & Num=  ,1572, 2 ,1572, 2 , 0 , 0 , 0 ,,
       4       4
     370     452
       4       4
     370     452
Pier Skew, UpSta & Num, DnSta & Num=  ,1652, 2 ,1652, 2 , 0 , 0 , 0 ,,
       4       4
     370     452
       4       4
     370     452
Pier Skew, UpSta & Num, DnSta & Num=  ,1732, 2 ,1732, 2 , 0 , 0 , 0 ,,
       4       4
     370     445
       4       4
     370     445
Pier Skew, UpSta & Num, DnSta & Num=  ,1812, 2 ,1812, 2 , 0 , 0 , 0 ,,
       4       4
     370     440
       4       4
     370     440
BR Coef=-1 , 1 , 1 ,1.05, 0 ,,,0.8,-1,1.2,1,
WSPro=,,,, 1 ,,,, 0 ,,,, 0 ,,,,-1 ,-1 ,-1 , 0 , 0 , 0 , 0 , 0
BC Design=,, 0 ,, 0 ,,,,,,
BC HTab HWMax=427
BC Use User HTab Curves=0
BC User HTab FreeFlow(D)= 0

Type RM Length L Ch R = 1 ,115697  ,72,72,72
BEGIN DESCRIPTION:
This cross section corresponds to cross section 115705 of the non-georeferenced CDC model which was the source of this model.
END DESCRIPTION:
XS GIS Cut Line= 2
2488072.575396276966125.604906132487179.820620096964455.05050446
#Sta/Elev= 30
     -63  426.09  -47.33  424.42  -35.88     422   14.87  406.02   27.29  403.02
   44.73  400.07   75.57  398.86  151.33  398.05  417.79  400.24  699.91     401
  721.16     395  744.55     387  751.24  386.22  845.18     382  865.93     378
  954.45     376  963.09  376.94  968.94     380 1033.46  399.97  1051.9     402
 1107.05  404.45 1545.51  399.58 1623.23     400 1672.44     399 1710.01     400
 1727.45  401.53 1737.66     404 1810.11     427  1815.1     428 1831.14     428
#Mann= 3 ,0,0
     -63    .055       0  699.91     .03       0 1033.46    .055       0
Levee=-1,-63,427.89,-1,1815,427.89,,
#XS Ineff= 2 , 0
       0  699.91     401 1033.46       0  399.97
Permanent Ineff=
       F       F
Bank Sta=699.91,1033.46
XS Rating Curve= 0 ,0
Exp/Cntr=0.3,0.1

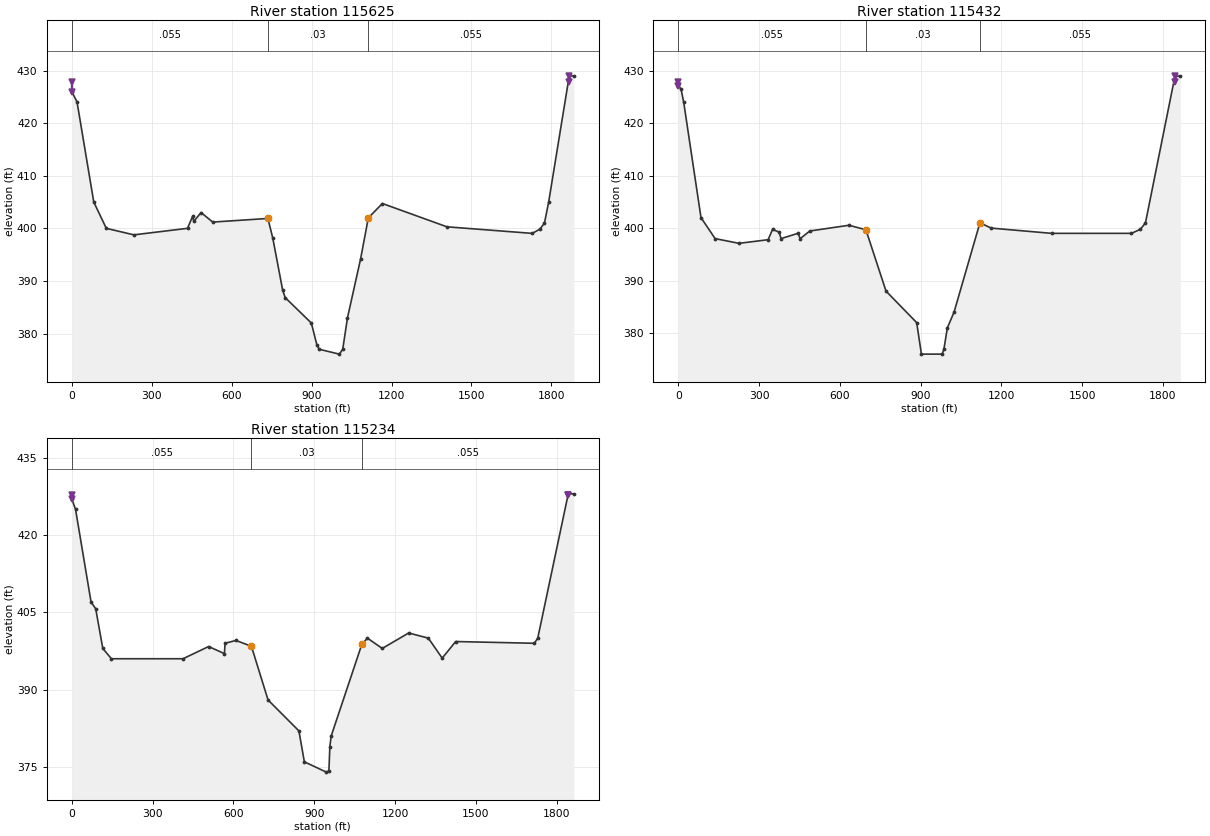
Type RM Length L Ch R = 1 ,115625  ,194,193,188
BEGIN DESCRIPTION:
This cross section corresponds to cross section 115633 of the non-georeferenced CDC model which was the source of this model.
END DESCRIPTION:
XS GIS Cut Line= 2
2488136.13432425 6966093.12531232487248.86542949 6964430.8746998
#Sta/Elev= 30
       0     426    19.7  424.05   82.55     405  129.62     400  233.03  398.76
  434.32     400  453.58  402.28  458.06  401.35  485.39     403  528.93  401.19
  736.04  401.88  754.15  398.19  791.46  388.25  800.87  386.83  899.04     382
  920.35  377.74  928.86     377 1004.09  376.08 1016.86     377 1034.76     383
 1083.81  394.15 1113.02     402 1165.81  404.72 1407.88  400.29 1728.16  399.04
 1756.62  399.84 1773.93     401 1789.72     405 1867.08     429 1884.23     429
#Mann= 3 ,0,0
       0    .055       0  736.04     .03       0 1113.02    .055       0
Levee=-1,0,427.86,-1,1867,427.86,,
#XS Ineff= 2 , 0
       0  736.04  401.88 1113.02       0     402
Permanent Ineff=
       F       F
Bank Sta=736.04,1113.02
XS Rating Curve= 0 ,0
Exp/Cntr=0.3,0.1

Type RM Length L Ch R = 1 ,115432  ,200,198,193
BEGIN DESCRIPTION:
This cross section corresponds to cross section 115434 of the non-georeferenced CDC model which was the source of this model.
END DESCRIPTION:
XS GIS Cut Line= 2
2488306.925649346965982.811884632487411.754211346964346.59927779
#Sta/Elev= 30
       0     427   10.15  426.54   20.22     424   84.54     402  137.05     398
   225.8   397.1  333.88  397.79   350.4  399.75  374.64  399.24  382.08     398
   444.4     399  453.37     398  488.76  399.45  634.29  400.54  697.14  399.68
  771.88     388  885.78     382  903.35     376  980.52     376  987.08     377
  999.77     381 1024.63     384 1120.66     401 1162.83     400 1387.38     399
 1683.58     399 1716.71  399.77 1735.63     401 1845.49     429 1865.08  428.92
#Mann= 3 ,0,0
       0    .055       0  697.14     .03       0 1120.66    .055       0
Levee=-1,0,427.79,-1,1845,427.79,,
#XS Ineff= 2 , 0
       0  697.14  399.68 1120.66       0     401
Permanent Ineff=
       F       F
Bank Sta=697.14,1120.66
XS Rating Curve= 0 ,0
Exp/Cntr=0.3,0.1

Type RM Length L Ch R = 1 ,115234  ,207,205,200
BEGIN DESCRIPTION:
This cross section corresponds to cross section 115236 of the non-georeferenced CDC model which was the source of this model.
END DESCRIPTION:
XS GIS Cut Line= 2
2488478.217957686965869.661848472487567.683033356964243.95446996
#Sta/Elev= 30
       0     427   13.97     425    71.6     407   88.85   405.7  115.15     398
   147.1     396  412.91     396   507.8  398.37  566.45     397  569.05     399
  609.21  399.55  666.67  398.42  728.48     388  843.01     382  863.18     376
  945.02     374  954.34  374.27  957.85  378.97  962.72     381 1076.64  398.82
  1097.3     400 1152.36     398 1250.27     401 1323.23     400  1374.8  396.12
 1424.74  399.34 1716.78     399 1729.38     400 1842.67     428 1863.33     428
#Mann= 3 ,0,0
       0    .055       0  666.67     .03       0 1076.64    .055       0
Levee=-1,0,427.72,-1,1842,427.72,,
#XS Ineff= 2 , 0
       0  666.67  398.42 1076.64       0  398.82
Permanent Ineff=
       F       F
Bank Sta=666.67,1076.64
XS Rating Curve= 0 ,0
Exp/Cntr=0.3,0.1