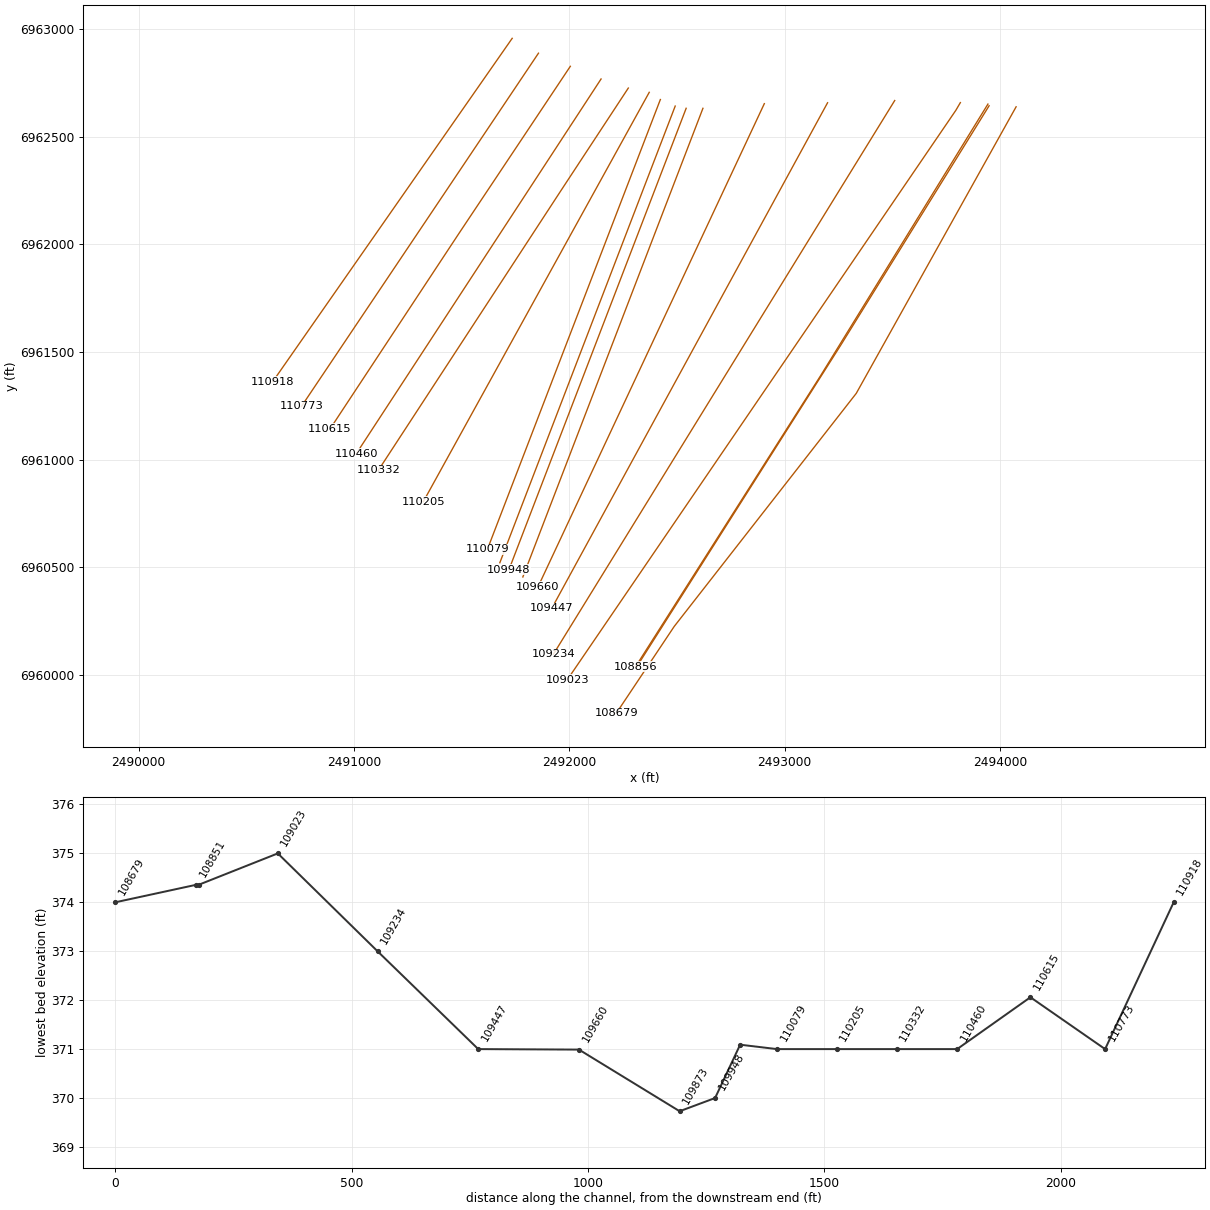
HEC-RAS study CDC_Consolidated_Model.prj: Upper Trinity CDC Consolidated Model

--- CDC_Consolidated_Model.g02 (geometry) --- (continued)

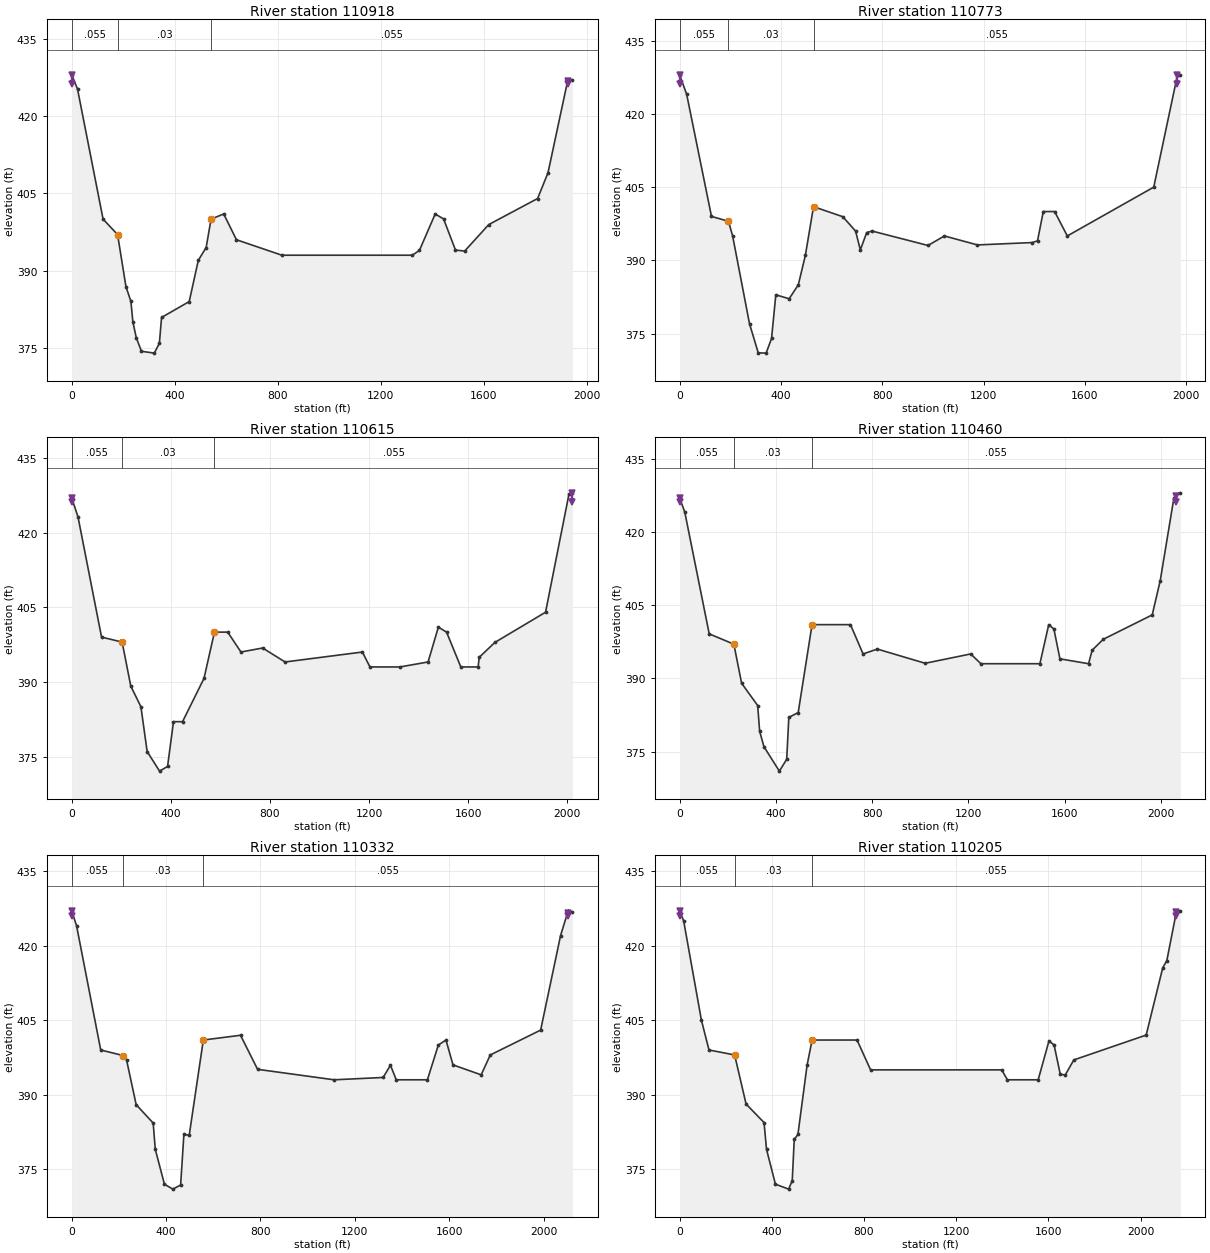
Type RM Length L Ch R = 1 ,110918  ,139,145,156
BEGIN DESCRIPTION:
This cross section corresponds to cross section 110929 of the non-georeferenced CDC model which was the source of this model.
END DESCRIPTION:
XS GIS Cut Line= 2
2491734.502455596962958.187684552490622.644771166961362.42939313
#Sta/Elev= 30
       0     428   22.54  425.25  121.83     400  178.19     397  210.66   386.9
  229.88  384.04  237.64  380.03  250.71  377.01   270.8  374.36  320.85     374
  340.54  375.92  348.97  380.92  456.36     384  491.65     392  522.21  394.49
  541.18     400   590.3     401  639.85     396  816.19     393 1322.74     393
 1350.46  393.93 1411.69     401 1444.28  400.04 1490.49     394 1526.15   393.8
 1619.65  398.94 1809.53     404 1849.88     409 1926.89     427 1944.91  426.97
#Mann= 3 ,0,0
       0    .055       0  178.19     .03       0  541.18    .055       0
Levee=-1,0,426.17,-1,1926,426.17,,
#XS Ineff= 2 , 0
       0  178.19     397  541.18       0     400
Permanent Ineff=
       F       F
Bank Sta=178.19,541.18
XS Rating Curve= 0 ,0
Exp/Cntr=0.3,0.1

Type RM Length L Ch R = 1 ,110773  ,151,158,156
BEGIN DESCRIPTION:
This cross section corresponds to cross section 110783 of the non-georeferenced CDC model which was the source of this model.
END DESCRIPTION:
XS GIS Cut Line= 2
2491856.513366436962889.141890882490755.759334336961247.08382329
#Sta/Elev= 30
       0     428   27.95     424  125.87     399  192.97     398  209.34     395
  276.06     377  310.46  371.06  341.52     371  362.98     374  379.81  382.94
  432.56  382.14  468.69     385  496.41     391  528.68     401  644.23  398.94
  694.71     396  713.52  392.15  738.71   395.7  760.05     396  980.71  393.05
 1045.39     395 1175.82  393.16 1392.65  393.65 1412.91     394 1435.72     400
 1480.49     400 1530.51     395 1871.77     405 1965.53     428 1976.87     428
#Mann= 3 ,0,0
       0    .055       0  192.97     .03       0  528.68    .055       0
Levee=-1,0,426.12,-1,1965,426.12,,
#XS Ineff= 2 , 0
       0  192.97     398  528.68       0     401
Permanent Ineff=
       F       F
Bank Sta=192.97,528.68
XS Rating Curve= 0 ,0
Exp/Cntr=0.3,0.1

Type RM Length L Ch R = 1 ,110615  ,149,155,154
BEGIN DESCRIPTION:
This cross section corresponds to cross section 110626 of the non-georeferenced CDC model which was the source of this model.
END DESCRIPTION:
XS GIS Cut Line= 3
2492004.450078436962828.175149312491486.999997826962051.00019446
2490888.592730086961142.50004296
#Sta/Elev= 30
       0     427   25.47  423.15  120.48     399  203.55     398  238.48  389.15
  279.41     385  304.54     376  354.62  372.06  386.99     373   410.9     382
  447.43     382  533.96  390.69  576.31     400   629.8     400   683.2     396
  770.85  396.81  861.22     394 1173.56     396 1203.87     393 1325.07     393
 1438.63     394 1480.12     401 1513.32     400 1570.74     393 1640.61     393
 1645.12  394.94 1708.35  397.93 1912.82     404 2007.57  427.78 2021.55     428
#Mann= 3 ,0,0
       0    .055       0  203.55     .03       0  576.31    .055       0
Levee=-1,0,426.07,-1,2021,426.07,,
#XS Ineff= 2 , 0
       0  203.55     398  576.31       0     400
Permanent Ineff=
       F       F
Bank Sta=203.55,576.31
XS Rating Curve= 0 ,0
Exp/Cntr=0.3,0.1

Type RM Length L Ch R = 1 ,110460  ,83,128,183
BEGIN DESCRIPTION:
This cross section corresponds to cross section 110470 of the non-georeferenced CDC model which was the source of this model.
END DESCRIPTION:
XS GIS Cut Line= 2
2492147.141066016962769.199217382491009.789994276961026.54981555
#Sta/Elev= 30
       0     427   21.73     424  123.11  399.11  225.46     397  257.69     389
  324.52  384.43  332.61  379.17  350.57     376  414.63     371  445.05  373.43
  453.89     382  492.87     383  550.38     401  710.05     401  762.46     395
  821.63     396 1020.55  393.09 1209.75     395 1252.02     393 1497.19     393
 1533.89     401 1555.38  400.11 1580.44     394 1699.44     393 1714.57  395.78
 1760.46     398 1963.98     403 1997.18     410 2054.22     427 2080.96     428
#Mann= 3 ,0,0
       0    .055       0  225.46     .03       0  550.38    .055       0
Levee=-1,0,426.02,-1,2063,426.02,,
#XS Ineff= 2 , 0
       0  225.46     397  550.38       0     401
Permanent Ineff=
       F       F
Bank Sta=225.46,550.38
XS Rating Curve= 0 ,0
Exp/Cntr=0.3,0.1

Type RM Length L Ch R = 1 ,110332  ,83,127,182
BEGIN DESCRIPTION:
This cross section corresponds to cross section 110342 of the non-georeferenced CDC model which was the source of this model.
END DESCRIPTION:
XS GIS Cut Line= 3
2492273.650655516962727.05494471 2491954.00004816962240.00014456
 2491112.69628456960949.94695038
#Sta/Elev= 30
       0     427   20.59     424  122.98     399  217.96  397.88  232.53     397
   273.2     388  345.31   384.3  354.28     379  393.01     372  428.56     371
  461.76  371.83  475.51     382  498.18  381.85  557.89     401  715.55  401.96
  787.93  395.11 1111.98     393 1320.06  393.47 1351.18  395.93 1375.77     393
 1507.71     393 1554.21     400 1586.49     401 1616.28     396 1735.57     394
 1774.34     398 1987.74     403  2072.1     422 2104.33     427 2122.72  426.78
#Mann= 3 ,0,0
       0    .055       0  217.96     .03       0  557.89    .055       0
Levee=-1,0,425.98,-1,2102,425.98,,
#XS Ineff= 2 , 0
       0  217.96  397.88  557.89       0     401
Permanent Ineff=
       F       F
Bank Sta=217.96,557.89
XS Rating Curve= 0 ,0
Exp/Cntr=0.3,0.1

Type RM Length L Ch R = 1 ,110205  ,82,126,180
BEGIN DESCRIPTION:
This cross section corresponds to cross section 110214 of the non-georeferenced CDC model which was the source of this model.
END DESCRIPTION:
XS GIS Cut Line= 2
2492370.806301096962707.303999962491321.99999976 6960805.0000618
#Sta/Elev= 30
       0     427   17.48     425    94.6     405   127.5     399  238.73     398
  288.37  388.12  366.33   384.4  377.02     379  415.66     372  472.98     371
  488.61   372.7  497.28     381  513.23     382  552.95  395.92  574.72     401
  769.77     401  828.38     395 1397.26     395 1421.82     393  1555.4     393
  1602.3  400.83 1624.53     400 1651.44  394.07 1673.26     394 1710.11     397
 2023.87     402  2095.7  415.53 2113.54     417 2155.88     427 2172.27     427
#Mann= 3 ,0,0
       0    .055       0  238.73     .03       0  574.72    .055       0
Levee=-1,0,425.94,-1,2155,425.94,,
#XS Ineff= 2 , 0
       0  238.73     398  574.72       0     401
Permanent Ineff=
       F       F
Bank Sta=238.73,574.72
XS Rating Curve= 0 ,0
Exp/Cntr=0.3,0.1

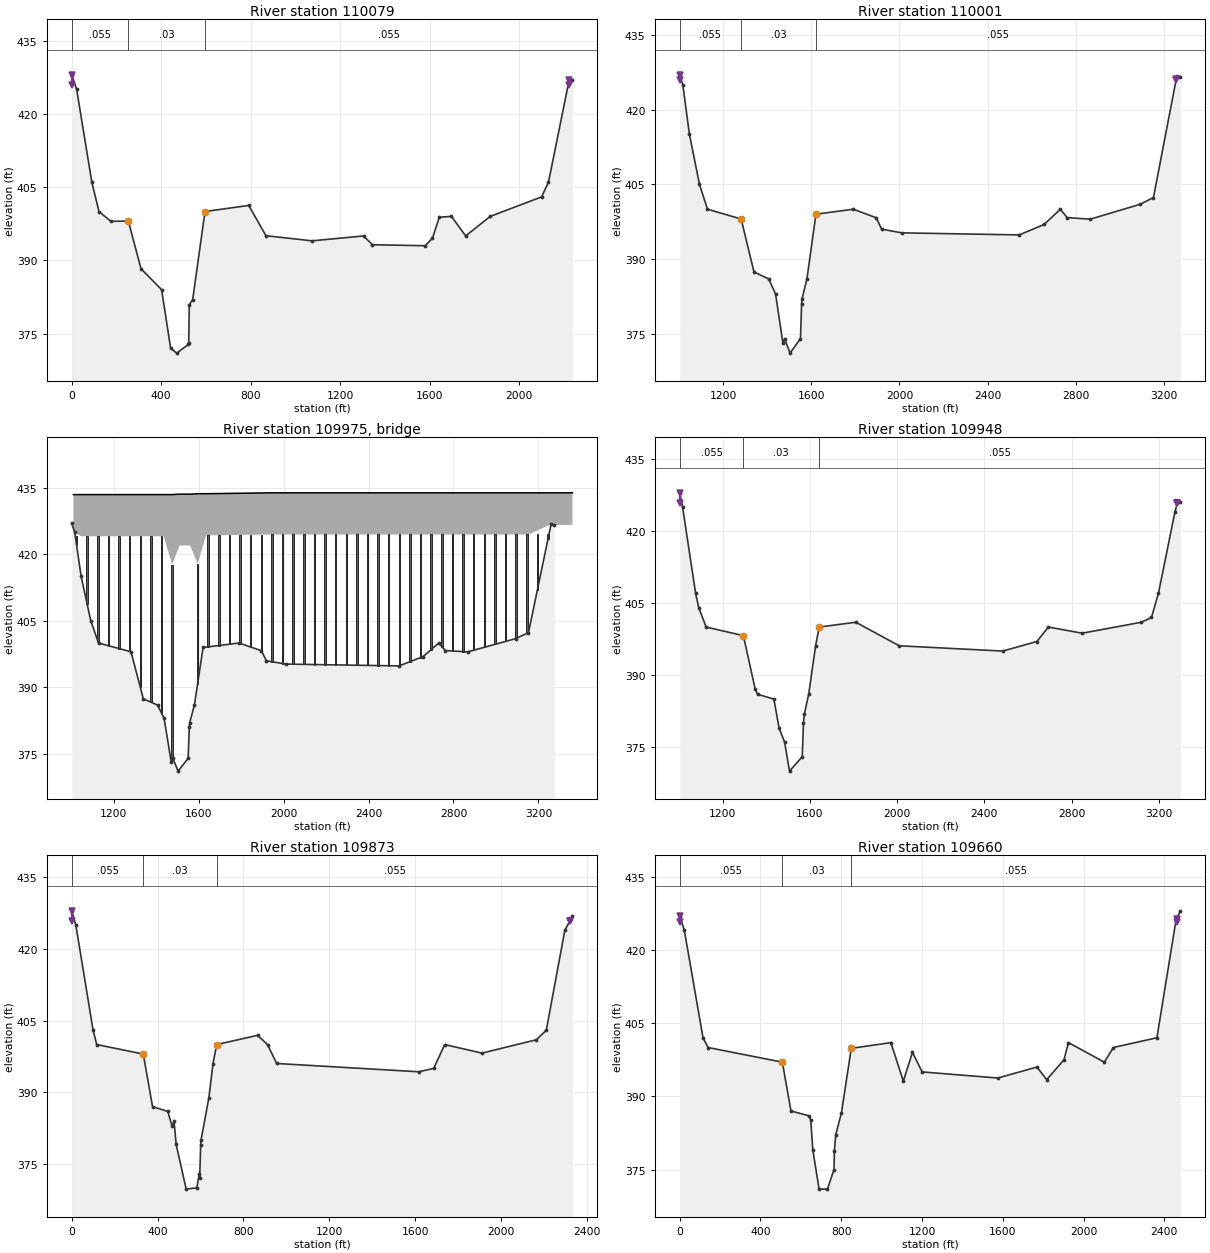
Type RM Length L Ch R = 1 ,110079  ,78,78,78
BEGIN DESCRIPTION:
This cross section corresponds to cross section 110086 of the non-georeferenced CDC model which was the source of this model.
END DESCRIPTION:
XS GIS Cut Line= 2
2492422.474504836962673.838843792491619.69691092 6960583.8312128
#Sta/Elev= 30
       0     428   22.26     425   90.05     406  121.96     400  175.23     398
  253.29  398.04     310  388.28  402.06     384  442.41     372   469.6     371
  521.76  372.79  523.34  373.16  525.73  380.93  540.81  381.91   596.1     400
  791.67  401.25  868.55  395.05  1074.6     394 1304.78     395 1344.65   393.2
 1579.86     393    1613  394.52 1643.71  398.84 1698.16     399 1761.62     395
 1871.26     399 2100.98     403  2131.9     406 2224.59     427 2238.88     427
#Mann= 3 ,0,0
       0    .055       0  253.29     .03       0   596.1    .055       0
Levee=-1,0,425.9,-1,2224,425.9,,
#XS Ineff= 2 , 0
       0  253.29  398.04   596.1       0     400
Permanent Ineff=
       F       F
Bank Sta=253.29,596.1
XS Rating Curve= 0 ,0
Exp/Cntr=0.3,0.1

Type RM Length L Ch R = 1 ,110001  ,53,53,53
BEGIN DESCRIPTION:
This cross section corresponds to cross section 110009 of the non-georeferenced CDC model which was the source of this model.
END DESCRIPTION:
XS GIS Cut Line= 2
2492491.390705596962643.413379712491677.178423266960520.85167997
#Sta/Elev= 30
    1002     427 1016.36     425 1046.22  415.07  1091.9     405 1128.31     400
 1281.15  398.03  1339.4   387.4 1406.18     386 1437.23     383 1470.85  373.08
 1478.25     374 1503.19  371.09 1550.51     374 1555.66     381 1557.54     382
 1579.84     386 1620.72     399 1790.26     400 1895.26  398.27 1918.69     396
  2010.5  395.25 2543.84  394.84  2656.8  396.94 2730.47     400 2761.18  398.31
 2866.68     398 3093.18     401 3153.12  402.35 3259.41  426.79 3275.37  426.66
#Mann= 3 ,0,0
    1002    .055       0 1281.15     .03       0 1620.72    .055       0
Levee=-1,1002,425.88,-1,3257,425.88,,
#XS Ineff= 2 , 0
       0 1281.15  398.03 1620.72       0     399
Permanent Ineff=
       F       F
Bank Sta=1281.15,1620.72
XS Rating Curve= 0 ,0
Exp/Cntr=0.3,0.1

Type RM Length L Ch R = 3 ,109975  ,,,
BEGIN DESCRIPTION:
109983  Corinth Street
END DESCRIPTION:
Node Name=Corinth Street
Bridge Culvert--1,0,-1,-1, 0
Deck Dist Width WeirC Skew NumUp NumDn MinLoCord MaxHiCord MaxSubmerge Is_Ogee
1.5,50,2.6,0, 9, 9, , , 0.95, 0, ,,,
    1010    1435    1475    1510    1560    1595    1635    1945    3360
   433.5   433.5   433.5   433.6   433.6   433.7   433.7   433.9   433.9
   424.1   424.1   417.7     422     422   417.9   424.3   424.5   424.5
    1010    1435    1475    1510    1560    1595    1635    1945    3360
   433.5   433.5   433.5   433.6   433.6   433.7   433.7   433.9   433.9
   424.1   424.1   417.7     422     422   417.9   424.3   424.5   424.5
Pier Skew, UpSta & Num, DnSta & Num=  ,1025, 5 ,1025, 5 , 3 , 3 , 0 ,,
       5     2.5     3.7     3.7       7
     390   420.8   420.8   422.3   424.1
       5     2.5     3.7     3.7       7
     390   420.8   420.8   422.3   424.1
Pier Skew, UpSta & Num, DnSta & Num=  ,1075, 5 ,1075, 5 , 3 , 3 , 0 ,,
       5     2.5     3.7     3.7       7
     390   420.8   420.8   422.3   424.1
       5     2.5     3.7     3.7       7
     390   420.8   420.8   422.3   424.1
Pier Skew, UpSta & Num, DnSta & Num=  ,1125, 5 ,1125, 5 , 3 , 3 , 0 ,,
       5     2.5     3.7     3.7       7
     390   420.8   420.8   422.3   424.1
       5     2.5     3.7     3.7       7
     390   420.8   420.8   422.3   424.1
Pier Skew, UpSta & Num, DnSta & Num=  ,1175, 5 ,1175, 5 , 3 , 3 , 0 ,,
       5     2.5     3.7     3.7       7
     390   420.8   420.8   422.3   424.1
       5     2.5     3.7     3.7       7
     390   420.8   420.8   422.3   424.1
Pier Skew, UpSta & Num, DnSta & Num=  ,1225, 5 ,1225, 5 , 3 , 3 , 0 ,,
       5     2.5     3.7     3.7       7
     390   420.8   420.8   422.3   424.1
       5     2.5     3.7     3.7       7
     390   420.8   420.8   422.3   424.1
Pier Skew, UpSta & Num, DnSta & Num=  ,1275, 5 ,1275, 5 , 3 , 3 , 0 ,,
       5     2.5     3.7     3.7       7
     390   420.8   420.8   422.3   424.1
       5     2.5     3.7     3.7       7
     390   420.8   420.8   422.3   424.1
Pier Skew, UpSta & Num, DnSta & Num=  ,1325, 5 ,1325, 5 , 3 , 3 , 0 ,,
       5     2.5     3.7     3.7       7
     390   420.8   420.8   422.3   424.1
       5     2.5     3.7     3.7       7
     390   420.8   420.8   422.3   424.1
Pier Skew, UpSta & Num, DnSta & Num=  ,1375, 5 ,1375, 5 , 3 , 3 , 0 ,,
       5     2.5     3.7     3.7       7
     390   420.8   420.8   422.3   424.1
       5     2.5     3.7     3.7       7
     390   420.8   420.8   422.3   424.1
Pier Skew, UpSta & Num, DnSta & Num=  ,1425, 5 ,1425, 5 , 3 , 3 , 0 ,,
       5     2.5     3.7     3.7       7
     390   420.8   420.8   422.3   424.1
       5     2.5     3.7     3.7       7
     390   420.8   420.8   422.3   424.1
Pier Skew, UpSta & Num, DnSta & Num=  ,1475, 6 ,1475, 6 , 5 , 5 , 0 ,,
       8       8       6     3.4       5       5
     380   392.5   392.5   413.7   413.7     423
       8       8       6     3.4       5       5
     380   392.5   392.5   413.7   413.7     423
Pier Skew, UpSta & Num, DnSta & Num=  ,1595, 6 ,1595, 6 , 5 , 5 , 0 ,,
       8       8       6     3.4       5       5
     380   392.5   392.5   413.7   413.7     423
       8       8       6     3.4       5       5
     380   392.5   392.5   413.7   413.7     423
Pier Skew, UpSta & Num, DnSta & Num=  ,1645, 5 ,1645, 5 , 3 , 3 , 0 ,,
       5     2.5     3.7     3.7       7
     390   421.2   421.2   422.7   424.5
       5     2.5     3.7     3.7       7
     390   421.2   421.2   422.7   424.5
Pier Skew, UpSta & Num, DnSta & Num=  ,1695, 5 ,1695, 5 , 3 , 3 , 0 ,,
       5     2.5     3.7     3.7       7
     390   421.2   421.2   422.7   424.5
       5     2.5     3.7     3.7       7
     390   421.2   421.2   422.7   424.5
Pier Skew, UpSta & Num, DnSta & Num=  ,1745, 5 ,1745, 5 , 3 , 3 , 0 ,,
       5     2.5     3.7     3.7       7
     390   421.2   421.2   422.7   424.5
       5     2.5     3.7     3.7       7
     390   421.2   421.2   422.7   424.5
Pier Skew, UpSta & Num, DnSta & Num=  ,1795, 5 ,1795, 5 , 3 , 3 , 0 ,,
       5     2.5     3.7     3.7       7
     390   421.2   421.2   422.7   424.5
       5     2.5     3.7     3.7       7
     390   421.2   421.2   422.7   424.5
Pier Skew, UpSta & Num, DnSta & Num=  ,1845, 5 ,1845, 5 , 3 , 3 , 0 ,,
       5     2.5     3.7     3.7       7
     390   421.2   421.2   422.7   424.5
       5     2.5     3.7     3.7       7
     390   421.2   421.2   422.7   424.5
Pier Skew, UpSta & Num, DnSta & Num=  ,1895, 5 ,1895, 5 , 3 , 3 , 0 ,,
       5     2.5     3.7     3.7       7
     390   421.2   421.2   422.7   424.5
       5     2.5     3.7     3.7       7
     390   421.2   421.2   422.7   424.5
Pier Skew, UpSta & Num, DnSta & Num=  ,1945, 5 ,1945, 5 , 3 , 3 , 0 ,,
       5     2.5     3.7     3.7       7
     390   421.2   421.2   422.7   424.5
       5     2.5     3.7     3.7       7
     390   421.2   421.2   422.7   424.5
Pier Skew, UpSta & Num, DnSta & Num=  ,1995, 5 ,1995, 5 , 3 , 3 , 0 ,,
       5     2.5     3.7     3.7       7
     390   421.2   421.2   422.7   424.5
       5     2.5     3.7     3.7       7
     390   421.2   421.2   422.7   424.5
Pier Skew, UpSta & Num, DnSta & Num=  ,2045, 5 ,2045, 5 , 3 , 3 , 0 ,,
       5     2.5     3.7     3.7       7
     390   421.2   421.2   422.7   424.5
       5     2.5     3.7     3.7       7
     390   421.2   421.2   422.7   424.5
Pier Skew, UpSta & Num, DnSta & Num=  ,2095, 5 ,2095, 5 , 3 , 3 , 0 ,,
       5     2.5     3.7     3.7       7
     390   421.2   421.2   422.7   424.5
       5     2.5     3.7     3.7       7
     390   421.2   421.2   422.7   424.5
Pier Skew, UpSta & Num, DnSta & Num=  ,2145, 5 ,2145, 5 , 3 , 3 , 0 ,,
       5     2.5     3.7     3.7       7
     390   421.2   421.2   422.7   424.5
       5     2.5     3.7     3.7       7
     390   421.2   421.2   422.7   424.5
Pier Skew, UpSta & Num, DnSta & Num=  ,2195, 5 ,2195, 5 , 3 , 3 , 0 ,,
       5     2.5     3.7     3.7       7
     390   421.2   421.2   422.7   424.5
       5     2.5     3.7     3.7       7
     390   421.2   421.2   422.7   424.5
Pier Skew, UpSta & Num, DnSta & Num=  ,2245, 5 ,2245, 5 , 3 , 3 , 0 ,,
       5     2.5     3.7     3.7       7
     390   421.2   421.2   422.7   424.5
       5     2.5     3.7     3.7       7
     390   421.2   421.2   422.7   424.5
Pier Skew, UpSta & Num, DnSta & Num=  ,2295, 5 ,2295, 5 , 3 , 3 , 0 ,,
       5     2.5     3.7     3.7       7
     390   421.2   421.2   422.7   424.5
       5     2.5     3.7     3.7       7
     390   421.2   421.2   422.7   424.5
Pier Skew, UpSta & Num, DnSta & Num=  ,2345, 5 ,2345, 5 , 3 , 3 , 0 ,,
       5     2.5     3.7     3.7       7
     390   421.2   421.2   422.7   424.5
       5     2.5     3.7     3.7       7
     390   421.2   421.2   422.7   424.5
Pier Skew, UpSta & Num, DnSta & Num=  ,2395, 5 ,2395, 5 , 3 , 3 , 0 ,,
       5     2.5     3.7     3.7       7
     390   421.2   421.2   422.7   424.5
       5     2.5     3.7     3.7       7
     390   421.2   421.2   422.7   424.5
Pier Skew, UpSta & Num, DnSta & Num=  ,2445, 5 ,2445, 5 , 3 , 3 , 0 ,,
       5     2.5     3.7     3.7       7
     390   421.2   421.2   422.7   424.5
       5     2.5     3.7     3.7       7
     390   421.2   421.2   422.7   424.5
Pier Skew, UpSta & Num, DnSta & Num=  ,2495, 5 ,2495, 5 , 3 , 3 , 0 ,,
       5     2.5     3.7     3.7       7
     390   421.2   421.2   422.7   424.5
       5     2.5     3.7     3.7       7
     390   421.2   421.2   422.7   424.5
Pier Skew, UpSta & Num, DnSta & Num=  ,2545, 5 ,2545, 5 , 3 , 3 , 0 ,,
       5     2.5     3.7     3.7       7
     390   421.2   421.2   422.7   424.5
       5     2.5     3.7     3.7       7
     390   421.2   421.2   422.7   424.5
Pier Skew, UpSta & Num, DnSta & Num=  ,2595, 5 ,2595, 5 , 3 , 3 , 0 ,,
       5     2.5     3.7     3.7       7
     390   421.2   421.2   422.7   424.5
       5     2.5     3.7     3.7       7
     390   421.2   421.2   422.7   424.5
Pier Skew, UpSta & Num, DnSta & Num=  ,2645, 5 ,2645, 5 , 3 , 3 , 0 ,,
       5     2.5     3.7     3.7       7
     390   421.2   421.2   422.7   424.5
       5     2.5     3.7     3.7       7
     390   421.2   421.2   422.7   424.5
Pier Skew, UpSta & Num, DnSta & Num=  ,2695, 5 ,2695, 5 , 3 , 3 , 0 ,,
       5     2.5     3.7     3.7       7
     390   421.2   421.2   422.7   424.5
       5     2.5     3.7     3.7       7
     390   421.2   421.2   422.7   424.5
Pier Skew, UpSta & Num, DnSta & Num=  ,2745, 5 ,2745, 5 , 3 , 3 , 0 ,,
       5     2.5     3.7     3.7       7
     390   421.2   421.2   422.7   424.5
       5     2.5     3.7     3.7       7
     390   421.2   421.2   422.7   424.5
Pier Skew, UpSta & Num, DnSta & Num=  ,2795, 5 ,2795, 5 , 3 , 3 , 0 ,,
       5     2.5     3.7     3.7       7
     390   421.2   421.2   422.7   424.5
       5     2.5     3.7     3.7       7
     390   421.2   421.2   422.7   424.5
Pier Skew, UpSta & Num, DnSta & Num=  ,2845, 5 ,2845, 5 , 3 , 3 , 0 ,,
       5     2.5     3.7     3.7       7
     390   421.2   421.2   422.7   424.5
       5     2.5     3.7     3.7       7
     390   421.2   421.2   422.7   424.5
Pier Skew, UpSta & Num, DnSta & Num=  ,2895, 5 ,2895, 5 , 3 , 3 , 0 ,,
       5     2.5     3.7     3.7       7
     390   421.2   421.2   422.7   424.5
       5     2.5     3.7     3.7       7
     390   421.2   421.2   422.7   424.5
Pier Skew, UpSta & Num, DnSta & Num=  ,2945, 5 ,2945, 5 , 3 , 3 , 0 ,,
       5     2.5     3.7     3.7       7
     390   421.2   421.2   422.7   424.5
       5     2.5     3.7     3.7       7
     390   421.2   421.2   422.7   424.5
Pier Skew, UpSta & Num, DnSta & Num=  ,2995, 5 ,2995, 5 , 3 , 3 , 0 ,,
       5     2.5     3.7     3.7       7
     390   421.2   421.2   422.7   424.5
       5     2.5     3.7     3.7       7
     390   421.2   421.2   422.7   424.5
Pier Skew, UpSta & Num, DnSta & Num=  ,3045, 5 ,3045, 5 , 3 , 3 , 0 ,,
       5     2.5     3.7     3.7       7
     390   421.2   421.2   422.7   424.5
       5     2.5     3.7     3.7       7
     390   421.2   421.2   422.7   424.5
Pier Skew, UpSta & Num, DnSta & Num=  ,3095, 5 ,3095, 5 , 3 , 3 , 0 ,,
       5     2.5     3.7     3.7       7
     390   421.2   421.2   422.7   424.5
       5     2.5     3.7     3.7       7
     390   421.2   421.2   422.7   424.5
Pier Skew, UpSta & Num, DnSta & Num=  ,3145, 5 ,3145, 5 , 3 , 3 , 0 ,,
       5     2.5     3.7     3.7       7
     390   421.2   421.2   422.7   424.5
       5     2.5     3.7     3.7       7
     390   421.2   421.2   422.7   424.5
Pier Skew, UpSta & Num, DnSta & Num=  ,3195, 5 ,3195, 5 , 3 , 3 , 0 ,,
       5     2.5     3.7     3.7       7
     390   421.2   421.2   422.7   424.5
       5     2.5     3.7     3.7       7
     390   421.2   421.2   422.7   424.5
Pier Skew, UpSta & Num, DnSta & Num=  ,3245, 5 ,3245, 5 , 3 , 3 , 0 ,,
       5     2.5     3.7     3.7       7
     390   421.2   421.2   422.7   424.5
       5     2.5     3.7     3.7       7
     390   421.2   421.2   422.7   424.5
Pier Skew, UpSta & Num, DnSta & Num=  ,3295, 5 ,3295, 5 , 3 , 3 , 0 ,,
       5     2.5     3.7     3.7       7
     390   421.2   421.2   422.7   424.5
       5     2.5     3.7     3.7       7
     390   421.2   421.2   422.7   424.5
BR Coef= 1 , 1 , 1 ,0.9, 0 ,,,0.8,0,1.33,1,
WSPro=,,,, 1 ,,,, 0 ,,,, 0 ,,,,-1 ,-1 ,-1 , 0 , 0 , 0 , 0 , 0
BC Design=,, 0 ,, 0 ,,,,,,
BC HTab HWMax=426.2
BC Use User HTab Curves=0
BC User HTab FreeFlow(D)= 0

Type RM Length L Ch R = 1 ,109948  ,75,75,75
BEGIN DESCRIPTION:
This cross section corresponds to cross section 109957 of the non-georeferenced CDC model which was the source of this model.
END DESCRIPTION:
XS GIS Cut Line= 2
2492542.255433266962633.059069722491719.313509586960488.20574789
#Sta/Elev= 30
    1002  427.95 1015.38     425 1075.24     407 1089.84     404 1123.41     400
 1294.33  398.21 1348.85     387  1359.4     386 1434.28     385 1458.07     379
 1483.61     376 1505.96     370 1564.33     373 1570.07     380 1574.02  381.87
 1593.94     386 1625.33     396 1642.13     400 1810.02     401 2009.38   396.1
 2484.08     395 2640.93  396.99 2693.53     400 2848.89  398.72 3120.04     401
 3166.62  401.99 3198.53     407 3274.52     424 3286.41     426 3299.31     426
#Mann= 3 ,0,0
    1002    .055       0 1294.33     .03       0 1642.13    .055       0
Levee=-1,1002,425.86,-1,3286,425.86,,
#XS Ineff= 2 , 0
       0 1294.33  398.21 1642.13       0     400
Permanent Ineff=
       F       F
Bank Sta=1294.33,1642.13
XS Rating Curve= 0 ,0
Exp/Cntr=0.3,0.1

Type RM Length L Ch R = 1 ,109873  ,231,213,176
BEGIN DESCRIPTION:
This cross section corresponds to cross section 109882 of the non-georeferenced CDC model which was the source of this model.
END DESCRIPTION:
XS GIS Cut Line= 2
2492620.142744666962632.977376972491784.024338196960454.69466005
#Sta/Elev= 30
       0     428   19.41     425   99.42  403.07  116.67     400   333.5  398.01
   376.8     387  447.63     386  467.11     383  477.05  383.89  486.59  379.12
  533.43  369.73  583.22     370   594.4     373  596.35     372  601.04     379
  602.67     380  639.09  388.81   658.5     396  675.48     400  865.96  401.93
  912.49     400  954.97  396.04  1616.7   394.3 1686.75     395 1738.26     400
 1911.67  398.21 2165.25     401 2211.56     403 2297.87  423.92 2333.24  426.84
#Mann= 3 ,0,0
       0    .055       0   333.5     .03       0  675.48    .055       0
Levee=-1,0,425.82,-1,2322,425.82,,
#XS Ineff= 2 , 0
       0   333.5  398.01  675.48       0     400
Permanent Ineff=
       F       F
Bank Sta=333.5,675.48
XS Rating Curve= 0 ,0
Exp/Cntr=0.3,0.1

Type RM Length L Ch R = 1 ,109660  ,231,213,176
BEGIN DESCRIPTION:
This cross section corresponds to cross section 109670 of the non-georeferenced CDC model which was the source of this model.
END DESCRIPTION:
XS GIS Cut Line= 2
2492905.195652256962654.681729882491854.341782846960408.57204889
#Sta/Elev= 30
       0     427   23.09     424  115.59     402  140.53     400  508.52     397
  551.25     387  641.18     386  649.12  385.12  659.45     379  690.52     371
  731.94  370.99  764.29     375  766.42  378.88  773.05  382.14  801.33  386.65
  849.85  399.83 1046.08     401 1107.54  393.11 1152.94     399 1200.96     395
 1575.58  393.75  1769.1     396 1817.95  393.42 1903.17  397.49 1925.58     401
 2103.16     397    2148     400 2363.53     402 2457.85     426 2479.78     428
#Mann= 3 ,0,0
       0    .055       0  508.52     .03       0  849.85    .055       0
Levee=-1,0,425.72,-1,2462,425.72,,
#XS Ineff= 2 , 0
       0  508.52     397  849.85       0  399.83
Permanent Ineff=
       F       F
Bank Sta=508.52,849.85
XS Rating Curve= 0 ,0
Exp/Cntr=0.3,0.1

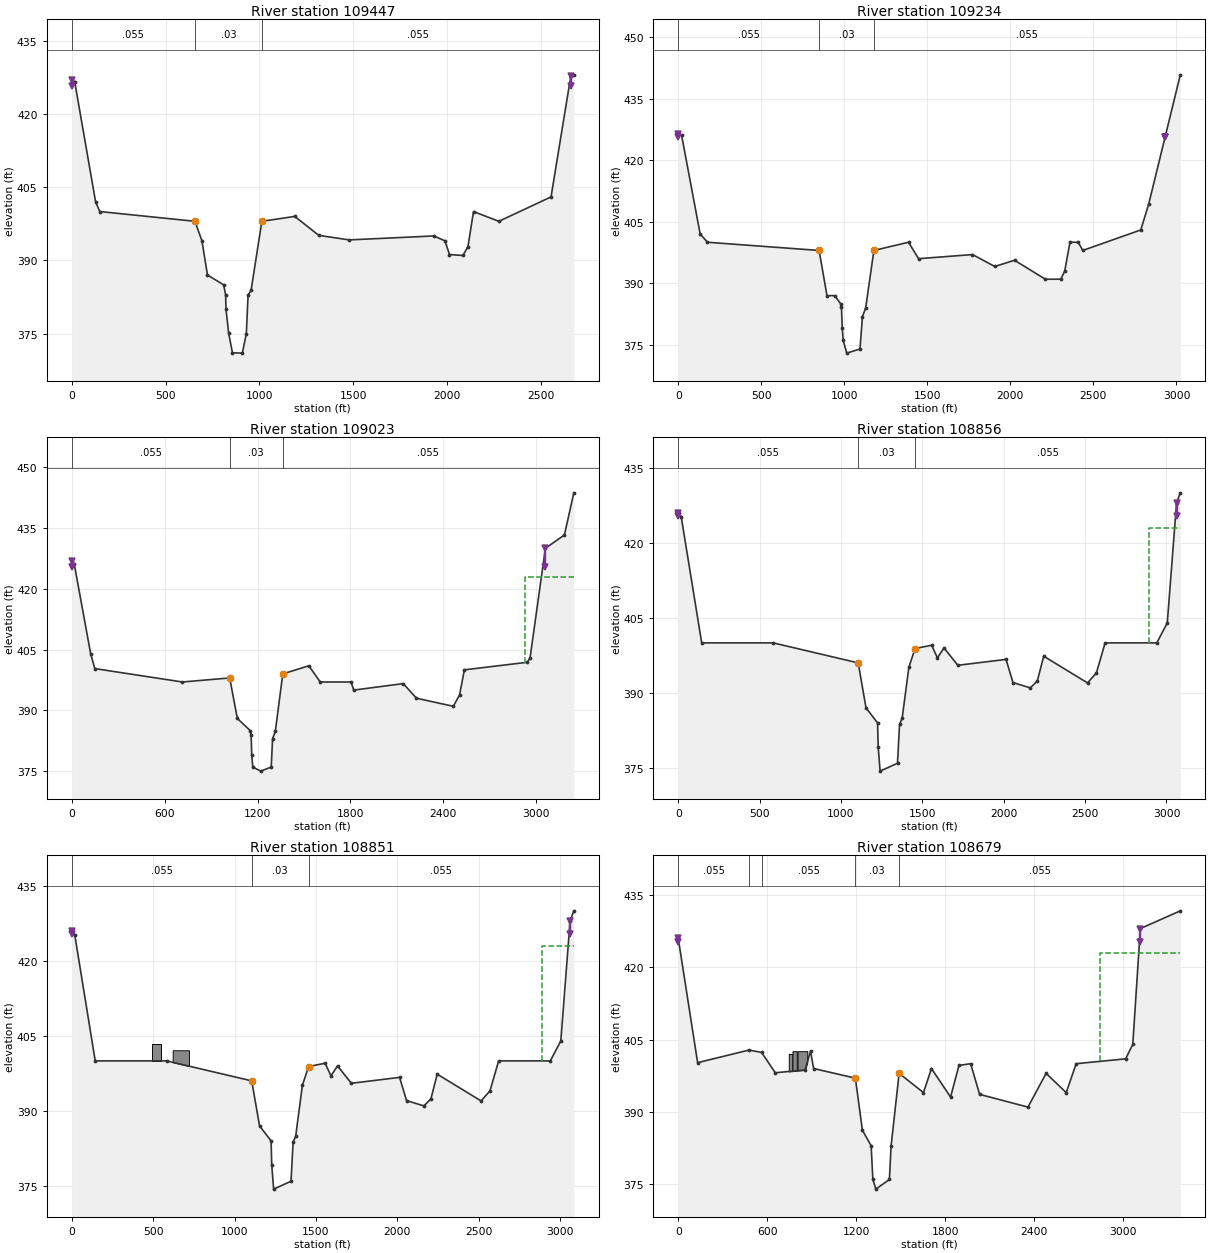
Type RM Length L Ch R = 1 ,109447  ,232,213,176
BEGIN DESCRIPTION:
This cross section corresponds to cross section 109458 of the non-georeferenced CDC model which was the source of this model.
END DESCRIPTION:
XS GIS Cut Line= 2
2493198.825642446962658.793598292491918.763898076960309.75728588
#Sta/Elev= 30
       0     427   15.82  426.54  126.74  402.03  149.15     400  656.19     398
  693.56     394  723.09     387  808.96     385  819.61     383  821.83     380
  835.73  375.12  856.25  371.06  908.76     371  930.15     375  939.28  382.82
  955.66  383.93 1012.86     398 1188.31     399 1316.13  395.12 1478.36  394.19
 1929.16     395 1988.41     394 2012.55  391.19 2084.21     391 2111.08  392.83
 2140.55     400 2275.59     398 2553.68     403 2659.19  427.79 2675.17     428
#Mann= 3 ,0,0
       0    .055       0  656.19     .03       0 1012.86    .055       0
Levee=-1,0,425.62,-1,2659,425.62,,
#XS Ineff= 2 , 0
       0  656.19     398 1012.86       0     398
Permanent Ineff=
       F       F
Bank Sta=656.19,1012.86
XS Rating Curve= 0 ,0
Exp/Cntr=0.3,0.1

Type RM Length L Ch R = 1 ,109234  ,230,211,175
BEGIN DESCRIPTION:
This cross section corresponds to cross section 109246 of the non-georeferenced CDC model which was the source of this model.
END DESCRIPTION:
XS GIS Cut Line= 2
2493510.549428436962669.136425382491925.412834916960094.93127197
#Sta/Elev= 30
       0  426.39   20.45     426  132.06     402  176.17     400  848.29     398
   895.6     387  942.46     387   978.3     385   982.8  384.12  987.74     379
  993.38  376.08 1014.54     373 1094.32     374 1109.23  381.89 1128.58     384
 1178.06     398 1386.52     400 1447.14     396  1771.8     397 1906.11   394.1
 2025.01  395.62 2210.26     391 2303.15     391 2326.86  392.95 2358.69     400
 2408.66     400 2435.75     398  2785.2     403 2833.26  409.37 3023.11  440.77
#Mann= 3 ,0,0
       0    .055       0  848.29     .03       0 1178.06    .055       0
Levee=-1,0,425.51,-1,2932,425.51,,
#XS Ineff= 2 , 0
       0  848.29     398 1178.06       0     398
Permanent Ineff=
       F       F
Bank Sta=848.29,1178.06
XS Rating Curve= 0 ,0
Exp/Cntr=0.3,0.1

Type RM Length L Ch R = 1 ,109023  ,148,167,157
BEGIN DESCRIPTION:
This cross section corresponds to cross section 109035 of the non-georeferenced CDC model which was the source of this model.
END DESCRIPTION:
XS GIS Cut Line= 3
2493815.362795176962659.379227042493793.999976996962623.00003472
2491990.779502096959977.57586363
#Sta/Elev= 30
       0  426.95   16.59     426  121.93     404  148.86  400.31   714.7     397
 1020.35     398  1069.6     388 1153.07     385  1158.5     384 1162.61     379
 1169.42     376  1220.8     375 1288.59     376 1297.33     383 1315.02   384.8
  1363.3     399 1531.38     401 1605.51     397 1804.41     397 1821.45     395
 2141.84   396.6 2226.78     393 2464.99     391 2505.44  393.82 2536.56     400
  2943.7  401.87 2961.02     403    3060     430 3182.61  433.29 3243.73  443.69
#Mann= 3 ,0,0
       0    .055       0 1020.35     .03       0  1363.3    .055       0
Levee=-1,0,425.41,-1,3060,425.41,,
#XS Ineff= 1 ,-1
    2930 3243.73     423
Permanent Ineff=
       T
Bank Sta=1020.35,1363.3
XS Rating Curve= 0 ,0
Exp/Cntr=0.3,0.1

Type RM Length L Ch R = 1 ,108856  ,5,5,5
BEGIN DESCRIPTION:
This cross section corresponds to cross section 108871 of the non-georeferenced CDC model which was the source of this model.
---------------------------------------------------------------------
CDC DAL010909-1 Sante Fe Trestle Trail
Cross-section added.
Upstream limit.
---------------------------------------------------------------------
END DESCRIPTION:
XS GIS Cut Line= 3
 2493943.39567566962652.621038472493166.999918676961391.00020213
2492307.19192702 6960037.3618333
#Sta/Elev= 30
       0     426   18.11  425.25  144.14     400  583.37     400 1105.75     396
 1153.84     387 1224.89     384 1228.59  379.21 1240.46  374.36 1347.29  375.94
 1359.87  383.71 1375.82  384.92 1417.07  395.12  1455.3  398.87 1557.07  399.53
  1592.5     397 1632.98     399 1717.94  395.52 2014.17   396.7 2056.96  392.07
 2163.28     391 2206.56  392.39 2245.54  397.34 2514.92     392 2569.57     394
 2622.92     400 2940.54     400    3005     404    3062     428    3085     430
#Mann= 3 ,0,0
       0    .055       0 1105.75     .03       0  1455.3    .055       0
Levee=-1,0,425.36,-1,3062,425.36,,
#XS Ineff= 1 ,-1
    2895    3085     423
Permanent Ineff=
       T
Bank Sta=1105.75,1455.3
XS Rating Curve= 0 ,0
Exp/Cntr=0.3,0.1

Type RM Length L Ch R = 1 ,108851  ,153,172,162
BEGIN DESCRIPTION:
This cross section corresponds to cross section 108866 of the non-georeferenced CDC model which was the source of this model.
Cross-section modified for CDC DAL010909-1 Sante Fe Trestle Trail.
END DESCRIPTION:
XS GIS Cut Line= 3
2493948.82643899 6962644.72669732493261.488246776961534.47137189
2492309.043301256960031.66761896
#Sta/Elev= 30
       0     426   18.11  425.25  144.14     400  583.37     400 1105.75     396
 1153.84     387 1224.89     384 1228.59  379.21 1240.46  374.36 1347.29  375.94
 1359.87  383.71 1375.82  384.92 1417.07  395.12  1455.3  398.87 1557.07  399.53
  1592.5     397 1632.98     399 1717.94  395.52 2014.17   396.7 2056.96  392.07
 2163.28     391 2206.56  392.39 2245.54  397.34 2514.92     392 2569.57     394
 2622.92     400 2940.54     400    3005     404    3062     428    3085     430
#Mann= 3 ,-1,0
       0    .055       0 1105.75     .03       0  1455.3    .055       0
Levee=-1,0,425.36,-1,3062,425.36,,
#XS Ineff= 1 ,-1
    2890    3085     423
Permanent Ineff=
       T
#Block Obstruct= 2 ,-1
     490     550  403.31     620     720  402.12
Bank Sta=1105.75,1455.3
XS Rating Curve= 0 ,0
Exp/Cntr=0.3,0.1

Type RM Length L Ch R = 1 ,108679  ,4,4,4
BEGIN DESCRIPTION:
This cross section corresponds to cross section 108698  of the non-georeferenced CDC model which was the source of this model.
Cross-section modified for CDC DAL010909-1 Sante Fe Trestle Trail.
END DESCRIPTION:
XS GIS Cut Line= 4
2494074.208734186962639.940617642493331.999916766961308.00004005
2492486.999966356960225.000237552492217.424061926959820.63621688
#Sta/Elev= 30
       0     426  130.76  400.21  476.53  402.82  561.53  402.34   654.3  398.12
  855.07   398.7  891.65  402.59  912.65     399 1194.03     397 1241.45   386.2
 1300.32     383 1311.88     376  1332.1     374 1423.42     376    1435     383
 1489.03     398 1653.19     394 1706.92     399 1835.84  393.08 1892.27  399.64
 1971.05     400 2031.41  393.64 2357.64     391 2479.73     398 2615.16     394
 2682.55     400 3015.81     401    3064     404    3115     428 3384.41  431.68
#Mann= 5 ,-1,0
       0    .055       0  476.53     .03       0  561.53    .055       0
 1194.03     .03       0 1489.03    .055       0
Levee=-1,0,425.32,-1,3115,425.32,,
#XS Ineff= 1 ,-1
    2845 3384.41     423
Permanent Ineff=
       T
#Block Obstruct= 3 ,-1
     745     770     402     770  798.74  402.59  804.32     870  402.59
Bank Sta=1194.03,1489.03
XS Rating Curve= 0 ,0
Exp/Cntr=0.3,0.1