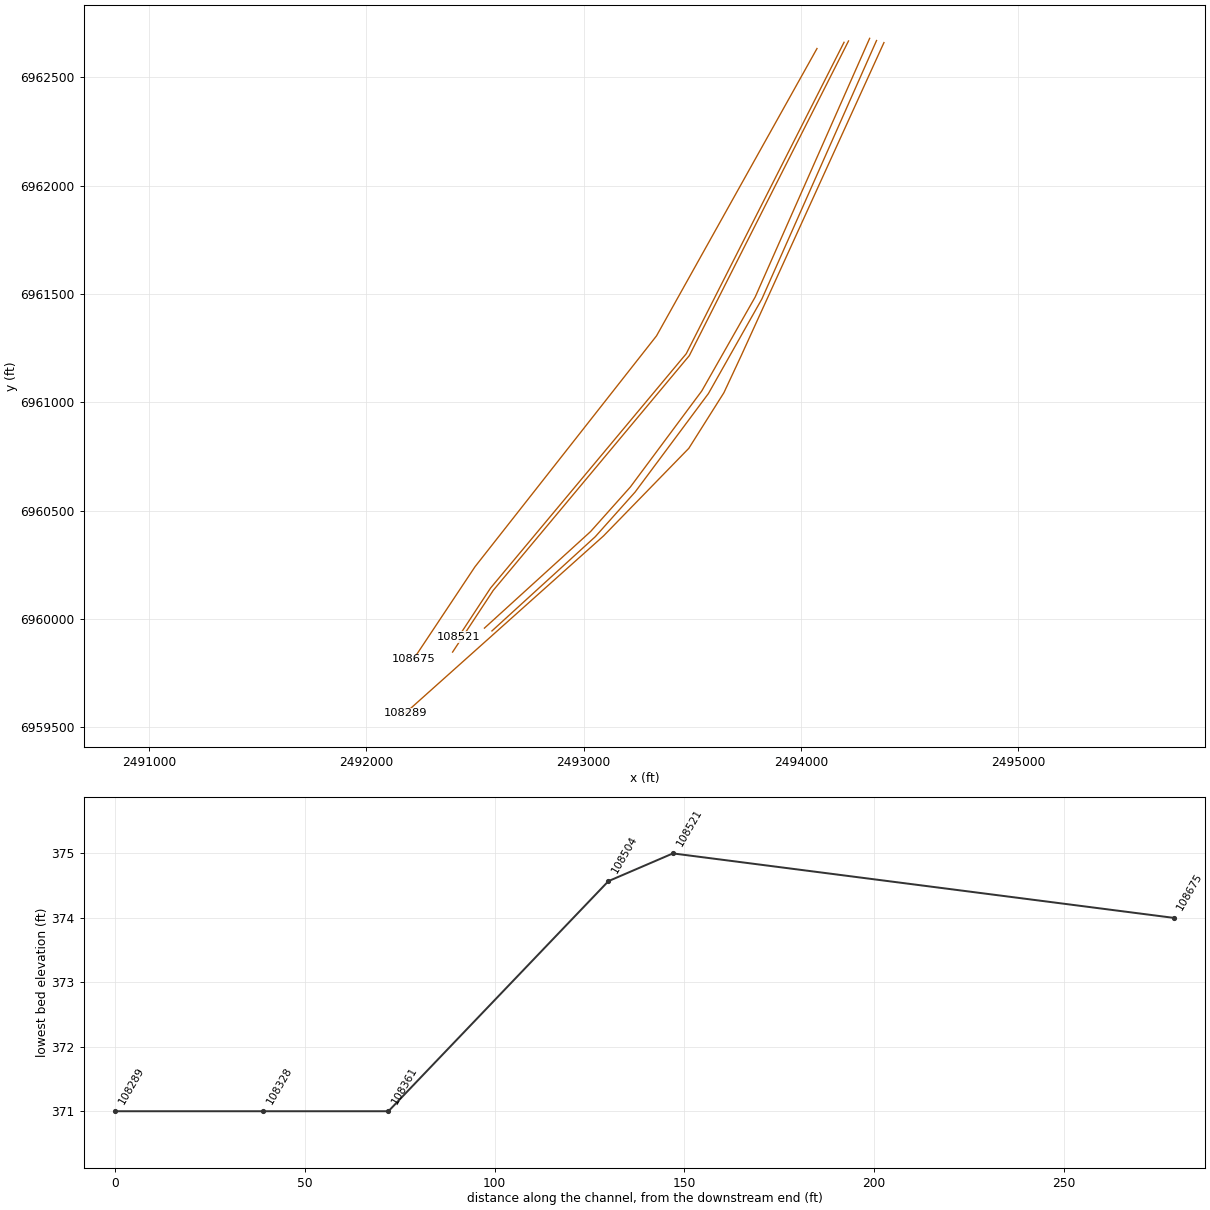
HEC-RAS study CDC_Consolidated_Model.prj: Upper Trinity CDC Consolidated Model

--- CDC_Consolidated_Model.g02 (geometry) --- (continued)

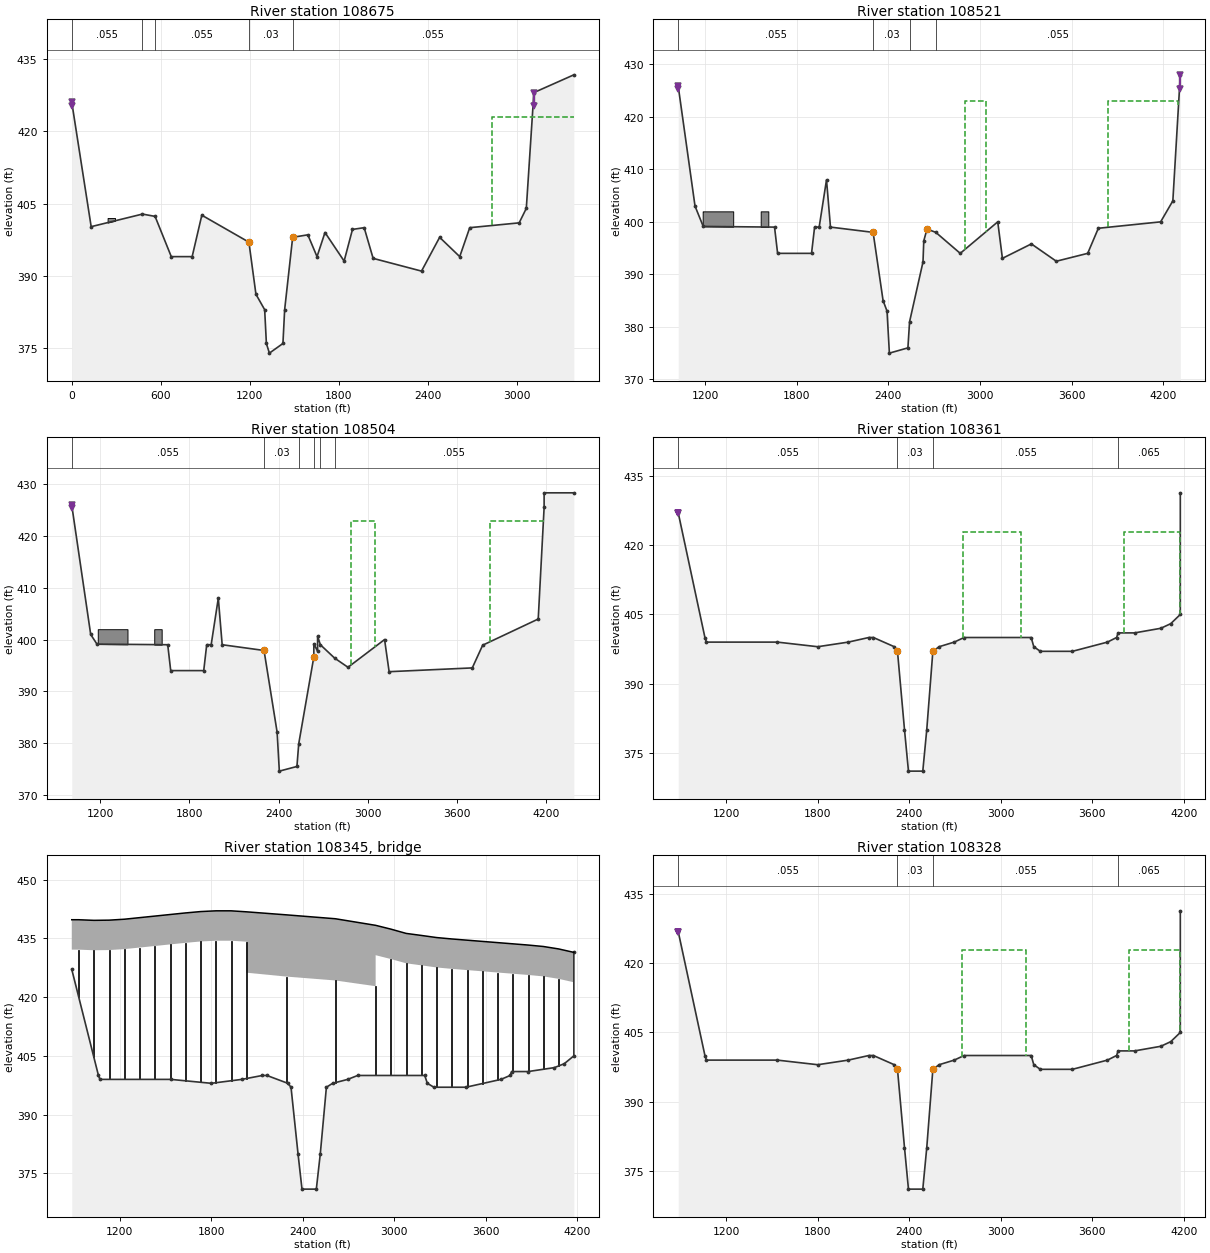
Type RM Length L Ch R = 1 ,108675  ,117,132,124
BEGIN DESCRIPTION:
This cross section corresponds to cross section 108688  of the non-georeferenced CDC model which was the source of this model.
Cross-section modified for CDC DAL010909-1 Sante Fe Trestle Trail.
END DESCRIPTION:
XS GIS Cut Line= 4
2494074.720872256962632.51412331 2493336.20200816961306.42195922
2492500.419887016960240.369957462492217.524783496959813.71923597
#Sta/Elev= 30
       0     426  130.76  400.21  476.53  402.82  561.53  402.34  670.78     394
  811.53     394  876.65  402.59 1194.03     397 1241.45   386.2 1300.32     383
 1311.88     376  1332.1     374 1423.42     376    1435     383 1489.03     398
 1591.23  398.52 1653.19     394 1706.92     399 1835.84  393.08 1892.27  399.64
 1971.05     400 2031.41  393.64 2357.64     391 2479.73     398 2615.16     394
 2682.55     400 3015.81     401    3064     404    3115     428 3384.41  431.68
#Mann= 5 ,-1,0
       0    .055       0  476.53     .03       0  561.53    .055       0
 1194.03     .03       0 1489.03    .055       0
Levee=-1,0,425.32,-1,3115,425.32,,
#XS Ineff= 1 ,-1
    2835 3384.41     423
Permanent Ineff=
       T
#Block Obstruct= 1 ,-1
  241.53  291.53     402
Bank Sta=1194.03,1489.03
XS Rating Curve= 0 ,0
Exp/Cntr=0.3,0.1

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
Type RM Length L Ch R = 1 ,108521  ,18,17,17
BEGIN DESCRIPTION:
This cross section corresponds to cross section 108530.  of the non-georeferenced CDC model which was the source of this model.
Cross-section modified for CDC DAL010909-1 Sante Fe Trestle Trail.
Cross-section modified for CDC DAL090508-1 Standing Wave Park.
END DESCRIPTION:
XS GIS Cut Line= 5
  2494199.2157026962661.280469972493472.999962846961224.00020805
2492572.000124426960142.000075462492424.176929276959916.37487055
2492424.176929276959916.37487055
#Sta/Elev= 30
    1024  425.82 1133.95     403 1187.64  399.13 1654.75     399 1674.75     394
    1897     394    1917     399    1947     399    1995     408    2021     399
 2300.22     398 2365.54     385 2391.42     383 2406.81     375 2528.12     376
 2538.99  380.97 2626.99  392.37    2632  396.37  2653.2  398.63 2710.74     398
 2870.84     394 3116.46     400 3147.04  393.05 3336.65   395.8 3499.94   392.5
 3705.51     394 3775.34  398.78 4183.26     400 4263.23     404 4312.09     428
#Mann= 4 ,-1,0
    1024    .055       0 2300.22     .03       0 2538.99    .024       0
 2710.74    .055       0
Levee=-1,1024,425.27,-1,4312.09,425.27,,
#XS Ineff= 2 ,-1
    2900    3040     423    3840    4300     423
Permanent Ineff=
       T       T
#Block Obstruct= 2 ,-1
    1184    1384     402    1564    1614     402
Bank Sta=2300.22,2653.2
XS Rating Curve= 0 ,0
Exp/Cntr=0.5,0.3

Type RM Length L Ch R = 1 ,108504  ,62,58,58
BEGIN DESCRIPTION:
This cross section corresponds to cross section 108514  of the non-georeferenced CDC model which was the source of this model.
Cross-section modified for CDC DAL010909-1 Sante Fe Trestle Trail.
Cross-section modified for CDC DAL090508-1 Standing Wave Park.
END DESCRIPTION:
XS GIS Cut Line= 5
2494219.884952016962667.526192382493486.999934856961215.00022605
2492585.000098416960132.000095472492507.330634336960013.86122413
2492397.460136536959846.74308115
#Sta/Elev= 30
 1009.17  425.95 1136.53  400.98 1178.66  399.12 1654.75     399 1674.75     394
    1897     394    1917     399    1947     399    1995     408    2021     399
 2302.65  397.89 2390.69   382.1 2405.55  374.57 2523.95  375.47 2536.02  379.85
  2637.6  396.63  2637.7  399.17 2662.98  397.73 2662.99  400.66 2681.51     399
 2777.67  396.41 2867.53  394.64 3113.57     400  3144.2  393.79 3703.62  394.52
 3773.57  398.91 4147.31  403.97 4186.93  425.55 4186.93  428.36 4386.93  428.36
#Mann= 6 ,-1,0
 1009.17    .055       0 2302.65     .03       0 2536.02    .024       0
  2637.6    .029       0 2681.51     .02       0 2777.67    .055       0
Levee=-1,1009.173,425.4609,0,,,,
#XS Ineff= 2 ,-1
    2885    3050     423    3826 4186.93     423
Permanent Ineff=
       T       T
#Block Obstruct= 2 ,-1
    1184    1384     402    1564    1614     402
Bank Sta=2302.65,2637.6
XS Rating Curve= 0 ,0
Exp/Cntr=0.5,0.3

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
Type RM Length L Ch R = 1 ,108361  ,33,33,33
BEGIN DESCRIPTION:
This cross section corresponds to cross section 108380   of the non-georeferenced CDC model which was the source of this model.
Cross-section modified for CDC DAL010909-1 Sante Fe Trestle Trail.
END DESCRIPTION:
XS GIS Cut Line= 6
  2494317.199718 6962679.61835982493790.49965593 6961486.1089358
2493544.491945836961052.10127363 2493215.34595066960608.29179379
2493032.445069676960402.828622042492544.080888936959957.35247888
#Sta/Elev= 30
     885  427.06    1060     400    1070     399    1535     399    1800     398
    2000     399    2135     400    2165     400    2302     398    2323     397
    2369     380    2395     371    2489     371    2515     380    2555     397
    2596     398    2695     399    2760     400    3200     400    3217     398
    3260     397    3470     397    3700     399    3760     400    3770     401
    3878     401    4050     402    4115     403    4178     405    4178   431.4
#Mann= 4 ,-1,0
     885    .055       0    2323     .03       0    2555    .055       0
    3770    .065       0
Levee=-1,885,427.06,0,,,,
#XS Ineff= 2 ,-1
    2750    3130     423    3810    4178     423
Permanent Ineff=
       T       T
#XS Lid=8
     885  426.88  426.88     885     432     432    1991     432     432
    1991  420.23  414.73    2012  420.23  414.73    2012     432     432
    4178     432     432    4178   431.4   431.4
Bank Sta=2323,2555
XS Rating Curve= 0 ,0
Exp/Cntr=0.6,0.4

Type RM Length L Ch R = 3 ,108345  ,,,
BEGIN DESCRIPTION:
This cross section corresponds to cross section 108364  DART Rail Line/End DFE - Begin Dallas Floodway of the non-georeferenced CDC model which was the source of this model.
END DESCRIPTION:
Node Name=DART Rail Line
Bridge Culvert--1,0,-1,-1, 0
Deck Dist Width WeirC Skew NumUp NumDn MinLoCord MaxHiCord MaxSubmerge Is_Ogee
1.5,30,2.6,0, 31, 31, , , 0.95, 0, ,,,
     885     930    1030    1130    1230    1330    1430    1530    1630    1730
    1830    1930    2030    2030    2294    2614    2878    2878    2978    3078
    3178    3278    3378    3478    3578    3678    3778    3878    3978    4078
    4178
  439.74  439.74  439.58  439.63  439.87  440.27  440.67  441.07  441.47  441.82
  442.01  442.01  441.76  441.76  440.98  439.99  438.31  438.31  437.34  436.25
  435.73  435.19  434.83  434.52  434.21   433.9  433.59  433.28  432.91  432.29
  431.41
  432.11  432.11  431.95     432  432.24  432.64  433.04  433.44  433.84  434.19
  434.38  434.38  434.14  426.23  425.23  424.24  422.78  430.69  429.71  428.62
   428.1  427.56   427.2  426.89  426.58  426.27  425.96  425.65  425.28  424.66
  423.78
     885     930    1030    1130    1230    1330    1430    1530    1630    1730
    1830    1930    2030    2030    2294    2614    2878    2878    2978    3078
    3178    3278    3378    3478    3578    3678    3778    3878    3978    4078
    4178
  439.74  439.74  439.58  439.63  439.87  440.27  440.67  441.07  441.47  441.82
  442.01  442.01  441.76  441.76  440.98  439.99  438.31  438.31  437.34  436.25
  435.73  435.19  434.83  434.52  434.21   433.9  433.59  433.28  432.91  432.29
  431.41
  432.11  432.11  431.95     432  432.24  432.64  433.04  433.44  433.84  434.19
  434.38  434.38  434.14  426.23  425.23  424.24  422.78  430.69  429.71  428.62
   428.1  427.56   427.2  426.89  426.58  426.27  425.96  425.65  425.28  424.66
  423.78
Pier Skew, UpSta & Num, DnSta & Num=  ,930, 2 ,930, 2 , 0 , 0 , 0 ,,
     5.5     5.5
       0     439
     5.5     5.5
       0     439
Pier Skew, UpSta & Num, DnSta & Num=  ,1030, 2 ,1030, 2 , 0 , 0 , 0 ,,
     5.5     5.5
       0     438
     5.5     5.5
       0     438
Pier Skew, UpSta & Num, DnSta & Num=  ,1130, 2 ,1130, 2 , 0 , 0 , 0 ,,
     5.5     5.5
       0     438
     5.5     5.5
       0     438
Pier Skew, UpSta & Num, DnSta & Num=  ,1230, 2 ,1230, 2 , 0 , 0 , 0 ,,
     5.5     5.5
       0     438
     5.5     5.5
       0     438
Pier Skew, UpSta & Num, DnSta & Num=  ,1330, 2 ,1330, 2 , 0 , 0 , 0 ,,
     5.5     5.5
       0     438
     5.5     5.5
       0     438
Pier Skew, UpSta & Num, DnSta & Num=  ,1430, 2 ,1430, 2 , 0 , 0 , 0 ,,
     5.5     5.5
       0     440
     5.5     5.5
       0     440
Pier Skew, UpSta & Num, DnSta & Num=  ,1530, 2 ,1530, 2 , 0 , 0 , 0 ,,
     5.5     5.5
       0     440
     5.5     5.5
       0     440
Pier Skew, UpSta & Num, DnSta & Num=  ,1630, 2 ,1630, 2 , 0 , 0 , 0 ,,
     5.5     5.5
       0     440
     5.5     5.5
       0     440
Pier Skew, UpSta & Num, DnSta & Num=  ,1730, 2 ,1730, 2 , 0 , 0 , 0 ,,
     5.5     5.5
       0     440
     5.5     5.5
       0     440
Pier Skew, UpSta & Num, DnSta & Num=  ,1830, 2 ,1830, 2 , 0 , 0 , 0 ,,
     5.5     5.5
       0     440
     5.5     5.5
       0     440
Pier Skew, UpSta & Num, DnSta & Num=  ,1930, 2 ,1930, 2 , 0 , 0 , 0 ,,
     5.5     5.5
       0     440
     5.5     5.5
       0     440
Pier Skew, UpSta & Num, DnSta & Num=  ,2030, 2 ,2030, 2 , 0 , 0 , 0 ,,
       6       6
       0     440
       6       6
       0     440
Pier Skew, UpSta & Num, DnSta & Num=  ,2294, 2 ,2294, 2 , 0 , 0 , 0 ,,
       6       6
       0     440
       6       6
       0     440
Pier Skew, UpSta & Num, DnSta & Num=  ,2614, 2 ,2614, 2 , 0 , 0 , 0 ,,
       6       6
       0     438
       6       6
       0     438
Pier Skew, UpSta & Num, DnSta & Num=  ,2878, 2 ,2878, 2 , 0 , 0 , 0 ,,
       6       6
       0     437
       6       6
       0     437
Pier Skew, UpSta & Num, DnSta & Num=  ,2978, 2 ,2978, 2 , 0 , 0 , 0 ,,
     5.5     5.5
       0     436
     5.5     5.5
       0     436
Pier Skew, UpSta & Num, DnSta & Num=  ,3078, 2 ,3078, 2 , 0 , 0 , 0 ,,
     5.5     5.5
       0     435
     5.5     5.5
       0     435
Pier Skew, UpSta & Num, DnSta & Num=  ,3178, 2 ,3178, 2 , 0 , 0 , 0 ,,
     5.5     5.5
       0     434
     5.5     5.5
       0     434
Pier Skew, UpSta & Num, DnSta & Num=  ,3278, 2 ,3278, 2 , 0 , 0 , 0 ,,
     5.5     5.5
       0     433
     5.5     5.5
       0     433
Pier Skew, UpSta & Num, DnSta & Num=  ,3378, 2 ,3378, 2 , 0 , 0 , 0 ,,
     5.5     5.5
       0     432
     5.5     5.5
       0     432
Pier Skew, UpSta & Num, DnSta & Num=  ,3478, 2 ,3478, 2 , 0 , 0 , 0 ,,
     5.5     5.5
       0     432
     5.5     5.5
       0     432
Pier Skew, UpSta & Num, DnSta & Num=  ,3578, 2 ,3578, 2 , 0 , 0 , 0 ,,
     5.5     5.5
       0     432
     5.5     5.5
       0     432
Pier Skew, UpSta & Num, DnSta & Num=  ,3678, 2 ,3678, 2 , 0 , 0 , 0 ,,
     5.5     5.5
       0     430
     5.5     5.5
       0     430
Pier Skew, UpSta & Num, DnSta & Num=  ,3778, 2 ,3778, 2 , 0 , 0 , 0 ,,
     5.5     5.5
       0     430
     5.5     5.5
       0     430
Pier Skew, UpSta & Num, DnSta & Num=  ,3878, 2 ,3878, 2 , 0 , 0 , 0 ,,
     5.5     5.5
       0     430
     5.5     5.5
       0     430
Pier Skew, UpSta & Num, DnSta & Num=  ,3978, 2 ,3978, 2 , 0 , 0 , 0 ,,
     5.5     5.5
       0     430
     5.5     5.5
       0     430
Pier Skew, UpSta & Num, DnSta & Num=  ,4078, 2 ,4078, 2 , 0 , 0 , 0 ,,
     5.5     5.5
       0     430
     5.5     5.5
       0     430
BR Coef= 1 , 1 , 1 ,1.25, 0 ,,,0.8,-1,2,1,
WSPro=,,,, 1 ,,,, 0 ,,,, 0 ,,,,-1 ,-1 ,-1 , 0 , 0 , 0 , 0 , 0
BC Design=,, 0 ,, 0 ,,,,,,
BC HTab HWMax=439
BC Use User HTab Curves=0
BC User HTab FreeFlow(D)= 0

Type RM Length L Ch R = 1 ,108328  ,31,39,23
BEGIN DESCRIPTION:
This cross section corresponds to cross section 108348  of the non-georeferenced CDC model which was the source of this model.
Cross-section modified for CDC DAL010909-1 Sante Fe Trestle Trail.
END DESCRIPTION:
XS GIS Cut Line= 6
2494348.851885686962669.410703052493821.257468436961476.90554214
2493575.18348551 6961040.26730782493237.470250166960585.25804722
2493054.129409496960379.160034212492578.629704336959944.31805614
#Sta/Elev= 30
     885  426.88    1060     400    1070     399    1535     399    1800     398
    2000     399    2135     400    2165     400    2302     398    2323     397
    2369     380    2395     371    2489     371    2515     380    2555     397
    2596     398    2695     399    2760     400    3200     400    3217     398
    3260     397    3470     397    3700     399    3760     400    3770     401
    3878     401    4050     402    4115     403    4178     405    4178   431.4
#Mann= 4 ,-1,0
     885    .055       0    2323     .03       0    2555    .055       0
    3770    .065       0
Levee=-1,885,426.88,0,,,,
#XS Ineff= 2 ,-1
    2745    3165     423    3840    4178     423
Permanent Ineff=
       T       T
#XS Lid=8
     885  426.88  426.88     885     432     432    1991     432     432
    1991  420.23  414.73    2012  420.23  414.73    2012     432     432
    4178     432     432    4178   431.4   431.4
Bank Sta=2323,2555
XS Rating Curve= 0 ,0
Exp/Cntr=0.6,0.4

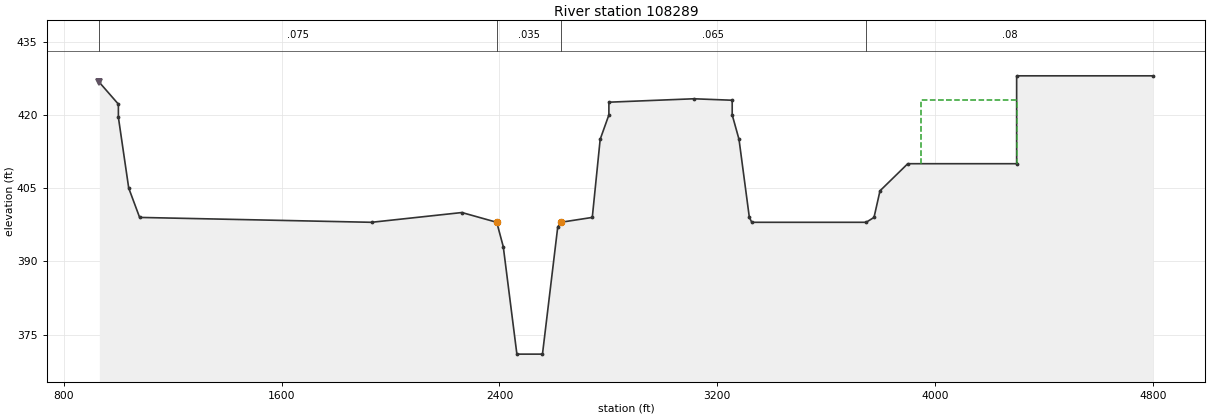
Type RM Length L Ch R = 1 ,108289  ,22,22,22
BEGIN DESCRIPTION:
This cross section corresponds to cross section 108298  of the non-georeferenced CDC model which was the source of this model.
Cross-section modified for CDC DAL010909-1 Sante Fe Trestle Trail.
END DESCRIPTION:
XS GIS Cut Line= 6
2494382.902670596962659.93106322  2493726.2875146961215.51498879
2493646.321466596961043.965463132493484.791277836960787.26420489
2493091.767129516960382.416917472492178.449692826959563.75712797
#Sta/Elev= 30
     930  426.67    1000   422.2    1000   419.5    1038     405    1078     399
    1930     398    2262     400    2390     398    2414     393    2464     371
    2558     371    2614     397    2625     398    2741     399    2770     415
    2802     420    2802   422.6    3114   423.3    3255     423    3255     420
    3280     415    3318     399    3327     398    3747     398    3776     399
    3798  404.45    3900     410    4300     410    4300     428    4800     428
#Mann= 4 ,-1,0
     930    .075       0    2390    .035       0    2625    .065       0
    3747     .08       0
Levee=-1,930,426.67,0,,,,
#XS Ineff= 1 ,-1
    3950    4300     423
Permanent Ineff=
       T
Bank Sta=2390,2625
XS Rating Curve= 0 ,0
Exp/Cntr=0.6,0.4