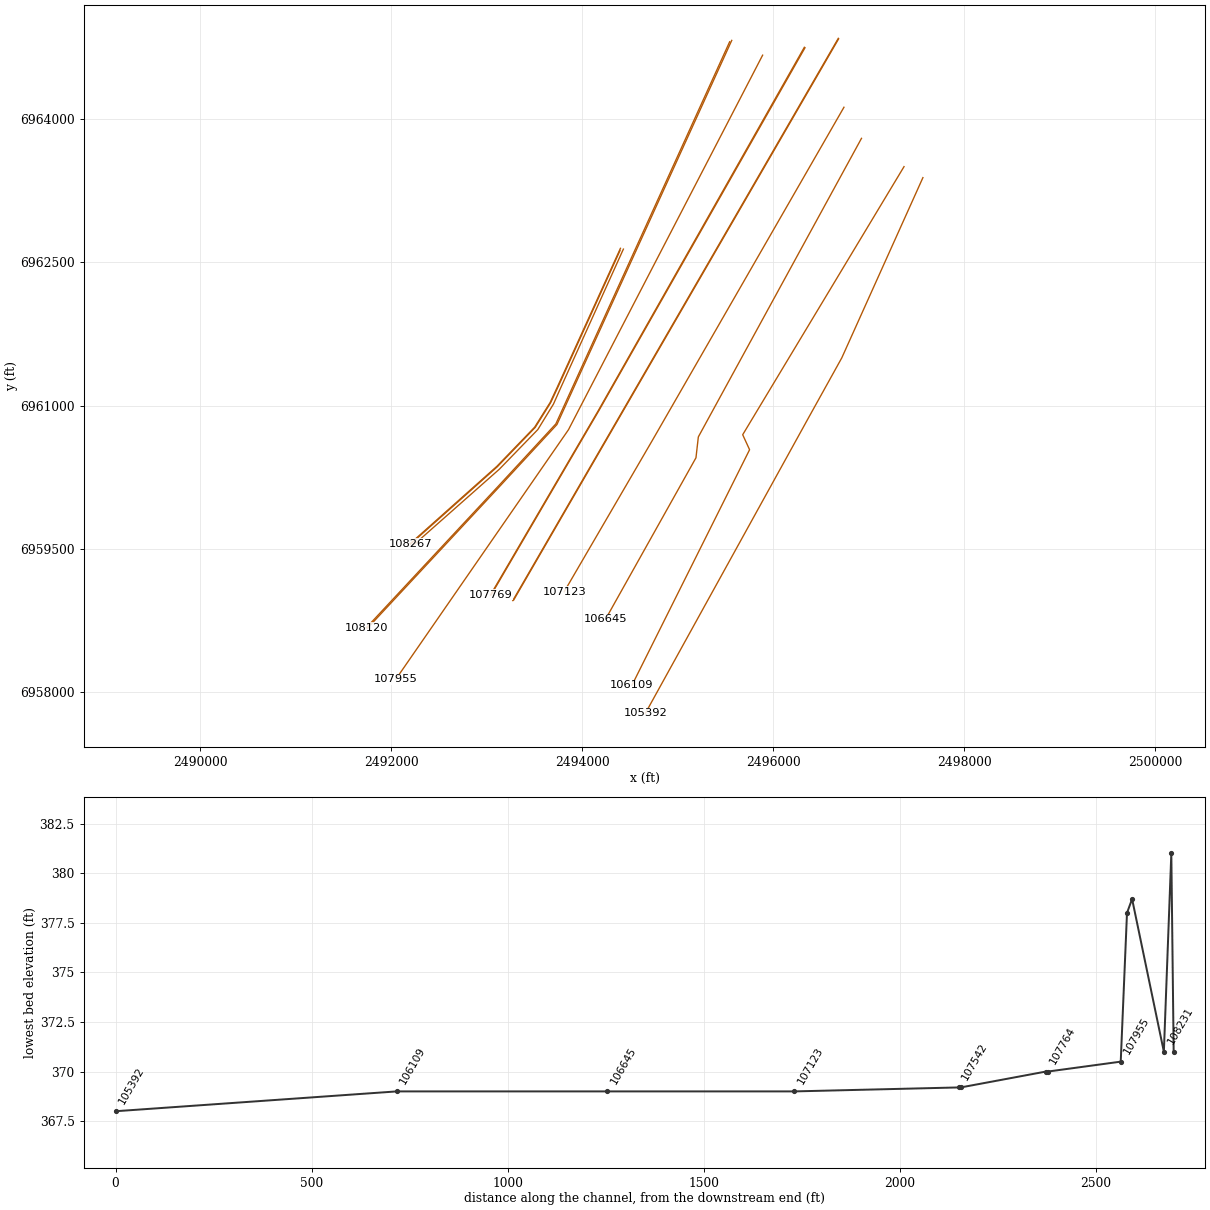
HEC-RAS study CDC_Consolidated_Model.prj: Upper Trinity CDC Consolidated Model

--- CDC_Consolidated_Model.g02 (geometry) --- (continued)

Type RM Length L Ch R = 3 ,108278  ,,,
BEGIN DESCRIPTION:
This cross section corresponds to cross section 108287  Abandoned Atchinson, Topeka, and Santa Fe Railroad bridge and includes modifications for the CDC DAL010909-1 Sante Fe Trestle Trail. of the non-georeferenced CDC model which was the source of this model.
END DESCRIPTION:
Node Name=ATSF Railroad
Bridge Culvert--1,0,-1,-1, 0
Deck Dist Width WeirC Skew NumUp NumDn MinLoCord MaxHiCord MaxSubmerge Is_Ogee
1,20,2.6,0, 77, 77, , , 0.95, 0, ,,,
    1000    1200    2010    2010    2010    2058    2058    2058    2105  2212.5
  2319.5  2319.5    2414    2414    2418    2418    2419    2419    2440    2440
    2441    2441    2462    2462    2463    2463    2484    2484    2485    2485
    2506    2506    2507    2507    2528    2528    2529    2529    2550    2550
    2551    2551    2572    2572    2573    2573    2594    2594    2595    2595
    2616    2616    2617    2617    2622    2622    2715    2715    2725    2725
    2745    2745    2802    2802    2890    2962    3000    3042    3114    3197
    3255    3825    3855    3855    3855    4300    4300
   422.2   422.7   422.7   422.7  427.95  427.95   422.7  421.97  423.71  427.95
  427.95  427.95  427.95  427.95  427.95     435     435  427.95  427.95     435
     435  427.95  427.95     435     435  427.95  427.95     435     435  427.95
  427.95     435     435  427.95  427.95     435     435  427.95  427.95     435
     435  427.95  427.95     435     435  427.95  427.95     435     435  427.95
  427.95     435     435  427.95  427.95  427.95  427.95  427.95  427.95     435
     435   422.6   422.6   422.6   422.9   422.9     423   423.1   423.3   423.2
     423   422.9   422.9   422.9  427.95  427.95   422.9
   419.5     420     420   422.7  427.95  427.95   422.7  416.47  418.21  422.45
  422.45  419.17  419.17     417     417     417     417     417     417     417
     417     417     417     417     417     417     417     417     417     417
     417     417     417     417     417     417     417     417     417     417
     417     417     417     417     417     417     417     417     417     417
     417     417     417     417     417  420.72  420.72  420.72  420.72     435
     435     420     420   422.6   422.9   422.9     423   423.1   423.3   423.2
     420     420     420   422.9  427.95  427.95   422.9
    1000    1200    2010    2010    2010    2058    2058    2058    2105  2212.5
  2319.5  2319.5    2414    2414    2418    2418    2419    2419    2440    2440
    2441    2441    2462    2462    2463    2463    2484    2484    2485    2485
    2506    2506    2507    2507    2528    2528    2529    2529    2550    2550
    2551    2551    2572    2572    2573    2573    2594    2594    2595    2595
    2616    2616    2617    2617    2622    2622    2715    2715    2725    2725
    2745    2745    2802    2802    2890    2962    3000    3042    3114    3197
    3255    3825    3855    3855    3855    4300    4300
   422.2   422.7   422.7   422.7  427.95  427.95   422.7  421.97  423.71  427.95
  427.95  427.95  427.95  427.95  427.95     435     435  427.95  427.95     435
     435  427.95  427.95     435     435  427.95  427.95     435     435  427.95
  427.95     435     435  427.95  427.95     435     435  427.95  427.95     435
     435  427.95  427.95     435     435  427.95  427.95     435     435  427.95
  427.95     435     435  427.95  427.95  427.95  427.95  427.95  427.95     435
     435   422.6   422.6   422.6   422.9   422.9     423   423.1   423.3   423.2
     423   422.9   422.9   422.9  427.95  427.95   422.9
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Pier Skew, UpSta & Num, DnSta & Num=  ,1014, 2 ,1014, 2 , 0 , 0 , 0 ,,
     1.3     1.3
       0     500
     1.3     1.3
       0     500
Pier Skew, UpSta & Num, DnSta & Num=  ,1028, 2 ,1028, 2 , 0 , 0 , 0 ,,
     1.3     1.3
     360     421
     1.3     1.3
     360     421
Pier Skew, UpSta & Num, DnSta & Num=  ,1042, 2 ,1042, 2 , 0 , 0 , 0 ,,
     1.3     1.3
     360     421
     1.3     1.3
     360     421
Pier Skew, UpSta & Num, DnSta & Num=  ,1056, 2 ,1056, 2 , 0 , 0 , 0 ,,
     1.3     1.3
     370     421
     1.3     1.3
     370     421
Pier Skew, UpSta & Num, DnSta & Num=  ,1070, 2 ,1070, 2 , 0 , 0 , 0 ,,
     1.3     1.3
     360     421
     1.3     1.3
     360     421
Pier Skew, UpSta & Num, DnSta & Num=  ,1084, 2 ,1084, 2 , 0 , 0 , 0 ,,
     1.3     1.3
     370     421
     1.3     1.3
     370     421
Pier Skew, UpSta & Num, DnSta & Num=  ,1098, 2 ,1098, 2 , 0 , 0 , 0 ,,
     1.3     1.3
     360     421
     1.3     1.3
     360     421
Pier Skew, UpSta & Num, DnSta & Num=  ,1112, 2 ,1112, 2 , 0 , 0 , 0 ,,
     1.3     1.3
     370     421
     1.3     1.3
     370     421
Pier Skew, UpSta & Num, DnSta & Num=  ,1126, 2 ,1126, 2 , 0 , 0 , 0 ,,
     1.3     1.3
     360     421
     1.3     1.3
     360     421
Pier Skew, UpSta & Num, DnSta & Num=  ,1140, 2 ,1140, 2 , 0 , 0 , 0 ,,
     1.3     1.3
     370     421
     1.3     1.3
     370     421
Pier Skew, UpSta & Num, DnSta & Num=  ,1154, 2 ,1154, 2 , 0 , 0 , 0 ,,
     1.3     1.3
     360     421
     1.3     1.3
     360     421
Pier Skew, UpSta & Num, DnSta & Num=  ,1168, 2 ,1168, 2 , 0 , 0 , 0 ,,
     1.3     1.3
     370     421
     1.3     1.3
     370     421
Pier Skew, UpSta & Num, DnSta & Num=  ,1182, 2 ,1182, 2 , 0 , 0 , 0 ,,
     1.3     1.3
     370     421
     1.3     1.3
     370     421
Pier Skew, UpSta & Num, DnSta & Num=  ,1196, 2 ,1196, 2 , 0 , 0 , 0 ,,
     1.3     1.3
     370     421
     1.3     1.3
     370     421
Pier Skew, UpSta & Num, DnSta & Num=  ,1210, 2 ,1210, 2 , 0 , 0 , 0 ,,
     1.3     1.3
     370     421
     1.3     1.3
     370     421
Pier Skew, UpSta & Num, DnSta & Num=  ,1224, 2 ,1224, 2 , 0 , 0 , 0 ,,
     1.3     1.3
     370     421
     1.3     1.3
     370     421
Pier Skew, UpSta & Num, DnSta & Num=  ,1238, 2 ,1238, 2 , 0 , 0 , 0 ,,
     1.3     1.3
     370     421
     1.3     1.3
     370     421
Pier Skew, UpSta & Num, DnSta & Num=  ,1252, 2 ,1252, 2 , 0 , 0 , 0 ,,
     1.3     1.3
     370     421
     1.3     1.3
     370     421
Pier Skew, UpSta & Num, DnSta & Num=  ,1266, 2 ,1266, 2 , 0 , 0 , 0 ,,
     1.3     1.3
     370     421
     1.3     1.3
     370     421
Pier Skew, UpSta & Num, DnSta & Num=  ,1280, 2 ,1280, 2 , 0 , 0 , 0 ,,
     1.3     1.3
     370     421
     1.3     1.3
     370     421
Pier Skew, UpSta & Num, DnSta & Num=  ,1294, 2 ,1294, 2 , 0 , 0 , 0 ,,
     1.3     1.3
     370     421
     1.3     1.3
     370     421
Pier Skew, UpSta & Num, DnSta & Num=  ,1308, 2 ,1308, 2 , 0 , 0 , 0 ,,
     1.3     1.3
     370     421
     1.3     1.3
     370     421
Pier Skew, UpSta & Num, DnSta & Num=  ,1322, 2 ,1322, 2 , 0 , 0 , 0 ,,
     1.3     1.3
     370     421
     1.3     1.3
     370     421
Pier Skew, UpSta & Num, DnSta & Num=  ,1336, 2 ,1336, 2 , 0 , 0 , 0 ,,
     1.3     1.3
     370     421
     1.3     1.3
     370     421
Pier Skew, UpSta & Num, DnSta & Num=  ,1350, 2 ,1350, 2 , 0 , 0 , 0 ,,
     1.3     1.3
     370     421
     1.3     1.3
     370     421
Pier Skew, UpSta & Num, DnSta & Num=  ,1364, 2 ,1364, 2 , 0 , 0 , 0 ,,
     1.3     1.3
     370     421
     1.3     1.3
     370     421
Pier Skew, UpSta & Num, DnSta & Num=  ,1378, 2 ,1378, 2 , 0 , 0 , 0 ,,
     1.3     1.3
     370     421
     1.3     1.3
     370     421
Pier Skew, UpSta & Num, DnSta & Num=  ,1392, 2 ,1392, 2 , 0 , 0 , 0 ,,
     1.3     1.3
     370     421
     1.3     1.3
     370     421
Pier Skew, UpSta & Num, DnSta & Num=  ,1406, 2 ,1406, 2 , 0 , 0 , 0 ,,
     1.3     1.3
     370     421
     1.3     1.3
     370     421
Pier Skew, UpSta & Num, DnSta & Num=  ,1420, 2 ,1420, 2 , 0 , 0 , 0 ,,
     1.3     1.3
     370     421
     1.3     1.3
     370     421
Pier Skew, UpSta & Num, DnSta & Num=  ,1434, 2 ,1434, 2 , 0 , 0 , 0 ,,
     1.3     1.3
     370     421
     1.3     1.3
     370     421
Pier Skew, UpSta & Num, DnSta & Num=  ,1448, 2 ,1448, 2 , 0 , 0 , 0 ,,
     1.3     1.3
     370     421
     1.3     1.3
     370     421
Pier Skew, UpSta & Num, DnSta & Num=  ,1462, 2 ,1462, 2 , 0 , 0 , 0 ,,
     1.3     1.3
     370     421
     1.3     1.3
     370     421
Pier Skew, UpSta & Num, DnSta & Num=  ,1476, 2 ,1476, 2 , 0 , 0 , 0 ,,
     1.3     1.3
     370     421
     1.3     1.3
     370     421
Pier Skew, UpSta & Num, DnSta & Num=  ,1490, 2 ,1490, 2 , 0 , 0 , 0 ,,
     1.3     1.3
     370     421
     1.3     1.3
     370     421
Pier Skew, UpSta & Num, DnSta & Num=  ,1504, 2 ,1504, 2 , 0 , 0 , 0 ,,
     1.3     1.3
     370     421
     1.3     1.3
     370     421
Pier Skew, UpSta & Num, DnSta & Num=  ,1518, 2 ,1518, 2 , 0 , 0 , 0 ,,
     1.3     1.3
     370     421
     1.3     1.3
     370     421
Pier Skew, UpSta & Num, DnSta & Num=  ,1532, 2 ,1532, 2 , 0 , 0 , 0 ,,
     1.3     1.3
     370     421
     1.3     1.3
     370     421
Pier Skew, UpSta & Num, DnSta & Num=  ,1546, 2 ,1546, 2 , 0 , 0 , 0 ,,
     1.3     1.3
     370     421
     1.3     1.3
     370     421
Pier Skew, UpSta & Num, DnSta & Num=  ,1560, 2 ,1560, 2 , 0 , 0 , 0 ,,
     1.3     1.3
     370     421
     1.3     1.3
     370     421
Pier Skew, UpSta & Num, DnSta & Num=  ,1574, 2 ,1574, 2 , 0 , 0 , 0 ,,
     1.3     1.3
     370     421
     1.3     1.3
     370     421
Pier Skew, UpSta & Num, DnSta & Num=  ,1588, 2 ,1588, 2 , 0 , 0 , 0 ,,
     1.3     1.3
     370     421
     1.3     1.3
     370     421
Pier Skew, UpSta & Num, DnSta & Num=  ,1602, 2 ,1602, 2 , 0 , 0 , 0 ,,
     1.3     1.3
     370     421
     1.3     1.3
     370     421
Pier Skew, UpSta & Num, DnSta & Num=  ,1616, 2 ,1616, 2 , 0 , 0 , 0 ,,
     1.3     1.3
     370     421
     1.3     1.3
     370     421
Pier Skew, UpSta & Num, DnSta & Num=  ,1630, 2 ,1630, 2 , 0 , 0 , 0 ,,
     1.3     1.3
     370     421
     1.3     1.3
     370     421
Pier Skew, UpSta & Num, DnSta & Num=  ,1644, 2 ,1644, 2 , 0 , 0 , 0 ,,
     1.3     1.3
     370     421
     1.3     1.3
     370     421
Pier Skew, UpSta & Num, DnSta & Num=  ,1658, 2 ,1658, 2 , 0 , 0 , 0 ,,
     1.3     1.3
     370     421
     1.3     1.3
     370     421
Pier Skew, UpSta & Num, DnSta & Num=  ,1672, 2 ,1672, 2 , 0 , 0 , 0 ,,
     1.3     1.3
     370     421
     1.3     1.3
     370     421
Pier Skew, UpSta & Num, DnSta & Num=  ,1686, 2 ,1686, 2 , 0 , 0 , 0 ,,
     1.3     1.3
     370     421
     1.3     1.3
     370     421
Pier Skew, UpSta & Num, DnSta & Num=  ,1700, 2 ,1700, 2 , 0 , 0 , 0 ,,
     1.3     1.3
     370     421
     1.3     1.3
     370     421
Pier Skew, UpSta & Num, DnSta & Num=  ,1714, 2 ,1714, 2 , 0 , 0 , 0 ,,
     1.3     1.3
     370     421
     1.3     1.3
     370     421
Pier Skew, UpSta & Num, DnSta & Num=  ,1728, 2 ,1728, 2 , 0 , 0 , 0 ,,
     1.3     1.3
     370     421
     1.3     1.3
     370     421
Pier Skew, UpSta & Num, DnSta & Num=  ,1742, 2 ,1742, 2 , 0 , 0 , 0 ,,
     1.3     1.3
     370     421
     1.3     1.3
     370     421
Pier Skew, UpSta & Num, DnSta & Num=  ,1756, 2 ,1756, 2 , 0 , 0 , 0 ,,
     1.3     1.3
     370     421
     1.3     1.3
     370     421
Pier Skew, UpSta & Num, DnSta & Num=  ,1770, 2 ,1770, 2 , 0 , 0 , 0 ,,
     1.3     1.3
     370     421
     1.3     1.3
     370     421
Pier Skew, UpSta & Num, DnSta & Num=  ,1784, 2 ,1784, 2 , 0 , 0 , 0 ,,
     1.3     1.3
     370     421
     1.3     1.3
     370     421
Pier Skew, UpSta & Num, DnSta & Num=  ,1798, 2 ,1798, 2 , 0 , 0 , 0 ,,
     1.3     1.3
     370     421
     1.3     1.3
     370     421
Pier Skew, UpSta & Num, DnSta & Num=  ,1812, 2 ,1812, 2 , 0 , 0 , 0 ,,
     1.3     1.3
     370     421
     1.3     1.3
     370     421
Pier Skew, UpSta & Num, DnSta & Num=  ,1826, 2 ,1826, 2 , 0 , 0 , 0 ,,
     1.3     1.3
     370     421
     1.3     1.3
     370     421
Pier Skew, UpSta & Num, DnSta & Num=  ,1840, 2 ,1840, 2 , 0 , 0 , 0 ,,
     1.3     1.3
     370     421
     1.3     1.3
     370     421
Pier Skew, UpSta & Num, DnSta & Num=  ,1854, 2 ,1854, 2 , 0 , 0 , 0 ,,
     1.3     1.3
     370     421
     1.3     1.3
     370     421
Pier Skew, UpSta & Num, DnSta & Num=  ,1868, 2 ,1868, 2 , 0 , 0 , 0 ,,
     1.3     1.3
     370     421
     1.3     1.3
     370     421
Pier Skew, UpSta & Num, DnSta & Num=  ,1882, 2 ,1882, 2 , 0 , 0 , 0 ,,
     1.3     1.3
     370     421
     1.3     1.3
     370     421
Pier Skew, UpSta & Num, DnSta & Num=  ,1896, 2 ,1896, 2 , 0 , 0 , 0 ,,
     1.3     1.3
     370     421
     1.3     1.3
     370     421
Pier Skew, UpSta & Num, DnSta & Num=  ,1910, 2 ,1910, 2 , 0 , 0 , 0 ,,
     1.3     1.3
     370     421
     1.3     1.3
     370     421
Pier Skew, UpSta & Num, DnSta & Num=  ,1924, 2 ,1924, 2 , 0 , 0 , 0 ,,
     1.3     1.3
     370     421
     1.3     1.3
     370     421
Pier Skew, UpSta & Num, DnSta & Num=  ,1938, 2 ,1938, 2 , 0 , 0 , 0 ,,
     1.3     1.3
     370     421
     1.3     1.3
     370     421
Pier Skew, UpSta & Num, DnSta & Num=  ,1952, 2 ,1952, 2 , 0 , 0 , 0 ,,
     1.3     1.3
     370     421
     1.3     1.3
     370     421
Pier Skew, UpSta & Num, DnSta & Num=  ,1966, 2 ,1966, 2 , 0 , 0 , 0 ,,
     1.3     1.3
     370     421
     1.3     1.3
     370     421
Pier Skew, UpSta & Num, DnSta & Num=  ,1980, 2 ,1980, 2 , 0 , 0 , 0 ,,
     1.3     1.3
     370     421
     1.3     1.3
     370     421
Pier Skew, UpSta & Num, DnSta & Num=  ,1994, 2 ,1994, 2 , 0 , 0 , 0 ,,
     1.3     1.3
     370     421
     1.3     1.3
     370     421
Pier Skew, UpSta & Num, DnSta & Num=  ,2008, 2 ,2008, 2 , 0 , 0 , 0 ,,
     1.3     1.3
     370     421
     1.3     1.3
     370     421
Pier Skew, UpSta & Num, DnSta & Num=  ,2061.5, 2 ,2061.5, 2 , 0 , 0 , 0 ,,
       4       4
     370     421
       4       4
     370     421
Pier Skew, UpSta & Num, DnSta & Num=  ,2078, 2 ,2078, 2 , 0 , 0 , 0 ,,
     1.3     1.3
     370     421
     1.3     1.3
     370     421
Pier Skew, UpSta & Num, DnSta & Num=  ,2092, 2 ,2092, 2 , 0 , 0 , 0 ,,
     1.3     1.3
     370     421
     1.3     1.3
     370     421
Pier Skew, UpSta & Num, DnSta & Num=  ,2105, 2 ,2105, 2 , 0 , 0 , 0 ,,
       4       4
     370     421
       4       4
     370     421
Pier Skew, UpSta & Num, DnSta & Num=  ,2120, 2 ,2120, 2 , 0 , 0 , 0 ,,
     1.3     1.3
     370     421
     1.3     1.3
     370     421
Pier Skew, UpSta & Num, DnSta & Num=  ,2134, 2 ,2134, 2 , 0 , 0 , 0 ,,
     1.3     1.3
     370     421
     1.3     1.3
     370     421
Pier Skew, UpSta & Num, DnSta & Num=  ,2148, 2 ,2148, 2 , 0 , 0 , 0 ,,
     1.3     1.3
     370     421
     1.3     1.3
     370     421
Pier Skew, UpSta & Num, DnSta & Num=  ,2162, 2 ,2162, 2 , 0 , 0 , 0 ,,
     1.3     1.3
     370     421
     1.3     1.3
     370     421
Pier Skew, UpSta & Num, DnSta & Num=  ,2176, 2 ,2176, 2 , 0 , 0 , 0 ,,
     1.3     1.3
     370     421
     1.3     1.3
     370     421
Pier Skew, UpSta & Num, DnSta & Num=  ,2190, 2 ,2190, 2 , 0 , 0 , 0 ,,
     1.3     1.3
     370     423
     1.3     1.3
     370     423
Pier Skew, UpSta & Num, DnSta & Num=  ,2204, 2 ,2204, 2 , 0 , 0 , 0 ,,
     1.3     1.3
     370     423
     1.3     1.3
     370     423
Pier Skew, UpSta & Num, DnSta & Num=  ,2212.5, 2 ,2212.5, 2 , 0 , 0 , 0 ,,
       4       4
     370     423
       4       4
     370     423
Pier Skew, UpSta & Num, DnSta & Num=  ,2232, 2 ,2232, 2 , 0 , 0 , 0 ,,
     1.3     1.3
     370     423
     1.3     1.3
     370     423
Pier Skew, UpSta & Num, DnSta & Num=  ,2246, 2 ,2246, 2 , 0 , 0 , 0 ,,
     1.3     1.3
     370     423
     1.3     1.3
     370     423
Pier Skew, UpSta & Num, DnSta & Num=  ,2260, 2 ,2260, 2 , 0 , 0 , 0 ,,
     1.3     1.3
     370     423
     1.3     1.3
     370     423
Pier Skew, UpSta & Num, DnSta & Num=  ,2274, 2 ,2274, 2 , 0 , 0 , 0 ,,
     1.3     1.3
     370     423
     1.3     1.3
     370     423
Pier Skew, UpSta & Num, DnSta & Num=  ,2288, 2 ,2288, 2 , 0 , 0 , 0 ,,
     1.3     1.3
     370     423
     1.3     1.3
     370     423
Pier Skew, UpSta & Num, DnSta & Num=  ,2302, 2 ,2302, 2 , 0 , 0 , 0 ,,
     1.3     1.3
     370     423
     1.3     1.3
     370     423
Pier Skew, UpSta & Num, DnSta & Num=  ,2319.5, 2 ,2319.5, 2 , 0 , 0 , 0 ,,
       4       4
     370     423
       4       4
     370     423
Pier Skew, UpSta & Num, DnSta & Num=  ,2330, 2 ,2330, 2 , 0 , 0 , 0 ,,
     1.3     1.3
     370     421
     1.3     1.3
     370     421
Pier Skew, UpSta & Num, DnSta & Num=  ,2344, 2 ,2344, 2 , 0 , 0 , 0 ,,
     1.3     1.3
     370     421
     1.3     1.3
     370     421
Pier Skew, UpSta & Num, DnSta & Num=  ,2358, 2 ,2358, 2 , 0 , 0 , 0 ,,
     1.3     1.3
     370     421
     1.3     1.3
     370     421
Pier Skew, UpSta & Num, DnSta & Num=  ,2372, 2 ,2372, 2 , 0 , 0 , 0 ,,
     1.3     1.3
     370     421
     1.3     1.3
     370     421
Pier Skew, UpSta & Num, DnSta & Num=  ,2386, 2 ,2386, 2 , 0 , 0 , 0 ,,
     1.3     1.3
     370     421
     1.3     1.3
     370     421
Pier Skew, UpSta & Num, DnSta & Num=  ,2400, 2 ,2400, 2 , 0 , 0 , 0 ,,
     1.3     1.3
     370     421
     1.3     1.3
     370     421
Pier Skew, UpSta & Num, DnSta & Num=  ,2418, 2 ,2418, 2 , 0 , 0 , 0 ,,
       8       8
     370     421
       8       8
     370     421
Pier Skew, UpSta & Num, DnSta & Num=  ,2618, 2 ,2618, 2 , 0 , 0 , 0 ,,
       8       8
     370     421
       8       8
     370     421
Pier Skew, UpSta & Num, DnSta & Num=  ,2636, 2 ,2636, 2 , 0 , 0 , 0 ,,
     1.3     1.3
     370     421
     1.3     1.3
     370     421
Pier Skew, UpSta & Num, DnSta & Num=  ,2650, 2 ,2650, 2 , 0 , 0 , 0 ,,
     1.3     1.3
     370     421
     1.3     1.3
     370     421
Pier Skew, UpSta & Num, DnSta & Num=  ,2664, 2 ,2664, 2 , 0 , 0 , 0 ,,
     1.3     1.3
     370     421
     1.3     1.3
     370     421
Pier Skew, UpSta & Num, DnSta & Num=  ,2678, 2 ,2678, 2 , 0 , 0 , 0 ,,
     1.3     1.3
     370     421
     1.3     1.3
     370     421
Pier Skew, UpSta & Num, DnSta & Num=  ,2692, 2 ,2692, 2 , 0 , 0 , 0 ,,
     1.3     1.3
     370     421
     1.3     1.3
     370     421
Pier Skew, UpSta & Num, DnSta & Num=  ,2704, 2 ,2704, 2 , 0 , 0 , 0 ,,
     1.3     1.3
     370     421
     1.3     1.3
     370     421
Pier Skew, UpSta & Num, DnSta & Num=  ,2720, 2 ,2720, 2 , 0 , 0 , 0 ,,
     1.3     1.3
     370     421
     1.3     1.3
     370     421
Pier Skew, UpSta & Num, DnSta & Num=  ,2748, 2 ,2748, 2 , 0 , 0 , 0 ,,
     1.3     1.3
     370     421
     1.3     1.3
     370     421
Pier Skew, UpSta & Num, DnSta & Num=  ,2762, 2 ,2762, 2 , 0 , 0 , 0 ,,
     1.3     1.3
     370     421
     1.3     1.3
     370     421
Pier Skew, UpSta & Num, DnSta & Num=  ,2776, 2 ,2776, 2 , 0 , 0 , 0 ,,
     1.3     1.3
     370     421
     1.3     1.3
     370     421
Pier Skew, UpSta & Num, DnSta & Num=  ,2790, 2 ,2790, 2 , 0 , 0 , 0 ,,
     1.3     1.3
     370     421
     1.3     1.3
     370     421
Pier Skew, UpSta & Num, DnSta & Num=  ,3288, 2 ,3288, 2 , 0 , 0 , 0 ,,
       2       2
     370     421
       2       2
     370     421
Pier Skew, UpSta & Num, DnSta & Num=  ,3321, 2 ,3321, 2 , 0 , 0 , 0 ,,
       2       2
     370     421
       2       2
     370     421
Pier Skew, UpSta & Num, DnSta & Num=  ,3354, 2 ,3354, 2 , 0 , 0 , 0 ,,
       2       2
     370     421
       2       2
     370     421
Pier Skew, UpSta & Num, DnSta & Num=  ,3387, 2 ,3387, 2 , 0 , 0 , 0 ,,
       2       2
     370     421
       2       2
     370     421
Pier Skew, UpSta & Num, DnSta & Num=  ,3420, 2 ,3420, 2 , 0 , 0 , 0 ,,
       2       2
     370     421
       2       2
     370     421
Pier Skew, UpSta & Num, DnSta & Num=  ,3453, 2 ,3453, 2 , 0 , 0 , 0 ,,
       2       2
     370     421
       2       2
     370     421
Pier Skew, UpSta & Num, DnSta & Num=  ,3486, 2 ,3486, 2 , 0 , 0 , 0 ,,
       2       2
     370     421
       2       2
     370     421
Pier Skew, UpSta & Num, DnSta & Num=  ,3519, 2 ,3519, 2 , 0 , 0 , 0 ,,
       2       2
     370     421
       2       2
     370     421
Pier Skew, UpSta & Num, DnSta & Num=  ,3552, 2 ,3552, 2 , 0 , 0 , 0 ,,
       2       2
     370     421
       2       2
     370     421
Pier Skew, UpSta & Num, DnSta & Num=  ,3585, 2 ,3585, 2 , 0 , 0 , 0 ,,
       2       2
     370     421
       2       2
     370     421
Pier Skew, UpSta & Num, DnSta & Num=  ,3618, 2 ,3618, 2 , 0 , 0 , 0 ,,
       2       2
     370     421
       2       2
     370     421
Pier Skew, UpSta & Num, DnSta & Num=  ,3651, 2 ,3651, 2 , 0 , 0 , 0 ,,
       2       2
     370     421
       2       2
     370     421
Pier Skew, UpSta & Num, DnSta & Num=  ,3684, 2 ,3684, 2 , 0 , 0 , 0 ,,
       2       2
     370     421
       2       2
     370     421
Pier Skew, UpSta & Num, DnSta & Num=  ,3717, 2 ,3717, 2 , 0 , 0 , 0 ,,
       2       2
     370     421
       2       2
     370     421
Pier Skew, UpSta & Num, DnSta & Num=  ,3750, 2 ,3750, 2 , 0 , 0 , 0 ,,
       2       2
     370     421
       2       2
     370     421
Pier Skew, UpSta & Num, DnSta & Num=  ,3783, 2 ,3783, 2 , 0 , 0 , 0 ,,
       2       2
     370     421
       2       2
     370     421
Pier Skew, UpSta & Num, DnSta & Num=  ,3816, 2 ,3816, 2 , 0 , 0 , 0 ,,
       2       2
     370     421
       2       2
     370     421
Pier Skew, UpSta & Num, DnSta & Num=  ,3849, 2 ,3849, 2 , 0 , 0 , 0 ,,
       2       2
     370     421
       2       2
     370     421
BR Coef= 1 , 1 , 1 ,2.5, 0 ,,,0.8,0,1.2,0,
WSPro=,,,, 1 ,,,, 0 ,,,, 0 ,,,,-1 ,-1 ,-1 , 0 , 0 , 0 , 0 , 0
BC Design=,, 0 ,, 0 ,,,,,,
BC HTab HWMax=428
BC Use User HTab Curves=0
BC User HTab FreeFlow(D)= 0

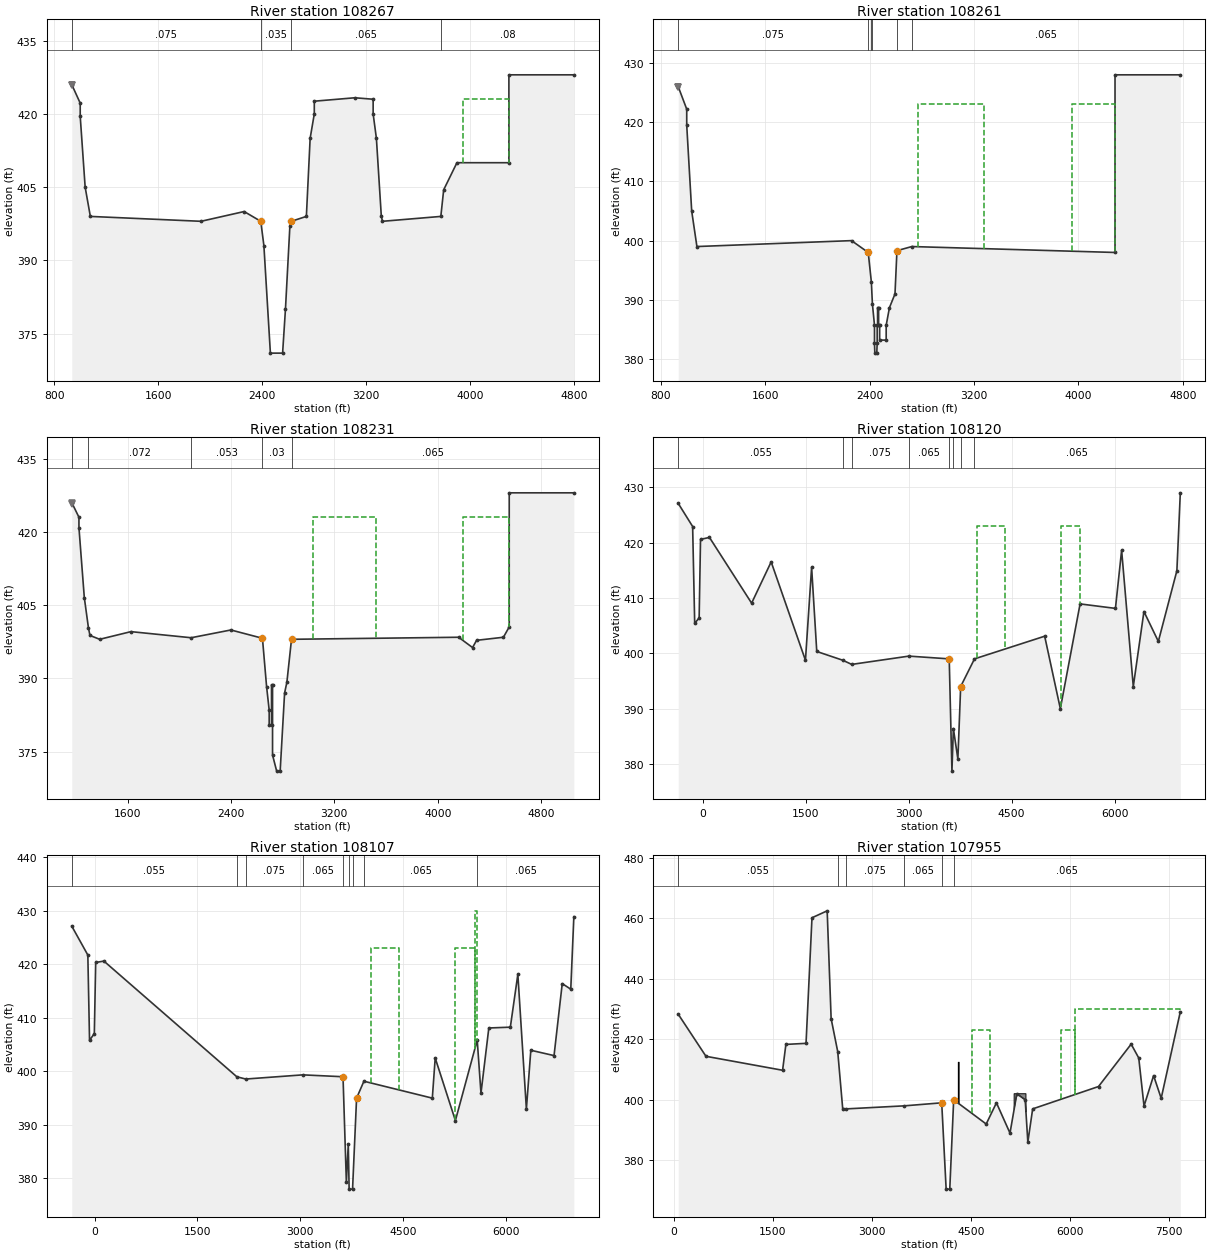
Type RM Length L Ch R = 1 ,108267  ,6,6,6
BEGIN DESCRIPTION:
This cross section corresponds to cross section 108276   of the non-georeferenced CDC model which was the source of this model.
Cross-section modified for CDC DAL010909-1 Sante Fe Trestle Trail.
END DESCRIPTION:
XS GIS Cut Line= 6
2494401.402633586962647.560024962493744.524354166961203.57472396
2493664.935602586961032.694816382493502.970703426960774.40563481
2493107.603711996960364.868396132492199.950116266959555.64501865
#Sta/Elev= 30
     935     426    1000   422.2    1000   419.5    1038     405    1078     399
    1930     398    2262     400    2390     398    2414     393    2464     371
    2558     371    2580     380    2614     397    2625     398    2741     399
    2770     415    2802     420    2802   422.6    3114   423.3    3255     423
    3255     420    3280     415    3318     399    3327     398    3776     399
    3798  404.45    3900     410    4300     410    4300     428    4800     428
#Mann= 4 ,-1,0
     935    .075       0    2390    .035       0    2625    .065       0
    3776     .08       0
Levee=-1,935,426,0,,,,
#XS Ineff= 1 ,-1
    3950    4300     423
Permanent Ineff=
       T
#XS Lid=12
     935     426     426     935     432     432    2742     432     432
    2742     428  422.45    2753     428  422.45    2753     432     432
    2770     432     432    2770     428  422.45    2784     428  422.45
    2784     432     432    4300     432     432    4300     428     428
Bank Sta=2390,2625
XS Rating Curve= 0 ,0
Exp/Cntr=0.6,0.4

Type RM Length L Ch R = 1 ,108261  ,18,19,20
BEGIN DESCRIPTION:
This cross section corresponds to cross section 108270   of the non-georeferenced CDC model which was the source of this model.
Cross-section modified for CDC DAL010909-1 Sante Fe Trestle Trail.
Cross-section added for CDC DAL090508-1 Standing Wave Park.
END DESCRIPTION:
XS GIS Cut Line= 6
2494396.344244756962623.688025462493749.511220846961200.33850996
2493670.042219676961030.630516052493508.362096856960771.86495747
2493111.420961596960359.907776132492203.039841926959550.28895397
#Sta/Elev= 30
     935     426    1000   422.2    1000   419.5    1038     405    1078     399
    2262     400    2390     398    2414     393    2422   389.3    2438   385.7
 2438.01   382.7 2440.51     381  2455.5     381  2458.5   382.7 2458.51   385.7
  2461.5   385.7 2461.51   388.7  2469.5   388.7 2469.51   385.7  2477.5   385.7
 2477.51   383.2  2527.5   383.2 2527.51   385.7 2552.51  388.68 2594.96     391
 2609.96   398.3    2724     399    4280     398    4280     428    4780     428
#Mann= 6 ,-1,0
     935    .075       0    2390    .035       0    2414     .03       0
    2422    .025       0 2609.96    .029       0    2724    .065       0
Levee=-1,935,426,0,,,,
#XS Ineff= 2 ,-1
    2770    3275     423    3950    4280     423
Permanent Ineff=
       T       T
#XS Lid=12
     935     426     426     935     432     432    2712     432     432
    2712     428  422.45    2723     428  422.45    2723     432     432
    2740     432     432    2740     428  422.45    2754     428  422.45
    2754     432     432    4280     432     432    4280     428     428
Bank Sta=2390,2609.96
XS Rating Curve= 0 ,0
Exp/Cntr=0.6,0.4

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
Type RM Length L Ch R = 1 ,108231  ,80,81,85
BEGIN DESCRIPTION:
This cross section corresponds to cross section 108240   of the non-georeferenced CDC model which was the source of this model.
Cross-section modified for CDC DAL010909-1 Sante Fe Trestle Trail.
Cross-section added for CDC DAL090508-1 Standing Wave Park.
END DESCRIPTION:
XS GIS Cut Line= 6
2494432.104343836962639.204726712493774.446538426961184.15711188
2493700.286581756961017.247340712493536.178642246960749.66257405
 2493134.39696556960335.754609212492224.149920096959531.10403109
#Sta/Elev= 30
 1168.45     426 1223.94     423 1223.94  420.87 1265.44  406.55 1297.11  400.41
 1309.13  398.79 1384.41     398 1626.55  399.57 2092.16  398.32 2399.77  399.91
 2643.94  398.21    2676   388.3    2696   383.5 2696.01   380.5    2714   380.5
 2714.01   388.7 2722.01   388.7 2722.02   374.3    2754     371    2781     371
  2815.3     387    2833   389.2  2868.8     398 4161.95  398.42 4269.63  396.31
 4300.96  397.79 4508.49  398.42 4553.52  400.54 4553.52     428 5053.52     428
#Mann= 5 ,-1,0
 1168.45    .067       0 1297.11    .072       0 2092.16    .053       0
 2643.94     .03       0  2868.8    .065       0
Levee=-1,1172.676,425.9958,0,,,,
#XS Ineff= 2 ,-1
    3035    3525     423    4195 4553.52     423
Permanent Ineff=
       T       T
#XS Lid=12
 1168.45     426     426 1168.45     432     432    2942     432     432
    2942     428  422.45    2953     428  422.45    2953     432     432
    2970     432     432    2970     428  422.45    2984     428  422.45
    2984     432     432 4553.52     432     432 4553.52     428     428
Bank Sta=2643.94,2868.8
XS Rating Curve= 0 ,0
Exp/Cntr=0.6,0.4

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
Type RM Length L Ch R = 1 ,108120  ,17,13,21
BEGIN DESCRIPTION:
This cross section corresponds to cross section 108128   of the non-georeferenced CDC model which was the source of this model.
Cross-section modified for CDC DAL010909-1 Sante Fe Trestle Trail.
Cross-section modified for CDC DAL090508-1 Standing Wave Park.
END DESCRIPTION:
XS GIS Cut Line= 6
2495545.041263366964810.547985972494553.875425766962631.36780013
2493725.000115016960809.000053792493113.000026676960147.00006546
2492733.611677836959739.951338892491740.152625186958674.06135171
#Sta/Elev= 30
    -354  427.12 -144.29  422.94 -114.33  405.43  -49.42  406.41  -29.45   420.6
  100.37  420.97  714.51  409.08  999.12  416.54 1498.42  398.75  1588.3  415.54
  1663.2  400.34 2042.67  398.75    2172     398    3005   399.5    3592     399
 3631.51   378.7 3652.51   386.4    3718   380.9 3758.78     394    3960     399
    4982   403.1    5210     390 5497.71  408.94 6012.49  408.13 6102.45  418.63
 6272.38     394 6427.31  407.56 6637.22  402.16  6907.1  414.94 6957.08  429.03
#Mann= 8 ,-1,0
    -354    .055       0 2042.67    .035       0    2172    .075       0
    3005    .065       0    3592    .028       0 3652.51    .025       0
 3758.78    .028       0    3960    .065       0
#XS Ineff= 2 ,-1
    3990    4400     423    5215    5500     423
Permanent Ineff=
       T       T
#XS Lid=18
    2025  425.98  425.98    2025     432     432    3846     432     432
    3846  422.15  416.66    3857  422.15  416.66    3857     432     432
    3886     432     432    3886  423.26  417.77    3896  423.26  417.77
    3896     432     432    3904     432     432    3904  424.84  419.34
    3916  424.84  419.34    3916  426.42  420.93    3936  426.42  420.93
    3936     432     432    5500     432     432    5500     428     428
Bank Sta=3592,3758.78
XS Rating Curve= 0 ,0
Exp/Cntr=0.6,0.4

Type RM Length L Ch R = 1 ,108107  ,20,16,25
BEGIN DESCRIPTION:
This cross section corresponds to cross section 108116   of the non-georeferenced CDC model which was the source of this model.
Cross-section modified for CDC DAL010909-1 Sante Fe Trestle Trail.
Cross-section modified for CDC DAL090508-1 Standing Wave Park.
END DESCRIPTION:
XS GIS Cut Line= 6
2495566.706791926964824.823646992494569.965288586962634.56825306
2493736.00009301 6960802.00006782493122.000008676960139.00008146
2492718.084149846959705.64727363 2491753.73148546958671.01363462
#Sta/Elev= 30
    -334  427.14  -99.48  421.74  -74.53   405.8   -4.68  407.07   15.28  420.35
  135.03  420.61 2076.07  398.99 2205.97  398.57 3038.54  399.35 3626.23     399
 3675.01   379.3    3703   386.4 3715.51     378  3765.5     378 3824.21     395
 3931.18  398.16    4930     395    4972   402.5 5266.85  390.81 5585.48  405.85
 5640.31  395.92 5754.96  408.11 6069.01  408.26 6178.68  418.14 6303.31  392.97
 6368.11  403.95 6707.09  402.95 6826.73   416.4 6951.35  415.36 6996.21   428.9
#Mann= 9 ,-1,0
    -334    .055       0 2076.07    .035       0 2205.97    .075       0
 3038.54    .065       0 3626.23    .029       0 3715.51    .025       0
  3765.5    .029       0 3931.18    .065       0 5585.48    .065       0
#XS Ineff= 3 ,-1
    4040    4440     423    5265    5550     423    5550    5582     430
Permanent Ineff=
       T       T       T
#XS Lid=9
    2025     432     432    3904     432     432    3904  424.84  419.34
    3916  424.84  419.34    3916  426.42  420.93    3936  426.42  420.93
    3936     432     432 5581.84     432     432 5581.84  426.31  426.31
Bank Sta=3626.23,3824.21
XS Rating Curve= 0 ,0
Exp/Cntr=0.6,0.4

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
Type RM Length L Ch R = 1 ,107955  ,217,186,248
BEGIN DESCRIPTION:
This cross section corresponds to cross section 107965   of the non-georeferenced CDC model which was the source of this model.
Cross-section modified for CDC DAL010909-1 Sante Fe Trestle Trail.
END DESCRIPTION:
XS GIS Cut Line= 5
2495890.163000836964670.02308867 2494781.46453756962531.31583488
2493856.99985102 6960748.00017582492792.274290176959209.12201996
2492048.817903236958134.58334469
#Sta/Elev= 30
      71  428.26  490.67  414.36 1649.74  409.75  1699.7  418.29 2004.46  418.64
 2094.39  460.11  2324.2   462.4 2384.15  426.78 2484.07  415.87 2559.03  397.11
    2616     397    3490     398    4057     399    4124   370.5    4179   370.5
    4238     400    4730     392    4885     399    5090     389  5193.5     402
    5320     400    5360     386    5433     397 6428.98  404.38 6923.05  418.38
 7037.84   413.8 7117.69  397.93 7262.42  407.99  7377.2   400.5 7666.66  429.06
#Mann= 6 ,-1,0
      71    .055       0 2484.07    .035       0    2616    .075       0
    3490    .065       0    4057    .035       0    4238    .065       0
#XS Ineff= 3 ,-1
    4510    4795     423    5860    6070     423    6070    6070     430
Permanent Ineff=
       T       T       T
#Block Obstruct= 2 ,-1
  5152.5  5331.5     402  4300.5  4313.5  412.55
#XS Lid=10
    2480  425.97  425.97    2480     432     432  4273.5     432     432
  4273.5  419.45  413.95  4291.5  419.45  413.95  4291.5  421.07  415.57
  4313.5  421.07  415.57  4313.5     432     432    6360     432     432
    6360     405     405
Bank Sta=4057,4238
XS Rating Curve= 0 ,0
Exp/Cntr=0.5,0.3

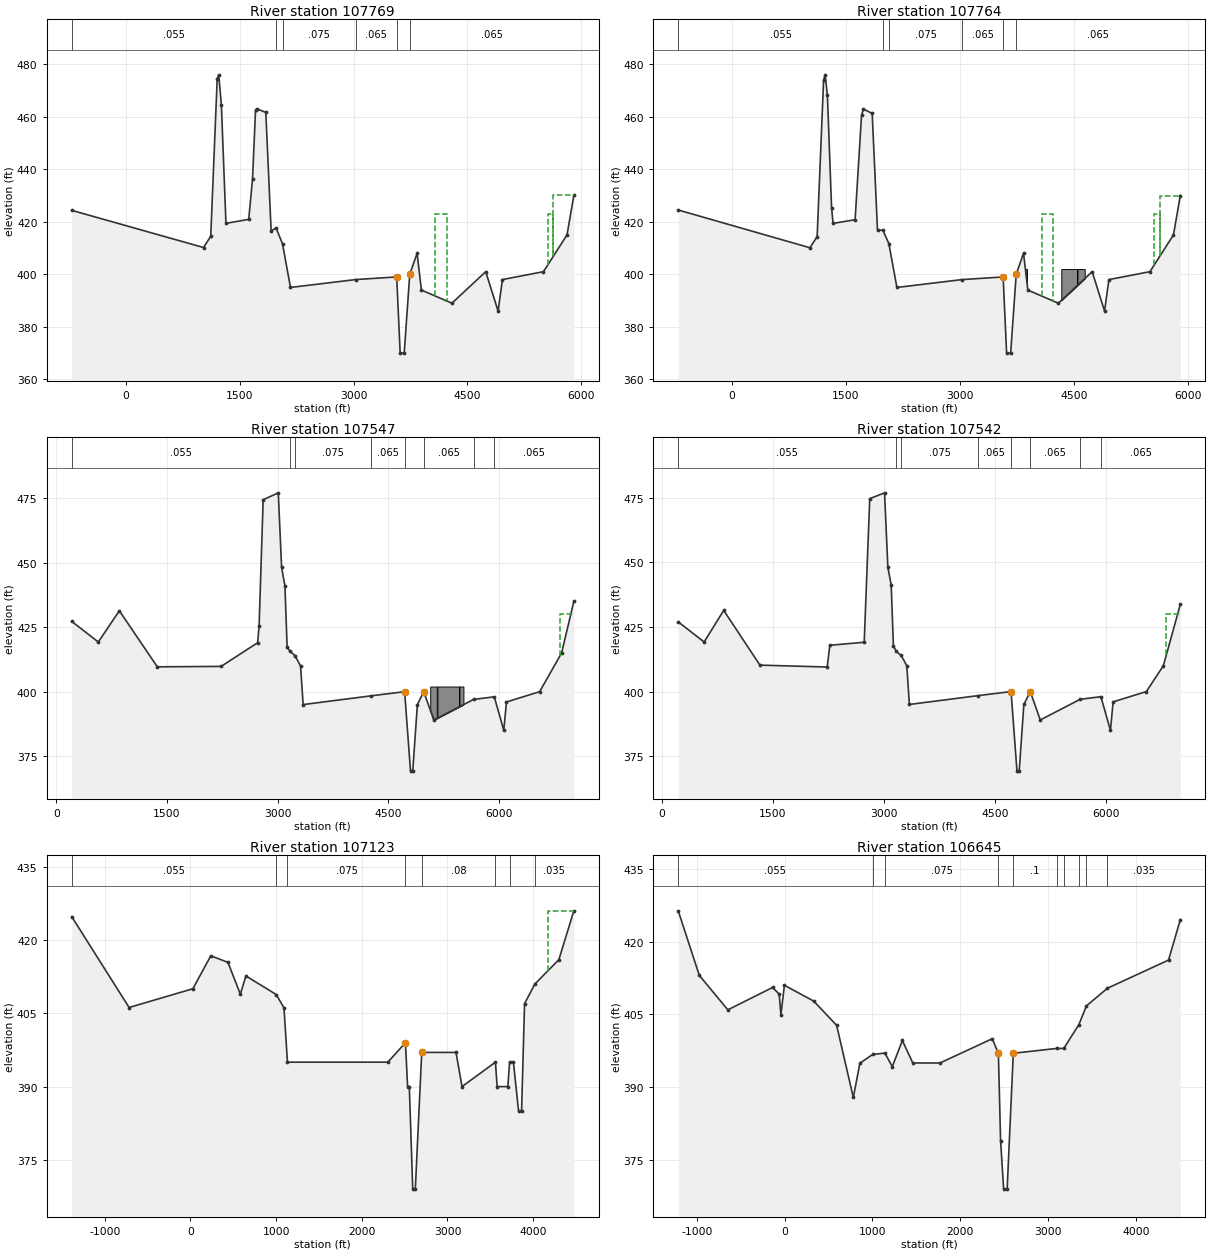
Type RM Length L Ch R = 1 ,107769  ,5,5,5
BEGIN DESCRIPTION:
This cross section corresponds to cross section 107781   of the non-georeferenced CDC model which was the source of this model.
Cross-section added for CDC DAL010909-1 Sante Fe Trestle Trail.
END DESCRIPTION:
XS GIS Cut Line= 4
2496326.946156066964752.304373722495000.405372596962413.28523105
2494168.882757436960947.105420632493040.743937586959018.36879255
#Sta/Elev= 30
    -709  424.34 1025.49  410.19 1120.46  414.49 1205.44  474.42 1225.43  475.92
 1260.42  464.43 1320.41  419.39 1620.31  420.91  1670.3  436.21 1710.28  462.58
 1730.28  462.95 1845.24  461.62 1915.22  416.53 1980.17  417.66 2064.95  411.61
    2170     395    3030     398    3568     399    3614     370    3667     370
    3740     400  3836.5     408 3893.58     394    4295     389    4740     401
    4903     386    4960     398    5500     401    5810     415    5900     430
#Mann= 6 ,-1,0
    -709    .055       0 1980.17    .035       0 2064.95    .075       0
    3030    .065       0    3568    .035       0    3740    .065       0
#XS Ineff= 3 ,-1
    4075    4230     423    5555    5630     423    5630    5900     430
Permanent Ineff=
       T       T       T
Bank Sta=3568,3740
XS Rating Curve= 0 ,0
Exp/Cntr=0.5,0.3

Type RM Length L Ch R = 1 ,107764  ,217,217,217
BEGIN DESCRIPTION:
This cross section corresponds to cross section 107776  of the non-georeferenced CDC model which was the source of this model.
Cross-section modified for CDC DAL010909-1 Sante Fe Trestle Trail.
END DESCRIPTION:
XS GIS Cut Line= 4
2496333.738004546964747.767083782495006.060873096962410.54278247
2494173.34731543 6960944.64545182493045.72817957 6959016.0016713
#Sta/Elev= 30
    -708  424.48  1025.4  410.11 1120.31  414.34 1205.23  473.91 1225.21  475.94
 1255.19  468.15 1310.14  425.29 1330.12  419.39 1619.85  420.78 1704.77  460.57
 1729.75  462.88 1844.64  461.27 1914.58  416.74 1984.49  416.85 2064.29  411.67
    2170     395    3030     398    3568     399    3614     370    3667     370
    3740     400  3836.5     408 3893.58     394    4295     389    4740     401
    4903     386    4960     398    5500     401    5810     415    5900     430
#Mann= 6 ,-1,0
    -708    .055       0 1984.49    .035       0 2064.29    .075       0
    3030    .065       0    3568    .035       0    3740    .065       0
#XS Ineff= 3 ,-1
    4080    4230     423    5560    5630     423    5630    5900     430
Permanent Ineff=
       T       T       T
#Block Obstruct= 3 ,-1
    3840  3882.5     402  4333.5    4541     402    4547  4641.5     402
Bank Sta=3568,3740
XS Rating Curve= 0 ,0
Exp/Cntr=0.5,0.3

Type RM Length L Ch R = 1 ,107547  ,5,5,5
BEGIN DESCRIPTION:
This cross section corresponds to cross section 107551   of the non-georeferenced CDC model which was the source of this model.
Cross-section modified for CDC DAL010909-1 Sante Fe Trestle Trail.
END DESCRIPTION:
XS GIS Cut Line= 4
2496682.692864996964846.322445572495202.087383936962289.01284181
2493278.051861916958965.808530212493273.99330049 6958958.7985615
#Sta/Elev= 30
     210  427.23  569.77  419.25  854.59  431.37 1369.26  409.63 2233.71   409.8
 2728.39  418.97 2748.37  425.47 2803.34  474.38 3008.21  477.08 3053.18  448.18
 3098.15  441.01 3128.13  417.19  3168.1  415.66    3233     414    3310     410
    3345     395    4270   398.4    4720     400    4800   369.2    4830   369.2
    4893     395    4980     400    5115     389    5655     397    5935     398
    6064     385    6100     396    6550     400    6847     415  7013.1  434.98
#Mann= 8 ,-1,0
     210    .055       0  3168.1    .035       0    3233    .075       0
    4270    .065       0    4720    .035       0    4980    .065       0
    5655    .055       0    5935    .065       0
#XS Ineff= 2 ,-1
                            6820    6820     430
Permanent Ineff=
       F       T
#Block Obstruct= 3 ,-1
    5067 5155.85     402 5164.15 5457.23     402 5462.77    5517     402
Bank Sta=4720,4980
XS Rating Curve= 0 ,0
Exp/Cntr=0.5,0.3

Type RM Length L Ch R = 1 ,107542  ,419,419,419
BEGIN DESCRIPTION:
This cross section corresponds to cross section 107546   of the non-georeferenced CDC model which was the source of this model.
Cross-section added for CDC DAL010909-1 Sante Fe Trestle Trail.
This is the approximate location of the borrow area used for CDC DAL061307-1 Moore Park Gateway Phase 1.  The borrow area for this project is in the same area as the borrow area for SFTT.  No additional modifications to the model have been made for the Moore Park project.
END DESCRIPTION:
XS GIS Cut Line= 4
2496685.604602786964840.402009452495209.286844586962291.00955696
2493284.962281176958967.972567892493282.977841036958964.54571978
#Sta/Elev= 30
     219  426.96     569  419.18  833.99   431.4 1323.99  410.22 2233.98  409.49
 2268.98   417.9 2733.97  419.07 2808.97  474.64 3008.96   476.9 3053.96  448.07
 3098.96  441.25 3128.96  417.63 3168.96  415.51    3233     414    3310     410
    3345     395    4270   398.4    4720     400    4800   369.2    4830   369.2
    4893     395    4980     400    5115     389    5655     397    5935     398
    6064     385    6100     396    6550     400    6780     410 7008.96  433.72
#Mann= 8 ,-1,0
     219    .055       0 3168.96    .035       0    3233    .075       0
    4270    .065       0    4720    .035       0    4980    .065       0
    5655    .055       0    5935    .065       0
#XS Ineff= 2 ,-1
                            6820    6820     430
Permanent Ineff=
       F       T
Bank Sta=4720,4980
XS Rating Curve= 0 ,0
Exp/Cntr=0.5,0.3

Type RM Length L Ch R = 1 ,107123  ,388,478,488
BEGIN DESCRIPTION:
This cross section corresponds to cross section 107130  of the non-georeferenced CDC model which was the source of this model.
Cross-section modified for CDC DAL010909-1 Sante Fe Trestle Trail.
Downstream limit of CDC DAL010909-1 Sante Fe Trestle Trail.
END DESCRIPTION:
XS GIS Cut Line= 4
2496741.707901796964124.809552342495553.154923266962058.21868397
2494741.613895426960647.155561222493811.790295756959051.03047264
#Sta/Elev= 30
   -1384  424.79 -714.95   406.2      29  410.04   238.7  416.79  438.42  415.44
  583.21  408.94  648.12  412.66 1002.62  408.85  1092.5  406.12    1133     395
    2305     395    2510     399    2535     390    2555     390    2595     369
    2625     369    2700     397    3100     397    3170     390    3560     395
    3580     390    3705     390    3725     395    3770     395    3830     385
    3865     385    3900     407    4020     411    4300     416    4475     426
#Mann= 8 ,-1,0
   -1384    .055       0 1002.62    .035       0    1133    .075       0
    2510     .04       0    2700     .08       0    3560    .055       0
    3725     .08       0    4020    .035       0
#XS Ineff= 2 , 0
       0                    4170       0     426
Permanent Ineff=
       F       F
Bank Sta=2510,2700
XS Rating Curve= 0 ,0
Exp/Cntr=0.3,0.1

Type RM Length L Ch R = 1 ,106645  ,414,536,468
BEGIN DESCRIPTION:
106650  Cedar Creek
END DESCRIPTION:
XS GIS Cut Line= 6
2496925.278572476963799.093106562495864.556859496961858.00747022
2495217.000083746960672.999997722495192.000133756960454.00010763
2494571.805179926959346.67095746 2494245.60658076958764.25857983
#Sta/Elev= 30
   -1212  426.36 -972.07  413.06 -647.16  405.95  -137.3  410.56  -62.32   409.2
  -42.33  404.98   -2.34  411.02  332.57  407.74  592.49  402.76  782.44  387.89
  857.42  394.95 1002.38  396.75 1141.92  397.04 1226.63  394.25 1341.24  399.64
    1460     395    1770     395    2365     400    2435     397    2460     379
    2495     369    2535     369    2605     397    3100     398    3180     398
 3352.69  402.93 3437.64  406.76 3677.48  410.41 4373.52  416.21 4507.54  424.54
#Mann= 10 ,-1,0
   -1212    .055       0 1002.38    .035       0 1141.92    .075       0
    2435     .04       0    2605      .1       0    3100    .045       0
    3180    .065       0 3352.69    .035       0 3437.64    .045       0
 3677.48    .035       0
Bank Sta=2435,2605
XS Rating Curve= 0 ,0
Exp/Cntr=0.5,0.3

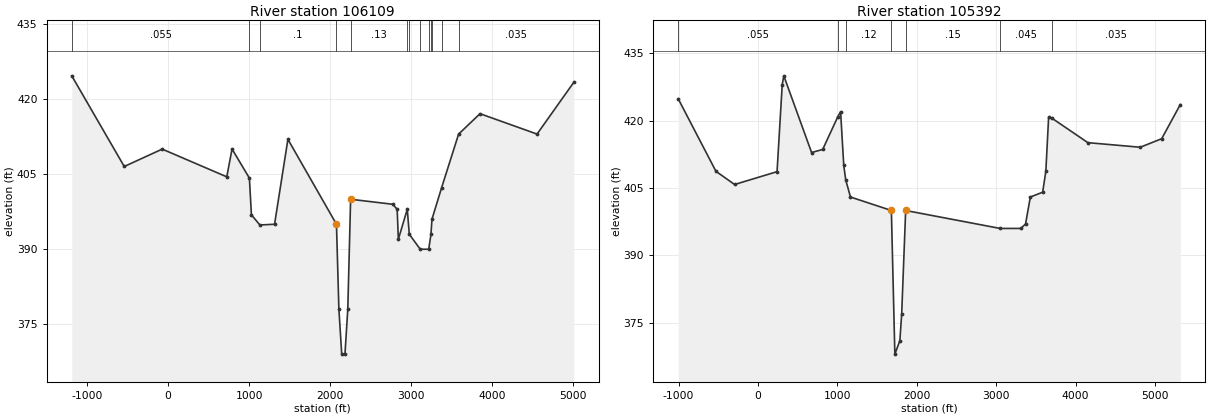
Type RM Length L Ch R = 1 ,106109  ,503,717,362
BEGIN DESCRIPTION:
This cross section corresponds to cross section 106100 of the non-georeferenced CDC model which was the source of this model.
END DESCRIPTION:
XS GIS Cut Line= 6
2497370.719743286963502.989663832496240.99573916 6961625.7031448
  2495681.4410846960695.879217042495753.58824942 6960538.9021688
2495109.308041936959248.826336882494522.449558366958073.72901493
#Sta/Elev= 30
   -1191  424.71 -542.45  406.56  -73.51  410.04   724.7  404.49  789.56  410.06
 1004.07  404.23 1028.96  396.89  1133.5  394.85    1315     395    1480     412
    2080     395    2110     378    2145     369    2185     369    2220     378
    2255     400    2775     399    2830     398    2845     392    2955     398
    2980     393    3115     390    3220     390    3248     393    3260     396
 3379.73  402.33  3589.3  413.04 3854.01  417.13  4558.7  413.05 5013.49  423.43
#Mann= 13 ,-1,0
   -1191    .055       0 1004.07    .035       0  1133.5      .1       0
    2080    .045       0    2255     .13       0    2955    .035       0
    2980    .045       0    3115    .025       0    3220    .045       0
    3248    .035       0    3260    .065       0 3379.73    .045       0
  3589.3    .035       0
Bank Sta=2080,2255
XS Rating Curve= 0 ,0
Exp/Cntr=0.3,0.1

Type RM Length L Ch R = 1 ,105392  ,69,69,69
BEGIN DESCRIPTION:
This cross section corresponds to cross section 105387 of the non-georeferenced CDC model which was the source of this model.
END DESCRIPTION:
XS GIS Cut Line= 6
2497568.453920326963387.736807152496745.943548176961560.30891864
2496719.170963916961500.826426042496367.382297436960867.10918956
2495429.785419346959168.772035052494661.978488556957777.98771343
#Sta/Elev= 30
   -1004  424.87 -529.19  408.73 -294.28  405.79  240.52  408.65  305.49  428.04
  325.48     430  675.35  412.91  815.29   413.6 1003.19   420.8 1040.46  422.01
 1080.45  410.05 1105.45  406.79    1165     403    1680     400    1724     368
    1787     371    1810     377    1860     400    3050     396    3310     396
    3370     397    3430     403 3585.25  404.07 3625.25  408.73 3660.25  420.75
 3705.25  420.52  4154.8  415.11 4814.15  414.09 5083.88  415.99 5318.65   423.6
#Mann= 7 ,-1,0
   -1004    .055       0 1003.19    .035       0 1105.45     .12       0
    1680     .05       0    1860     .15       0    3050    .045       0
 3705.25    .035       0
Bank Sta=1680,1860
XS Rating Curve= 0 ,0
Exp/Cntr=0.5,0.3