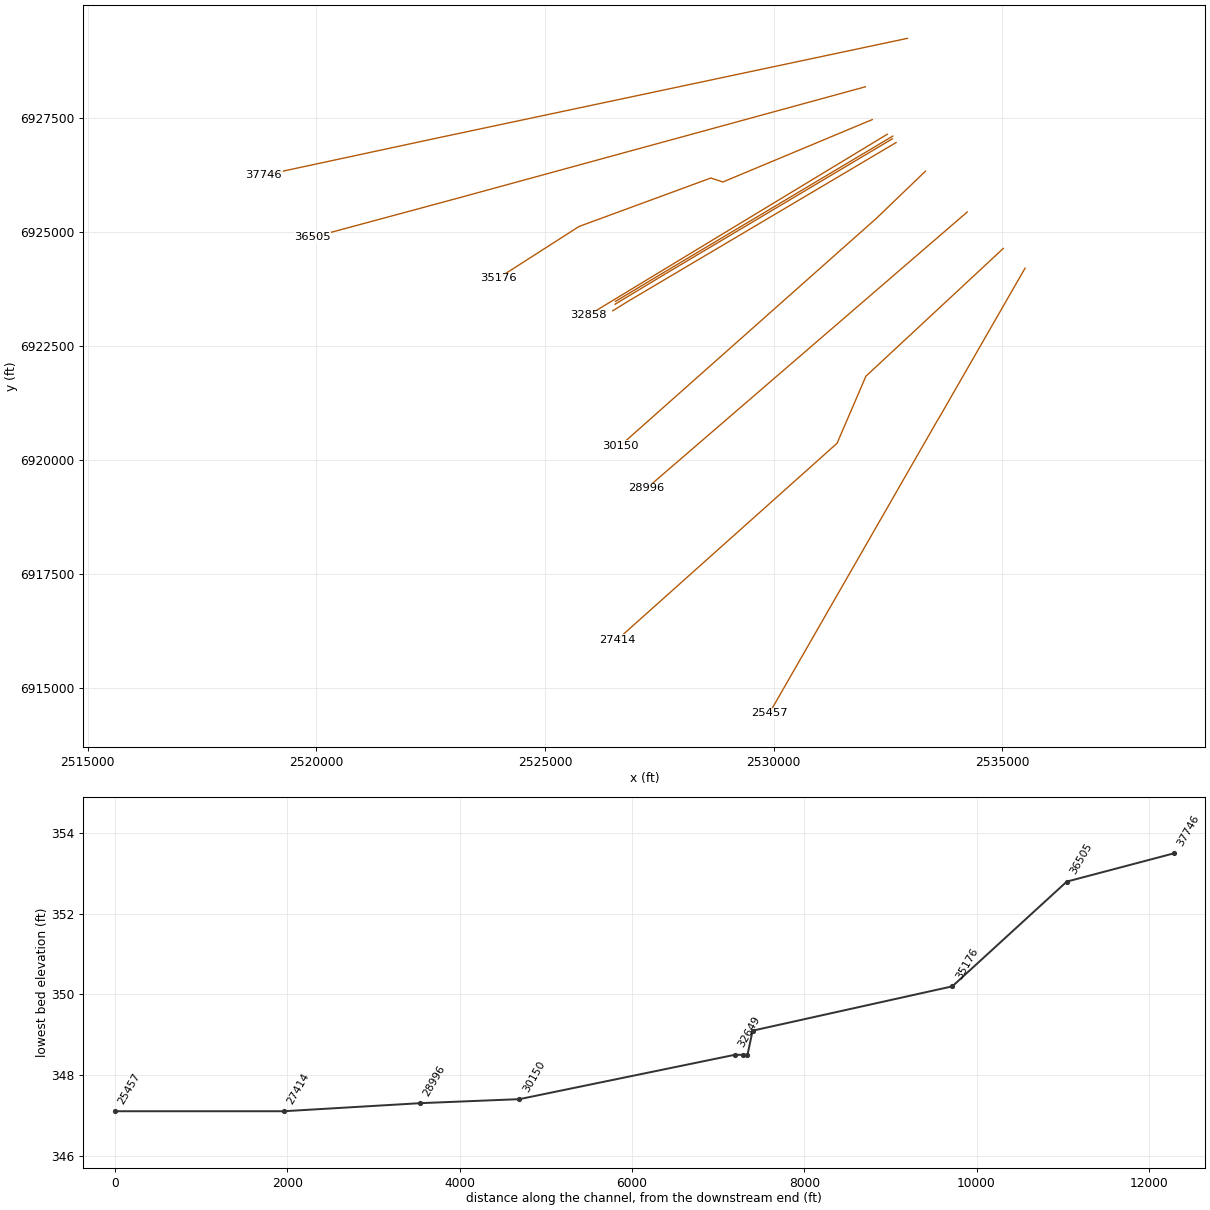
HEC-RAS study CDC_Consolidated_Model.prj: Upper Trinity CDC Consolidated Model

--- CDC_Consolidated_Model.g02 (geometry) --- (continued)

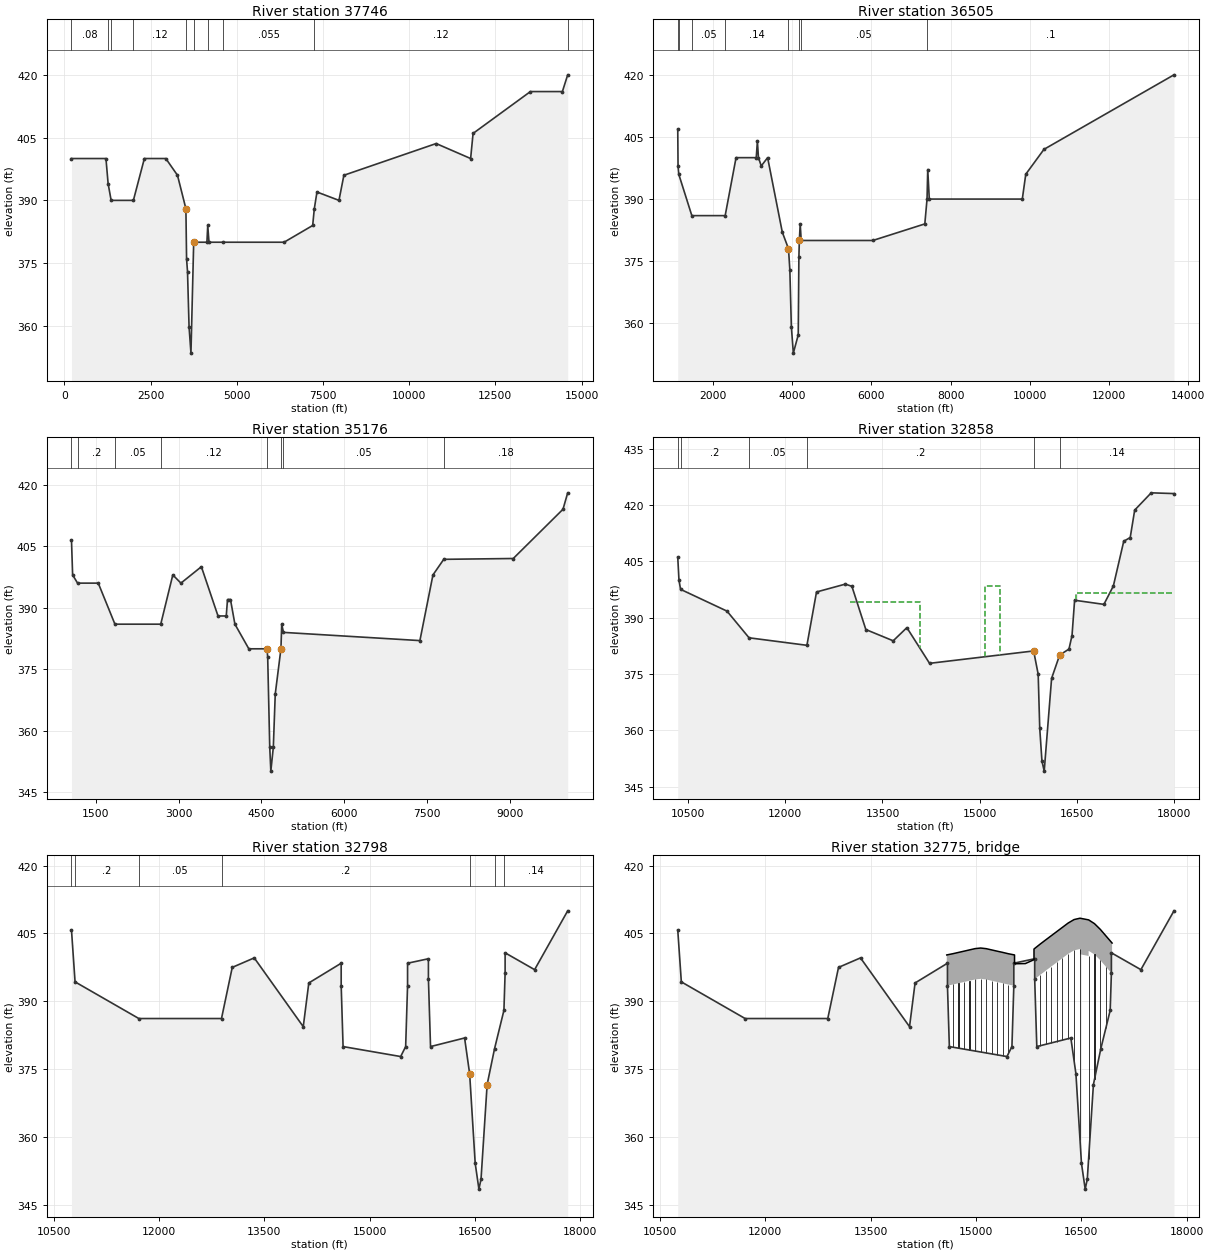
Type RM Length L Ch R = 1 ,37746   ,960,1241,1260
BEGIN DESCRIPTION:
This cross section corresponds to cross section 37760 of the non-georeferenced CDC model which was the source of this model.
END DESCRIPTION:
XS GIS Cut Line= 4
2532926.589845656929248.149480832531948.441056436929040.24338147
2522565.999847596927045.999994642518848.287794836926245.29293463
#Sta/Elev= 30
     204     400    1204     400  1266.9     394  1354.7     390  1999.9     390
  2318.6     400  2940.7     400    3279     396  3523.6     388  3542.8     376
    3570     373    3615   359.8    3670   353.5  3749.5     380  4133.3     380
  4156.8     384  4193.4     380  4599.5     380  6371.5     380    7201     384
  7248.3     388  7325.8     392  7963.8     390  8106.1     396   10783  403.58
   11783     400   11854     406   13518     416   14445     416   14599     420
#Mann= 10 ,-1,0
     204     .08       0  1266.9     .08       0  1354.7     .05       0
  1999.9     .12       0  3523.6    .055       0  3749.5      .2       0
  4156.8     .05       0  4599.5    .055       0  7248.3     .12       0
   14599       2       0
#XS Ineff= 2 , 0
          3523.6     388  3749.5             380
Permanent Ineff=
       F       F
Bank Sta=3523.6,3749.5
XS Rating Curve= 0 ,0
Exp/Cntr=0.3,0.1

Type RM Length L Ch R = 1 ,36505   ,951,1329,1302
BEGIN DESCRIPTION:
This cross section corresponds to cross section 36519 of the non-georeferenced CDC model which was the source of this model.
END DESCRIPTION:
XS GIS Cut Line= 3
 2532005.15419766928185.576127542523073.000145916925737.99998596
 2519915.63113266924884.57649596
#Sta/Elev= 30
  1108.9   406.9  1116.4     398  1134.2     396  1464.7     386  2306.4     386
  2581.6     400  3091.6     400  3120.2     404  3147.1     400    3218     398
  3378.7     400  3749.4     382  3905.9     378    3940   372.9    3978   359.2
    4028   352.8    4152   357.2  4168.3     376  4179.8     380  4201.7     384
  4226.5     380  6035.5     380  7348.6     384  7404.8     390  7422.4  397.13
  7461.8     390  9810.8     390  9898.4     396   10357     402   13641     420
#Mann= 8 ,-1,0
  1108.9     .03       0  1134.2      .1       0  1464.7     .05       0
  2306.4     .14       0  3905.9    .055       0  4179.8      .2       0
  4226.5     .05       0  7404.8      .1       0
#XS Ineff= 2 , 0
          3905.9     378  4179.8             380
Permanent Ineff=
       F       F
Bank Sta=3905.9,4179.8
XS Rating Curve= 0 ,0
Exp/Cntr=0.3,0.1

Type RM Length L Ch R = 1 ,35176   ,849,2318,1797
BEGIN DESCRIPTION:
This cross section corresponds to cross section 35192 of the non-georeferenced CDC model which was the source of this model.
END DESCRIPTION:
XS GIS Cut Line= 5
2532155.647334936927466.298694712528888.999996846926097.99992213
2528625.999866666926185.000076222525745.000051266925123.00023171
2523980.464538346923989.68852197
#Sta/Elev= 30
  1059.7   406.5  1080.5     398  1170.1     396  1544.8     396  1846.7     386
  2676.3     386  2894.7     398  3041.7     396    3412     400  3713.4     388
  3862.6     388  3885.2     392  3939.2     392  4019.4     386  4271.3     380
  4599.5     380    4613     378    4650   356.1    4670   350.2    4715     356
    4750     369    4853     380    4867     386  4898.5     384  7369.4     382
  7605.9     398  7801.3   401.8  9060.1     402    9961     414   10046     418
#Mann= 8 ,-1,0
  1059.7     .03       0  1170.1      .2       0  1846.7     .05       0
  2676.3     .12       0  4599.5    .055       0    4853      .2       0
  4898.5     .05       0  7801.3     .18       0
#XS Ineff= 2 , 0
          4599.5     380    4853             380
Permanent Ineff=
       F       F
Bank Sta=4599.5,4853
XS Rating Curve= 0 ,0
Exp/Cntr=0.3,0.1

Type RM Length L Ch R = 1 ,32858   ,60,60,60
BEGIN DESCRIPTION:
This cross section corresponds to cross section 32870 of the non-georeferenced CDC model which was the source of this model.
END DESCRIPTION:
XS GIS Cut Line= 2
 2532484.41898716927145.076568132525940.685355426923170.92441146
#Sta/Elev= 30
   10341   406.1   10360   399.9   10385   397.5   11101   391.7   11441   384.6
   12334   382.6   12482   396.8   12928   398.9   13028   398.3   13243   386.8
   13665   383.8   13876   387.3   14226   377.8   15832   381.1   15902   374.9
   15926   360.5   15960   351.8   15995   349.1   16109   373.8   16233     380
   16377   381.6   16424   385.2   16464   394.6   16916   393.5   17062   398.4
   17222   410.3   17322   411.3   17391   418.6   17646   423.2   17997     423
#Mann= 6 ,-1,0
   10341     .03       0   10385      .2       0   11441     .05       0
   12334      .2       0   15832    .055       0   16233     .14       0
#XS Ineff= 3 ,-1
   13000   14085     394   15085   15320   398.3   16480   17997   396.6
Permanent Ineff=
       F       F       F
Bank Sta=15832,16233
XS Rating Curve= 0 ,0
Exp/Cntr=0.3,0.1

Type RM Length L Ch R = 1 ,32798   ,47,47,47
BEGIN DESCRIPTION:
This cross section corresponds to cross section 32796 of the non-georeferenced CDC model which was the source of this model.
END DESCRIPTION:
XS GIS Cut Line= 3
2532603.880034276927103.952306552527617.459232846924126.36967905
2526539.912503426923478.69938646
#Sta/Elev= 30
   10755   405.8   10806   394.3   11714   386.2   12891   386.2   13044   397.5
   13357   399.6   14055   384.4   14134  394.06   14595  398.42   14595  393.44
   14622     380   15442   377.8   15513     380   15540  393.44   15540  398.42
   15837  399.41   15837  394.95   15867     380   16352   381.9   16424     374
   16503   354.2   16556   348.5   16586   350.7   16673   371.6   16778   379.5
   16912     388   16929  396.27   16929  400.72   17349     397   17820     410
#Mann= 7 ,-1,0
   10755     .03       0   10806      .2       0   11714     .05       0
   12891      .2       0   16424    .055       0   16778      .2       0
   16912     .14       0
#XS Ineff= 1 ,-1
   13500   14134     394
Permanent Ineff=
       F
Bank Sta=16424,16673
XS Rating Curve= 0 ,0
Exp/Cntr=0.3,0.1

Type RM Length L Ch R = 3 ,32775   ,,,
BEGIN DESCRIPTION:
32772  Dowdy-Ferry Road
Bridge data revised May 2002 from bridge plans dated 12-98 supplied by TXDOT.  Bridge plans supplied in metric, therefore stationing and elevations were converted to english prior to input.  Main bridge length is 1092.2 ft. (333.0 m) and relief bridge length is 944.6 ft (288.0m).
END DESCRIPTION:
Node Name=Dowdy-Ferry Road
Bridge Culvert--1,0,-1,-1, 0
Deck Dist Width WeirC Skew NumUp NumDn MinLoCord MaxHiCord MaxSubmerge Is_Ogee
1.5,44,2.6,0, 33, 33, , , 0.95, 0, ,,,
   14585   14674   14753   14832   14910   14989   15068   15146   15225   15304
   15383   15461   15550   15550   15571   15703   15827   15827   15916   15994
   16073   16152   16231   16314   16398   16482   16482   16605   16605   16688
   16772   16851   16939
  400.25  400.53  400.81  401.09  401.37  401.65  401.78  401.64  401.36  401.08
  400.81  400.52  400.25  398.42  398.31  398.34   399.2  401.56  402.66  403.58
   404.5  405.42  406.34  407.31  408.07  408.37  408.37     408     408  407.17
  405.89  404.46  402.88
  393.44  393.72     394  394.28  394.56  394.84  394.97  394.83  394.55  394.27
     394  393.71  393.44  398.42  398.31  398.34   399.2  394.75  395.85  396.77
  397.69  398.61  399.53   400.5  401.26  401.56   400.4  400.02  401.17  400.36
  399.08  397.65  396.07
   14585   14674   14753   14832   14910   14989   15068   15146   15225   15304
   15383   15461   15550   15550   15571   15703   15827   15827   15916   15994
   16073   16152   16231   16314   16398   16482   16482   16605   16605   16688
   16772   16851   16939
  400.25  400.53  400.81  401.09  401.37  401.65  401.78  401.64  401.36  401.08
  400.81  400.52  400.25  398.42  398.31  398.34   399.2  401.56  402.66  403.58
   404.5  405.42  406.34  407.31  408.07  408.37  408.37     408     408  407.17
  405.89  404.46  402.88
  393.44  393.72     394  394.28  394.56  394.84  394.97  394.83  394.55  394.27
     394  393.71  393.44  398.42  398.31  398.34   399.2  394.75  395.85  396.77
  397.69  398.61  399.53   400.5  401.26  401.56   400.4  400.02  401.17  400.36
  399.08  397.65  396.07
Pier Skew, UpSta & Num, DnSta & Num=  ,14674, 2 ,14674, 2 , 0 , 0 , 0 ,,
     2.5     2.5
       0     396
     2.5     2.5
       0     396
Pier Skew, UpSta & Num, DnSta & Num=  ,14753, 2 ,14753, 2 , 0 , 0 , 0 ,,
     2.5     2.5
       0     396
     2.5     2.5
       0     396
Pier Skew, UpSta & Num, DnSta & Num=  ,14832, 2 ,14832, 2 , 0 , 0 , 0 ,,
     2.5     2.5
       0     396
     2.5     2.5
       0     396
Pier Skew, UpSta & Num, DnSta & Num=  ,14910, 2 ,14910, 2 , 0 , 0 , 0 ,,
     2.5     2.5
       0     396
     2.5     2.5
       0     396
Pier Skew, UpSta & Num, DnSta & Num=  ,14989, 2 ,14989, 2 , 0 , 0 , 0 ,,
     2.5     2.5
       0     396
     2.5     2.5
       0     396
Pier Skew, UpSta & Num, DnSta & Num=  ,15068, 2 ,15068, 2 , 0 , 0 , 0 ,,
     2.5     2.5
       0     396
     2.5     2.5
       0     396
Pier Skew, UpSta & Num, DnSta & Num=  ,15146, 2 ,15146, 2 , 0 , 0 , 0 ,,
     2.5     2.5
       0     396
     2.5     2.5
       0     396
Pier Skew, UpSta & Num, DnSta & Num=  ,15225, 2 ,15225, 2 , 0 , 0 , 0 ,,
     2.5     2.5
       0     396
     2.5     2.5
       0     396
Pier Skew, UpSta & Num, DnSta & Num=  ,15304, 2 ,15304, 2 , 0 , 0 , 0 ,,
     2.5     2.5
       0     396
     2.5     2.5
       0     396
Pier Skew, UpSta & Num, DnSta & Num=  ,15383, 2 ,15383, 2 , 0 , 0 , 0 ,,
     2.5     2.5
       0     396
     2.5     2.5
       0     396
Pier Skew, UpSta & Num, DnSta & Num=  ,15461, 2 ,15461, 2 , 0 , 0 , 0 ,,
     2.5     2.5
       0     396
     2.5     2.5
       0     396
Pier Skew, UpSta & Num, DnSta & Num=  ,15916, 2 ,15916, 2 , 0 , 0 , 0 ,,
     2.5     2.5
       0     400
     2.5     2.5
       0     400
Pier Skew, UpSta & Num, DnSta & Num=  ,15994, 2 ,15994, 2 , 0 , 0 , 0 ,,
     2.5     2.5
       0     400
     2.5     2.5
       0     400
Pier Skew, UpSta & Num, DnSta & Num=  ,16073, 2 ,16073, 2 , 0 , 0 , 0 ,,
     2.5     2.5
       0     400
     2.5     2.5
       0     400
Pier Skew, UpSta & Num, DnSta & Num=  ,16152, 2 ,16152, 2 , 0 , 0 , 0 ,,
     2.5     2.5
       0     401
     2.5     2.5
       0     401
Pier Skew, UpSta & Num, DnSta & Num=  ,16231, 2 ,16231, 2 , 0 , 0 , 0 ,,
     2.5     2.5
       0     401
     2.5     2.5
       0     401
Pier Skew, UpSta & Num, DnSta & Num=  ,16314, 2 ,16314, 2 , 0 , 0 , 0 ,,
     2.5     2.5
       0     402
     2.5     2.5
       0     402
Pier Skew, UpSta & Num, DnSta & Num=  ,16398, 2 ,16398, 2 , 0 , 0 , 0 ,,
     2.5     2.5
       0     403
     2.5     2.5
       0     403
Pier Skew, UpSta & Num, DnSta & Num=  ,16482, 2 ,16482, 2 , 0 , 0 , 0 ,,
     3.5     3.5
       0     403
     3.5     3.5
       0     403
Pier Skew, UpSta & Num, DnSta & Num=  ,16605, 2 ,16605, 2 , 0 , 0 , 0 ,,
     3.5     3.5
       0     403
     3.5     3.5
       0     403
Pier Skew, UpSta & Num, DnSta & Num=  ,16688, 2 ,16688, 2 , 0 , 0 , 0 ,,
     2.5     2.5
       0     403
     2.5     2.5
       0     403
Pier Skew, UpSta & Num, DnSta & Num=  ,16772, 2 ,16772, 2 , 0 , 0 , 0 ,,
     2.5     2.5
       0     403
     2.5     2.5
       0     403
Pier Skew, UpSta & Num, DnSta & Num=  ,16851, 2 ,16851, 2 , 0 , 0 , 0 ,,
     2.5     2.5
       0     403
     2.5     2.5
       0     403
BR Coef= 1 , 0 , 0 ,1.05, 0 ,,,0.8,-1,0.5,1,
WSPro=,,,, 1 ,,,, 0 ,,,, 0 ,,,,-1 ,-1 ,-1 , 0 , 0 , 0 , 0 , 0
BC Design=,, 0 ,, 0 ,,,,,,
BC HTab HWMax=410
BC Use User HTab Curves=0
BC User HTab FreeFlow(D)= 0

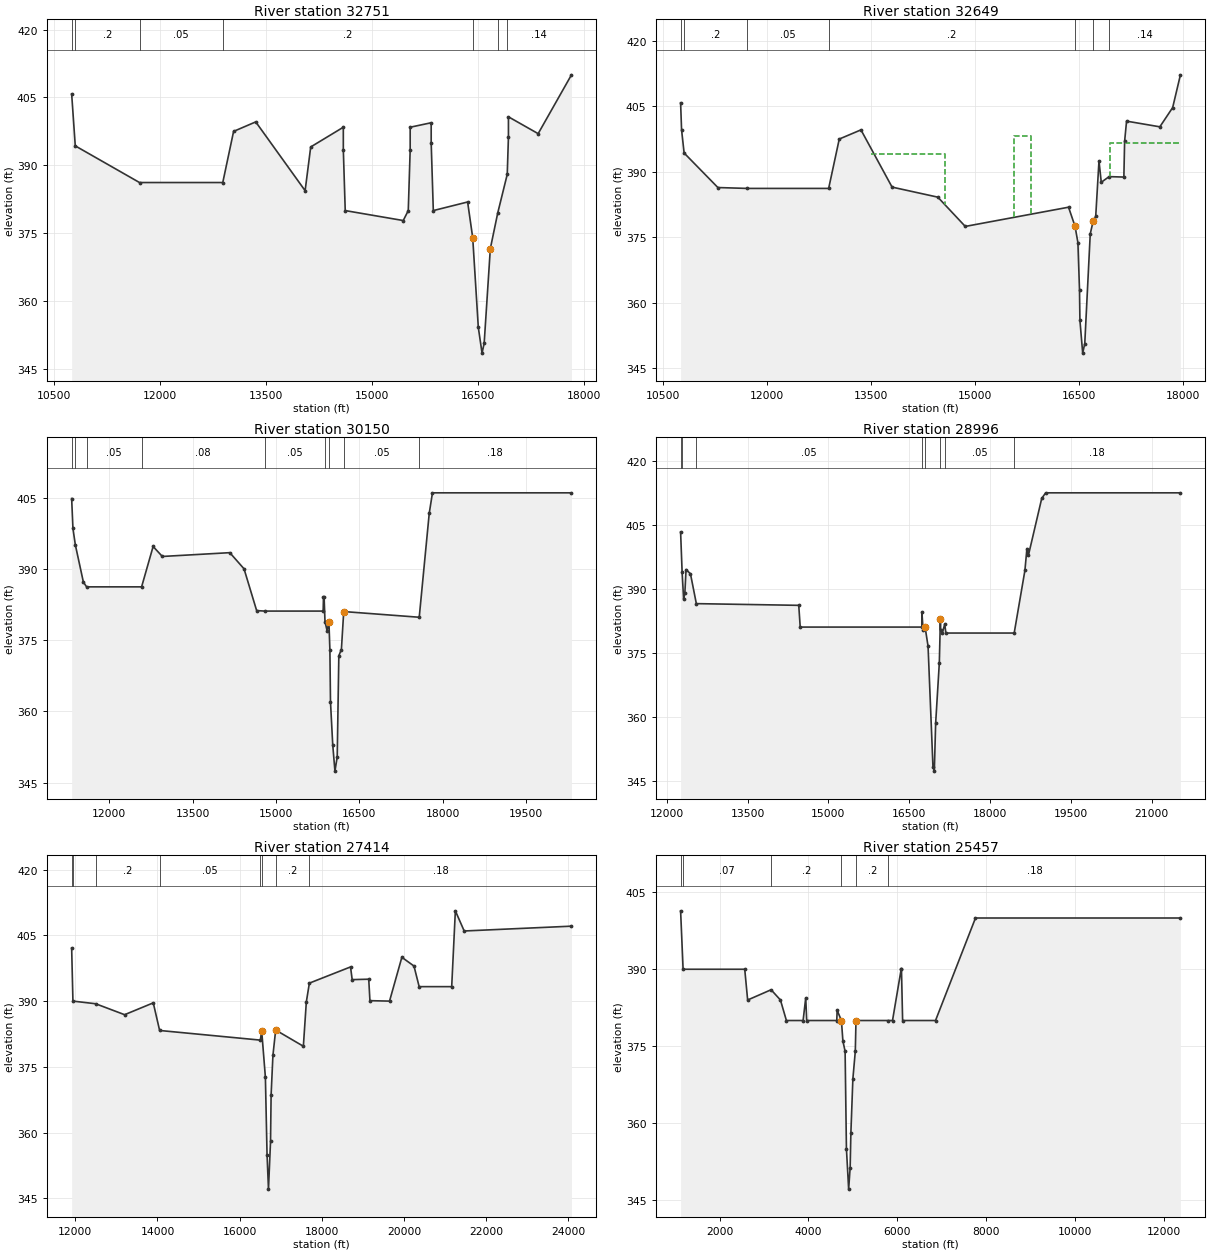
Type RM Length L Ch R = 1 ,32751   ,102,102,102
BEGIN DESCRIPTION:
This cross section corresponds to cross section 32748 of the non-georeferenced CDC model which was the source of this model.
END DESCRIPTION:
XS GIS Cut Line= 3
  2532593.520803 6927043.47112832527625.427064666924079.38912997
2526530.35117084 6923416.9134208
#Sta/Elev= 30
   10755   405.8   10806   394.3   11714   386.2   12891   386.2   13044   397.5
   13357   399.6   14055   384.4   14134  394.06   14595  398.42   14595  393.44
   14622     380   15442   377.8   15513     380   15540  393.44   15540  398.42
   15837  399.41   15837  394.95   15867     380   16352   381.9   16424     374
   16503   354.2   16556   348.5   16586   350.7   16673   371.6   16778   379.5
   16912     388   16929  396.27   16929  400.72   17349     397   17820     410
#Mann= 7 ,-1,0
   10755     .03       0   10806      .2       0   11714     .05       0
   12891      .2       0   16424    .055       0   16778      .2       0
   16912     .14       0
#XS Ineff= 1 ,-1
   13500   14134     394
Permanent Ineff=
       F
Bank Sta=16424,16673
XS Rating Curve= 0 ,0
Exp/Cntr=0.3,0.1

Type RM Length L Ch R = 1 ,32649   ,1449,2499,2298
BEGIN DESCRIPTION:
This cross section corresponds to cross section 32658 of the non-georeferenced CDC model which was the source of this model.
END DESCRIPTION:
XS GIS Cut Line= 3
2532676.001937276926961.907643142526802.99990377 6923473.9999208
2526480.132767356923272.92781638
#Sta/Elev= 30
   10755   405.8   10769   399.6   10806   394.3   11293   386.4   11714   386.2
   12891   386.2   13044   397.5   13357   399.6   13806   386.5   14466   384.2
   14862   377.5   16352   381.9   16446   377.5   16487   373.8   16510     363
   16516     356   16556   348.5   16586   350.7   16665   375.8   16707   378.7
   16744   379.8   16791   392.5   16824   387.6   16937   388.9   17150   388.8
   17161     397   17189   401.6   17669   400.3   17854   404.7   17966   412.2
#Mann= 7 ,-1,0
   10755     .03       0   10806      .2       0   11714     .05       0
   12891      .2       0   16446    .055       0   16707      .2       0
   16937     .14       0
#XS Ineff= 3 ,-1
   13500   14575     394   15560   15817   398.3   16950   17966   396.5
Permanent Ineff=
       F       F       F
Bank Sta=16446,16707
XS Rating Curve= 0 ,0
Exp/Cntr=0.3,0.1

Type RM Length L Ch R = 1 ,30150   ,1200,1154,1130
BEGIN DESCRIPTION:
This cross section corresponds to cross section 30157 of the non-georeferenced CDC model which was the source of this model.
END DESCRIPTION:
XS GIS Cut Line= 4
2533318.201440246926333.938426632532243.99984851 6925299.0002078
2528511.396421346921976.166630392526644.106699696920313.87029838
#Sta/Elev= 30
   11325   404.8   11348   398.5   11392     395   11536   387.2   11594   386.2
   12583   386.2   12790   394.7   12956   392.6   14169   393.4   14425     390
   14652   381.2   14798   381.1   15848   381.1   15854   384.1   15865   384.1
   15881   378.9   15918     377   15952   378.7   15969     373   15980     362
   16020     353   16060   347.4   16101   350.4   16130   371.7   16176     373
   16218     381   17576   379.8   17756   401.7   17814     406   20314     406
#Mann= 9 ,-1,0
   11325     .03       0   11392      .2       0   11594     .05       0
   12583     .08       0   14798     .05       0   15881      .2       0
   15952    .055       0   16218     .05       0   17576     .18       0
#XS Ineff= 2 , 0
           15952   378.7   16218             381
Permanent Ineff=
       F       F
Bank Sta=15952,16218
XS Rating Curve= 0 ,0
Exp/Cntr=0.3,0.1

Type RM Length L Ch R = 1 ,28996   ,1245,1582,1992
BEGIN DESCRIPTION:
This cross section corresponds to cross section 29003 of the non-georeferenced CDC model which was the source of this model.
END DESCRIPTION:
XS GIS Cut Line= 3
 2534234.07690516925440.849333552529110.048767336921011.64362505
2527218.705116846919376.76772892
#Sta/Elev= 30
   12258   403.4   12286     394   12314   387.7   12337   389.1   12359   394.6
   12441   393.6   12550   386.6   14450   386.2   14477   381.1   16733   381.1
   16735   384.6   16756   380.5   16794   381.1   16849   376.6   16940   348.3
   16965   347.3   16990   358.6   17058   372.7   17078     383   17082   380.5
   17115   379.8   17159   381.8   17179   379.7   18447   379.7   18646   394.4
   18683   399.5   18712     398   18958   411.3   19031   412.6   21531   412.6
#Mann= 8 ,-1,0
   12258     .03       0   12286     .16       0   12550     .05       0
   16733      .2       0   16794    .055       0   17078      .2       0
   17159     .05       0   18447     .18       0
#XS Ineff= 2 , 0
           16794   381.1   17078             383
Permanent Ineff=
       F       F
Bank Sta=16794,17078
XS Rating Curve= 0 ,0
Exp/Cntr=0.3,0.1

Type RM Length L Ch R = 1 ,27414   ,1300,1957,1999
BEGIN DESCRIPTION:
This cross section corresponds to cross section 27415 of the non-georeferenced CDC model which was the source of this model.
END DESCRIPTION:
XS GIS Cut Line= 5
2535021.79120892 6924641.00742932532016.999974436921839.00023805
2531385.99992409 6920368.00022732528440.778124246917728.59376071
2526578.997260126916060.12979226
#Sta/Elev= 30
   11911   402.1   11942     390   12494   389.4   13200   386.9   13897   389.6
   14052   383.3   16503   381.1   16536   383.2   16626   372.6   16666     355
   16701   347.1   16751     358   16765   368.6   16809   377.6   16876   383.4
   17550   379.7   17622   389.8   17696   394.1   18698   397.8   18738   394.9
   19141     395   19170   390.1   19647     390   19947     400   20242     398
   20368   393.3   21160   393.3   21249   410.6   21464     406   24075   407.1
#Mann= 8 ,-1,0
   11911     .03       0   11942     .08       0   12494      .2       0
   14052     .05       0   16503      .2       0   16536    .055       0
   16876      .2       0   17696     .18       0
#XS Ineff= 2 , 0
           16536   383.2   16876           383.4
Permanent Ineff=
       F       F
Bank Sta=16536,16876
XS Rating Curve= 0 ,0
Exp/Cntr=0.3,0.1

Type RM Length L Ch R = 1 ,25457   ,0,0,0
BEGIN DESCRIPTION:
This cross section corresponds to cross section 25457 of the non-georeferenced CDC model which was the source of this model.
END DESCRIPTION:
XS GIS Cut Line= 5
2535497.477593516924208.306194962533614.000061246920921.00010554
2533600.635914746920903.282293222531145.627045246916614.24133064
2529903.705690966914444.53366605
#Sta/Elev= 30
  1121.7   401.4  1177.8     390  2565.6     390  2631.2     384  3159.1     386
  3369.4     384  3503.5     380  3879.8     380  3938.8  384.42  3960.6     380
  4637.8     380  4645.8     382  4742.3     380  4775.5     376  4825.3     374
    4855     355    4905   347.1    4939  351.31    4955     358    5000   368.6
  5054.8     374  5070.4     380    5800     380  5892.7     380  6087.4     390
  6094.1     390  6120.1     380    6861     380  7760.7     400 12374.5     400
#Mann= 6 ,-1,0
  1121.7     .03       0  1177.8     .07       0  3159.1      .2       0
  4742.3    .055       0  5070.4      .2       0    5800     .18       0
#XS Ineff= 2 , 0
          4742.3     380  5070.4             380
Permanent Ineff=
       F       F
Bank Sta=4742.3,5070.4
XS Rating Curve= 0 ,0
Exp/Cntr=0.3,0.1
Stream Node=Elm Fork        ,ef6             , 0 , 0 ,Upstream end
Stream Node=Elm Fork        ,ef6             , 0 , 1 ,Downstream end
Stream Node=Elm Fork        ,ef5             , 0 , 0 ,Upstream end
Stream Node=Elm Fork        ,ef5             , 0 , 1 ,Downstream end
Stream Node=Elm Fork        ,ef4             , 0 , 0 ,Upstream end
Stream Node=Elm Fork        ,ef4             , 0 , 1 ,Downstream end
Stream Node=Elm Fork        ,ef3             , 0 , 0 ,Upstream end
Stream Node=Elm Fork        ,ef3             , 0 , 1 ,Downstream end
Stream Node=Elm Fork        ,PGBT split west , 0 , 0 ,Upstream end
Stream Node=Elm Fork        ,PGBT split west , 0 , 1 ,Downstream end
Stream Node=Elm Fork        ,PGBT split east , 0 , 0 ,Upstream end
Stream Node=Elm Fork        ,PGBT split east , 0 , 1 ,Downstream end
Stream Node=Elm Fork        ,ef3 ds          , 0 , 0 ,Upstream end
Stream Node=Elm Fork        ,ef3 ds          , 0 , 1 ,Downstream end
Stream Node=Elm Fork        ,ef2             , 0 , 0 ,Upstream end
Stream Node=Elm Fork        ,ef2             , 0 , 1 ,Downstream end
Stream Node=Elm Fork        ,ef1             , 0 , 0 ,Upstream end
Stream Node=Elm Fork        ,ef1             , 0 , 1 ,Downstream end
Stream Node=Elm Fork L-Spill,efl             , 0 , 0 ,Upstream end
Stream Node=Elm Fork L-Spill,efl             , 0 , 1 ,Downstream end
Stream Node=Elm Fork Split1 ,efs1b           , 0 , 0 ,Upstream end
Stream Node=Elm Fork Split1 ,efs1b           , 0 , 1 ,Downstream end
Stream Node=Elm Fork Split1 ,efs1a           , 0 , 0 ,Upstream end
Stream Node=Elm Fork Split1 ,efs1a           , 0 , 1 ,Downstream end
Stream Node=Elm Fork Split2 ,efs2            , 0 , 0 ,Upstream end
Stream Node=Elm Fork Split2 ,efs2            , 0 , 1 ,Downstream end
Stream Node=Main Stem       ,ms              , 0 , 0 ,Upstream end
Stream Node=Main Stem       ,ms              , 0 , 1 ,Downstream end
Stream Node=West Fork       ,wf              , 0 , 0 ,Upstream end
Stream Node=West Fork       ,wf              , 0 , 1 ,Downstream end
LCMann Table=0

Chan Stop Cuts=-1
Use User Specified Reach Order=0
User Specified Reach Order=Main Stem       ,ms
User Specified Reach Order=West Fork       ,wf1
User Specified Reach Order=West Fork       ,wf2
User Specified Reach Order=West Fork       ,wf
User Specified Reach Order=West Fork       ,wf4
User Specified Reach Order=West Fork Split1,wfs1a
User Specified Reach Order=West Fork Split1,wfs1b
User Specified Reach Order=Clear Fork      ,cf
User Specified Reach Order=Elm Fork Split1 ,efs1a
User Specified Reach Order=Elm Fork Split1 ,efs1b
User Specified Reach Order=Elm Fork Split2 ,efs2
User Specified Reach Order=Elm Fork        ,ef1
User Specified Reach Order=Elm Fork        ,ef2
User Specified Reach Order=Elm Fork        ,ef3
User Specified Reach Order=Elm Fork        ,ef4
User Specified Reach Order=Elm Fork        ,ef5
User Specified Reach Order=Elm Fork        ,ef6
User Specified Reach Order=Elm Fork L-Spill,efl
Composite Channel Slope=5

--- CDC_Consolidated_Model.g03 (geometry) ---

Geom Title=Exist: 10%,4%,2%,1%,0.2%,1%+ AEP [WF/CF]
Program Version=6.60
BEGIN GEOM DESCRIPTION:
Existing: Geometry file for use with 10%, 4%, 2%, 1%, 1%+ AEP peak flows for the WF/CF, and for the FEMA Floodway
END GEOM DESCRIPTION:

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
River Reach=Clear Fork      ,cf
Reach XY= 30
      2292288.59      6921831.41      2292395.97       6922397.8
      2291489.05      6924108.77      2292420.81      6926165.57
      2293153.16      6926162.36       2293269.8      6925436.76
      2293758.24      6925387.77      2294181.12      6926746.94
      2295837.81      6927186.34       2295473.1      6928409.34
      2296111.76      6928883.73        2296737.      6931056.08
      2297422.82      6931404.05      2297950.73      6932634.33
      2299232.22      6932867.28      2297680.47      6937064.23
      2298189.42      6937701.98       2301232.1      6938651.28
      2303699.09      6941339.79      2305947.37      6941667.25
      2308069.54      6941107.18      2310975.73      6945211.82
      2315573.97      6947689.72      2316990.27      6947731.35
      2318888.83      6948531.06      2319676.25       6949929.2
      2319101.67      6952610.66      2321572.42      6955397.54
      2323769.41       6959883.4      2325609.76      6961458.94

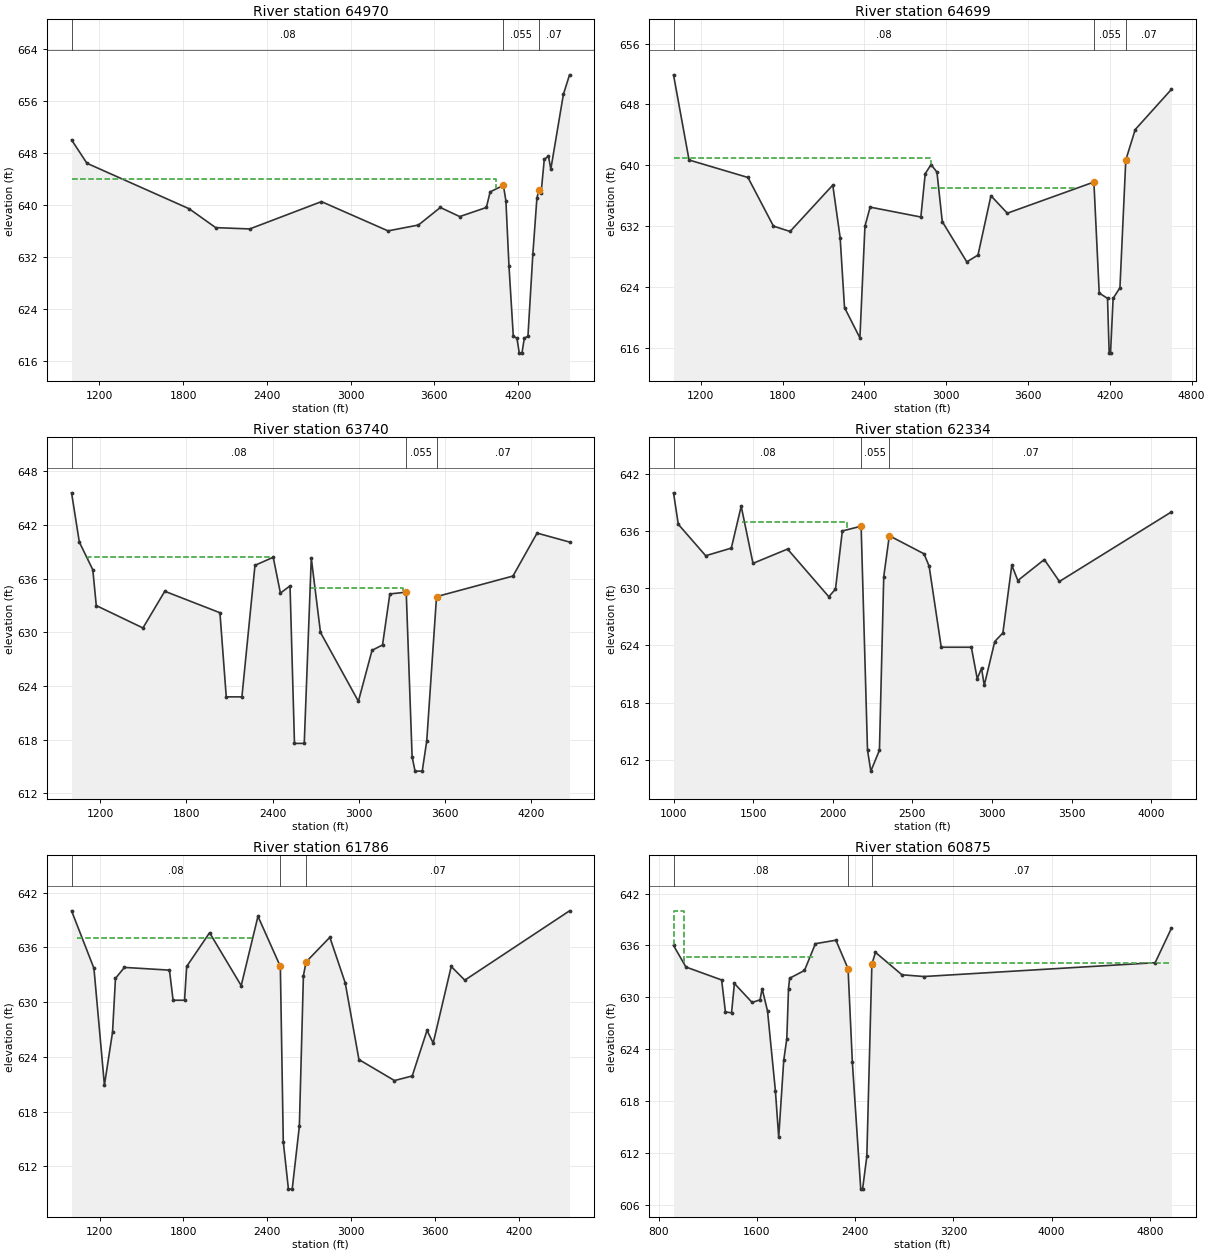
Type RM Length L Ch R = 1 ,64970   ,272,272,171
BEGIN DESCRIPTION:
This cross section corresponds to cross section 65616 of the non-georeferenced CDC model which was the source of this model.
Approx. 600 feet downstream from centerline of Benbrook Dam.  Main channel within Benbrook Lake outlet works basin.  Benbrook Dam at sta 66206, river mile 12.54.
Channel data from 1975 USACE field survey.
END DESCRIPTION:
XS GIS Cut Line= 5
2289302.451151216923055.48400696   2290010.37999   6922808.27192
     2290779.761   6922562.03816   2291609.16911   6922297.63712
   2292697.71615   6921956.35204
#Sta/Elev= 30
    1000     650    1110   646.4    1843   639.4    2033   636.5    2277   636.3
    2791   640.5    3268     636    3486   636.9    3643   639.6    3782   638.2
    3973   639.6    4000     642    4095     643    4113   640.6    4135   630.6
    4166   619.8 4191.91   619.5 4208.91   617.2 4227.91   617.2 4244.91   619.5
    4271   619.8    4306   632.4    4335     641    4349   642.3    4365   641.8
    4388     647    4418   647.5    4435   645.5    4525     657    4569     660
#Mann= 3 ,0,0
    1000     .08       0    4095    .055       0    4349     .07       0
#XS Ineff= 2 , 0
       0    4044     644               0
Permanent Ineff=
       F       F
Bank Sta=4095,4349
XS Rating Curve= 0 ,0
Exp/Cntr=0.3,0.1

Type RM Length L Ch R = 1 ,64699   ,959,959,1278
BEGIN DESCRIPTION:
This cross section corresponds to cross section 65344 of the non-georeferenced CDC model which was the source of this model.
Main channel is Benbrook Lake outlet works discharge
channel.  Old Clear Fork channel in LOB.  Pecan Valley Golf Course in LOB and ROB.
Channel data from 1975 USACE field survey.
END DESCRIPTION:
XS GIS Cut Line= 3
   2289405.28901   6923376.84001   2292198.44615   6922304.71912
   2292855.65612    6922369.6209
#Sta/Elev= 30
    1000   651.9    1114   640.7    1546   638.4    1733     632    1855   631.3
    2168   637.4    2222   630.5    2254   621.3    2367   617.3    2404     632
    2442   634.5    2814   633.2    2846   638.9    2889   640.1    2932   639.1
    2971   632.6    3151   627.3    3233   628.2    3328     636    3448   633.7
    4083   637.8    4122   623.2    4183   622.5    4195   615.3    4205   615.3
    4224   622.5    4274   623.9    4317   640.7    4386   644.7    4652     650
#Mann= 3 ,0,0
    1000     .08       0    4083    .055       0    4317     .07       0
#XS Ineff= 2 ,-1
    1000    2889     641    2889    3939     637
Permanent Ineff=
       F       F
Bank Sta=4083,4317
XS Rating Curve= 0 ,0
Exp/Cntr=0.3,0.1

Type RM Length L Ch R = 1 ,63740   ,1406,1406,1657
BEGIN DESCRIPTION:
This cross section corresponds to cross section 64380 of the non-georeferenced CDC model which was the source of this model.
Main channel is Benbrook Lake outlet works discharge
channel.  Old Clear Fork channel in LOB.  Pecan Valley Golf Course in LOB and ROB.
Channel data from 1975 USACE field survey.
END DESCRIPTION:
XS GIS Cut Line= 4
   2289805.88893   6924138.74006   2291888.51206   6923134.21812
   2292151.08995   6923248.88784   2292843.05903   6922725.25897
#Sta/Elev= 30
    1000   645.6    1054   640.1    1148     637    1172     633    1497   630.5
    1649   634.6    2033   632.2    2077   622.8    2186   622.8    2277   637.5
    2404   638.4    2454   634.4    2521   635.2    2552   617.6    2620   617.6
    2669   638.3    2733     630    2997   622.3    3092     628    3165   628.6
    3216   634.3    3330   634.5    3371   616.1  3391.5   614.5  3441.5   614.5
    3473   617.9    3541     634    4073   636.3    4241   641.1    4467   640.1
#Mann= 3 ,0,0
    1000     .08       0    3330    .055       0    3541     .07       0
#XS Ineff= 3 ,-1
  1112.4 2379.84  638.44 2405.08    2670   636.2    2670  3304.3     635
Permanent Ineff=
       F       F       F
Bank Sta=3330,3541
XS Rating Curve= 0 ,0
Exp/Cntr=0.3,0.1

Type RM Length L Ch R = 1 ,62334   ,548,548,394
BEGIN DESCRIPTION:
This cross section corresponds to cross section 62953 of the non-georeferenced CDC model which was the source of this model.
Approx. 300 feet downstream of Clear Fork/old Clear Fork
confluence.  Pecan Valley Golf Course in LOB and ROB.
Channel data from 1975 USACE field survey.
END DESCRIPTION:
XS GIS Cut Line= 5
   2290353.38291   6924913.24311   2291747.77809   6924311.60815
    2292745.2131   6923474.95399      2292737.38     6923479.203
     2292708.734     6923173.213
#Sta/Elev= 30
    1000     640    1030   636.7    1202   633.4    1363   634.2    1425   638.6
    1499   632.6    1716   634.1    1975   629.1    2017   629.9    2060     636
    2178   636.5    2218     613    2239   610.8    2293     613    2320   631.2
    2355   635.5    2573   633.6    2605   632.3    2681   623.8    2870   623.8
    2907   620.5    2934   621.6    2951   619.8    3017   624.4    3068   625.3
    3124   632.4    3162   630.8    3328     633    3423   630.7  4126.6     638
#Mann= 3 ,0,0
    1000     .08       0    2178    .055       0    2355     .07       0
#XS Ineff= 4 ,-1
                         1013.29    1428     638    1428  2089.7 636.911
    2431    4500  634.23
Permanent Ineff=
       F       F       F       F
Bank Sta=2178,2355
XS Rating Curve= 0 ,0
Exp/Cntr=0.3,0.1

Type RM Length L Ch R = 1 ,61786   ,910,910,983
BEGIN DESCRIPTION:
This cross section corresponds to cross section 62405 of the non-georeferenced CDC model which was the source of this model.
Benbrook Lake spillway channel in LOB, Pecan Valley
Golf Course in LOB and ROB.
Channel data from 1975 USACE field survey.
END DESCRIPTION:
XS GIS Cut Line= 3
   2290801.86397   6925909.86907   2292800.27992   6923879.75895
     2293230.432     6923313.582
#Sta/Elev= 30
    1000     640    1160   633.7    1235   620.9    1293   626.7    1314   632.6
    1378   633.8    1700   633.5    1726   630.2    1808   630.2    1823   633.9
    1987   637.6    2213   631.8    2333   639.4    2493   633.9    2514   614.7
 2550.81   609.5 2577.81   609.5    2629   616.4    2658   632.9    2677   634.4
    2847   637.1    2957   632.1    3055   623.7    3309   621.4    3436   621.9
    3542   626.9    3586   625.5    3715   633.9    3812   632.4    4561     640
#Mann= 3 ,0,0
    1000     .08       0    2493    .055       0    2677     .07       0
#XS Ineff= 3 ,-1
                         1036.54 2292.36     637    2847    4500   634.1
Permanent Ineff=
       F       F       F
Bank Sta=2493,2677
XS Rating Curve= 0 ,0
Exp/Cntr=0.3,0.1

Type RM Length L Ch R = 1 ,60875   ,1006,1006,481
BEGIN DESCRIPTION:
This cross section corresponds to cross section 61472 of the non-georeferenced CDC model which was the source of this model.
Approx. 650 feet upstream of Clear Fork/Benbrook Lake
spillway channel confluence.  Benbrook Lake spillway channel in LOB.  Pecan Valley Golf Course in LOB and ROB.
Channel data from 1975 USACE field survey.
END DESCRIPTION:
XS GIS Cut Line= 5
 2291138.8580606 6926573.7674949   2291196.79297   6926518.59915
   2291893.24794   6925855.40198   2292731.49659   6925311.56547
     2293229.455     6923357.887
#Sta/Elev= 30
     920     636    1021   633.5    1312     632    1343   628.3    1393   628.2
    1416   631.6    1560   629.4    1625   629.7    1642     631    1686   628.4
    1750   619.2    1777   613.8    1818   622.7    1843   625.2    1857     631
    1866   632.2    1987   633.1    2076   636.2    2243   636.6    2342   633.3
    2377   622.5 2445.35   607.8 2460.35   607.8    2495   611.6    2536   633.8
    2565   635.2    2781   632.6    2961   632.4    4844     634    4977     638
#Mann= 3 ,0,0
     920     .08       0    2342    .055       0    2536     .07       0
#XS Ineff= 3 ,-1
     920 1004.43     640    2667    4977     634 1004.43    2076   634.6
Permanent Ineff=
       F       F       F
Bank Sta=2342,2536
XS Rating Curve= 0 ,0
Exp/Cntr=0.3,0.1

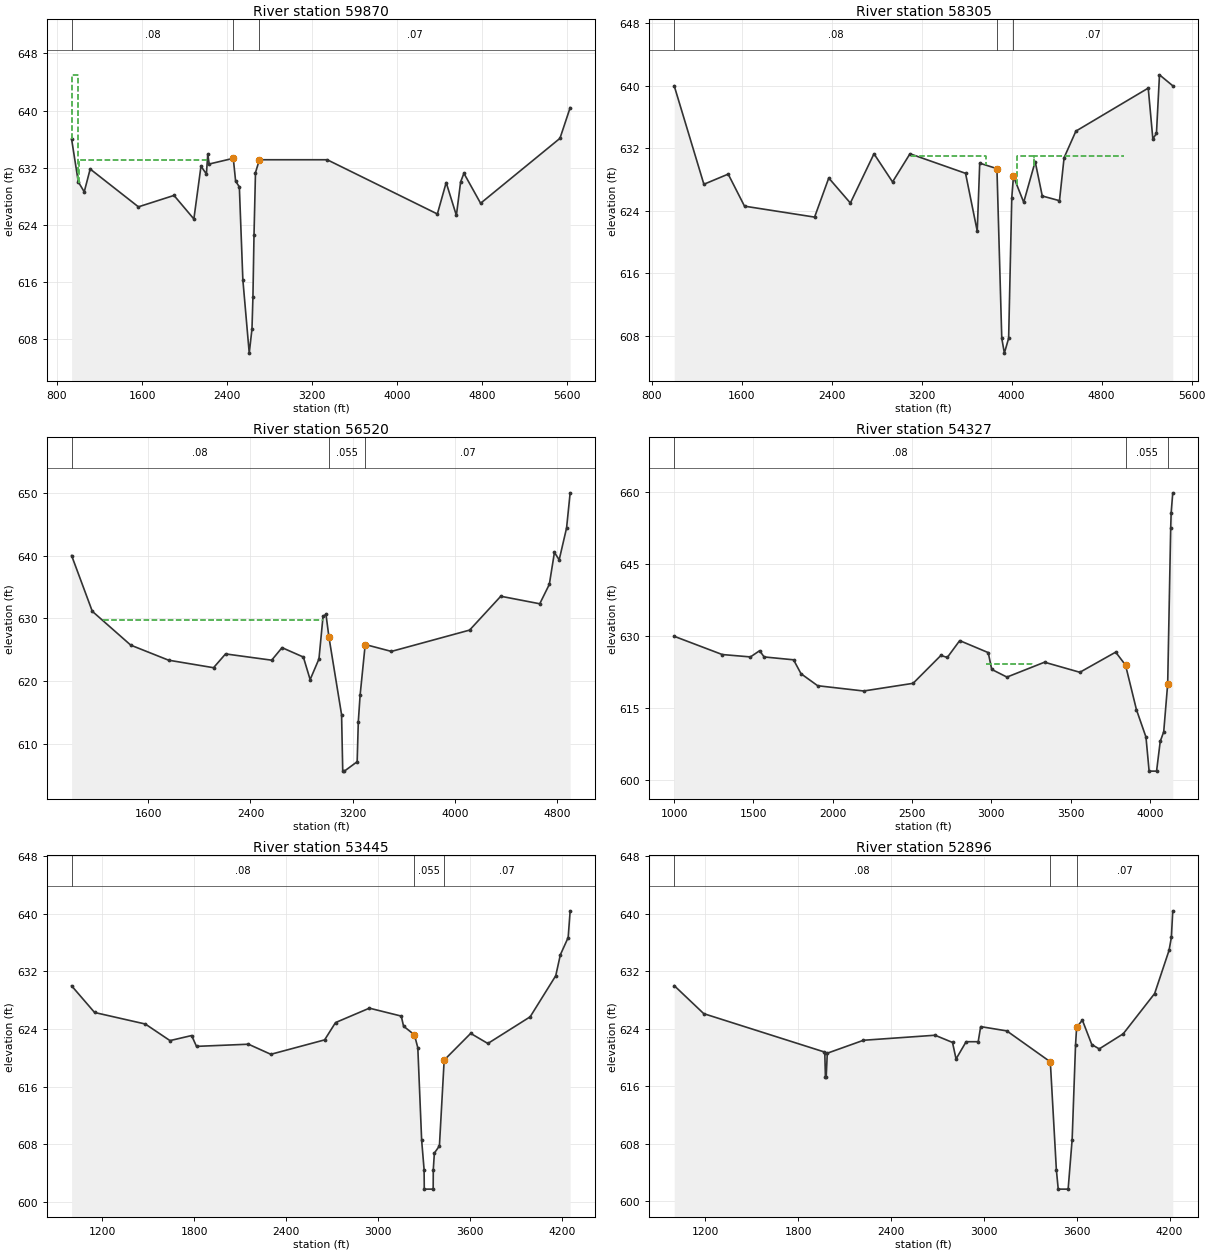
Type RM Length L Ch R = 1 ,59870   ,1565,1565,5283
BEGIN DESCRIPTION:
This cross section corresponds to cross section 60451 of the non-georeferenced CDC model which was the source of this model.
Approx. 400 feet downstream of Clear Fork/Benbrook Lake
spillway channel confluence.
Channel data from 1975 USACE field survey.
END DESCRIPTION:
XS GIS Cut Line= 5
 2291850.84332586927377.71680122   2291904.80796   6927345.20806
   2292821.71098   6926792.85811   2292731.61306   6925311.49001
   2293246.02903    6923300.9189
#Sta/Elev= 30
     937     636    1000     630    1056   628.6    1112   631.8    1566   626.5
    1901   628.1    2088   624.8    2155   632.2    2206   631.1    2219   633.9
    2232   632.5    2459   633.3    2481   630.1    2516   629.3    2549   616.3
 2609.17     606    2635   609.4    2644   613.9    2654   622.5    2668   631.3
    2705   633.1    3343   633.1    4380   625.5    4463   629.9    4559   625.3
    4599     630    4630   631.2    4787     627    5534   636.1    5630   640.4
#Mann= 3 ,0,0
     937     .08       0    2459    .055       0    2705     .07       0
#XS Ineff= 3 ,-1
     937    1000     645 1005.54 2218.16  633.02    2877    5247   632.5
Permanent Ineff=
       F       F       F
Bank Sta=2459,2705
XS Rating Curve= 0 ,0
Exp/Cntr=0.3,0.1

Type RM Length L Ch R = 1 ,58305   ,1785,1785,4102
BEGIN DESCRIPTION:
This cross section corresponds to cross section 58850 of the non-georeferenced CDC model which was the source of this model.
Channel data from 1975 USACE field survey.
END DESCRIPTION:
XS GIS Cut Line= 3
   2292254.84499   6927827.90985   2293628.29008   6926249.91694
   2293665.95995   6923910.19098
#Sta/Elev= 30
    1000     640    1264   627.4    1480   628.7    1625   624.6    2248   623.2
    2374   628.2    2566     625    2776   631.3    2941   627.7    3096   631.3
    3590   628.8    3694   621.4    3716   630.1    3869   629.4    3912   607.7
 3935.14   605.8    3973   607.7    4001   625.7    4016   628.4    4107   625.1
    4209   630.3    4272   625.9    4425   625.3    4466   630.8    4571   634.2
    5214   639.7    5255   633.2    5287   633.9    5314   641.4    5432     640
#Mann= 3 ,0,0
    1000     .08       0    3869    .055       0    4016     .07       0
#XS Ineff= 4 ,-1
  1149.5  3104.1  630.99  3104.1 3768.55  630.99  4045.4    4199  630.99
    4199    5000  630.99
Permanent Ineff=
       F       F       F       F
Bank Sta=3869,4016
XS Rating Curve= 0 ,0
Exp/Cntr=0.3,0.1

Type RM Length L Ch R = 1 ,56520   ,2193,2193,4113
BEGIN DESCRIPTION:
This cross section corresponds to cross section 57021 of the non-georeferenced CDC model which was the source of this model.
USGS gaging station 08047000 - Benbrook Gage - located
on left bank.  Gage datum elev. 604.22 MSL.
Channel data from 1975 USACE field survey.
END DESCRIPTION:
XS GIS Cut Line= 4
   2292550.51402    6928102.5179   2294005.40415   6926968.38795
   2294400.56511   6926451.90112   2295520.89095   6925600.00092
#Sta/Elev= 30
    1000     640    1162   631.1    1463   625.7    1759   623.3    2111   622.1
    2205   624.3    2566   623.3    2647   625.3    2814   623.8    2867   620.2
    2936   623.5    2968   630.3    2991   630.6    3014     627    3113   614.6
    3122   605.7    3135   605.6    3235   607.1    3244   613.5    3258   617.7
    3298   625.8    3503   624.7    4115   628.1    4359   633.5    4664   632.3
    4739   635.4    4779   640.5    4816   639.3    4874   644.4    4902     650
#Mann= 3 ,0,0
    1000     .08       0    3014    .055       0    3298     .07       0
#XS Ineff= 2 ,-1
 1243.63 2966.78  629.69 3303.43 3662.24  625.49
Permanent Ineff=
       F       F
Bank Sta=3014,3298
XS Rating Curve= 0 ,0
Exp/Cntr=0.3,0.1

Type RM Length L Ch R = 1 ,54327   ,882,882,789
BEGIN DESCRIPTION:
This cross section corresponds to cross section 54806 of the non-georeferenced CDC model which was the source of this model.
Channel data from 1975 USACE field survey.
END DESCRIPTION:
XS GIS Cut Line= 3
   2292993.46195   6928436.13009   2295483.60001   6927485.79013
   2295952.42716   6927587.07601
#Sta/Elev= 30
    1000     630    1303   626.2    1481   625.7    1539     627    1567   625.7
    1753   625.1    1800   622.2    1905   619.7    2195   618.6    2507   620.2
    2682     626    2723   625.6    2801   629.1    2981   626.6    3003   623.1
    3099   621.5    3336   624.6    3559   622.5    3785   626.7    3847     624
    3916   614.7    3976     609  3995.9   601.9  4042.9   601.9    4066   608.1
    4088   610.1    4113   620.1    4132   652.6    4135   655.8    4145   659.9
#Mann= 3 ,0,0
    1000     .08       0    3847    .055       0    4113     .07       0
#XS Ineff= 3 ,-1
 1093.02 2802.33  627.56 2965.12 3255.81  624.21    4113    4145   620.1
Permanent Ineff=
       F       F       F
Bank Sta=3847,4113
XS Rating Curve= 0 ,0
Exp/Cntr=0.3,0.1

Type RM Length L Ch R = 1 ,53445   ,549,549,218
BEGIN DESCRIPTION:
This cross section corresponds to cross section 53901 of the non-georeferenced CDC model which was the source of this model.
Channel data from 1975 USACE field survey.
END DESCRIPTION:
XS GIS Cut Line= 3
   2293225.28596   6929086.76691   2295284.68112   6928387.10099
   2296332.22004   6928130.91909
#Sta/Elev= 30
    1000     630    1150   626.3    1481   624.7    1642   622.4    1783   623.1
    1815   621.6    2154   621.9    2300   620.5    2651   622.5    2722   624.9
    2943   626.9    3151   625.8    3166   624.4    3237   623.2    3259   621.4
    3284   608.6    3300   604.5 3301.22   601.8 3359.22   601.8    3360   604.5
    3367   606.8    3400   607.8    3431   619.7    3604   623.4    3716     622
    3992   625.7    4159   631.4    4189   634.3    4240   636.7    4253   640.4
#Mann= 3 ,0,0
    1000     .08       0    3237    .055       0    3431     .07       0
#XS Ineff= 1 ,-1
 1135.66 2934.11  626.63
Permanent Ineff=
       F
Bank Sta=3237,3431
XS Rating Curve= 0 ,0
Exp/Cntr=0.3,0.1

Type RM Length L Ch R = 1 ,52896   ,1104,1104,2458
BEGIN DESCRIPTION:
This cross section corresponds to cross section 53352 of the non-georeferenced CDC model which was the source of this model.
Channel data from 1975 USACE field survey.
END DESCRIPTION:
XS GIS Cut Line= 4
   2293577.18191   6929578.50805   2295600.82714   6928956.42597
     2295998.348   6928545.33591   2296332.11374   6928131.05098
#Sta/Elev= 30
    1000     630    1191   626.1    1966   620.8    1973   620.6    1977   617.3
    1982   617.3    1989   620.6    2223   622.4    2685   623.1    2798   622.1
    2821   619.8    2886   622.2    2964   622.2    2980   624.3    3149   623.7
    3430   619.4    3469   604.4 3481.07   601.7 3545.07   601.7    3571   608.6
    3593   621.8    3600   624.2    3637   625.2    3698   621.8    3746   621.2
    3901   623.3    4104   628.9    4197   634.9    4212   636.7    4221   640.4
#Mann= 3 ,0,0
    1000     .08       0    3430    .055       0    3600     .07       0
#XS Ineff= 2 ,-1
 1406.98 2988.37  624.17 3620.16 3953.49621.5899
Permanent Ineff=
       F       F
Bank Sta=3430,3600
XS Rating Curve= 0 ,0
Exp/Cntr=0.3,0.1