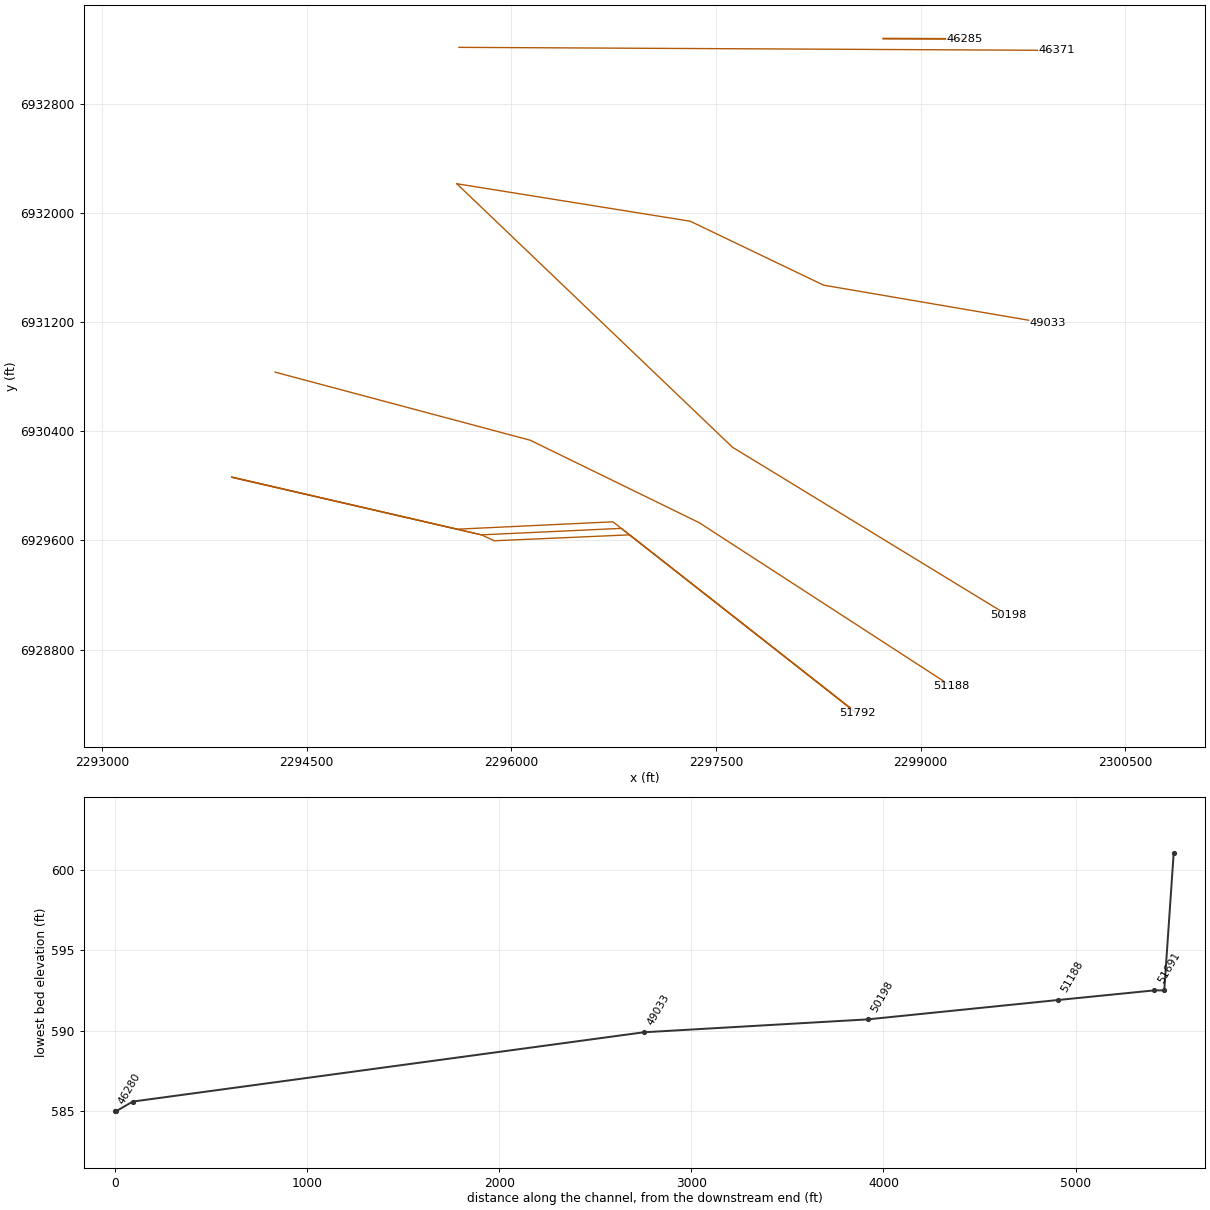
HEC-RAS study CDC_Consolidated_Model.prj: Upper Trinity CDC Consolidated Model

--- CDC_Consolidated_Model.g03 (geometry) --- (continued)

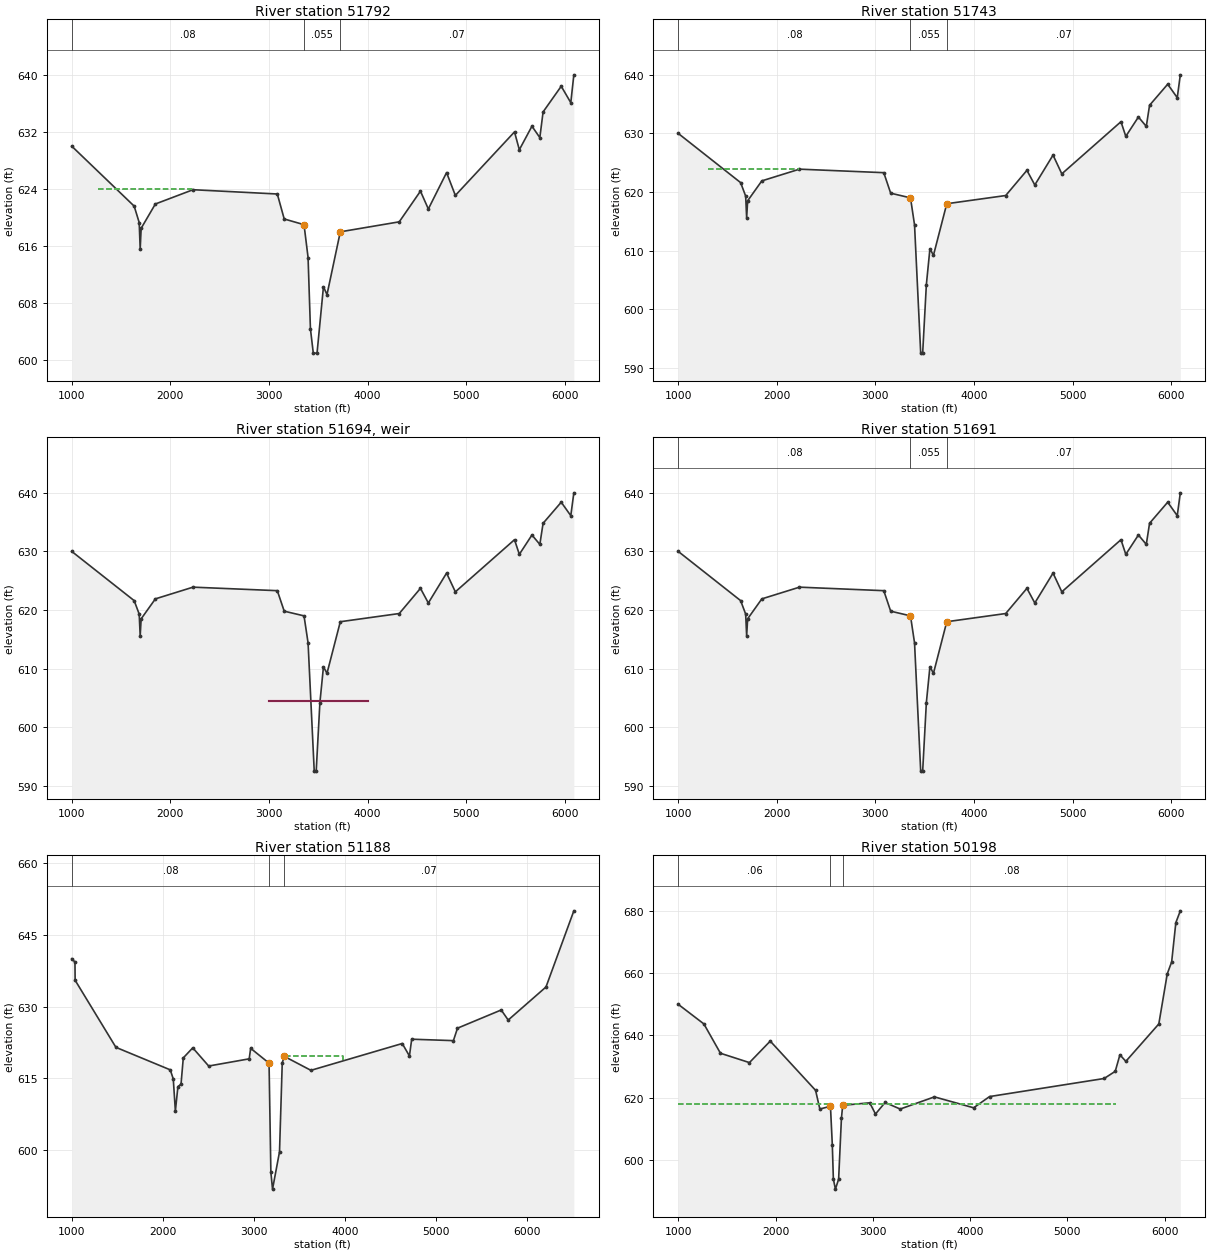
Type RM Length L Ch R = 1 ,51792   ,49,49,49
BEGIN DESCRIPTION:
This cross section corresponds to cross section 52242 of the non-georeferenced CDC model which was the source of this model.
50 feet upstream of Rawls Dam.
Channel data from 1975 USACE field survey.
END DESCRIPTION:
XS GIS Cut Line= 5
      2293950.84      6930062.52      2295780.52      6929641.18
     2295873.856     6929597.844      2296865.83      6929641.16
    2298532.2459    6928332.6397
#Sta/Elev= 30
    1000     630    1633   621.6    1684   619.3    1694   615.6    1704   618.5
    1848   621.9    2230   623.9    3085   623.3    3155   619.8    3356     619
    3397   614.4    3421   604.4    3450     601    3488     601    3553   610.3
    3589   609.2    3724     618    4322   619.4    4537   623.7    4617   621.2
    4802   626.3    4891   623.1    5491     632    5540   629.5    5668   632.8
    5748   631.2    5781   634.8    5965   638.4    6062   636.1    6093     640
#Mann= 3 ,0,0
    1000     .08       0    3356    .055       0    3724     .07       0
#XS Ineff= 1 ,-1
 1265.78 2215.95 623.967
Permanent Ineff=
       F
Bank Sta=3356,3724
XS Rating Curve= 0 ,0
Exp/Cntr=0.3,0.1

Type RM Length L Ch R = 1 ,51743   ,52,52,52
BEGIN DESCRIPTION:
This cross section corresponds to cross section 52192 of the non-georeferenced CDC model which was the source of this model.
One-foot upstream of Rawls Dam.
Channel data from 1975 USACE field survey.
END DESCRIPTION:
XS GIS Cut Line= 4
     2293951.113     6930064.424      2295780.54     6929641.247
    2296805.5596    6929688.6595     2298532.276     6928332.653
#Sta/Elev= 30
    1000     630    1633   621.6    1684   619.3    1694   615.6    1704   618.5
    1848   621.9    2230   623.9    3085   623.3    3155   619.8    3356     619
    3397   614.4  3459.5   592.5  3479.5   592.5    3517   604.2    3553   610.3
    3589   609.2    3724     618    4322   619.4    4537   623.7    4617   621.2
    4802   626.3    4891   623.1    5491     632    5540   629.5    5668   632.8
    5748   631.2    5781   634.8    5965   638.4    6062   636.1    6093     640
#Mann= 3 ,0,0
    1000     .08       0    3356    .055       0    3724     .07       0
#XS Ineff= 1 ,-1
 1305.65 2222.59  623.95
Permanent Ineff=
       F
Bank Sta=3356,3724
XS Rating Curve= 0 ,0
Exp/Cntr=0.3,0.1

Type RM Length L Ch R = 5 ,51694   ,,,
BEGIN DESCRIPTION:
Rawls Dam
crest elevation 604.4
END DESCRIPTION:
Node Name=Rawls Dam
IW Pilot Flow=0
#Inline Weir SE= 2
    3000   604.4    4000   604.4
IW Dist,WD,Coef,Skew,MaxSub,Min_El,Is_Ogee,SpillHt,DesHd
1,5,3,0,0.95,, 0 ,,,0,0,
Inline Weir Flap Gates= 0
IW Outlet Rating Curve= 0 ,False,,

Type RM Length L Ch R = 1 ,51691   ,503,503,216
BEGIN DESCRIPTION:
This cross section corresponds to cross section 52140 of the non-georeferenced CDC model which was the source of this model.
52 feet downstream of Rawls Dam.
Channel data from 1975 USACE field survey.
END DESCRIPTION:
XS GIS Cut Line= 5
    2293951.1174    6930064.4332    2295602.0909    6929682.6609
     2296744.081     6929736.733    2296805.5702    6929688.6655
      2298533.18      6928333.95
#Sta/Elev= 30
    1000     630    1633   621.6    1684   619.3    1694   615.6    1704   618.5
    1848   621.9    2230   623.9    3085   623.3    3155   619.8    3356     619
    3397   614.4  3459.5   592.5  3479.5   592.5    3517   604.2    3553   610.3
    3589   609.2    3724     618    4322   619.4    4537   623.7    4617   621.2
    4802   626.3    4891   623.1    5491     632    5540   629.5    5668   632.8
    5748   631.2    5781   634.8    5965   638.4    6062   636.1    6093     640
#Mann= 3 ,0,0
    1000     .08       0    3356    .055       0    3724     .07       0
#XS Ineff= 1 ,-1
 1332.23 2229.24  623.69
Permanent Ineff=
       F
Bank Sta=3356,3724
XS Rating Curve= 0 ,0
Exp/Cntr=0.3,0.1

Type RM Length L Ch R = 1 ,51188   ,990,990,546
BEGIN DESCRIPTION:
This cross section corresponds to cross section 51599 of the non-georeferenced CDC model which was the source of this model.
Channel data from 1975 USACE field survey.
END DESCRIPTION:
XS GIS Cut Line= 4
   2294267.97515    6930833.8169   2296137.94188   6930334.70799
   2297376.60509   6929730.37291   2299223.99706   6928532.58495
#Sta/Elev= 30
    1000     640    1035   639.3    1037   635.5    1485   621.5    2082   616.8
    2115   614.9    2138   608.2    2166   613.3    2200   613.8    2225   619.3
    2329   621.4    2504   617.6    2949   619.1    2965   621.3    3167   618.2
    3187   595.4 3205.33   591.9    3282   599.7    3312   618.3    3336   619.6
    3627   616.7    4630   622.3    4709   619.7    4734   623.2    5192   622.9
    5237   625.5    5717   629.3    5794   627.2    6209   634.1    6515     650
#Mann= 3 ,0,0
    1000     .08       0    3167    .055       0    3336     .07       0
#XS Ineff= 2 ,-1
 1471.76 2973.42     621  3358.8 3983.39  619.65
Permanent Ineff=
       F       F
Bank Sta=3167,3336
XS Rating Curve= 0 ,0
Exp/Cntr=0.3,0.1

Type RM Length L Ch R = 1 ,50198   ,1165,1165,1476
BEGIN DESCRIPTION:
This cross section corresponds to cross section 50598 of the non-georeferenced CDC model which was the source of this model.
Channel data from 1975 USACE field survey.
END DESCRIPTION:
XS GIS Cut Line= 3
   2295599.88587   6932214.68192   2297620.19909   6930283.47909
   2299641.16585   6929050.26502
#Sta/Elev= 30
    1000     650    1264   643.7    1434   634.3    1732   631.3    1946   638.2
    2412   622.4    2456   616.4    2565   617.3    2584     605    2595   593.9
 2616.04   590.7    2649   593.9    2678   613.5    2691   617.6    2969   618.4
    3028   614.8    3127   618.5    3282   616.4    3634   620.3    4037   616.8
    4201   620.4    5379   626.2    5493   628.5    5541   633.8    5602   631.7
    5941   643.7    6028   659.8    6073   663.6    6116   676.2    6162     680
#Mann= 3 ,0,0
    1000     .06       0    2565    .055       0    2691     .08       0
#XS Ineff= 3 ,-1
    1000    2565     618    2691    2733     618    2733    5500     618
Permanent Ineff=
       F       F       F
Bank Sta=2565,2691
XS Rating Curve= 0 ,0
Exp/Cntr=0.3,0.1

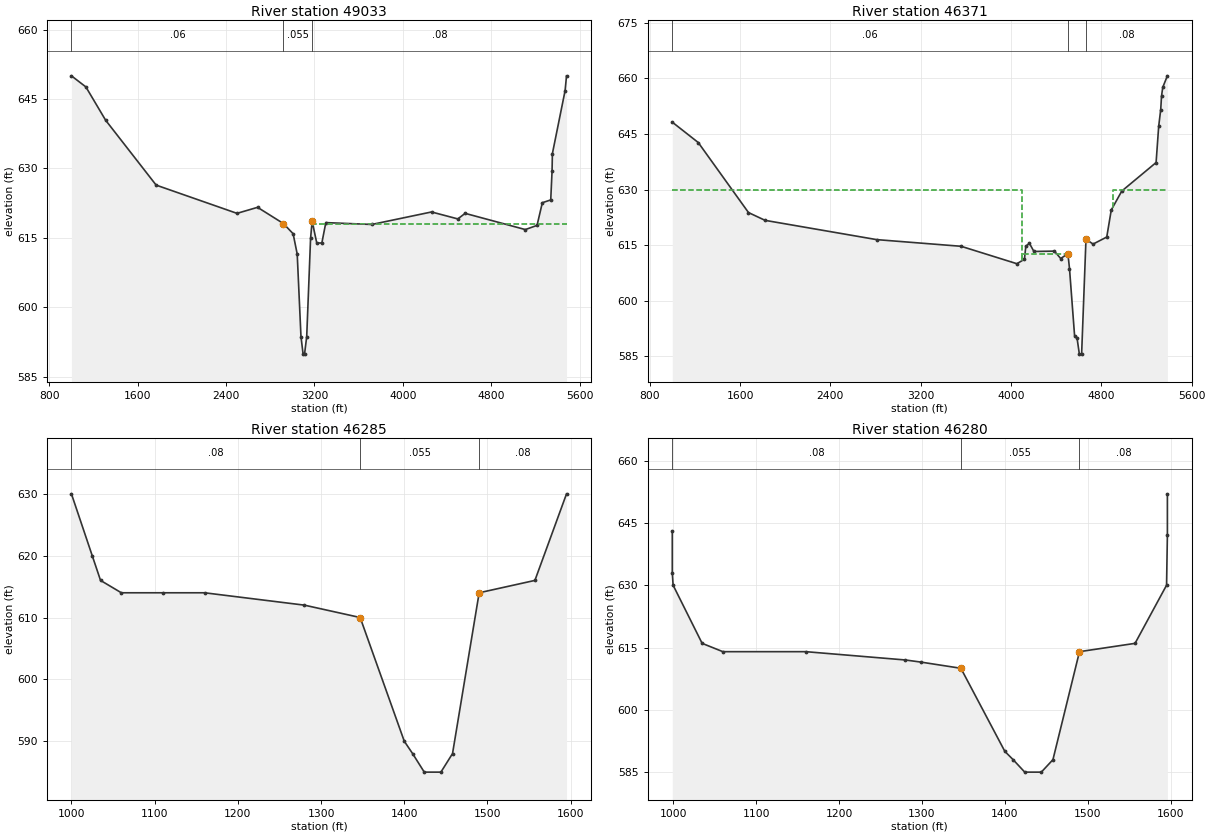
Type RM Length L Ch R = 1 ,49033   ,2661,2661,2957
BEGIN DESCRIPTION:
This cross section corresponds to cross section 49420 of the non-georeferenced CDC model which was the source of this model.
Channel data from 1975 USACE field survey.
END DESCRIPTION:
XS GIS Cut Line= 4
   2295600.04958   6932214.65567   2297310.18986   6931940.04893
   2298288.57013   6931471.27789     2299929.828   6931190.55404
#Sta/Elev= 30
    1000     650    1131   647.6    1310   640.4    1767   626.4    2499   620.3
    2685   621.6    2919   618.1    3007   615.9    3044   611.5    3078   593.7
  3097.3   589.9  3110.3   589.9    3130   593.7    3165   614.9    3179   618.6
    3221   613.9    3267   613.9    3303   618.3    3719   617.9    4260   620.6
    4498   619.1    4564   620.3    5109   616.8    5215   617.7    5263   622.6
    5339   623.2    5351   629.4    5354   633.2    5469   646.8    5482     650
#Mann= 3 ,0,0
    1000     .06       0    2919    .055       0    3179     .08       0
#XS Ineff= 2 , 0
       0                    3188       0     618
Permanent Ineff=
       F       F
Bank Sta=2919,3179
XS Rating Curve= 0 ,0
Exp/Cntr=0.3,0.1

Type RM Length L Ch R = 1 ,46371   ,87,87,867
BEGIN DESCRIPTION:
This cross section corresponds to cross section 46736 of the non-georeferenced CDC model which was the source of this model.
Cross-section modified by USACE February 2007 - blocked obstruction in LOB changed to ineffective flow.
Effective flow limit set at sta 4100 in LOB, at sta 4900 in ROB.
126 feet upstream of I.H. 20.
Channel data from 1975 USACE field survey.
END DESCRIPTION:
XS GIS Cut Line= 2
   2295615.17291   6933214.44107    2300000.0001   6933192.25214
#Sta/Elev= 30
    1000   648.2    1230   642.7    1675   623.8    1822   621.7    2810   616.5
    3558   614.7    4052     610    4119   611.2    4131   614.7    4163   615.5
    4203   613.3    4384   613.4    4440   611.4    4504   612.7    4518   608.7
    4563   590.6    4585   589.9 4605.39   585.6 4625.39   585.6    4664   616.6
    4727   615.3    4848   617.2    4888   624.5    4981   629.6    5285   637.3
    5308   647.1    5326   651.6    5333   655.2    5344   657.6    5385   660.7
#Mann= 3 ,0,0
    1000     .06       0    4504    .055       0    4664     .08       0
#XS Ineff= 4 ,-1
    1000    4100     630    4900    5385     630    4664    4900   616.6
    4100    4504   612.7
Permanent Ineff=
       F       F       F       F
Bank Sta=4504,4664
XS Rating Curve= 0 ,0
Exp/Cntr=0.3,0.1

Type RM Length L Ch R = 1 ,46285   ,4,4,4
BEGIN DESCRIPTION:
This cross section corresponds to cross section 46611 of the non-georeferenced CDC model which was the source of this model.
Duplication of previous bridge cross-section without bridge piers.
One-foot upstream of I.H. 20.
Channel data from 1975 USACE field survey.
END DESCRIPTION:
XS GIS Cut Line= 2
      2298724.45      6933276.342299319.445994796933274.15684196
#Sta/Elev= 16
    1000     630    1025     620    1035     616    1060     614    1110     614
    1160     614    1280     612    1347     610    1400     590    1410     588
 1424.03     585 1444.03     585    1458     588    1490     614    1557     616
    1595     630
#Mann= 3 ,0,0
    1000     .08       0    1347    .055       0    1490     .08       0
Bank Sta=1347,1490
XS Rating Curve= 0 ,0
Exp/Cntr=0.5,0.3

Type RM Length L Ch R = 1 ,46280   ,120,120,120
BEGIN DESCRIPTION:
This cross section corresponds to cross section 46610 of the non-georeferenced CDC model which was the source of this model.
END DESCRIPTION:
XS GIS Cut Line= 2
      2298724.63      6933280.482299321.625474626933278.15550353
#Sta/Elev= 19
     999     643     999     633    1000     630    1035     616    1060     614
    1160     614    1280     612  1298.5   611.5    1347     610    1400     590
    1410     588    1424     585    1444     585    1458     588    1490     614
    1557     616    1595     630    1596     642    1596     652
#Mann= 3 ,0,0
     999     .08       0    1347    .055       0    1490     .08       0
Bank Sta=1347,1490
XS Rating Curve= 0 ,0
Exp/Cntr=0.5,0.3