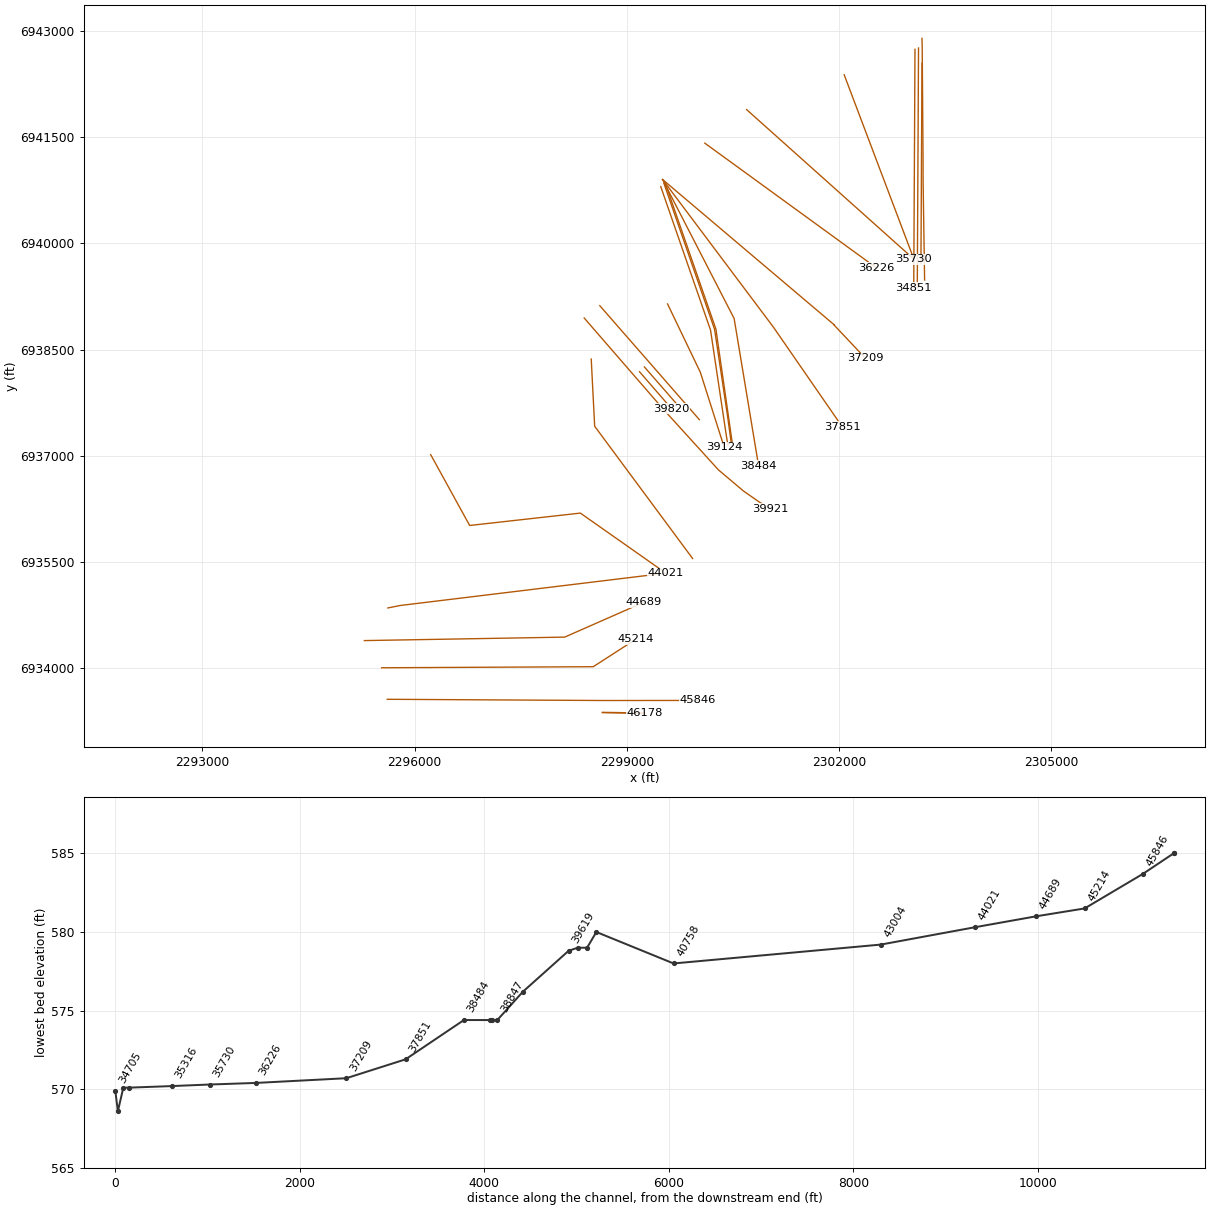
HEC-RAS study CDC_Consolidated_Model.prj: Upper Trinity CDC Consolidated Model

--- CDC_Consolidated_Model.g03 (geometry) --- (continued)

Type RM Length L Ch R = 3 ,46237   ,,,
BEGIN DESCRIPTION:
IH 20
Double bridge - one composite bridge represented.
Bridge data from bridge plans.  Downstream bridge four rows of piers.  Upstream bridge has six rows of piers.  Minimum low chord elev. 633.0.  Bridge width set at 120 feet.
Channel data from 1975 USACE field survey.
END DESCRIPTION:
Node Name=IH 20
Bridge Culvert--1,0,-1,-1, 0
Deck Dist Width WeirC Skew NumUp NumDn MinLoCord MaxHiCord MaxSubmerge Is_Ogee
1,118,2.6,0, 14, 10, , , 0.95, 0, ,,,
     999  1138.5  1141.5  1198.5  1201.5  1298.5  1301.5  1348.5  1351.5  1448.5
  1451.5  1563.5  1566.5    1596
     643   645.1   645.2     646   646.1   647.5   647.6   648.3   648.3   649.8
   649.8   651.5   651.6     652
     633   635.1   635.2     636   636.1   637.5   637.6   638.3   638.3   639.8
   639.8   641.5   641.6     642
     999  1138.5  1141.5  1298.5  1301.5  1448.5  1451.5  1563.5  1566.5    1596
     643   645.1   645.2   647.5   647.6   649.8   649.8   651.5   651.6     652
     633   635.1   635.2   637.5   637.6   639.8   639.8   641.5   641.6     642
Pier Skew, UpSta & Num, DnSta & Num=  ,1140, 2 ,1140, 2 , 0 , 0 , 0 ,,
       3       3
     580     640
       3       3
     580     640
Pier Skew, UpSta & Num, DnSta & Num=  ,1200, 2 ,1200, 2 , 0 , 0 , 0 ,,
       3       3
     580     640
       3       3
     580     640
Pier Skew, UpSta & Num, DnSta & Num=  ,1300, 2 ,1300, 2 , 0 , 0 , 0 ,,
       3       3
     580     640
       3       3
     580     640
Pier Skew, UpSta & Num, DnSta & Num=  ,1351, 2 ,1351, 2 , 0 , 0 , 0 ,,
       3       3
     580     642
       3       3
     580     642
Pier Skew, UpSta & Num, DnSta & Num=  ,1450, 2 ,1450, 2 , 0 , 0 , 0 ,,
       3       3
     580     642
       3       3
     580     642
Pier Skew, UpSta & Num, DnSta & Num=  ,1565, 2 ,1565, 2 , 0 , 0 , 0 ,,
       3       3
     580     642
       3       3
     580     642
BR Coef= 1 , 0 , 0 ,1.05, 0 ,,,0.8,-1,0.5,1,
WSPro=,,,, 1 ,,,, 0 ,,,, 0 ,,,,-1 ,-1 ,-1 , 0 , 0 , 0 , 0 , 0
BC Design=,, 0 ,, 0 ,,,,,,
BC HTab HWMax=652
BC Use User HTab Curves=0
BC User HTab FreeFlow(D)= 0

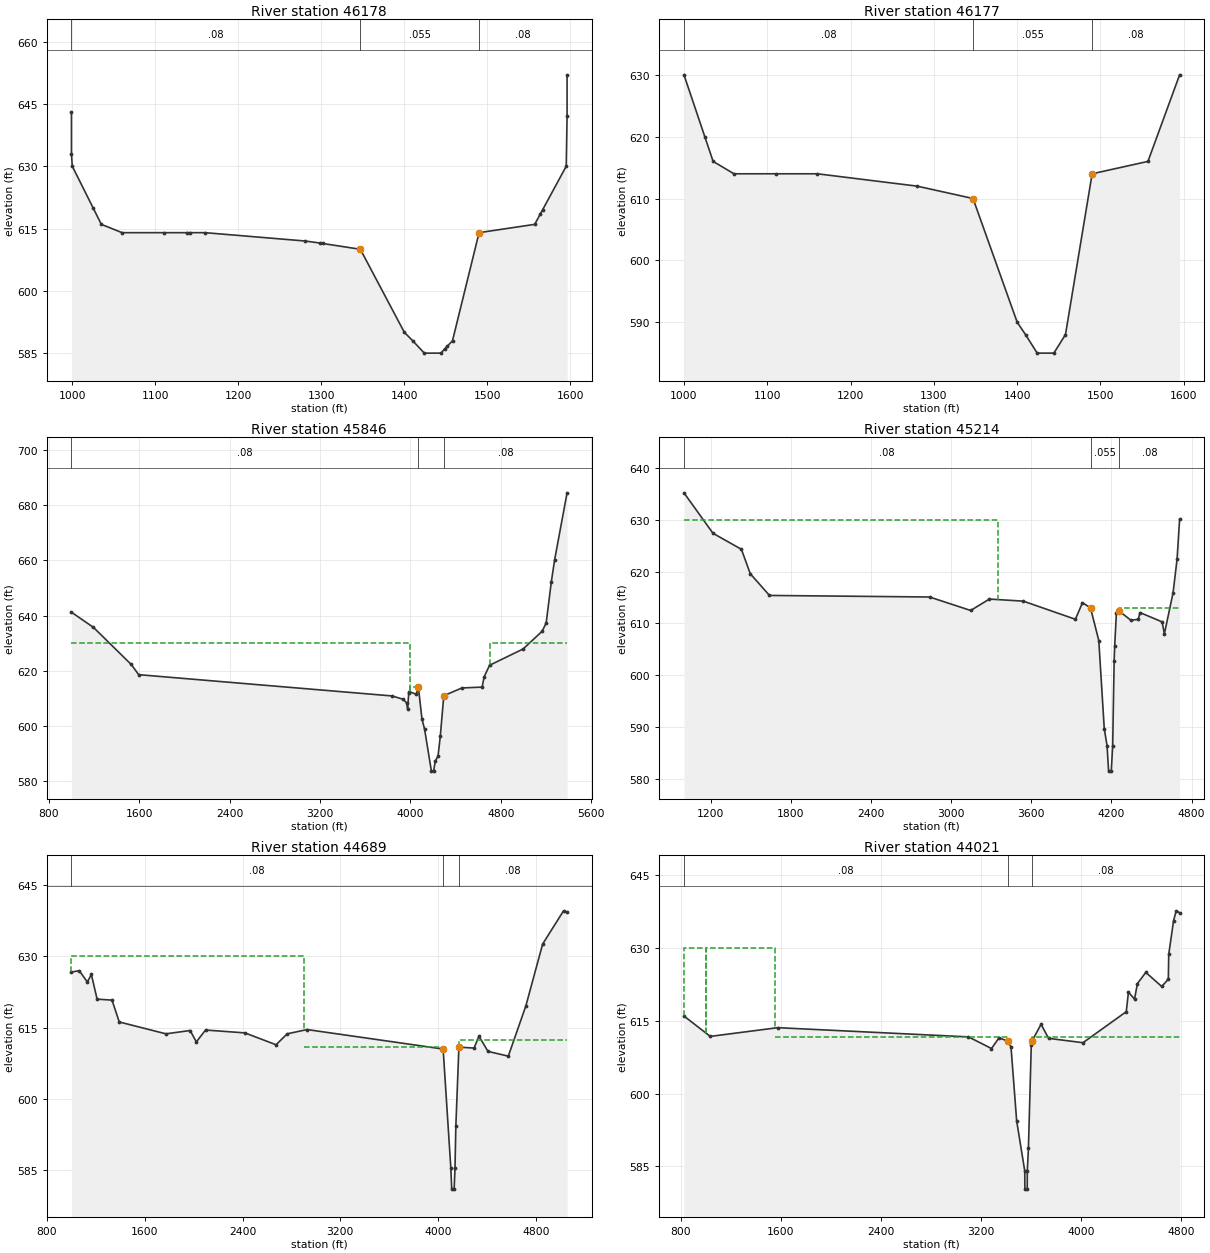
Type RM Length L Ch R = 1 ,46178   ,1,1,1
BEGIN DESCRIPTION:
This cross section corresponds to cross section 46490  of the non-georeferenced CDC model which was the source of this model.
END DESCRIPTION:
XS GIS Cut Line= 3
      2298655.66      6933368.69      2298729.42      6933367.14
2299252.561891536933357.88699104
#Sta/Elev= 28
     999     643     999     633    1000     630    1025     620    1035     616
    1060     614    1110     614  1138.5     614  1141.5     614    1160     614
    1280     612  1298.5   611.5  1301.5   611.4    1347     610    1400     590
    1410     588    1424     585    1444     585  1448.5     586  1451.5   586.6
    1458     588    1490     614    1557     616  1563.5   618.4  1566.5   619.5
    1595     630    1596     642    1596     652
#Mann= 3 ,0,0
     999     .08       0    1347    .055       0    1490     .08       0
Bank Sta=1347,1490
XS Rating Curve= 0 ,0
Exp/Cntr=0.5,0.3

Type RM Length L Ch R = 1 ,46177   ,332,332,144
BEGIN DESCRIPTION:
This cross section corresponds to cross section 46489 of the non-georeferenced CDC model which was the source of this model.
Duplication of following bridge cross-section without bridge piers.  One-foot downstream of I.H. 20.
Channel data from 1975 USACE field survey.
END DESCRIPTION:
XS GIS Cut Line= 3
      2298655.03      6933372.26      2298827.09      6933370.08
2299249.94041611 6933362.0745018
#Sta/Elev= 16
    1000     630    1025     620    1035     616    1060     614    1110     614
    1160     614    1280     612    1347     610    1400     590    1410     588
 1424.03     585 1444.03     585    1458     588    1490     614    1557     616
    1595     630
#Mann= 3 ,0,0
    1000     .08       0    1347    .055       0    1490     .08       0
Bank Sta=1347,1490
XS Rating Curve= 0 ,0
Exp/Cntr=0.3,0.1

Type RM Length L Ch R = 1 ,45846   ,632,632,590
BEGIN DESCRIPTION:
This cross section corresponds to cross section 46175 of the non-georeferenced CDC model which was the source of this model.
Cross-section modified by USACE February 2007 - blocked obstruction in LOB and ROB changed to ineffective flow.
Effective flow limit set at sta 4000 in LOB, at sta 4700 in ROB.
315 feet downstream of I.H. 20.
Channel data from 1975 USACE field survey.
END DESCRIPTION:
XS GIS Cut Line= 3
   2295613.70901   6933556.90594   2298682.34099   6933539.63694
    2300000.0001   6933540.79803
#Sta/Elev= 30
    1000   641.2    1195   635.7    1529   622.3    1595   618.6    3838   610.9
    3935   609.7    3966   608.4    3975   606.3    3985     612    3988   612.5
    4051   611.5    4070   614.1    4102   602.5    4125   598.9 4185.33   583.7
 4205.33   583.7    4219   587.3    4244   589.1    4264   596.3    4295     611
    4456   613.8    4634   614.1    4652   617.8    4700     622    4997   627.9
    5165   634.3    5201   637.3    5247   652.3    5276   660.2    5386   684.4
#Mann= 3 ,0,0
    1000     .08       0    4070    .055       0    4295     .08       0
#XS Ineff= 3 ,-1
    1000    4000     630    4700    5386     630    4000    4070   614.1
Permanent Ineff=
       F       F       F
Bank Sta=4070,4295
XS Rating Curve= 0 ,0
Exp/Cntr=0.3,0.1

Type RM Length L Ch R = 1 ,45214   ,525,525,344
BEGIN DESCRIPTION:
This cross section corresponds to cross section 45544 of the non-georeferenced CDC model which was the source of this model.
Cross-section modified by USACE February 2007 - blocked obstruction in LOB changed to ineffective flow.
Effective flow limit set at sta 3350 in LOB.
Channel data from 1975 USACE field survey.
END DESCRIPTION:
XS GIS Cut Line= 3
   2295534.77904   6934002.51003   2298525.87707   6934017.55101
   2299129.91096   6934407.41014
#Sta/Elev= 30
    1000   635.2    1217   627.4    1430   624.3    1496   619.6    1640   615.4
    2838   615.1    3146   612.5    3286   614.7    3540   614.3    3930   610.8
    3983     614    4043     613    4105   606.7    4146   589.7    4167   586.4
  4178.5   581.5  4198.5   581.5    4209   586.4    4220   602.8    4224   605.6
    4237   612.1    4257   612.4    4346   610.6    4401   610.8    4413   612.1
    4579   610.3    4596     608    4661   615.9    4691   622.4    4710   630.1
#Mann= 3 ,0,0
    1000     .08       0    4043    .055       0    4257     .08       0
#XS Ineff= 3 ,-1
    1000    3350     630    3350    4043     613    4257    4710     613
Permanent Ineff=
       F       F       F
Bank Sta=4043,4257
XS Rating Curve= 0 ,0
Exp/Cntr=0.3,0.1

Type RM Length L Ch R = 1 ,44689   ,668,668,503
BEGIN DESCRIPTION:
This cross section corresponds to cross section 45015 of the non-georeferenced CDC model which was the source of this model.
Cross-section modified by USACE February 2007 - blocked obstruction in LOB changed to ineffective flow.
Effective flow limit set at sta 2900 in LOB.
Channel data from 1975 USACE field survey.
END DESCRIPTION:
XS GIS Cut Line= 3
   2295290.26116   6934386.60605    2298121.8221   6934435.63187
   2299240.73193   6934928.33692
#Sta/Elev= 30
    1000   626.7    1064     627    1130   624.6    1163   626.2    1210     621
    1332   620.8    1391   616.2    1773   613.7    1971   614.4    2022     612
    2097   614.5    2419   613.9    2674   611.4    2765   613.7    2928   614.6
    4041   610.5    4104   585.4 4111.11     581 4131.11     581    4138   585.4
    4145   594.3    4170   610.9    4294   610.7    4334   613.2    4408     610
    4574     609    4718   619.6    4855   632.6    5026   639.6    5055   639.3
#Mann= 3 ,0,0
    1000     .08       0    4041    .055       0    4170     .08       0
#XS Ineff= 3 ,-1
    1000    2900     630    4170    5055   612.5    2900    4041     611
Permanent Ineff=
       F       F       F
Bank Sta=4041,4170
XS Rating Curve= 0 ,0
Exp/Cntr=0.3,0.1

Type RM Length L Ch R = 1 ,44021   ,1017,1017,641
BEGIN DESCRIPTION:
This cross section corresponds to cross section 44342 of the non-georeferenced CDC model which was the source of this model.
Cross-section modified by USACE February 2007 - blocked obstruction in LOB changed to ineffective flow.
Effective flow limit set at sta 1550 in LOB.
Channel data from 1975 USACE field survey.
END DESCRIPTION:
XS GIS Cut Line= 3
     2295622.839     6934847.758     2295795.582      6934882.48
   2299551.85238   6935339.42632
#Sta/Elev= 30
     825     616    1035   611.8    1574   613.6    3098   611.7    3282   609.3
    3342   611.5    3416   610.8    3438   609.6    3483   594.4    3548     584
 3548.62   580.3 3567.62   580.3    3568     584    3577   588.7    3600   610.1
    3605   610.8    3678   614.3    3738   611.4    4013   610.5    4359   616.9
    4376   620.9    4425   619.5    4448   622.7    4515     625    4642   622.1
    4695   623.6    4698   628.7    4737   635.7    4758   637.7    4785   637.3
#Mann= 3 ,0,0
     825     .08       0    3416    .055       0    3605     .08       0
#XS Ineff= 4 ,-1
    1000    1550     630     825    1000     630    3605    4785   611.7
    1550    3416   611.7
Permanent Ineff=
       F       F       F       F
Bank Sta=3416,3605
XS Rating Curve= 0 ,0
Exp/Cntr=0.3,0.1

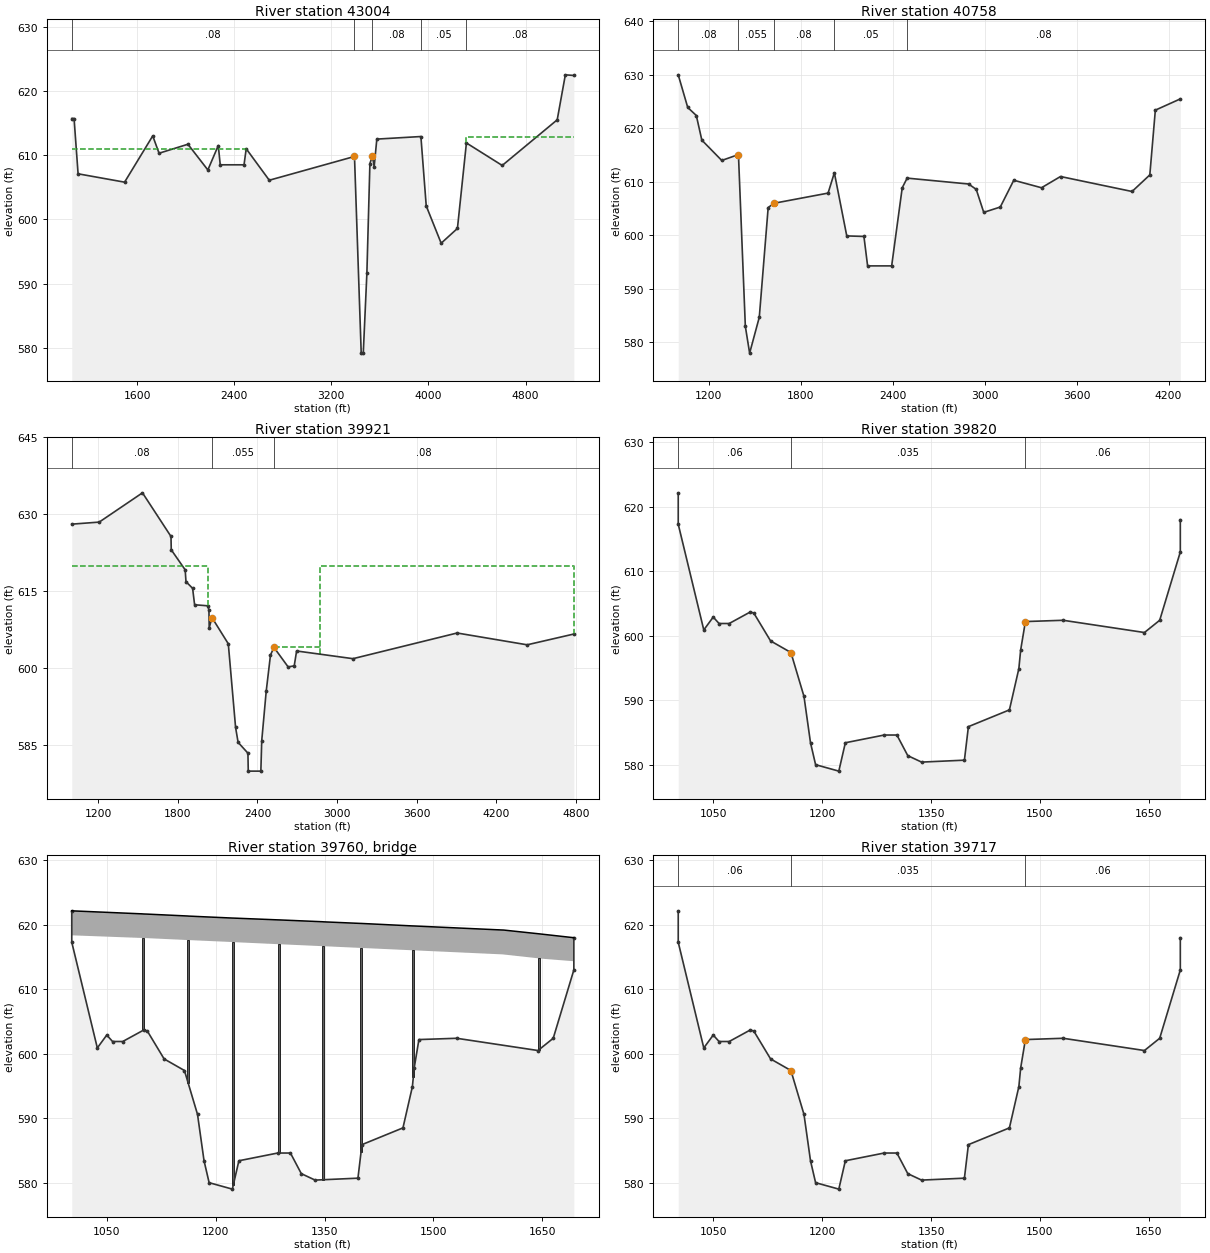
Type RM Length L Ch R = 1 ,43004   ,2246,2246,813
BEGIN DESCRIPTION:
This cross section corresponds to cross section 43324 of the non-georeferenced CDC model which was the source of this model.
Cross-section modified by USACE February 2007 - n value established for swale in ROB.
Channel data from 1975 USACE field survey.
END DESCRIPTION:
XS GIS Cut Line= 4
2296227.922348656937015.32448816   2296778.68994   6936013.50995
   2298343.33904   6936188.58014 2299503.9428611 6935373.2690315
#Sta/Elev= 30
    1062   615.7    1081   615.7    1114   607.1    1497   605.8    1729     613
    1781   610.3    2019   611.7    2183   607.7    2269   611.5    2285   608.5
    2481   608.5    2499     611    2689   606.1    3391   609.8 3446.38   579.2
 3463.38   579.2    3493   591.6    3518   608.7    3539   609.9    3553   608.2
    3575   612.5    3938   612.9    3982   602.1    4105   596.3    4239   598.6
    4313   611.9    4608   608.4    5061   615.5    5128   622.5    5198   622.4
#Mann= 5 ,-1,0
    1062     .08       0    3391    .055       0    3539     .08       0
    3938     .05       0    4313     .08       0
#XS Ineff= 3 ,-1
    1062    2495     611    2495    3391   609.8    4313    5198   612.9
Permanent Ineff=
       F       F       F
Bank Sta=3391,3539
XS Rating Curve= 0 ,0
Exp/Cntr=0.3,0.1

Type RM Length L Ch R = 1 ,40758   ,837,837,1301
BEGIN DESCRIPTION:
This cross section corresponds to cross section 41045 of the non-georeferenced CDC model which was the source of this model.
Cross-section modified by USACE February 2007.
Approx. 500 feet downstream of left bank of Mary's Creek. Channel data from 1975 USACE field survey.
END DESCRIPTION:
XS GIS Cut Line= 3
   2298496.96997   6938365.66108   2298545.68707   6937415.72991
     2299929.661   6935546.92492
#Sta/Elev= 30
    1000     630    1062   623.9    1118   622.4    1154   617.8    1284     614
    1393   615.1    1438     583    1466     578    1529   584.7    1587   605.2
    1625     606    1978   607.9    2019   611.7    2100   599.9    2212   599.8
    2236   594.3    2393   594.3    2462   608.9    2494   610.7    2895   609.6
    2945   608.6    2994   604.3    3102   605.3    3190   610.3    3371   608.9
    3495     611    3962   608.2    4078   611.3    4114   623.4    4277   625.5
#Mann= 5 ,-1,0
    1000     .08       0    1393    .055       0    1625     .08       0
    2019     .05       0    2494     .08       0
#XS Ineff= 2 , 0
       0    1393   615.1    1625       0   597.5
Permanent Ineff=
       F       F
Bank Sta=1393,1625
XS Rating Curve= 0 ,0
Exp/Cntr=0.3,0.1

Type RM Length L Ch R = 1 ,39921   ,101,101,101
BEGIN DESCRIPTION:
This cross section corresponds to cross section 40178 of the non-georeferenced CDC model which was the source of this model.
Cross-section modified by USACE February 2007. Effective flow set at sta 2030 in LOB, at sta 2870 in ROB.
END DESCRIPTION:
XS GIS Cut Line= 6
      2298397.21   6938946.20093   2299518.00992   6937653.98206
   2300294.94997   6936799.31513   2300648.71993   6936500.80195
   2300867.35795   6936348.04504   2301029.37403   6936250.21912
#Sta/Elev= 30
    1000   628.1    1207   628.5    1533   634.2    1748   625.7    1750   623.1
    1855   619.2    1861   616.9    1911   615.6    1926   612.4    2024   612.2
    2034   611.4    2036   607.9    2057   609.9    2180   604.8    2235   588.5
    2254   585.6    2328   583.5  2330.5     580  2425.5     580    2432   585.9
    2466   595.6    2498   602.6    2524   604.1    2631   600.3    2677   600.5
    2695   603.4    3120   601.9    3905   606.9    4433   604.6    4785   606.7
#Mann= 3 ,0,0
    1000     .08       0    2057    .055       0    2524     .08       0
#XS Ineff= 4 ,-1
    1000    2030     620    2870    4785     620    2030    2057   609.9
    2524    2870   604.1
Permanent Ineff=
       F       F       F       F
Bank Sta=2057,2524
XS Rating Curve= 0 ,0
Exp/Cntr=0.5,0.3

Type RM Length L Ch R = 1 ,39820   ,103,103,103
BEGIN DESCRIPTION:
This cross section corresponds to cross section 40064 of the non-georeferenced CDC model which was the source of this model.
Duplication of previous bridge cross-section without bridge piers.
One-foot upstream of S.H. 183 - Southwest Boulevard.
END DESCRIPTION:
XS GIS Cut Line= 2
     2299179.361     6938186.4732299632.674345646937664.15353711
#Sta/Elev= 30
  1001.8  622.17  1001.8   617.3    1037   600.9    1050   602.9    1058   601.9
    1072   601.9 1101.25   603.7    1106   603.5    1129   599.2    1157   597.4
    1175   590.6    1184   583.4    1191     580    1223     579    1232   583.4
  1285.5   584.6    1303   584.6    1318   581.4    1337   580.4    1396   580.7
  1401.5   585.9    1458   588.5    1471   594.9  1473.5   597.8    1480   602.2
    1532   602.4    1644   600.5    1665   602.4  1693.4     613  1693.4     618
#Mann= 3 ,0,0
  1001.8     .06       0    1157    .035       0    1480     .06       0
Bank Sta=1157,1480
XS Rating Curve= 0 ,0
Exp/Cntr=0.5,0.3

Type RM Length L Ch R = 3 ,39760   ,,,
BEGIN DESCRIPTION:
SH 183/Southwest Boulevard
Bridge data from 1975 survey.  Minimum low chord elev. 614.77.  Bridge width 85 feet.
Channel data from 1975 USACE field survey.
END DESCRIPTION:
Node Name=SH 183
Bridge Culvert--1,0,-1,-1, 0
Deck Dist Width WeirC Skew NumUp NumDn MinLoCord MaxHiCord MaxSubmerge Is_Ogee
1,85,2.6,0, 22, 22, , , 0.95, 0, ,,,
  1001.8 1098.75 1101.25    1106    1161  1163.5    1205    1223  1225.5  1285.5
    1288 1346.75 1349.25    1399  1401.5    1471  1473.5    1594  1596.5    1644
  1646.5  1693.4
  622.17   621.7  621.68  621.66  621.37  621.35  621.14  621.05  621.04  620.77
  620.76  620.48  620.46  620.22  620.21  619.83  619.82   619.2  619.19  618.62
  618.59     618
  618.37  617.96  617.95  617.93  617.64  617.63  617.42  617.33  617.31     617
  616.99  616.69  616.68  616.42  616.41  616.05  616.04  615.42   615.4  614.81
  614.77  614.35
  1001.8 1098.75 1101.25    1106    1161  1163.5    1205    1223  1225.5  1285.5
    1288 1346.75 1349.25    1399  1401.5    1471  1473.5    1594  1596.5    1644
  1646.5  1693.4
  622.17   621.7  621.68  621.66  621.37  621.35  621.14  621.05  621.04  620.77
  620.76  620.48  620.46  620.22  620.21  619.83  619.82   619.2  619.19  618.62
  618.59     618
  618.37  617.96  617.95  617.93  617.64  617.63  617.42  617.33  617.31     617
  616.99  616.69  616.68  616.42  616.41  616.05  616.04  615.42   615.4  614.81
  614.77  614.35
Pier Skew, UpSta & Num, DnSta & Num=  ,1100, 2 ,1100, 2 , 0 , 0 , 0 ,,
     2.5     2.5
     600     620
     2.5     2.5
     600     620
Pier Skew, UpSta & Num, DnSta & Num=  ,1162.25, 2 ,1162.25, 2 , 0 , 0 , 0 ,,
     2.5     2.5
     570     620
     2.5     2.5
     570     620
Pier Skew, UpSta & Num, DnSta & Num=  ,1224.25, 2 ,1224.25, 2 , 0 , 0 , 0 ,,
     2.5     2.5
     570     620
     2.5     2.5
     570     620
Pier Skew, UpSta & Num, DnSta & Num=  ,1286.75, 2 ,1286.75, 2 , 0 , 0 , 0 ,,
     2.5     2.5
     570     620
     2.5     2.5
     570     620
Pier Skew, UpSta & Num, DnSta & Num=  ,1348, 2 ,1348, 2 , 0 , 0 , 0 ,,
     2.5     2.5
     570     620
     2.5     2.5
     570     620
Pier Skew, UpSta & Num, DnSta & Num=  ,1400.25, 2 ,1400.25, 2 , 0 , 0 , 0 ,,
     2.5     2.5
     570     619
     2.5     2.5
     570     619
Pier Skew, UpSta & Num, DnSta & Num=  ,1472.25, 2 ,1472.25, 2 , 0 , 0 , 0 ,,
     2.5     2.5
     570     619
     2.5     2.5
     570     619
Pier Skew, UpSta & Num, DnSta & Num=  ,1645.25, 2 ,1645.25, 2 , 0 , 0 , 0 ,,
     2.5     2.5
     570     618
     2.5     2.5
     570     618
BR Coef= 1 , 0 , 0 ,1.05, 0 ,,,0.8,-1,0.5,1,
WSPro=,,,, 1 ,,,, 0 ,,,, 0 ,,,,-1 ,-1 ,-1 , 0 , 0 , 0 , 0 , 0
BC Design=,, 0 ,, 0 ,,,,,,
BC HTab HWMax=622.17
BC Use User HTab Curves=0
BC User HTab FreeFlow(D)= 0

Type RM Length L Ch R = 1 ,39717   ,98,98,98
BEGIN DESCRIPTION:
This cross section corresponds to cross section 39977 of the non-georeferenced CDC model which was the source of this model.
Duplication of following bridge cross-section without bridge piers.
Upstream end of Fort Worth Floodway.
Channel data from 1975 USACE field survey.
END DESCRIPTION:
XS GIS Cut Line= 2
2299248.380017766938253.76990765 2299703.3820877 6937732.9208633
#Sta/Elev= 30
  1001.8  622.17  1001.8   617.3    1037   600.9    1050   602.9    1058   601.9
    1072   601.9 1101.25   603.7    1106   603.5    1129   599.2    1157   597.4
    1175   590.6    1184   583.4    1191     580    1223     579    1232   583.4
  1285.5   584.6    1303   584.6    1318   581.4    1337   580.4    1396   580.7
  1401.5   585.9    1458   588.5    1471   594.9  1473.5   597.8    1480   602.2
    1532   602.4    1644   600.5    1665   602.4  1693.4     613  1693.4     618
#Mann= 3 ,0,0
  1001.8     .06       0    1157    .035       0    1480     .06       0
Bank Sta=1157,1480
XS Rating Curve= 0 ,0
Exp/Cntr=0.5,0.3

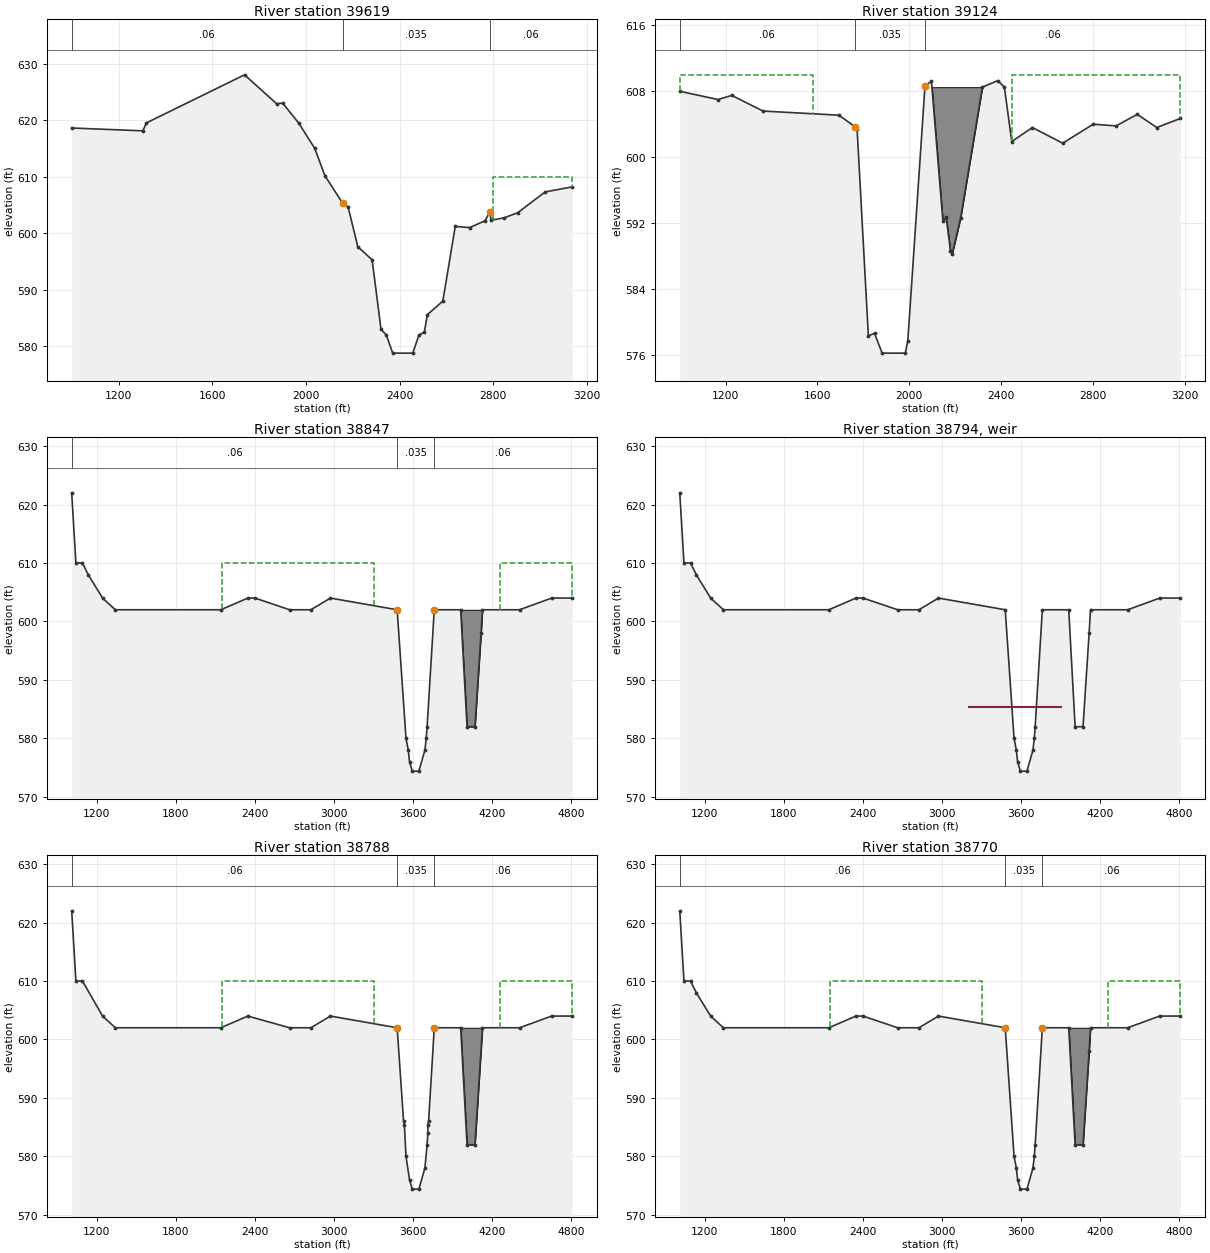
Type RM Length L Ch R = 1 ,39619   ,495,495,418
BEGIN DESCRIPTION:
This cross section corresponds to cross section 39879 of the non-georeferenced CDC model which was the source of this model.
Cross-section modified by USACE February 2007.  Effective  in LOB set at sta 2050, in ROB set at sta 2800.
99 feet downstream of S.H. 183 - Southwest Boulevard.
Channel data from 1975 USACE field survey.
END DESCRIPTION:
XS GIS Cut Line= 5
   2298618.45398   6939119.50899   2298788.15213   6938925.26889
   2299301.79513   6938337.33601   2299792.84107    6937775.2269
 2300025.2667818 6937509.5644535
#Sta/Elev= 30
    1000   618.6    1304   618.1    1319   619.5    1738     628    1875   622.9
    1901     623    1969   619.5    2038     615    2081   610.2    2157   605.3
    2180   604.7    2222   597.6    2283   595.3    2321     583 2343.81     582
 2370.81   578.8 2456.81   578.8 2482.81     582    2506   582.5    2519   585.6
    2585     588    2638   601.2    2700     601    2765   602.2    2786   603.8
    2791   602.3    2845   602.7    2904   603.6    3022   607.3    3138   608.2
#Mann= 3 ,0,0
    1000     .06       0    2157    .035       0    2786     .06       0
#XS Ineff= 4 ,-1
    1000    2050     610    2800    3138     610    2050    2157   605.3
    2786    2800   603.8
Permanent Ineff=
       F       F       F       F
Bank Sta=2157,2786
XS Rating Curve= 0 ,0
Exp/Cntr=0.3,0.1

Type RM Length L Ch R = 1 ,39124   ,277,277,277
BEGIN DESCRIPTION:
This cross section corresponds to cross section 39380 of the non-georeferenced CDC model which was the source of this model.
Cross-section modified by USACE February 2007.  Effective  in LOB set at sta 1580, in ROB set at sta 2450.  Old river channel in ROB.  Channel data from 1975 USACE field survey.
Note:  Channel dam indicated on 1991 topography has been removed by the TRWD after construction of the new downstream channel dam and during the completion of the original CDC Model.
END DESCRIPTION:
XS GIS Cut Line= 3
   2299575.70305   6939144.79109   2300039.24313   6938178.48396
    2300375.7546   6937120.47394
#Sta/Elev= 30
    1000     608    1167     607    1227   607.5    1363   605.6    1694   605.1
    1763   603.7    1773   603.4    1822   578.3    1849   578.6    1882   576.2
    1983   576.2    1994   577.7    2069   608.7    2097   609.2    2147   592.2
    2161   592.7    2180   588.6    2187   588.2    2224   592.6    2319   608.5
    2386   609.3    2415   608.5    2447   601.9    2537   603.6    2669   601.7
    2802     604    2902   603.8    2994   605.2    3079   603.6    3182   604.7
#Mann= 3 ,0,0
    1000     .06       0    1763    .035       0    2069     .06       0
#XS Ineff= 2 , 0
       0    1580     610    2450       0     610
Permanent Ineff=
       F       F
#Block Obstruct= 1 ,-1
    2097    2319   608.5
Bank Sta=1763,2069
XS Rating Curve= 0 ,0
Exp/Cntr=0.3,0.1

Type RM Length L Ch R = 1 ,38847   ,58,58,58
BEGIN DESCRIPTION:
This cross section corresponds to cross section 39101 of the non-georeferenced CDC model which was the source of this model.
Cross-section modified by USACE February 2007.
Ineffective flow in LOB due to group of structures, effective flow in ROB set at sta 4260.
END DESCRIPTION:
XS GIS Cut Line= 4
2299479.566364796940803.23077657 2300183.0383354 6938775.8264183
      2300405.25      6937290.92       2300429.4     6937142.698
#Sta/Elev= 30
  1009.4     622  1041.3     610    1091     610  1134.8     608  1243.6     604
  1340.3     602  2140.2     602  2345.8     604  2400.2     604  2661.8     602
  2823.7     602  2971.9     604  3478.3     602  3545.3     580  3562.8     578
  3572.1     576    3593   574.4    3643   574.4  3688.7     578  3698.8     580
  3705.5     582  3759.8     602  3960.1     602  4008.4     582  4068.4     582
  4114.7     598  4125.3     602    4407     602    4650     604    4807     604
#Mann= 3 ,0,0
  1009.4     .06       0  3478.3    .035       0  3759.8     .06       0
#XS Ineff= 5 ,-1
  1009.4    2150     602    2150    3300     610    3300  3478.3     602
  3759.8    4260     602    4260    4807     610
Permanent Ineff=
       F       F       F       F       F
#Block Obstruct= 1 ,-1
 3960.12  4125.3     602
Bank Sta=3478.3,3759.8
XS Rating Curve= 0 ,0
Exp/Cntr=0.3,0.1

Type RM Length L Ch R = 5 ,38794   ,,,
BEGIN DESCRIPTION:
Cityview Dam
Data from plans.  Crest elevation 585.4, width 12 feet.
END DESCRIPTION:
Node Name=Cityview Dam
IW Pilot Flow=0
#Inline Weir SE= 2
    3200   585.4    3900   585.4
IW Dist,WD,Coef,Skew,MaxSub,Min_El,Is_Ogee,SpillHt,DesHd
33,12,3,0,0.95,, 0 ,,,2,2,
Inline Weir Flap Gates= 0
IW Outlet Rating Curve= 0 ,False,,

Type RM Length L Ch R = 1 ,38788   ,18,18,18
BEGIN DESCRIPTION:
This cross section corresponds to cross section 39055 of the non-georeferenced CDC model which was the source of this model.
One-foot downstream of Cityview Dam.
Cross-section modified by USACE February 2007.
Ineffective flow in LOB due to group of structures, effective flow in ROB set at sta 4260.
Old river channel in ROB.
Channel data from 1975 USACE field survey.
END DESCRIPTION:
XS GIS Cut Line= 4
2299524.272482346940850.03415726   2300240.39496   6938786.17107
   2300421.66396   6937574.60689      2300474.54      6937190.25
#Sta/Elev= 30
  1009.4     622  1041.3     610    1091     610  1243.6     604  1340.3     602
  2140.2     602  2345.8     604  2661.8     602  2823.7     602  2971.9     604
  3478.3     602    3527     586  3533.1   585.4  3545.3     580  3572.1     576
    3593   574.4    3643   574.4  3688.7     578  3705.5     582  3711.2     584
  3711.2   585.4  3716.8     586  3759.8     602  3960.1     602  4008.4     582
  4068.4     582  4125.3     602    4407     602    4650     604    4807     604
#Mann= 3 ,0,0
  1009.4     .06       0  3478.3    .035       0  3759.8     .06       0
#XS Ineff= 5 ,-1
  1009.4    2150     602    2150    3300     610    3300  3478.3     602
  3759.8    4260     602    4260    4807     610
Permanent Ineff=
       F       F       F       F       F
#Block Obstruct= 1 ,-1
 3960.12  4125.3     602
Bank Sta=3478.3,3759.8
XS Rating Curve= 0 ,0
Exp/Cntr=0.3,0.1

Type RM Length L Ch R = 1 ,38770   ,286,286,286
BEGIN DESCRIPTION:
This cross section corresponds to cross section 39023 of the non-georeferenced CDC model which was the source of this model.
Cross-section modified by USACE February 2007.
39 feet downstream of Cityview Dam.  Ineffective flow in LOB due to group of structures, effective flow in ROB set at sta 4260.
Old river channel in ROB.
Channel data from 1975 USACE field survey.
END DESCRIPTION:
XS GIS Cut Line= 4
2299530.905865176940852.77955862      2299570.13      6940774.24
 2300259.3457513 6938788.5749798      2300487.99      6937196.98
#Sta/Elev= 30
  1009.4     622  1041.3     610    1091     610  1134.8     608  1243.6     604
  1340.3     602  2140.2     602  2345.8     604  2400.2     604  2661.8     602
  2823.7     602  2971.9     604  3478.3     602  3545.3     580  3562.8     578
  3572.1     576    3593   574.4    3643   574.4  3688.7     578  3698.8     580
  3705.5     582  3759.8     602  3960.1     602  4008.4     582  4068.4     582
  4114.7     598  4125.3     602    4407     602    4650     604    4807     604
#Mann= 3 ,0,0
  1009.4     .06       0  3478.3    .035       0  3759.8     .06       0
#XS Ineff= 5 ,-1
  1009.4    2150     602    2150    3300     610    3300  3478.3     602
  3759.8    4260     602    4260    4807     610
Permanent Ineff=
       F       F       F       F       F
#Block Obstruct= 1 ,-1
 3960.12  4125.3     602
Bank Sta=3478.3,3759.8
XS Rating Curve= 0 ,0
Exp/Cntr=0.3,0.1

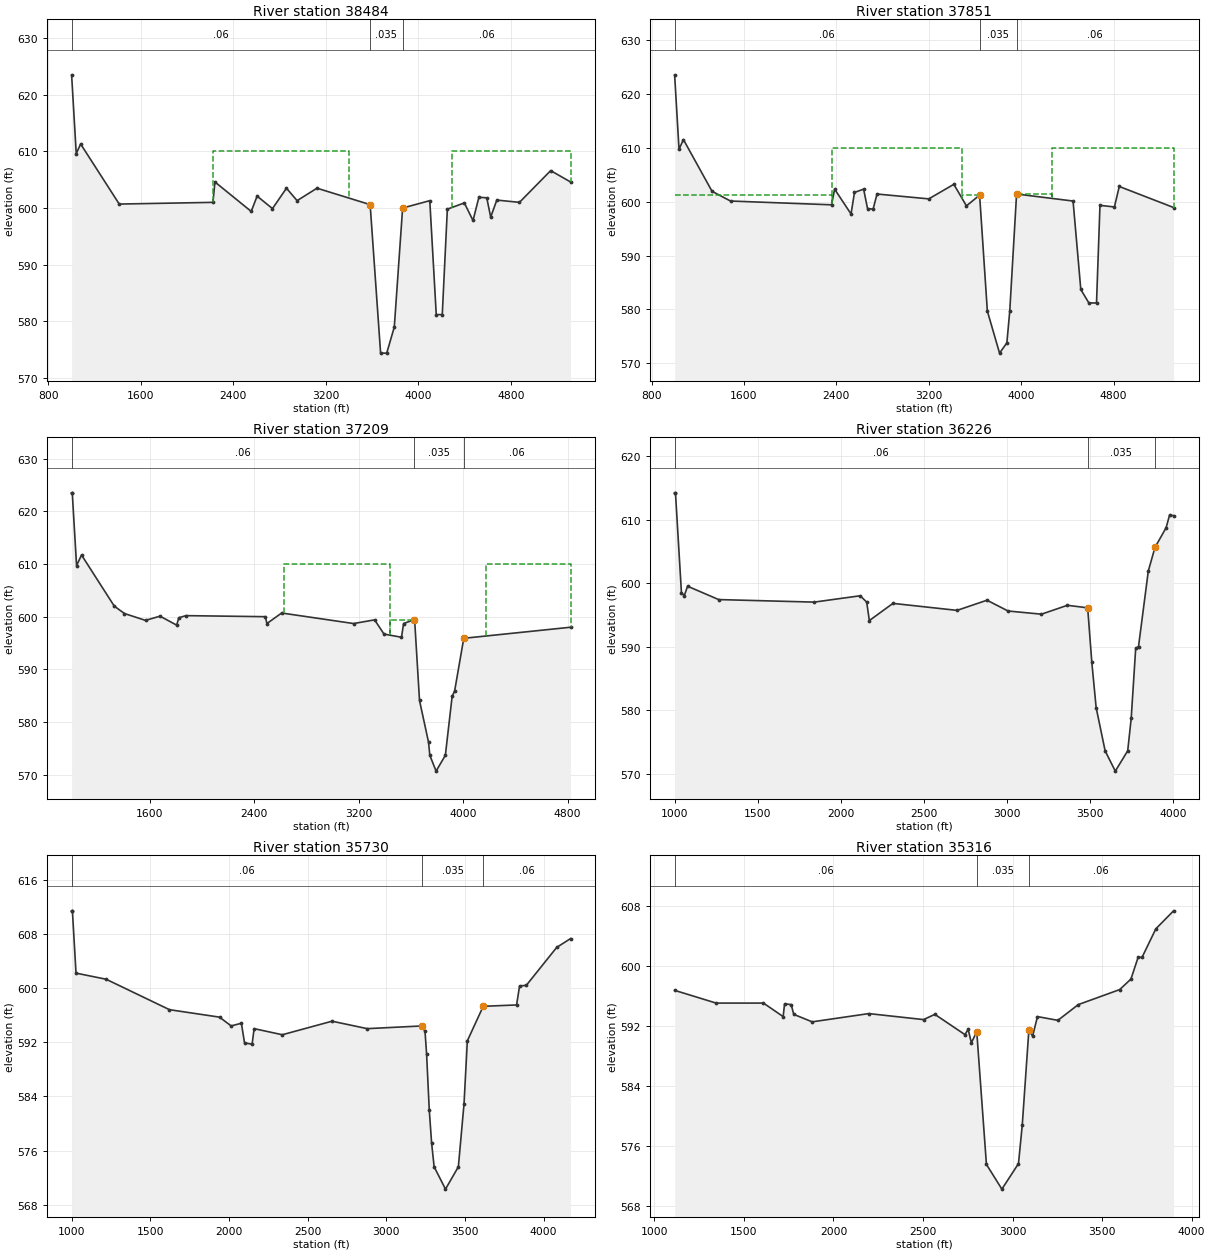
Type RM Length L Ch R = 1 ,38484   ,633,633,838
BEGIN DESCRIPTION:
This cross section corresponds to cross section 38738 of the non-georeferenced CDC model which was the source of this model.
Cross-section modified by USACE February 2007.
Ineffective flow in LOB due to group of structures, effective flow in ROB set at sta 4290.
Old river channel in ROB.
Channel data from 1975 USACE field survey.
END DESCRIPTION:
XS GIS Cut Line= 3
   2299505.98206   6940902.74689   2300516.75005   6938938.63894
   2300862.11911   6936859.02007
#Sta/Elev= 30
    1000   623.5    1040   609.6    1078   611.3    1412   600.7    2223     601
    2240   604.6    2554   599.4    2605   602.1    2738   599.9    2859   603.5
    2951   601.3    3123   603.5    3583   600.6 3673.51   574.4 3726.51   574.4
    3792     579    3864     600    4099   601.3    4155   581.2    4207   581.2
    4251   599.8    4398   600.9    4473   597.8    4524   601.9    4592   601.8
    4626   598.4    4679   601.4    4875     601    5145   606.6    5317   604.6
#Mann= 3 ,0,0
    1000     .06       0    3583    .035       0    3864     .06       0
#XS Ineff= 5 ,-1
    2220    3400     610    4290    5317     610    3400    3583   600.6
    1000    2220   600.6    3864    4290     600
Permanent Ineff=
       F       F       F       F       F
#Block Obstruct= 2 , 0
                            4099           601.3
Bank Sta=3583,3864
XS Rating Curve= 0 ,0
Exp/Cntr=0.3,0.1

Type RM Length L Ch R = 1 ,37851   ,642,642,751
BEGIN DESCRIPTION:
This cross section corresponds to cross section 38091 of the non-georeferenced CDC model which was the source of this model.
Cross-section modified by USACE February 2007.
Ineffective flow in LOB due to group of structures, effective flow in ROB set at sta 4270.
Old river channel in ROB.
Channel data from 1975 USACE field survey.
END DESCRIPTION:
XS GIS Cut Line= 3
    2299506.1169    6940902.5671   2301072.22401   6938816.13295
   2302044.02292   6937409.74206
#Sta/Elev= 30
    1000   623.5    1038   609.7    1076   611.5    1324   601.9    1484   600.1
    2358   599.4    2385   602.3    2527   597.7    2557   601.7    2636   602.3
    2670   598.7    2718   598.6    2752   601.4    3200   600.5    3417   603.2
    3526   599.2    3640   601.2    3707   579.7 3812.69   571.9    3876   573.8
    3901   579.7    3960   601.4    4449   600.1    4516   583.7    4586   581.2
    4652   581.2    4682   599.3    4807     599    4849   602.8    5319   598.9
#Mann= 3 ,0,0
    1000     .06       0    3640    .035       0    3960     .06       0
#XS Ineff= 5 ,-1
    2360    3490     610    4270    5319     610    3960    4270   601.4
    3490    3640   601.2    1000    2360   601.2
Permanent Ineff=
       F       F       F       F       F
#Block Obstruct= 2 , 0
                            4449           600.1
Bank Sta=3640,3960
XS Rating Curve= 0 ,0
Exp/Cntr=0.3,0.1

Type RM Length L Ch R = 1 ,37209   ,982,982,1023
BEGIN DESCRIPTION:
This cross section corresponds to cross section 37449 of the non-georeferenced CDC model which was the source of this model.
Cross-section modified by USACE February 2007.
Ineffective flow in LOB due to group of structures.
Lockheed Recreation Area in ROB.
Channel data from 1975 USACE field survey.
END DESCRIPTION:
XS GIS Cut Line= 4
   2299506.17596   6940902.58285   2301929.37091   6938851.04594
     2301925.292     6938850.987     2302370.605     6938378.331
#Sta/Elev= 30
    1000   623.5    1005   623.5    1038   609.7    1076   611.7    1327     602
    1405   600.6    1566   599.3    1677   600.1    1805   598.4    1821   599.8
    1876   600.2    2484     600    2496   598.7    2609   600.7    3160   598.7
    3321   599.4    3393   596.7    3527   596.1    3543   598.7    3621   599.4
    3628   599.2    3665   584.1    3734   576.2    3744   573.7 3792.04   570.7
    3863   573.7    3915   584.9    3934   585.9    4004   595.9    4822     598
#Mann= 3 ,0,0
    1000     .06       0    3621    .035       0    4004     .06       0
#XS Ineff= 5 ,-1
    2630    3440     610    4175    4822     610    3440    3621   599.4
    1000    2630   599.4    4004    4175   595.9
Permanent Ineff=
       F       F       F       F       F
Bank Sta=3621,4004
XS Rating Curve= 0 ,0
Exp/Cntr=0.3,0.1

Type RM Length L Ch R = 1 ,36226   ,497,497,463
BEGIN DESCRIPTION:
This cross section corresponds to cross section 36466 of the non-georeferenced CDC model which was the source of this model.
Channel data from 1975 USACE field survey.
END DESCRIPTION:
XS GIS Cut Line= 2
   2300102.25187   6941417.19993   2302531.11905   6939651.87898
#Sta/Elev= 30
    1000   614.2    1005   614.2    1041   598.5    1058     598    1078   599.5
    1265   597.4    1840     597    2117     598    2156     597    2172   594.1
    2314   596.8    2700   595.7    2880   597.3    3007   595.6    3208   595.1
    3364   596.5    3486   596.1    3511   587.5    3537   580.4    3591   573.6
 3652.28   570.4    3727   573.6    3748   578.7    3775   589.7    3792     590
    3851   601.9    3891   605.6    3958   608.7    3979   610.7    4003   610.6
#Mann= 3 ,0,0
    1000     .06       0    3486    .035       0    3891     .06       0
Bank Sta=3486,3891
XS Rating Curve= 0 ,0
Exp/Cntr=0.3,0.1

Type RM Length L Ch R = 1 ,35730   ,414,414,271
BEGIN DESCRIPTION:
This cross section corresponds to cross section 35969 of the non-georeferenced CDC model which was the source of this model.
Channel data from 1975 USACE field survey.
END DESCRIPTION:
XS GIS Cut Line= 2
    2300693.3081   6941891.10515    2303057.2768   6939777.65334
#Sta/Elev= 30
    1000   611.4    1005   611.4    1028   602.2    1219   601.3    1622   596.8
    1940   595.7    2014   594.4    2079   594.8    2099   591.9    2147   591.7
    2160     594    2339   593.1    2655   595.1    2879     594    3227   594.4
    3246   593.6    3256   590.3    3273     582    3288   577.1    3304   573.6
 3376.18   570.3    3458   573.6    3494   582.9    3515   592.2    3616   597.3
    3828   597.5    3847   600.3    3890   600.4    4083     606    4171   607.3
#Mann= 3 ,0,0
    1000     .06       0    3227    .035       0    3616     .06       0
Bank Sta=3227,3616
XS Rating Curve= 0 ,0
Exp/Cntr=0.3,0.1

Type RM Length L Ch R = 1 ,35316   ,465,465,336
BEGIN DESCRIPTION:
This cross section corresponds to cross section 35519 of the non-georeferenced CDC model which was the source of this model.
Channel data from 1975 USACE field survey.
END DESCRIPTION:
XS GIS Cut Line= 2
2302071.995496046942383.72166837   2303057.27811   6939777.76423
#Sta/Elev= 30
    1113   596.7    1345     595    1609     595    1719   593.2    1727   594.9
    1764   594.8    1778   593.5    1881   592.5    2197   593.6    2503   592.8
    2566   593.5    2734   590.8    2752   591.5    2770   589.7    2800   591.2
    2854   573.5  2940.3   570.2    3033   573.6    3054   578.7    3091   591.4
    3112   590.6    3139   593.2    3253   592.7    3367   594.8    3598   596.8
    3661   598.2    3701   601.1    3723   601.1    3800   604.9    3899   607.3
#Mann= 3 ,0,0
    1113     .06       0    2800    .035       0    3091     .06       0
Bank Sta=2800,3091
XS Rating Curve= 0 ,0
Exp/Cntr=0.3,0.1

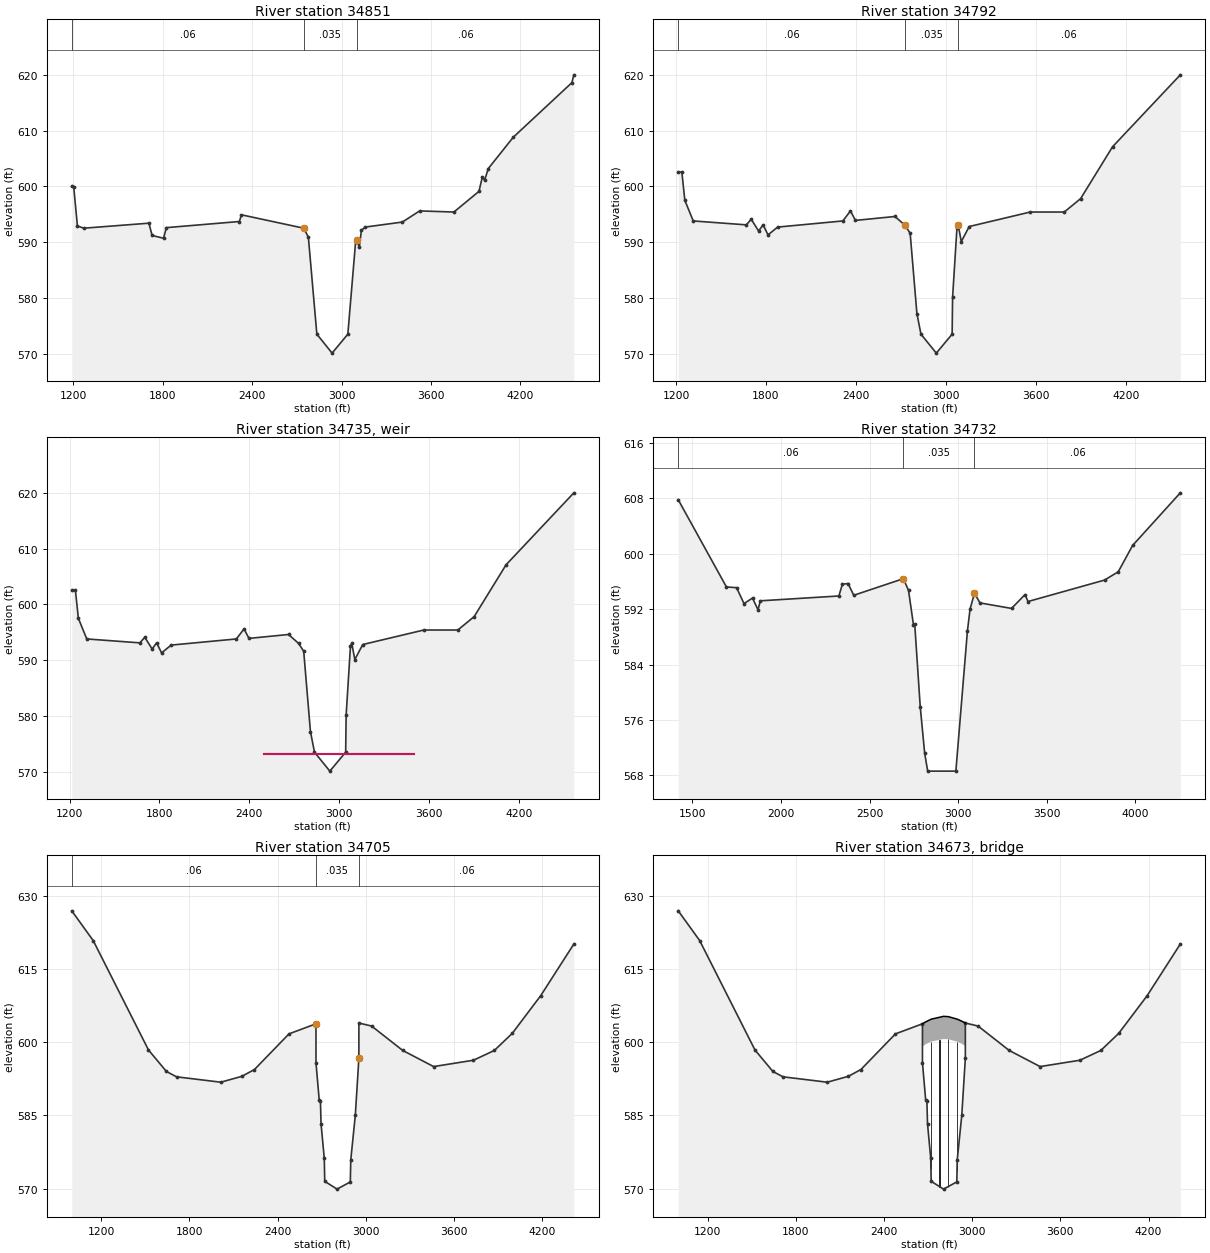
Type RM Length L Ch R = 1 ,34851   ,59,59,59
BEGIN DESCRIPTION:
This cross section corresponds to cross section 35076 of the non-georeferenced CDC model which was the source of this model.
50 feet upstream of channel dam.
Channel data from 1975 USACE field survey.
END DESCRIPTION:
XS GIS Cut Line= 4
2303072.729449086942743.06528603   2303057.34208   6939777.59494
 2303055.4949284 6939421.6380934      2303055.49      6939373.11
#Sta/Elev= 30
    1189     600    1202   599.9    1227   592.9    1270   592.5    1707   593.4
    1728   591.2    1805   590.7    1824   592.6    2314   593.7    2328   594.9
    2746   592.5    2777   590.9    2834   573.5 2936.39   570.1    3042   573.5
    3094     590    3103   590.3    3119   589.1    3133   592.1    3158   592.7
    3408   593.6    3524   595.6    3754   595.4    3922   599.1    3945   601.7
    3960   601.1    3985   603.2    4152   608.8    4546   618.6    4559     620
#Mann= 3 ,0,0
    1189     .06       0    2746    .035       0    3103     .06       0
Bank Sta=2746,3103
XS Rating Curve= 0 ,0
Exp/Cntr=0.3,0.1

Type RM Length L Ch R = 1 ,34792   ,59,59,59
BEGIN DESCRIPTION:
This cross section corresponds to cross section 35016 of the non-georeferenced CDC model which was the source of this model.
One-foot upstream of channel dam.
END DESCRIPTION:
XS GIS Cut Line= 3
 2303122.8282236 6942762.0636041  2303105.622972  6939446.267027
      2303106.02      6939373.11
#Sta/Elev= 30
    1215   602.5    1239   602.6    1259   597.5    1315   593.8    1669   593.1
    1702   594.1    1751     592    1781   593.1    1814   591.3    1878   592.7
    2313   593.8    2364   595.6    2397   593.9    2661   594.6    2728     593
    2762   591.6    2807   577.2    2834   573.5 2936.39   570.1    3042   573.5
    3045   580.1    3074   592.5    3083     593    3103   590.1    3156   592.8
    3563   595.4    3790   595.4    3899   597.8    4112   607.1    4564     620
#Mann= 3 ,0,0
    1215     .06       0    2728    .035       0    3083     .06       0
Bank Sta=2728,3083
XS Rating Curve= 0 ,0
Exp/Cntr=0.3,0.1

Type RM Length L Ch R = 5 ,34735   ,,,
BEGIN DESCRIPTION:
channel dam
crest elevation 573.2
END DESCRIPTION:
Node Name=channel dam
IW Pilot Flow=0
#Inline Weir SE= 2
    2500   573.2    3500   573.2
IW Dist,WD,Coef,Skew,MaxSub,Min_El,Is_Ogee,SpillHt,DesHd
1,5,3,0,0.95,, 0 ,,,2,2,
Inline Weir Flap Gates= 0
IW Outlet Rating Curve= 0 ,False,,

Type RM Length L Ch R = 1 ,34732   ,28,28,28
BEGIN DESCRIPTION:
This cross section corresponds to cross section 34957 of the non-georeferenced CDC model which was the source of this model.
43 feet upstream of Bryant-Irvin Road, 55.5 feet downstream of channel dam.
Channel data from 1975 USACE field survey.
END DESCRIPTION:
XS GIS Cut Line= 3
  2303171.707448 6942545.9068369 2303157.7506186  6939856.216303
2303157.012371286939713.94496309
#Sta/Elev= 30
    1421   607.8    1693   595.2    1750   595.1    1792   592.8    1840   593.6
    1871   591.9    1884   593.2    2327   593.9    2347   595.6    2379   595.7
    2411     594    2691   596.4    2720   594.7    2748   589.7    2755   589.8
    2786   577.9    2811   571.2    2828   568.6    2987   568.6    3052   588.8
    3067     592    3092   594.3    3123   592.9    3301   592.1    3377   594.1
    3394   593.1    3826   596.2    3903   597.4    3984   601.2    4253   608.8
#Mann= 3 ,0,0
    1421     .06       0    2691    .035       0    3092     .06       0
#XS Ineff= 2 , 0
       0    2691   596.4    3092       0   594.3
Permanent Ineff=
       F       F
Bank Sta=2691,3092
XS Rating Curve= 0 ,0
Exp/Cntr=0.5,0.3

Type RM Length L Ch R = 1 ,34705   ,50,50,50
BEGIN DESCRIPTION:
This cross section corresponds to cross section 34915 of the non-georeferenced CDC model which was the source of this model.
Duplication of previous bridge cross-section without bridge piers.
One-foot upstream of Bryant-Irvin Road.
Bank stations changed by USACE February 2007.
END DESCRIPTION:
XS GIS Cut Line= 5
      2303171.28      6942898.55  2303174.718485 6942779.8316517
     2303186.522     6941229.008     2303187.607     6940864.424
2303208.961237226939482.81133342
#Sta/Elev= 30
    1000   626.9    1146   620.8    1522   598.4    1644     594    1713   592.9
    2014   591.8    2157     593    2243   594.4    2478   601.7 2661.58  603.76
 2661.58   595.8 2683.39   588.2 2691.78     588 2695.97   583.3 2717.95  576.21
 2721.13   571.5    2805   569.9 2895.23  571.38 2898.23  575.89 2929.12     585
 2953.44   596.7 2953.44  603.92    3040   603.3    3252   598.3    3462     595
    3733   596.3    3875   598.3    3997   601.8    4190   609.5    4416   620.1
#Mann= 3 ,0,0
    1000     .06       0 2661.58    .035       0 2953.44     .06       0
Bank Sta=2661.58,2953.44
XS Rating Curve= 0 ,0
Exp/Cntr=0.5,0.3

Type RM Length L Ch R = 3 ,34673   ,,,
BEGIN DESCRIPTION:
Bryant-Irvin Road - south bound
END DESCRIPTION:
Node Name=Bryant-Irvin Roa
Bridge Culvert--1,0,-1,-1, 0
Deck Dist Width WeirC Skew NumUp NumDn MinLoCord MaxHiCord MaxSubmerge Is_Ogee
1,35,2.6,0, 14, 14, , , 0.95, 0, ,,,
 2661.58 2683.39 2717.95 2720.95 2721.13 2776.66 2779.66    2805 2835.37 2838.37
 2895.23 2898.23 2929.12    2954
  603.76  604.15  604.66  604.71  604.71  605.09  605.11  605.29  605.23  605.22
  604.74  604.71  604.29  603.92
  599.08  599.57  600.08  600.12  600.12  600.47  600.49  600.65   600.6  600.59
  600.13   600.1  599.67  599.18
 2661.58 2683.39 2717.95 2720.95 2721.13 2776.66 2779.66    2805 2835.37 2838.37
 2895.23 2898.23 2929.12    2954
  603.76  604.15  604.66  604.71  604.71  605.09  605.11  605.29  605.23  605.22
  604.74  604.71  604.29  603.92
  599.08  599.57  600.08  600.12  600.12  600.47  600.49  600.65   600.6  600.59
  600.13   600.1  599.67  599.18
Pier Skew, UpSta & Num, DnSta & Num=  ,2719.45, 2 ,2719.45, 2 , 0 , 0 , 0 ,,
       3       3
     560     602
       3       3
     560     602
Pier Skew, UpSta & Num, DnSta & Num=  ,2778.16, 2 ,2778.16, 2 , 0 , 0 , 0 ,,
       3       3
     560     602
       3       3
     560     602
Pier Skew, UpSta & Num, DnSta & Num=  ,2836.87, 2 ,2836.87, 2 , 0 , 0 , 0 ,,
       3       3
     560     602
       3       3
     560     602
Pier Skew, UpSta & Num, DnSta & Num=  ,2896.73, 2 ,2896.73, 2 , 0 , 0 , 0 ,,
       3       3
     560     602
       3       3
     560     602
BR Coef= 1 , 0 , 0 ,1.05, 0 ,,,0.8,-1,0.5,1,
WSPro=,,,, 1 ,,,, 0 ,,,, 0 ,,,,-1 ,-1 ,-1 , 0 , 0 , 0 , 0 , 0
BC Design=,, 0 ,, 0 ,,,,,,
BC HTab HWMax=626.9
BC Use User HTab Curves=0
BC User HTab FreeFlow(D)= 0