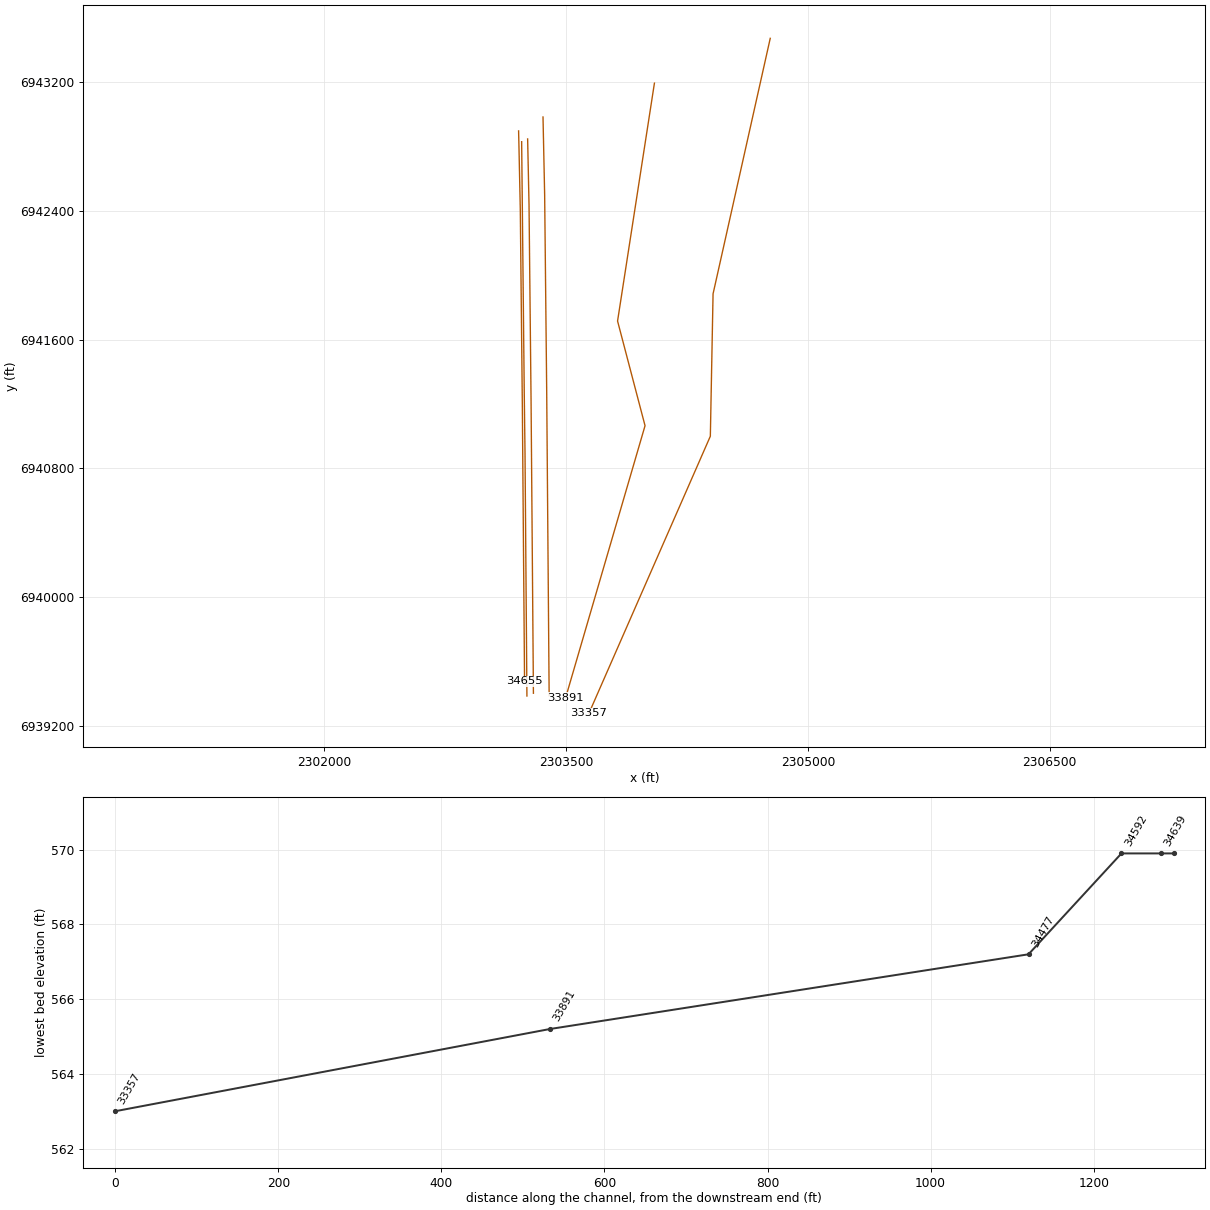
HEC-RAS study CDC_Consolidated_Model.prj: Upper Trinity CDC Consolidated Model

--- CDC_Consolidated_Model.g03 (geometry) --- (continued)

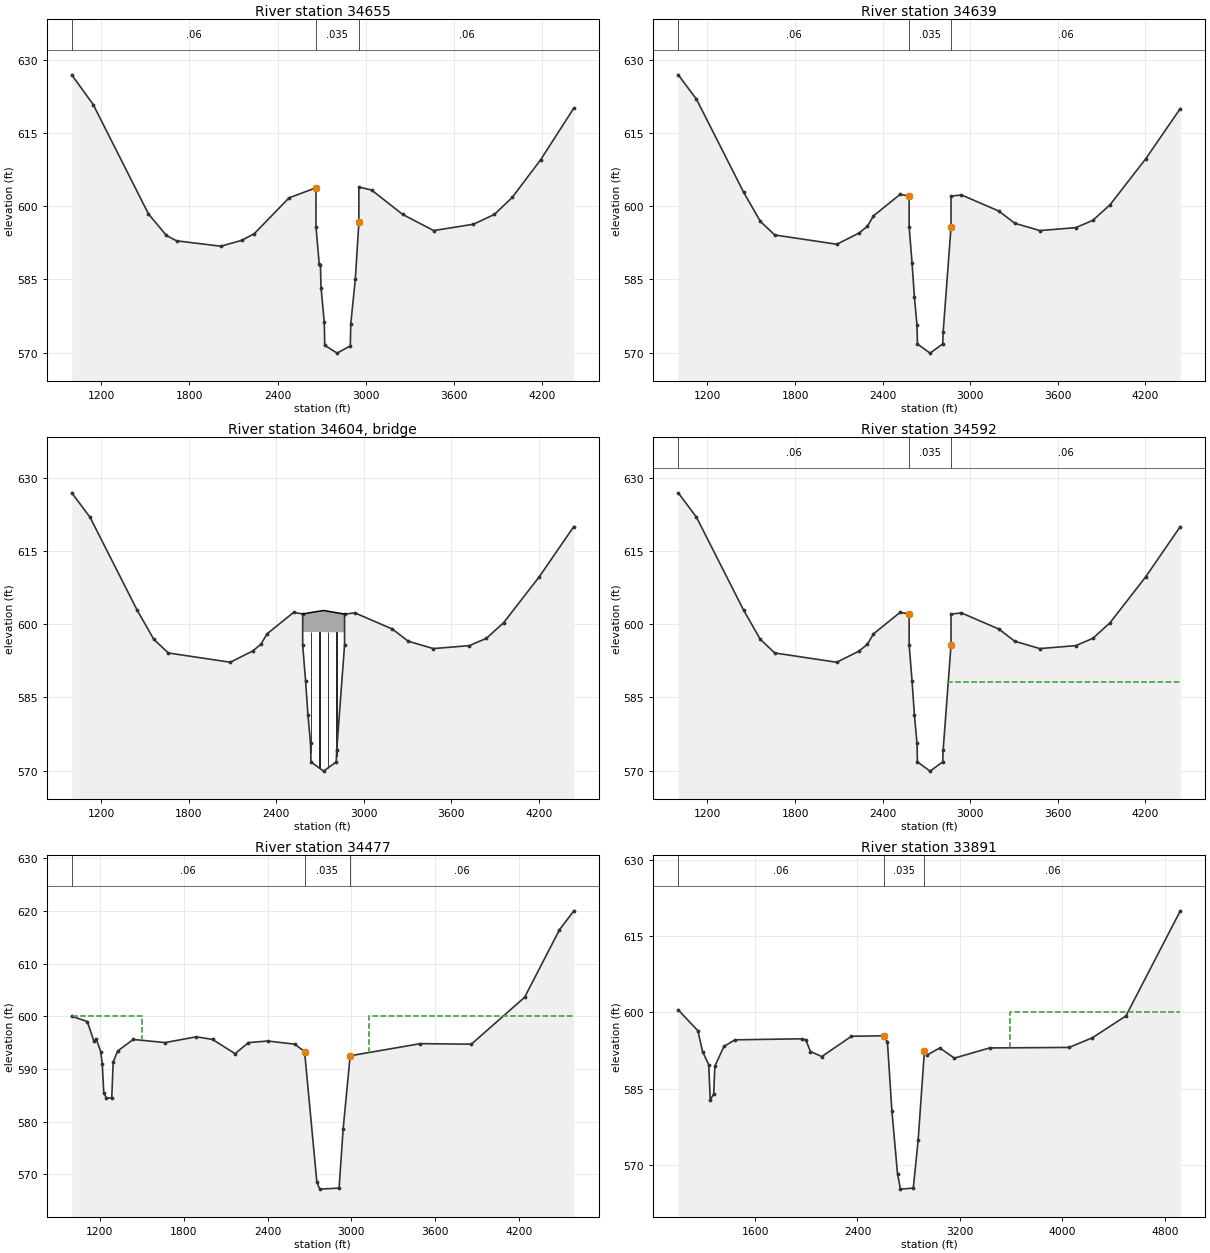
Type RM Length L Ch R = 1 ,34655   ,16,16,16
BEGIN DESCRIPTION:
This cross section corresponds to cross section 34878 of the non-georeferenced CDC model which was the source of this model.
Channel data from 1975 USACE field survey.  Duplication of following bridge cross-section without bridge piers.
Bank stations changed by USACE February 2007.
END DESCRIPTION:
XS GIS Cut Line= 5
      2303204.96      6942894.34  2303207.195843 6942799.2908942
 2303215.5347035 6942403.6342418 2303228.2174235 6941187.5024818
2303241.978059426939478.57568988
#Sta/Elev= 30
    1000   626.9    1146   620.8    1522   598.4    1644     594    1713   592.9
    2014   591.8    2157     593    2243   594.4    2478   601.7 2661.58  603.76
 2661.58   595.8 2683.39   588.2 2691.78     588 2695.97   583.3 2717.95  576.21
 2721.13   571.5    2805   569.9 2895.23  571.38 2898.23  575.89 2929.12     585
 2953.44   596.7 2953.44  603.92    3040   603.3    3252   598.3    3462     595
    3733   596.3    3875   598.3    3997   601.8    4190   609.5    4416   620.1
#Mann= 3 ,0,0
    1000     .06       0 2661.58    .035       0 2953.44     .06       0
#XS Ineff= 2 , 0
       0 2691.78     588 2929.12       0     585
Permanent Ineff=
       F       F
Bank Sta=2661.58,2953.44
XS Rating Curve= 0 ,0
Exp/Cntr=0.5,0.3

Type RM Length L Ch R = 1 ,34639   ,48,48,48
BEGIN DESCRIPTION:
This cross section corresponds to cross section 34846 of the non-georeferenced CDC model which was the source of this model.
Duplication of previous bridge cross-section without bridge piers.
One-foot upstream of Bryant-Irvin Road.
Bank stations changed by USACE February 2007.
END DESCRIPTION:
XS GIS Cut Line= 4
2303223.945786546942827.34139884     2303240.198     6941261.185
     2303244.842      6940894.282303256.640458846939388.50133359
#Sta/Elev= 30
    1000   626.9    1125   621.9    1449   602.8    1562   596.9    1661   594.1
    2086   592.2    2239   594.5    2296   595.9    2337     598    2519   602.4
 2581.58   602.1 2581.58   595.8 2601.71   588.3 2617.65   581.4 2635.44 575.578
 2638.44  571.78    2725   569.9 2811.56 571.785 2814.56 574.199 2868.41   595.7
 2868.41  602.06    2940   602.3    3196     599    3305   596.5    3477     595
    3723   595.6    3840   597.1    3958   600.3    4202   609.7    4439     620
#Mann= 3 ,0,0
    1000     .06       0 2581.58    .035       0 2868.41     .06       0
Bank Sta=2581.58,2868.41
XS Rating Curve= 0 ,0
Exp/Cntr=0.5,0.3

Type RM Length L Ch R = 3 ,34604   ,,,
BEGIN DESCRIPTION:
Bryant-Irvin Road - north bound
Downstream bridge: bridge data from 1975 survey.  Minimum low chord elev. 598.3.  Bridge width 30 feet.
Channel data from 1975 USACE field survey.
END DESCRIPTION:
Node Name=Bryant-Irvin Roa
Bridge Culvert--1,0,-1,-1, 0
Deck Dist Width WeirC Skew NumUp NumDn MinLoCord MaxHiCord MaxSubmerge Is_Ogee
4,25,2.6,0, 11, 11, , , 0.95, 0, ,,,
 2581.58 2635.44 2638.44 2694.14 2697.14    2725 2752.85 2755.85 2811.56 2814.56
    2869
   602.1 602.363 602.378 602.649 602.664   602.8 602.656 602.641 602.353 602.338
  602.06
  598.41 598.391  598.39 598.371  598.37  598.36 598.352 598.351 598.336 598.335
  598.32
 2581.58 2635.44 2638.44 2694.14 2697.14    2725 2752.85 2755.85 2811.56 2814.56
    2869
   602.1 602.363 602.378 602.649 602.664   602.8 602.656 602.641 602.353 602.338
  602.06
  598.41 598.391  598.39 598.371  598.37  598.36 598.352 598.351 598.336 598.335
  598.32
Pier Skew, UpSta & Num, DnSta & Num=  ,2636.94, 2 ,2636.94, 2 , 0 , 0 , 0 ,,
       3       3
     560     600
       3       3
     560     600
Pier Skew, UpSta & Num, DnSta & Num=  ,2695.64, 2 ,2695.64, 2 , 0 , 0 , 0 ,,
       3       3
     560     600
       3       3
     560     600
Pier Skew, UpSta & Num, DnSta & Num=  ,2754.35, 2 ,2754.35, 2 , 0 , 0 , 0 ,,
       3       3
     560     600
       3       3
     560     600
Pier Skew, UpSta & Num, DnSta & Num=  ,2813.06, 2 ,2813.06, 2 , 0 , 0 , 0 ,,
       3       3
     560     600
       3       3
     560     600
BR Coef= 1 , 0 , 0 ,1.05, 0 ,,,0.8,-1,0.5,1,
WSPro=,,,, 1 ,,,, 0 ,,,, 0 ,,,,-1 ,-1 ,-1 , 0 , 0 , 0 , 0 , 0
BC Design=,, 0 ,, 0 ,,,,,,
BC HTab HWMax=626.9
BC Use User HTab Curves=0
BC User HTab FreeFlow(D)= 0

Type RM Length L Ch R = 1 ,34592   ,114,114,114
BEGIN DESCRIPTION:
This cross section corresponds to cross section 34814 of the non-georeferenced CDC model which was the source of this model.
Bridge skewed 33 degrees - bridge area is duplication of
following bridge cross-section without bridge piers.
Channel data from 1975 USACE field survey.
Bank stations changed by USACE February 2007.
END DESCRIPTION:
XS GIS Cut Line= 4
 2303261.09176746942844.41489762 2303269.6729479 6942437.2607985
 2303282.3556679 6941221.12903852303296.974443446939405.63030242
#Sta/Elev= 30
    1000   626.9    1125   621.9    1449   602.8    1562   596.9    1661   594.1
    2086   592.2    2239   594.5    2296   595.9    2337     598    2519   602.4
 2581.58   602.1 2581.58   595.8 2601.71   588.3 2617.65   581.4 2635.44 575.578
 2638.44  571.78    2725   569.9 2811.56 571.785 2814.56 574.199 2868.41   595.7
 2868.41  602.06    2940   602.3    3196     599    3305   596.5    3477     595
    3723   595.6    3840   597.1    3958   600.3    4202   609.7    4439     620
#Mann= 3 ,0,0
    1000     .06       0 2581.58    .035       0 2868.41     .06       0
#XS Ineff= 2 , 0
       0 2601.71   588.3 2849.12       0   588.1
Permanent Ineff=
       F       F
Bank Sta=2581.58,2868.41
XS Rating Curve= 0 ,0
Exp/Cntr=0.5,0.3

Type RM Length L Ch R = 1 ,34477   ,587,587,721
BEGIN DESCRIPTION:
This cross section corresponds to cross section 34699 of the non-georeferenced CDC model which was the source of this model.
116 feet downstream of Bryant-Irvin Road.
Effective flow limit in ROB established by USACE October 2006.
Channel data from 1975 USACE field survey.
END DESCRIPTION:
XS GIS Cut Line= 4
   2303356.44713   6942980.68893   2303366.63116   6942497.48386
   2303379.31388    6941281.3521   2303394.54515   6939389.78797
#Sta/Elev= 30
    1000     600    1111     599    1158   595.3    1176   595.6    1207   593.3
    1218     591    1229   585.4    1248   584.5    1286   584.5    1296   591.3
    1328   593.4    1440   595.6    1667     595    1891   596.1    2007   595.6
    2168   592.9    2264     595    2403   595.3    2595   594.7    2665   593.3
    2753   568.5    2774   567.2    2912   567.4    2941   578.6    2991   592.5
    3493   594.8    3858   594.7    4239   603.6    4488   616.4    4591     620
#Mann= 3 ,0,0
    1000     .06       0    2665    .035       0    2991     .06       0
#XS Ineff= 4 ,-1
    1000    1500     600    3125    4591     600    1500    2665   593.3
    2991    3125   592.5
Permanent Ineff=
       F       F       F       F
Bank Sta=2665,2991
XS Rating Curve= 0 ,0
Exp/Cntr=0.3,0.1

Type RM Length L Ch R = 1 ,33891   ,533,533,427
BEGIN DESCRIPTION:
This cross section corresponds to cross section 34116 of the non-georeferenced CDC model which was the source of this model.
Effective flow limit in ROB established by USACE October 2006.
Drainage channel in LOB removed from conveyance.
Channel data from 1975 USACE field survey.
END DESCRIPTION:
XS GIS Cut Line= 4
   2304047.70198   6943190.78004   2303819.00493   6941714.72295
   2303989.44914   6941065.44013   2303497.05511    6939378.6561
#Sta/Elev= 30
    1000   600.5    1153   596.4    1190   592.3    1238   589.7    1250   582.8
    1277   583.9    1286   589.4    1357   593.3    1443   594.6    1966   594.8
    1996   594.6    2033   592.3    2121   591.3    2353   595.3    2604   595.4
    2634   594.2    2669   580.6    2713   568.2    2736   565.2    2836   565.4
    2874   574.8    2923   592.4    2944   591.6    3043     593    3157     591
    3433     593    4053   593.1    4235     595    4497   599.3    4922     620
#Mann= 3 ,0,0
    1000     .06       0    2604    .035       0    2923     .06       0
#XS Ineff= 3 ,-1
    3590    4922     600    1000    2604   595.4    2923    3590   592.4
Permanent Ineff=
       F       F       F
#Block Obstruct= 2 , 0
            1357   593.3
Bank Sta=2604,2923
XS Rating Curve= 0 ,0
Exp/Cntr=0.3,0.1

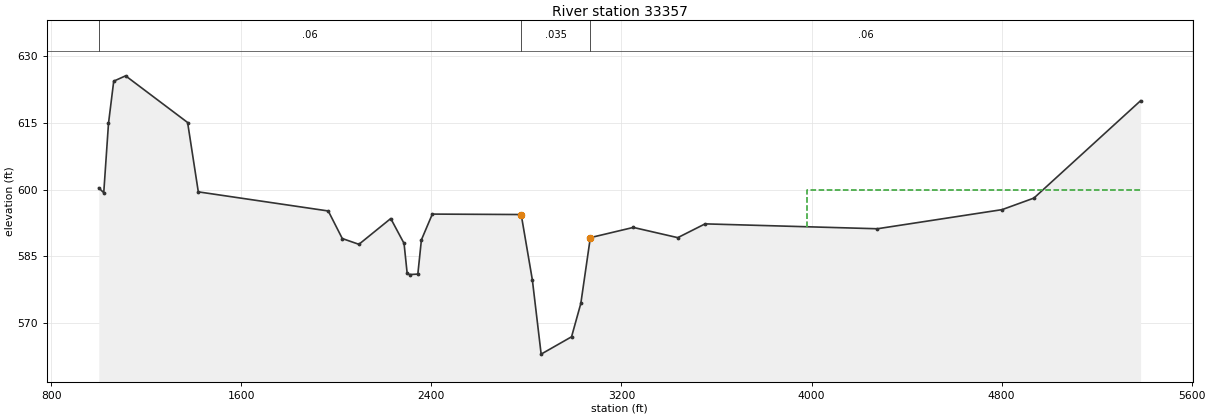
Type RM Length L Ch R = 1 ,33357   ,643,643,618
BEGIN DESCRIPTION:
This cross section corresponds to cross section 33577 of the non-georeferenced CDC model which was the source of this model.
Effective flow limit in ROB established by USACE October 2006.
Drainage channel in LOB removed from conveyance.
Channel data from 1975 USACE field survey.
END DESCRIPTION:
XS GIS Cut Line= 4
    2304766.1779   6943468.66597   2304411.44896   6941883.67997
   2304394.57005   6941000.22012   2303641.18015   6939280.79114
#Sta/Elev= 30
    1000   600.4    1021   599.3    1041   614.9    1063   624.4    1113   625.6
    1374   615.1    1419   599.5    1966   595.2    2025     589    2095   587.7
    2229   593.5    2285   587.9    2298   581.2    2308   580.9    2343     581
    2358   588.7    2404   594.5    2778   594.4    2825   579.7    2862     563
    2990   566.9    3029   574.4    3069   589.2    3250   591.5    3437   589.2
    3552   592.3    4277   591.2    4802   595.5    4936   598.1    5385     620
#Mann= 3 ,0,0
    1000     .06       0    2778    .035       0    3069     .06       0
#XS Ineff= 3 ,-1
    3980    5385     600    1000    2778   594.4    3069    3980   589.2
Permanent Ineff=
       F       F       F
#Block Obstruct= 2 , 0
            2404   594.5
Bank Sta=2778,3069
XS Rating Curve= 0 ,0
Exp/Cntr=0.3,0.1