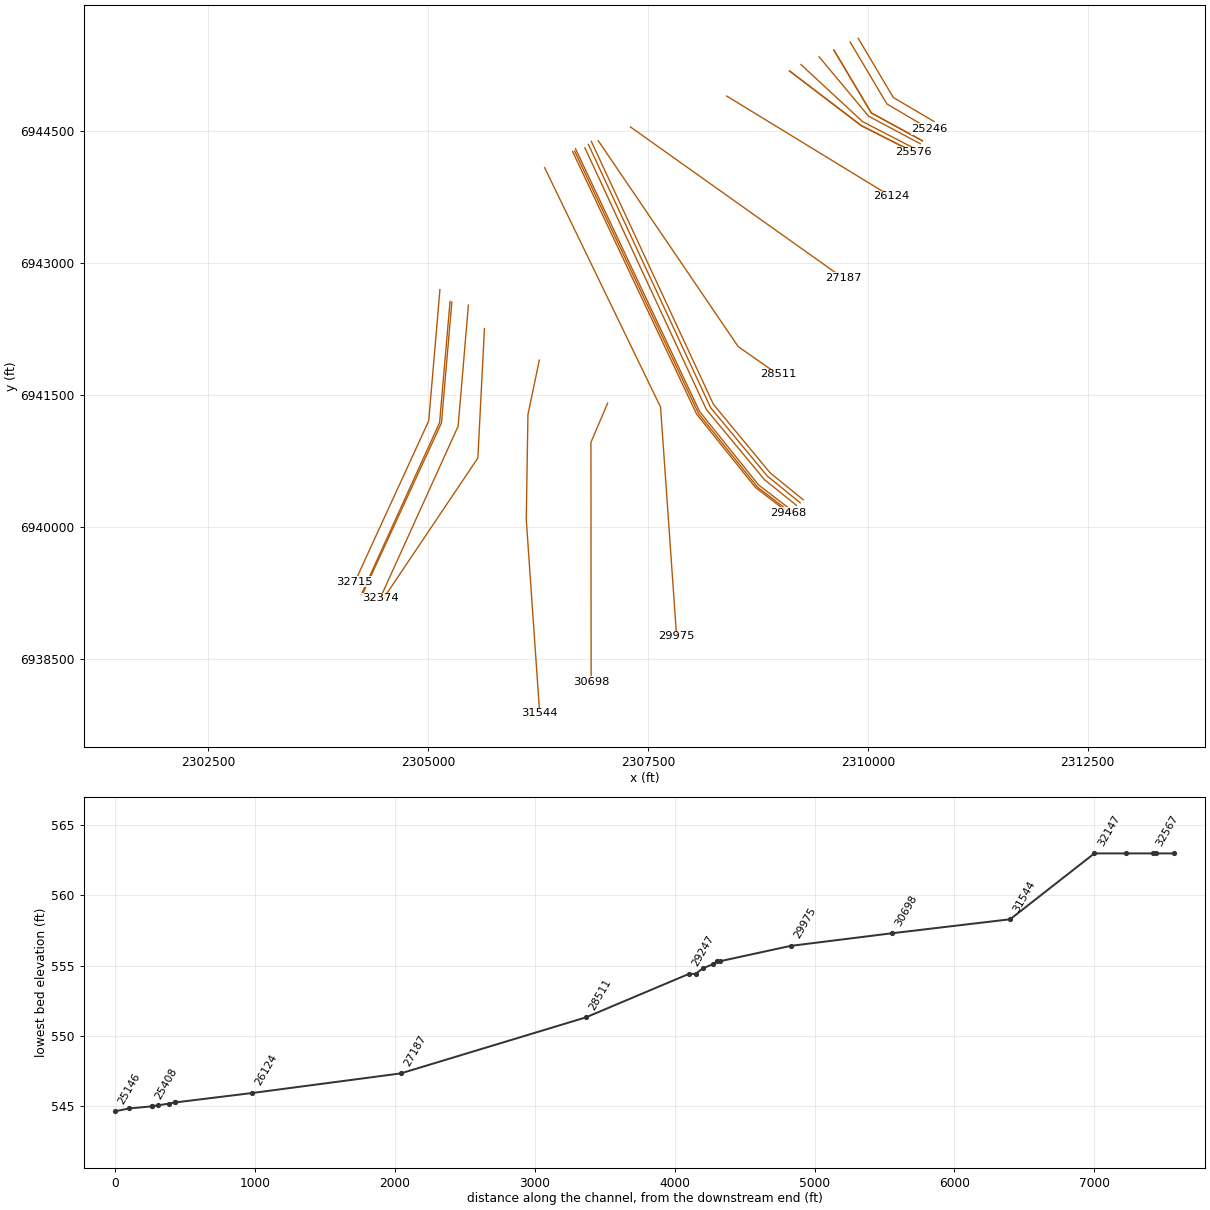
HEC-RAS study CDC_Consolidated_Model.prj: Upper Trinity CDC Consolidated Model

--- CDC_Consolidated_Model.g03 (geometry) --- (continued)

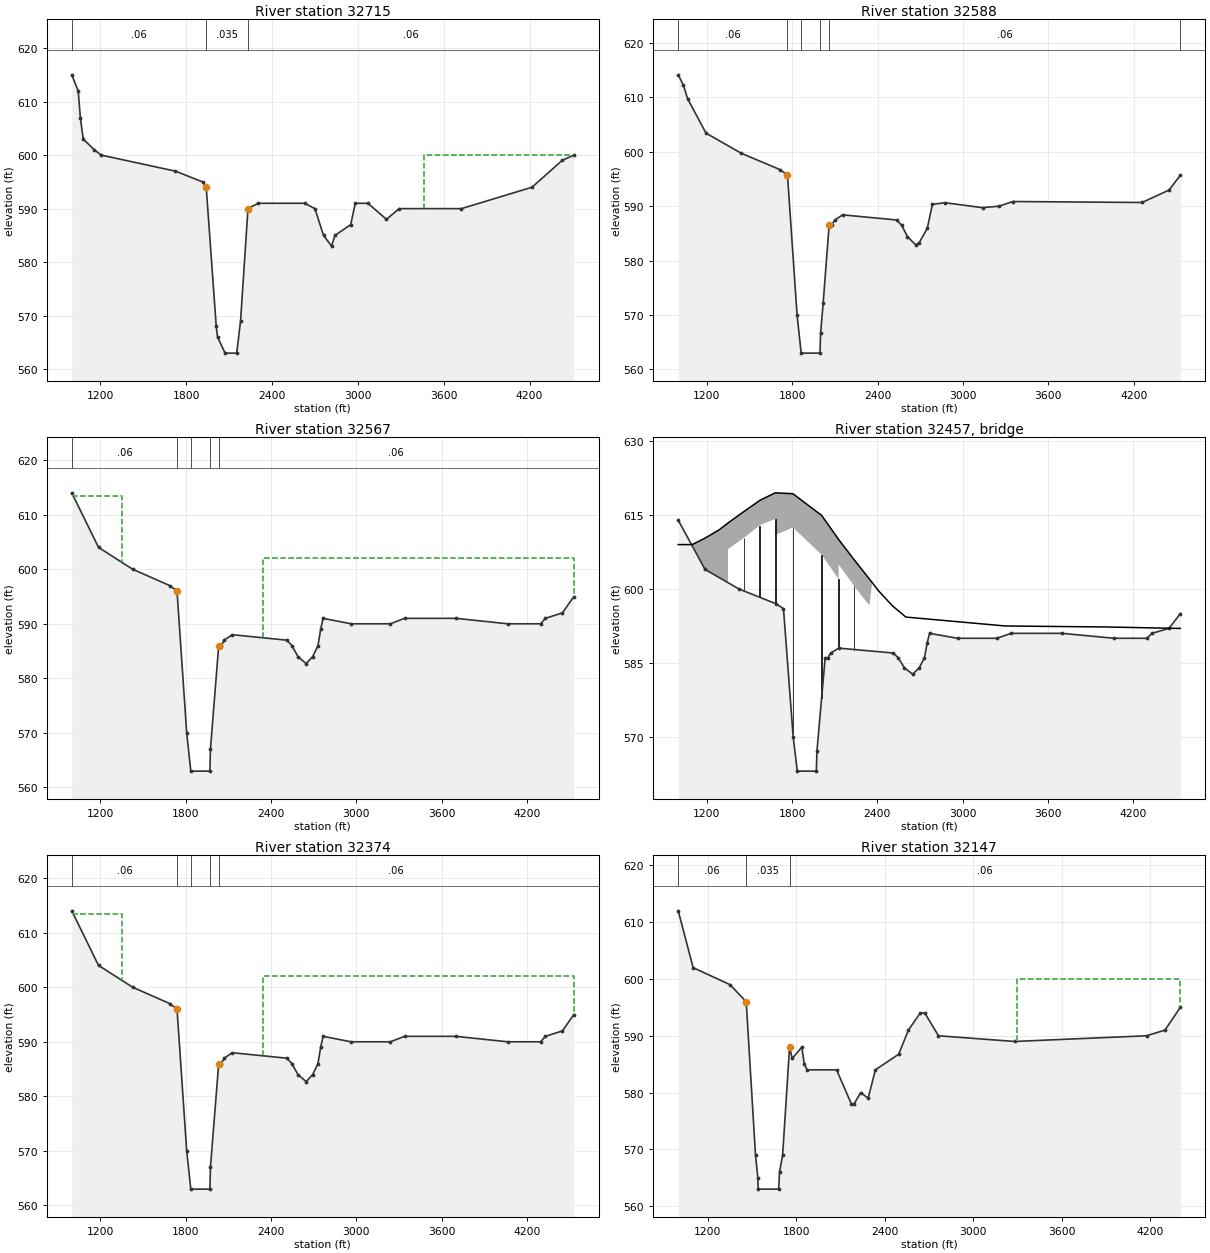
Type RM Length L Ch R = 1 ,32715   ,126,126,126
BEGIN DESCRIPTION:
This cross section corresponds to cross section 32940 of the non-georeferenced CDC model which was the source of this model.
Cross-section generated from SH 121 Southwest Tollway project study using new topo.  Replaces original cross-section.Effective flow limit in ROB established by USACE October 2006.
----------------------------------------------
CDC FW111809-01 SH121/SOUTHWEST PARKWAY
CROSS-SECTION 32602 - 32940
UPSTREAM END.
---------------------------------------------------------------------
END DESCRIPTION:
XS GIS Cut Line= 3
   2305136.54888   6942700.42111   2305009.22991    6941209.1531
 2304169.8036398 6939379.1891681
#Sta/Elev= 30
    1000     615    1045     612    1060     607    1080     603    1157     601
    1206     600    1725     597    1914     595    1940     594    2010     568
    2019     566    2072     563    2153     563    2180     569    2232     590
    2303     591    2628     591    2700     590    2760     585    2816     583
    2840     585    2950     587    2982     591    3070     591    3200     588
    3289     590    3724     590    4218     594    4428     599    4510     600
#Mann= 3 ,0,0
    1000     .06       0    1940    .035       0    2232     .06       0
#XS Ineff= 3 ,-1
    3460    4510     600    1000    1940     594    2232    3460     590
Permanent Ineff=
       F       F       F
Bank Sta=1940,2232
XS Rating Curve= 0 ,0
Exp/Cntr=0.3,0.1

Type RM Length L Ch R = 1 ,32588   ,21,21,21
BEGIN DESCRIPTION:
This cross section corresponds to cross section 32814 of the non-georeferenced CDC model which was the source of this model.
Interpolated cross-section by USACE 12/1/07.
Paved side slopes of concrete block, natural bottom.
END DESCRIPTION:
XS GIS Cut Line= 3
2305251.616347856942566.71575549       2305132.9      6941189.36
      2304244.23      6939237.33
#Sta/Elev= 30
    1000  614.14 1036.74   612.2 1065.31  609.78 1194.96  603.43 1443.85  599.71
 1714.51  596.73  1767.4  595.73 1834.92  570.01 1863.71     563 1995.93     563
 2000.08  566.62 2017.92  572.13 2060.26  586.55 2078.04  586.55 2098.79  587.41
 2154.12  588.41 2533.51  587.47 2569.07  586.53 2610.57   584.4 2667.87  582.91
 2692.71   583.3 2749.87  585.94 2785.44  590.33 2872.49  590.64 3137.81  589.73
 3252.76     590 3351.56  590.86 4258.68  590.68 4448.22  592.97 4527.26  595.68
#Mann= 6 ,-1,0
    1000     .06       0  1767.4    .018       0 1863.71    .035       0
 1995.93    .018       0 2060.26     .06       0 4527.26     .06       0
Bank Sta=1767.4,2060.26
XS Rating Curve= 0 ,0
Exp/Cntr=0.5,0.3

Type RM Length L Ch R = 1 ,32567   ,193,193,193
BEGIN DESCRIPTION:
This cross section corresponds to cross section 32794 of the non-georeferenced CDC model which was the source of this model.
Upstream bounding bridge cross-section.
Copy of cross-section 32602 by USACE 12/1/07.  Paved side slopes of concrete block - no change of cross-section template.
Revised Existing Cross Section 32602
USACE relocated 32611 here Dec2006.
END DESCRIPTION:
XS GIS Cut Line= 3
2305271.851324616942559.61834532      2305154.01      6941186.11
      2304253.61      6939232.14
#Sta/Elev= 30
    1000     614    1188     604    1428     600    1689     597    1740     596
    1808     570    1837     563    1971     563    1975     567    2033     586
    2051     586    2072     587    2128     588    2512     587    2548     586
    2590     584    2648   582.7    2694     584    2731     586    2750     589
    2767     591    2964     590    3240     590    3340     591    3700     591
    4065     590    4296     590    4330     591    4450     592    4530     595
#Mann= 5 ,-1,0
    1000     .06       0    1740    .018       0    1837    .035       0
    1971    .018       0    2033     .06       0
#XS Ineff= 2 , 0
       0    1350  613.43    2344       0  602.04
Permanent Ineff=
       F       F
Bank Sta=1740,2033
XS Rating Curve= 0 ,0
Exp/Cntr=0.5,0.3

Type RM Length L Ch R = 3 ,32457   ,,,
BEGIN DESCRIPTION:
SH 121/Southwest Parkway
Data from bridge plans.  Concrete block on river side slopes.
END DESCRIPTION:
Node Name=SH 121/SW Parkwa
Bridge Culvert--1,0,-1,-1, 0
Deck Dist Width WeirC Skew NumUp NumDn MinLoCord MaxHiCord MaxSubmerge Is_Ogee
0.5,167,2.6,0, 22, 22, , , 0.95, 0, 0,0,,
    1000    1005    1098    1192    1287    1350    1462    1575    1682 1682.01
    1806    2008    2128 2128.01    2236    2344    2410    2505    2600    3300
    4000    4530
  609.04  609.04  609.04  610.41  612.03  613.43  615.76  618.05  619.56  619.56
  619.38  614.98  610.06  610.06  605.99  602.04  599.59  596.62  594.31   592.5
   592.3     592
                                           608.1  610.43     613  614.23     611
   612.5     607     602     605  600.66  596.67
    1000    1005    1098    1192    1287    1350    1462    1575    1682 1682.01
    1806    2008    2128 2128.01    2236    2344    2410    2505    2600    3300
    4000    4530
  609.04  609.04  609.04  610.41  612.03  613.43  615.76  618.05  619.56  619.56
  619.38  614.98  610.06  610.06  605.99  602.04  599.59  596.62  594.31   592.5
   592.3     592
                                           608.1  610.43     613  614.23     611
   612.5     607     602     605  600.66  596.67
Pier Skew, UpSta & Num, DnSta & Num=  ,1462, 2 ,1462, 2 , 0 , 0 , 0 ,,
       5       5
     580     620
       5       5
     580     620
Pier Skew, UpSta & Num, DnSta & Num=  ,1570, 2 ,1570, 2 , 0 , 0 , 0 ,,
       5       5
     580     620
      15      15
     580     620
Pier Skew, UpSta & Num, DnSta & Num=  ,1682, 2 ,1682, 2 , 0 , 0 , 0 ,,
       5       5
     580     620
       5       5
     580     620
Pier Skew, UpSta & Num, DnSta & Num=  ,1806, 2 ,1806, 2 , 0 , 0 , 0 ,,
       5       5
     580     620
       5       5
     580     620
Pier Skew, UpSta & Num, DnSta & Num=  ,2008, 2 ,2008, 2 , 0 , 0 , 0 ,,
       5       5
     580     620
       5       5
     580     620
Pier Skew, UpSta & Num, DnSta & Num=  ,2128, 2 ,2128, 2 , 0 , 0 , 0 ,,
       5       5
     580     620
       5       5
     580     620
Pier Skew, UpSta & Num, DnSta & Num=  ,2236, 2 ,2236, 2 , 0 , 0 , 0 ,,
       5       5
     580     620
       5       5
     580     620
BR Coef=-1 , 0 , 0 ,, 0 ,,,0.8,-1,,0,
WSPro=,,,, 1 ,,,, 0 ,,,, 0 ,,,,-1 ,-1 ,-1 , 0 , 0 , 0 , 0 , 0
BC Design=,, 0 ,, 0 ,,,,,,
BC Use User HTab Curves=0
BC User HTab FreeFlow(D)= 0

Type RM Length L Ch R = 1 ,32374   ,227,227,227
BEGIN DESCRIPTION:
This cross section corresponds to cross section 32602 of the non-georeferenced CDC model which was the source of this model.
Downstream bridge bounding cross-section.
Paved side slopes of concrete block - no change of cross-section template.
Revised Existing Cross Section 32602
USACE relocated 32611 here Dec2006.
------------------------------------------------------
CDC FW111809-01 SH121/SOUTHWEST PARKWAY
CROSS-SECTION 32602 - 32940
DOWNSTREAM END
------------------------------------------------
END DESCRIPTION:
XS GIS Cut Line= 3
2305460.240985066942525.59415373       2305343.7      6941149.03
      2304456.55      6939192.23
#Sta/Elev= 30
    1000     614    1188     604    1428     600    1689     597    1740     596
    1808     570    1837     563    1971     563    1975     567    2033     586
    2051     586    2072     587    2128     588    2512     587    2548     586
    2590     584    2648   582.7    2694     584    2731     586    2750     589
    2767     591    2964     590    3240     590    3340     591    3700     591
    4065     590    4296     590    4330     591    4450     592    4530     595
#Mann= 5 ,-1,0
    1000     .06       0    1740    .018       0    1837    .035       0
    1971    .018       0    2033     .06       0
#XS Ineff= 2 , 0
       0    1350  613.43    2344       0  602.04
Permanent Ineff=
       F       F
Bank Sta=1740,2033
XS Rating Curve= 0 ,0
Exp/Cntr=0.5,0.3

Type RM Length L Ch R = 1 ,32147   ,602,602,541
BEGIN DESCRIPTION:
This cross section corresponds to cross section 32371 of the non-georeferenced CDC model which was the source of this model.
Cross-section generated from SH 121 Southwest Tollway project study using newly topo.  Replaces original cross-section.
Effective flow limit in ROB established by USACE October 2006.
END DESCRIPTION:
XS GIS Cut Line= 3
2305642.604083846942258.56714084   2305567.67204    6940787.4689
      2304490.23      6939183.81
#Sta/Elev= 30
    1000     612    1101     602    1351     599    1461     596    1524     569
    1540     565    1542     563    1681     563    1687     566    1708     569
    1755     588    1773     586    1838     588    1855     585    1875     584
    2074     584    2174     578    2192     578    2238     580    2288     579
    2337     584    2495  586.75    2561     591    2641     594    2672     594
    2765     590    3281     589    4176     590    4301     591    4405     595
#Mann= 3 ,0,0
    1000     .06       0    1461    .035       0    1755     .06       0
#XS Ineff= 3 ,-1
    3298    4405     600    1000    1461     596    1755    3298     588
Permanent Ineff=
       F       F       F
Bank Sta=1461,1755
XS Rating Curve= 0 ,0
Exp/Cntr=0.3,0.1

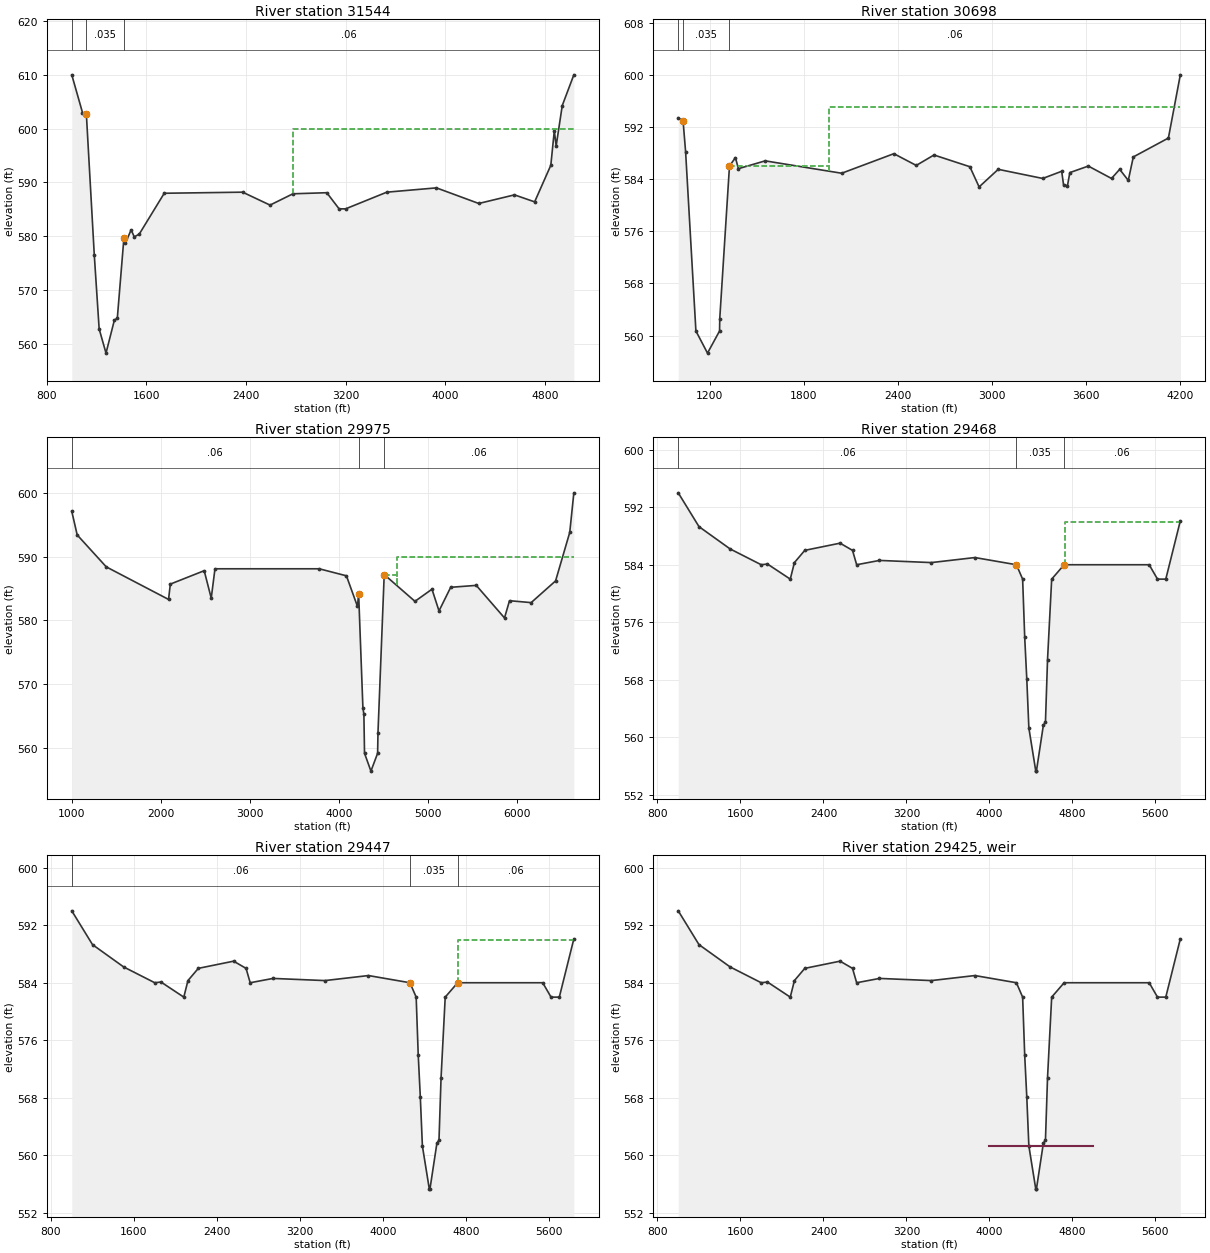
Type RM Length L Ch R = 1 ,31544   ,846,846,775
BEGIN DESCRIPTION:
This cross section corresponds to cross section 31770 of the non-georeferenced CDC model which was the source of this model.
Effective flow limit in ROB established by USACE October 2006.
Channel data from 1975 USACE field survey.
END DESCRIPTION:
XS GIS Cut Line= 4
   2306266.49216   6941900.40795   2306137.03212   6941282.05092
   2306117.89895   6940089.65009   2306270.41505   6937885.00916
#Sta/Elev= 30
    1000     610    1086     603    1117   602.8    1181   576.5    1220   562.8
 1275.08   558.3    1342   564.4    1366   564.8    1419   579.7    1430   578.7
    1477   581.2    1502   579.9    1542   580.4    1743     588    2373   588.2
    2593   585.8    2777   587.9    3049   588.1    3148   585.1    3200   585.1
    3531   588.2    3930     589    4270   586.1    4557   587.7    4719   586.4
    4849   593.2    4877   599.6    4892   596.8    4941   604.3    5034     610
#Mann= 3 ,0,0
    1000     .06       0    1117    .035       0    1419     .06       0
#XS Ineff= 3 ,-1
    1000    1117   602.8    2775    5034     600    1419    2775   579.7
Permanent Ineff=
       F       F       F
Bank Sta=1117,1419
XS Rating Curve= 0 ,0
Exp/Cntr=0.3,0.1

Type RM Length L Ch R = 1 ,30698   ,724,724,840
BEGIN DESCRIPTION:
This cross section corresponds to cross section 30913 of the non-georeferenced CDC model which was the source of this model.
Effective flow limit in ROB established by USACE October 2006.
Channel data from 1975 USACE field survey.
END DESCRIPTION:
XS GIS Cut Line= 3
   2307042.71207     6941410.571   2306852.94899   6940965.73889
   2306855.10713   6938245.54912
#Sta/Elev= 30
    1000   593.4    1031   592.9    1047   588.2 1112.75   560.7 1186.75   557.3
 1263.75   560.7    1265   562.6    1327     586    1365   587.3    1384   585.6
    1555   586.8    2043   584.9    2376   587.9    2519   586.1    2632   587.7
    2861   585.9    2920   582.8    3042   585.5    3326   584.1    3447   585.2
    3459   583.1    3484     583    3499     585    3617     586    3765   584.1
    3817   585.5    3872   583.8    3904   587.4    4128   590.3    4204     600
#Mann= 3 ,0,0
    1000     .06       0    1031    .035       0    1327     .06       0
#XS Ineff= 3 ,-1
    1965    4204     595    1000    1031   592.9    1327    1965     586
Permanent Ineff=
       F       F       F
Bank Sta=1031,1327
XS Rating Curve= 0 ,0
Exp/Cntr=0.3,0.1

Type RM Length L Ch R = 1 ,29975   ,507,507,812
BEGIN DESCRIPTION:
This cross section corresponds to cross section 30174 of the non-georeferenced CDC model which was the source of this model.
Effective flow limit in ROB established by USACE October 2006.
Channel data from 1975 USACE field survey.
END DESCRIPTION:
XS GIS Cut Line= 3
   2306326.32997   6944087.84911   2307644.36014   6941365.81913
    2307826.3601   6938762.19802
#Sta/Elev= 30
    1000   597.1    1061   593.4    1387   588.4    2086   583.3    2106   585.7
    2486   587.8    2565   583.5    2607   588.1    3777   588.1    4082     587
    4206   582.2    4219   584.2    4267   566.3    4278   565.3 4285.11   559.2
 4357.11   556.4 4432.11   559.2    4436   562.4    4506   587.2    4851     583
    5042   584.9    5121   581.5    5252   585.2    5539   585.5    5856   580.4
    5912   583.1    6155   582.8    6429   586.2    6588   593.8    6634     600
#Mann= 3 ,0,0
    1000     .06       0    4219    .035       0    4506     .06       0
#XS Ineff= 3 ,-1
    4645    6634     590    4506    4645   587.2    1000    4219   584.2
Permanent Ineff=
       F       F       F
Bank Sta=4219,4506
XS Rating Curve= 0 ,0
Exp/Cntr=0.3,0.1

Type RM Length L Ch R = 1 ,29468   ,21,21,21
BEGIN DESCRIPTION:
This cross section corresponds to cross section 29663 of the non-georeferenced CDC model which was the source of this model.
Effective flow limit in ROB established by USACE October 2006.
25 feet upstream of channel dam.
Channel data from 1975 USACE field survey.
END DESCRIPTION:
XS GIS Cut Line= 4
  2306643.936829 6944272.3195512 2308054.4169494 6941285.6073512
 2308724.6117994 6940450.5906412 2309098.2170294 6940164.7906912
#Sta/Elev= 30
    1000     594    1200   589.3    1500   586.2    1800     584    1860   584.1
    2080     582    2120   584.3    2220     586    2560     587    2680     586
    2720     584    2940   584.6    3440   584.3    3860     585    4260     584
    4320     582    4340   573.9    4360   568.1    4380   561.3 4446.79   555.3
 4452.79   555.3    4520   561.7    4540   562.1    4560   570.8    4600     582
    4720     584    5540     584    5620     582    5700     582    5840   590.1
#Mann= 3 ,0,0
    1000     .06       0    4260    .035       0    4720     .06       0
#XS Ineff= 3 ,-1
    4725    5840     590    4720    4725     584    1000    4260     584
Permanent Ineff=
       F       F       F
Bank Sta=4260,4720
XS Rating Curve= 0 ,0
Exp/Cntr=0.3,0.1

Type RM Length L Ch R = 1 ,29447   ,24,24,24
BEGIN DESCRIPTION:
This cross section corresponds to cross section 29638 of the non-georeferenced CDC model which was the source of this model.
One-foot upstream of channel dam.
Cross-section generated from topographic file.
Effective flow limit in ROB established by USACE October 2006.
END DESCRIPTION:
XS GIS Cut Line= 4
   2306667.43493   6944276.10891   2308077.91505   6941289.39671
    2308748.1099      6940454.38   2309121.71513   6940168.58005
#Sta/Elev= 30
    1000     594    1200   589.3    1500   586.2    1800     584    1860   584.1
    2080     582    2120   584.3    2220     586    2560     587    2680     586
    2720     584    2940   584.6    3440   584.3    3860     585    4260     584
    4320     582    4340   573.9    4360   568.1    4380   561.3 4446.79   555.3
 4452.79   555.3    4520   561.7    4540   562.1    4560   570.8    4600     582
    4720     584    5540     584    5620     582    5700     582    5840   590.1
#Mann= 3 ,0,0
    1000     .06       0    4260    .035       0    4720     .06       0
#XS Ineff= 3 ,-1
    4725    5840     590    4720    4725     584    1000    4260     584
Permanent Ineff=
       F       F       F
Bank Sta=4260,4720
XS Rating Curve= 0 ,0
Exp/Cntr=0.3,0.1

Type RM Length L Ch R = 5 ,29425   ,,,
BEGIN DESCRIPTION:
channel dam
crest elevation 561.3
END DESCRIPTION:
Node Name=channel dam
IW Pilot Flow=0
#Inline Weir SE= 2
    4000   561.3    5000   561.3
IW Dist,WD,Coef,Skew,MaxSub,Min_El,Is_Ogee,SpillHt,DesHd
1,5,3,0,0.95,, 0 ,,,2,2,
Inline Weir Flap Gates= 0
IW Outlet Rating Curve= 0 ,False,,

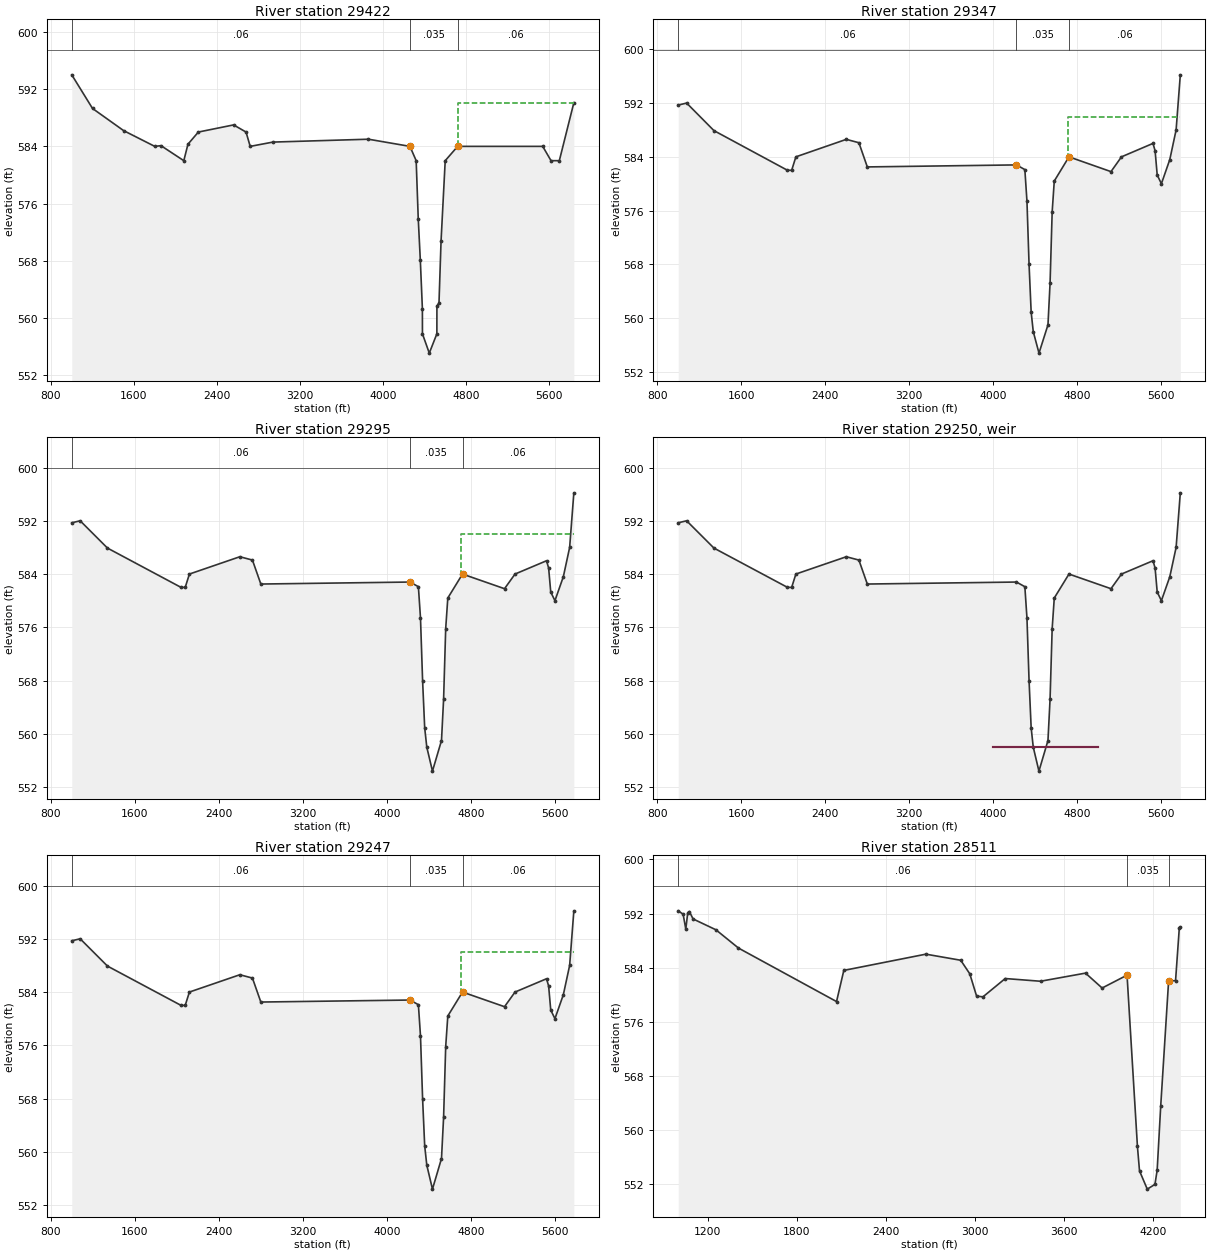
Type RM Length L Ch R = 1 ,29422   ,76,76,76
BEGIN DESCRIPTION:
This cross section corresponds to cross section 29613 of the non-georeferenced CDC model which was the source of this model.
Effective flow limit in ROB established by USACE October 2006.
21.5 feet downstream of channel dam.
Channel data from 1975 USACE field survey.
END DESCRIPTION:
XS GIS Cut Line= 4
  2306677.273096 6944302.6838326 2308087.7532162 6941315.9716326
 2308757.9480662 6940480.9549226 2309131.5532962 6940195.1549726
#Sta/Elev= 30
    1000     594    1200   589.3    1500   586.2    1800     584    1860   584.1
    2080     582    2120   584.3    2220     586    2560     587    2680     586
    2720     584    2940   584.6    3860     585    4260     584    4320     582
    4340   573.9    4360   568.1    4380   561.3 4380.51   557.8 4446.51   555.1
 4519.51   557.8    4520   561.7    4540   562.1    4560   570.8    4600     582
    4720     584    5540     584    5620     582    5700     582    5840   590.1
#Mann= 3 ,0,0
    1000     .06       0    4260    .035       0    4720     .06       0
#XS Ineff= 3 ,-1
    4725    5840     590    4720    4725     584    1000    4260     584
Permanent Ineff=
       F       F       F
Bank Sta=4260,4720
XS Rating Curve= 0 ,0
Exp/Cntr=0.3,0.1

Type RM Length L Ch R = 1 ,29347   ,51,51,51
BEGIN DESCRIPTION:
This cross section corresponds to cross section 29535 of the non-georeferenced CDC model which was the source of this model.
Effective flow limit in ROB established by USACE October 2006.
Cross-section generated from topographic file.  50 feet upstream of channel dam.
Channel data from 1975 USACE field survey.
END DESCRIPTION:
XS GIS Cut Line= 4
2306784.007642616944313.01996774      2308165.41       6941337.6
      2308825.17       6940541.52309188.082737116940249.83446717
#Sta/Elev= 30
    1000   591.7    1080     592    1340   587.9    2040     582    2080     582
    2120     584    2600   586.6    2720   586.1    2800   582.5    4220   582.8
    4300   582.1    4320   577.4    4340     568    4360   560.9    4380     558
 4434.58   554.8    4520     559    4540   565.2    4560   575.8    4580   580.4
    4720     584    5120   581.8    5220     584    5520     586    5540   584.9
    5560   581.3    5600     580    5680   583.6    5740     588    5780   596.2
#Mann= 3 ,0,0
    1000     .06       0    4220    .035       0    4720     .06       0
#XS Ineff= 2 ,-1
    1000    4220   582.8    4710    5780     590
Permanent Ineff=
       F       F
Bank Sta=4220,4720
XS Rating Curve= 0 ,0
Exp/Cntr=0.3,0.1

Type RM Length L Ch R = 1 ,29295   ,48,48,48
BEGIN DESCRIPTION:
This cross section corresponds to cross section 29485 of the non-georeferenced CDC model which was the source of this model.
One-foot upstream of channel dam.  Cross-section generated from topographic file.  Effective flow limit in ROB established by USACE October 2006.
END DESCRIPTION:
XS GIS Cut Line= 4
     2306824.119   6944350.91585   2308212.45513   6941360.99597
    2308856.7501     6940582.885   2309231.92914   6940278.03915
#Sta/Elev= 30
    1000   591.7    1080     592    1340   587.9    2040     582    2080     582
    2120     584    2600   586.6    2720   586.1    2800   582.5    4220   582.8
    4300   582.1    4320   577.4    4340     568    4360   560.9    4380     558
 4434.01   554.4    4520     559    4540   565.2    4560   575.8    4580   580.4
    4720     584    5120   581.8    5220     584    5520     586    5540   584.9
    5560   581.3    5600     580    5680   583.6    5740     588    5780   596.2
#Mann= 3 ,0,0
    1000     .06       0    4220    .035       0    4720     .06       0
#XS Ineff= 2 ,-1
    1000    4220   582.8    4710    5780     590
Permanent Ineff=
       F       F
Bank Sta=4220,4720
XS Rating Curve= 0 ,0
Exp/Cntr=0.3,0.1

Type RM Length L Ch R = 5 ,29250   ,,,
BEGIN DESCRIPTION:
channel dam
crest elevation 558.0
END DESCRIPTION:
Node Name=channel dam
IW Pilot Flow=0
#Inline Weir SE= 2
    4000     558    5000     558
IW Dist,WD,Coef,Skew,MaxSub,Min_El,Is_Ogee,SpillHt,DesHd
1,5,3,0,0.95,, 0 ,,,2,2,
Inline Weir Flap Gates= 0
IW Outlet Rating Curve= 0 ,False,,

Type RM Length L Ch R = 1 ,29247   ,736,736,877
BEGIN DESCRIPTION:
This cross section corresponds to cross section 29435 of the non-georeferenced CDC model which was the source of this model.
Effective flow limit in ROB established by USACE October 2006.
Approx. 250 feet upstream of left bank of Overton Woods diversion channel, 46.5 feet downstream of channel
dam.
Channel data from 1975 USACE field survey.
END DESCRIPTION:
XS GIS Cut Line= 4
  2306857.262319 6944386.2579837 2308245.5984494 6941396.3381037
 2308889.8934194 6940618.2271337 2309265.0724594 6940313.3812837
#Sta/Elev= 30
    1000   591.7    1080     592    1340   587.9    2040     582    2080     582
    2120     584    2600   586.6    2720   586.1    2800   582.5    4220   582.8
    4300   582.1    4320   577.4    4340     568    4360   560.9    4380     558
 4434.01   554.4    4520     559    4540   565.2    4560   575.8    4580   580.4
    4720     584    5120   581.8    5220     584    5520     586    5540   584.9
    5560   581.3    5600     580    5680   583.6    5740     588    5780   596.2
#Mann= 3 ,0,0
    1000     .06       0    4220    .035       0    4720     .06       0
#XS Ineff= 2 ,-1
    1000    4220   582.8    4710    5780     590
Permanent Ineff=
       F       F
Bank Sta=4220,4720
XS Rating Curve= 0 ,0
Exp/Cntr=0.3,0.1

Type RM Length L Ch R = 1 ,28511   ,1324,1324,1309
BEGIN DESCRIPTION:
This cross section corresponds to cross section 28689 of the non-georeferenced CDC model which was the source of this model.
Approx. 450 feet downstream of right bank of Overton
Woods diversion channel.  Effective flow limit set at Overton Levee in ROB.
Channel data from 1975 USACE field survey.
END DESCRIPTION:
XS GIS Cut Line= 3
   2306935.33006   6944394.67494   2308526.63003   6942053.40994
   2308979.91784   6941736.65795
#Sta/Elev= 30
    1000   592.4    1033   591.9    1051   589.7    1064   592.1    1075   592.3
    1100   591.2    1254   589.6    1406   586.9    2067     579    2116   583.6
    2669     586    2904   585.1    2965   583.1    3011   579.8    3054   579.7
    3204   582.4    3442     582    3745   583.2    3857     581    4025   582.9
    4095   557.6    4109     554 4161.26   551.3    4213     552    4228   554.1
    4252   563.6    4305     582    4352   582.1    4377   589.8    4384     590
#Mann= 3 ,0,0
    1000     .06       0    4025    .035       0    4305     .06       0
#XS Ineff= 2 , 0
       0    4025   582.9    4305       0     582
Permanent Ineff=
       F       F
Bank Sta=4025,4305
XS Rating Curve= 0 ,0
Exp/Cntr=0.3,0.1

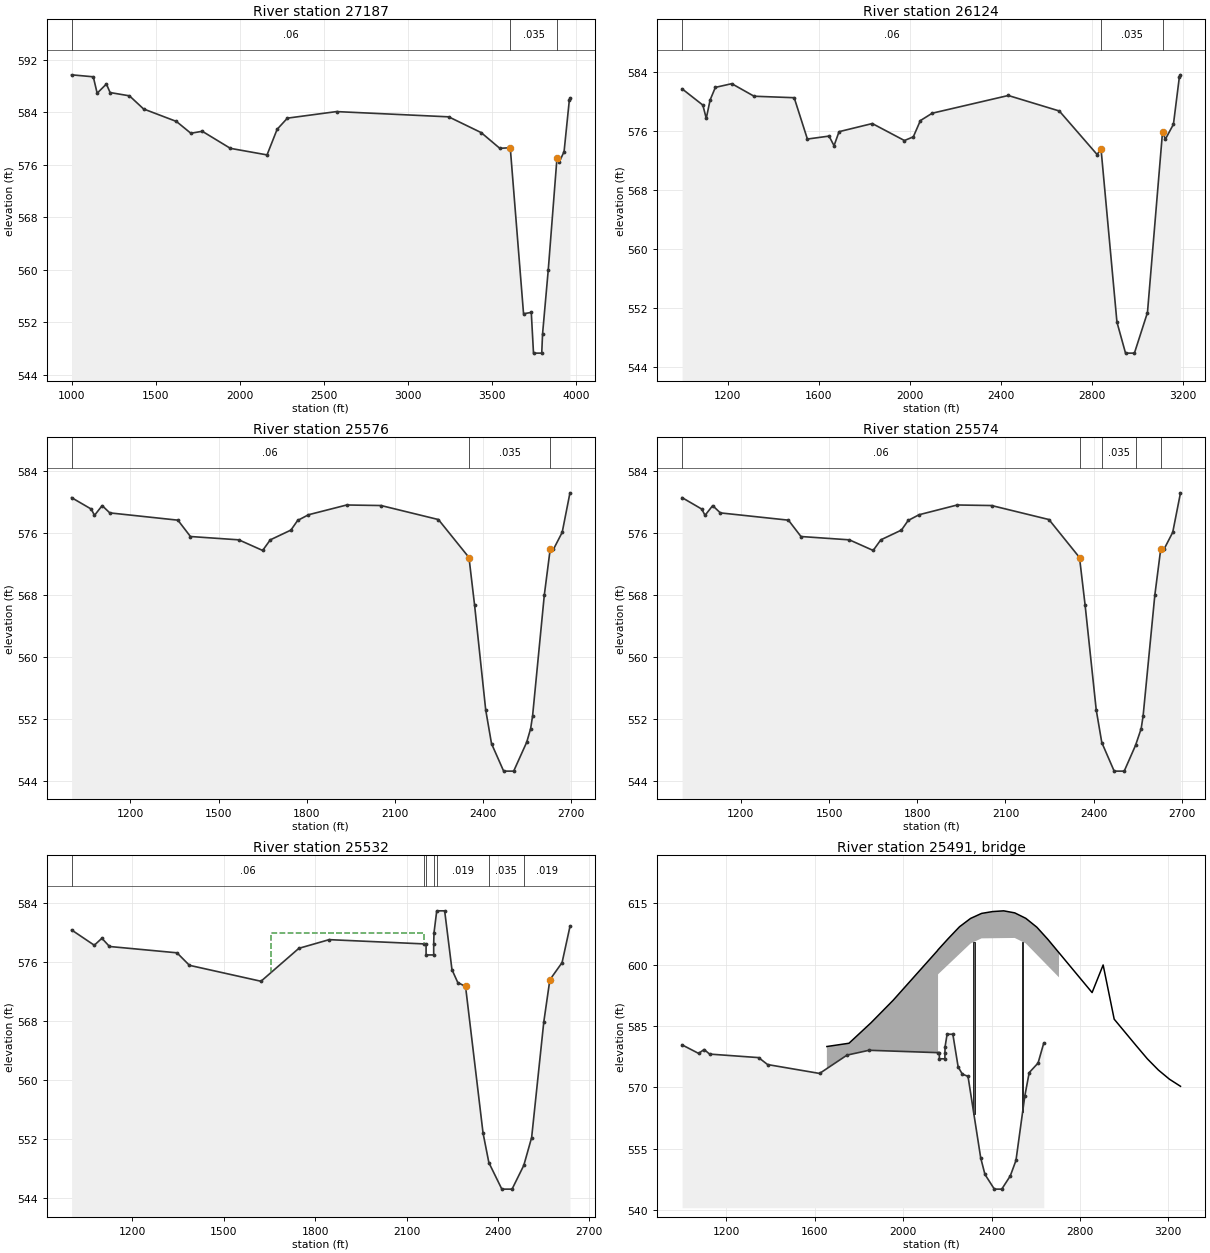
Type RM Length L Ch R = 1 ,27187   ,1063,1063,1083
BEGIN DESCRIPTION:
This cross section corresponds to cross section 27364 of the non-georeferenced CDC model which was the source of this model.
Effective flow limit set at Overton Levee in ROB.
Channel data from 1975 USACE field survey.
END DESCRIPTION:
XS GIS Cut Line= 2
   2307302.02093   6944549.78585   2309717.94687   6942833.62885
#Sta/Elev= 30
    1000   589.7    1129   589.4    1152   586.9    1207   588.3    1229     587
    1344   586.5    1428   584.5    1623   582.6    1709   580.8    1777   581.1
    1944   578.5    2162   577.5    2222   581.4    2283   583.1    2575   584.1
    3242   583.3    3435   580.9    3546   578.5    3608   578.6    3687   553.3
    3733   553.5 3746.19   547.3 3795.19   547.3    3800   550.2    3834     560
    3886   577.1    3899   576.4    3928     578    3959   585.8    3963   586.1
#Mann= 3 ,0,0
    1000     .06       0    3608    .035       0    3886     .06       0
#XS Ineff= 2 , 0
       0    3608   578.6    3886       0   577.1
Permanent Ineff=
       F       F
Bank Sta=3608,3886
XS Rating Curve= 0 ,0
Exp/Cntr=0.3,0.1

Type RM Length L Ch R = 1 ,26124   ,548,548,548
BEGIN DESCRIPTION:
This cross section corresponds to cross section 26300 of the non-georeferenced CDC model which was the source of this model.
Effective flow limit set at Overton Levee in ROB.
Channel data from 1975 USACE field survey.
END DESCRIPTION:
XS GIS Cut Line= 2
   2308395.51809   6944901.52596   2310262.30799   6943760.74314
#Sta/Elev= 30
    1000   581.7    1091   579.5    1106   577.7    1123   580.2    1146   581.9
    1218   582.4    1316   580.7    1492   580.5    1550   574.9    1645   575.3
    1667     574    1689   575.9    1835     577    1976   574.7    2015   575.2
    2046   577.4    2098   578.4    2432   580.8    2656   578.7    2822   572.8
    2839   573.6    2909   550.1 2946.71   545.9 2985.71   545.9    3043   551.4
    3109   575.8    3122   574.9    3157   576.9    3183   583.3    3188   583.6
#Mann= 3 ,0,0
    1000     .06       0    2839    .035       0    3109     .06       0
#XS Ineff= 2 , 0
       0    2839   573.6    3109       0   575.8
Permanent Ineff=
       F       F
Bank Sta=2839,3109
XS Rating Curve= 0 ,0
Exp/Cntr=0.3,0.1

Type RM Length L Ch R = 1 ,25576   ,2,2,2
BEGIN DESCRIPTION:
This cross section corresponds to cross section 25739 of the non-georeferenced CDC model which was the source of this model.
Copy of cross-section 25738.
Interpolated cross-section.
Effective flow limit set at Overton Levee in ROB.
---------------------------------------------------------------------
CDC FW110209-01 STONEGATE/CLEAR FORK MAIN STREET BRIDGE
CROSS-SECTION 25577 - 25739
UPSTREAM END
---------------------------------------------------------------------
END DESCRIPTION:
XS GIS Cut Line= 3
2309110.272845756945185.53241212      2309923.17      6944565.19
2310523.454409876944261.50273915
#Sta/Elev= 30
    1000  580.54 1066.89  579.06 1077.92  578.25 1103.98  579.51 1129.98  578.57
 1361.65  577.63 1404.29  575.52 1568.94  575.09  1649.9  573.72 1675.89  575.09
 1746.09  576.35 1768.88  577.59 1805.87  578.33 1935.85  579.59 2052.61  579.52
  2247.8  577.71 2351.78  572.81 2370.73   566.7 2408.63  553.14 2428.42  548.78
 2469.71  545.23 2503.83  545.23 2548.19  548.97 2561.48  550.71 2568.11  552.35
 2607.96  567.94 2627.88  573.85 2638.97  573.86 2668.84  576.06 2695.29  581.16
#Mann= 3 ,-1,0
    1000     .06       0 2351.78    .035       0 2627.88     .06       0
#XS Ineff= 2 , 0
       0 2351.78  572.81 2627.88       0  573.85
Permanent Ineff=
       F       F
Bank Sta=2351.78,2627.88
XS Rating Curve= 0 ,0
Exp/Cntr=0.3,0.1

Type RM Length L Ch R = 1 ,25574   ,42,42,42
BEGIN DESCRIPTION:
This cross section corresponds to cross section 25738 of the non-georeferenced CDC model which was the source of this model.
Upstream end of paved side slopes of concrete block.
Interpolated cross-section.
Effective flow limit set at Overton Levee in ROB.
END DESCRIPTION:
XS GIS Cut Line= 3
2309110.891708116945186.57215516     2309925.819     6944566.601
2310524.262564366944262.35663211
#Sta/Elev= 30
    1000  580.54 1066.89  579.06 1077.92  578.25 1103.98  579.51 1129.98  578.57
 1361.65  577.63 1404.29  575.52 1568.94  575.09  1649.9  573.72 1675.89  575.09
 1746.09  576.35 1768.88  577.59 1805.87  578.33 1935.85  579.59 2052.61  579.52
  2247.8  577.71 2351.78  572.81 2370.73   566.7 2408.63  553.14 2427.58  548.92
 2469.71  545.23 2503.83  545.23 2542.36  548.56 2561.48  550.71 2568.11  552.35
 2607.96  567.94 2627.88  573.85 2638.97  573.86 2668.84  576.06 2695.29  581.16
#Mann= 5 ,-1,0
    1000     .06       0 2351.78    .019       0 2427.58    .035       0
 2542.36    .019       0 2627.88     .06       0
#XS Ineff= 2 , 0
       0 2351.78  572.81 2627.88       0  573.85
Permanent Ineff=
       F       F
Bank Sta=2351.78,2627.88
XS Rating Curve= 0 ,0
Exp/Cntr=0.5,0.3

Type RM Length L Ch R = 1 ,25532   ,81,81,81
BEGIN DESCRIPTION:
This cross section corresponds to cross section 25699 of the non-georeferenced CDC model which was the source of this model.
Upstream bounding cross-section of Stonegate.
Interpolated cross-section.
Paved side slopes of concrete block.
Effective flow limit set at Overton Levee in ROB.
END DESCRIPTION:
XS GIS Cut Line= 3
2309239.666768716945259.45987825     2309939.245     6944611.454
2310545.627939216944297.41560301
#Sta/Elev= 30
    1000   580.4 1074.57  578.32 1099.51  579.27 1124.39  578.15 1346.09  577.29
 1386.89  575.59 1621.93  573.42 1746.31   577.9 1845.82  579.08    2158   578.5
    2164   578.5    2164     577    2189     577    2189   578.5    2190     580
    2199     583    2225     583    2249     575    2268  573.25 2293.61  572.71
 2351.04  552.78 2370.19  548.75 2412.76  545.15 2446.29  545.15 2484.85  548.38
 2510.62  552.17  2550.5  567.88 2570.43  573.62 2610.55  575.96 2636.46  580.87
#Mann= 7 ,-1,0
    1000     .06       0    2158    .035       0    2164    .025       0
    2189    .035       0    2199    .019       0 2370.19    .035       0
 2484.85    .019       0
#XS Ineff= 1 ,-1
    1655    2158     580
Permanent Ineff=
       F
Bank Sta=2293.61,2570.43
XS Rating Curve= 0 ,0
Exp/Cntr=0.5,0.3

Type RM Length L Ch R = 3 ,25491   ,,,
BEGIN DESCRIPTION:
Stonegate/Clear Fork Main Street
Data from bridge plans.  Concrete block on river side slopes.
END DESCRIPTION:
Node Name=Stonegate/Clear
Bridge Culvert--1,0,-1,-1, 0
Deck Dist Width WeirC Skew NumUp NumDn MinLoCord MaxHiCord MaxSubmerge Is_Ogee
0.99,80,2.6,0, 30, 30, , , 0.98, 0, 0,0,,
    1655    1755    1855    1955    2055    2155    2158    2158    2205    2255
    2305    2355    2405    2455    2505    2555    2605    2655    2705    2755
    2805    2855    2905    2955    3005    3055    3105    3155    3205    3255
     580   580.8  585.82  591.31  597.36  603.41  603.64  603.64  606.43  609.26
   611.3  612.53  612.98  613.16  612.66  611.33  609.16  606.18  602.93  599.68
  596.43  593.18  599.93  586.68  583.43  580.18  576.99  574.25  572.01  570.28
                                                          597.64  600.05  602.61
  605.17  606.43  606.46   606.5  606.53   605.2  602.44  599.68  596.91
    1564    1664    1764    1864    1964    2064    2067    2067    2114    2164
    2214    2264    2314    2364    2414    2464    2514    2564    2614    2664
    2714    2764    2814    2864    2914    2964    3014    3064    3114    3164
     580   580.8  585.82  591.31  597.36  603.41  603.64  603.64  606.43  609.26
   611.3  612.53  612.98  613.16  612.66  611.33  609.16  606.18  602.93  599.68
  596.43  593.18  599.93  586.68  583.43  580.18  576.99  574.25  572.01  570.28
                                                          597.64  600.05  602.61
  605.17  606.43  606.46   606.5  606.53   605.2  602.44  599.68  596.91
Pier Skew, UpSta & Num, DnSta & Num=  ,2320.35, 2 ,2229.35, 2 , 0 , 0 , 0 ,,
     5.5     5.5
  545.11  606.54
     5.5     5.5
  545.11  606.54
Pier Skew, UpSta & Num, DnSta & Num=  ,2540.35, 2 ,2449.35, 2 , 0 , 0 , 0 ,,
     5.5     5.5
  545.11  606.54
     5.5     5.5
  545.11  606.54
BR Coef=-1 , 0 , 0 ,, 0 ,,,0.8,-1,,0,
WSPro=,,,, 1 ,,,, 0 ,,,, 0 ,,,,-1 ,-1 ,-1 , 0 , 0 , 0 , 0 , 0
BC Design=,, 0 ,, 0 ,,,,,,
BC Use User HTab Curves=0
BC User HTab FreeFlow(D)= 0

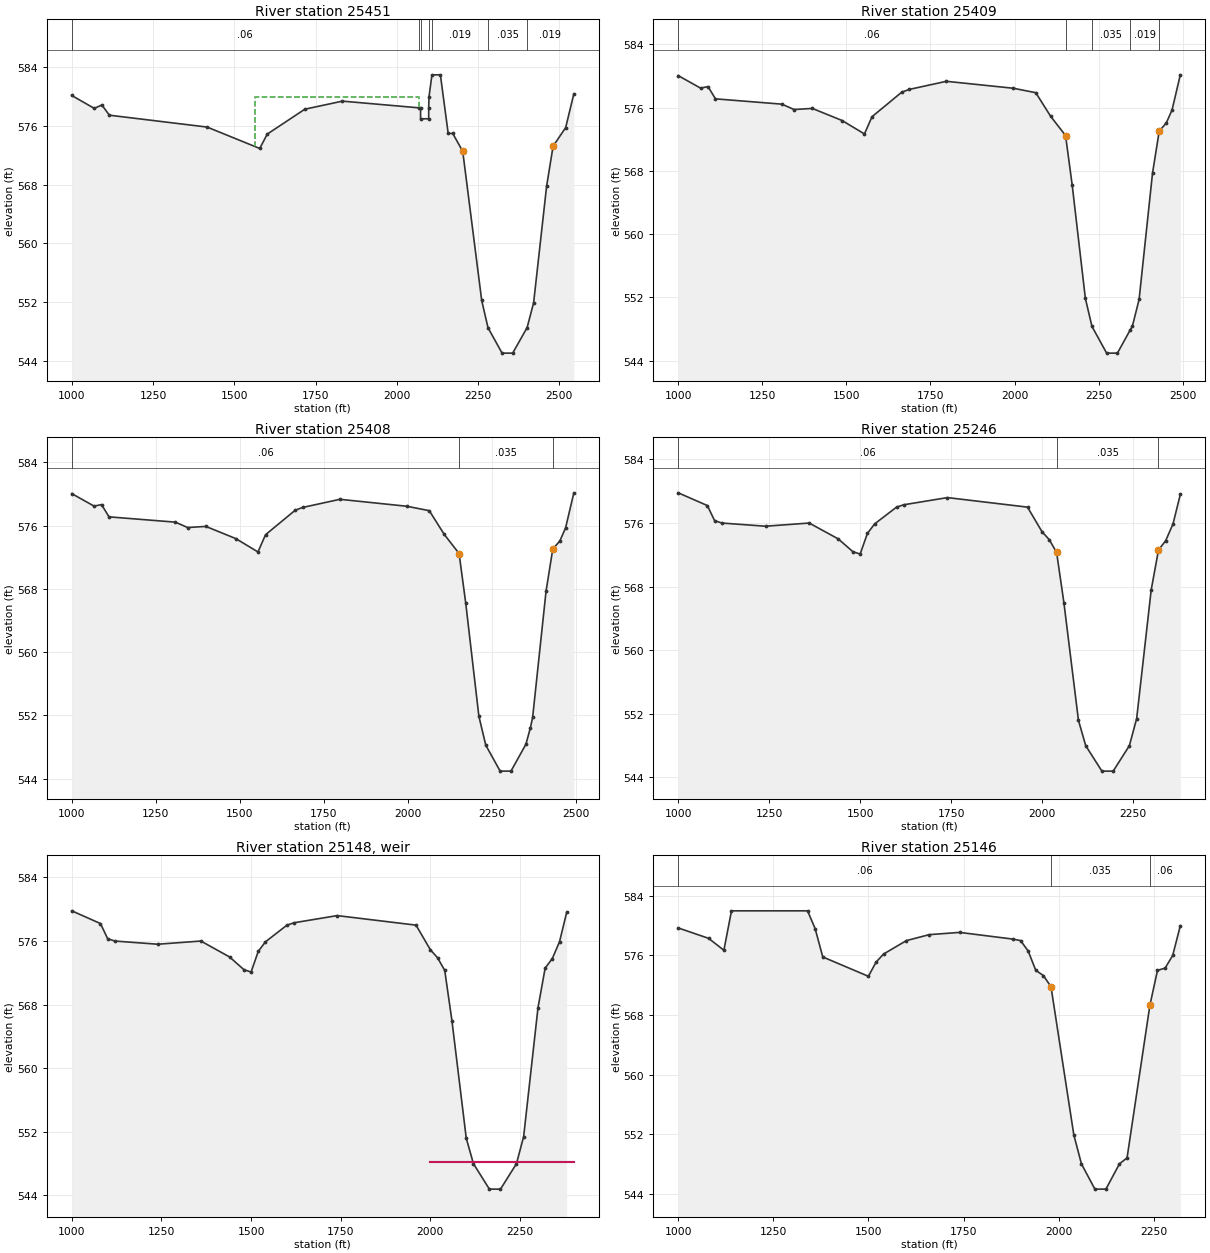
Type RM Length L Ch R = 1 ,25451   ,42,42,42
BEGIN DESCRIPTION:
This cross section corresponds to cross section 25618 of the non-georeferenced CDC model which was the source of this model.
Downstream bounding cross-section of Stonegate.
Interpolated cross-section.
Paved side slopes of concrete block.
Effective flow limit set at Overton Levee in ROB.
END DESCRIPTION:
XS GIS Cut Line= 3
2309445.706353996945347.86257521     2310009.001     6944671.909
2310595.700238596944359.59845725
#Sta/Elev= 30
    1000  580.18 1069.33  578.42 1092.52  578.89 1115.65  577.49 1416.32  575.87
 1578.23  572.95 1601.35  574.91    1717  578.31 1832.64  579.41    2067   578.5
    2073   578.5    2073     577    2098     577    2098   578.5    2099     580
    2108     583    2134     583    2158     575    2172     575 2202.71  572.56
 2261.06  552.21 2280.52  548.48 2323.77  545.02 2356.39  545.02 2400.83  548.51
 2420.79  551.89 2460.71  567.78 2480.67  573.25 2519.48  575.81 2544.54  580.41
#Mann= 7 ,-1,0
    1000     .06       0    2067    .035       0    2073    .025       0
    2098    .035       0    2108    .019       0 2280.52    .035       0
 2400.83    .019       0
#XS Ineff= 1 ,-1
    1564    2067     580
Permanent Ineff=
       F
Bank Sta=2202.71,2480.67
XS Rating Curve= 0 ,0
Exp/Cntr=0.5,0.3

Type RM Length L Ch R = 1 ,25409   ,1,1,1
BEGIN DESCRIPTION:
This cross section corresponds to cross section 25578 of the non-georeferenced CDC model which was the source of this model.
Downstream end paved side slopes of concrete block.
Interpolated cross-section.
Effective flow limit set at Overton Levee in ROB.
END DESCRIPTION:
XS GIS Cut Line= 3
2309613.89585912  6945423.224461     2310039.229     6944709.113
 2310620.20372676944392.01525908
#Sta/Elev= 30
    1000  580.06  1066.4  578.48  1088.6  578.67 1110.75  577.12 1308.15  576.45
 1344.48  575.77  1398.7  575.91 1487.29  574.38 1553.75  572.68 1576.22  574.86
  1664.5  577.96 1686.65  578.31  1797.4  579.34 1996.76  578.46  2063.2   577.9
  2107.5  574.91 2151.81  572.48 2171.43  566.25 2210.67  551.89  2230.3  548.33
 2273.93  544.95 2306.05  544.95 2344.67  547.93 2350.51  548.35 2370.49  551.74
 2410.43  567.72  2430.4  573.05 2451.29  574.06 2468.48  575.72 2493.06  580.16
#Mann= 5 ,-1,0
    1000     .06       0 2151.81    .019       0  2230.3    .035       0
 2344.67    .019       0  2430.4     .06       0
#XS Ineff= 2 , 0
       0 2151.81  572.48  2430.4       0  573.05
Permanent Ineff=
       F       F
Bank Sta=2151.81,2430.4
XS Rating Curve= 0 ,0
Exp/Cntr=0.3,0.1

Type RM Length L Ch R = 1 ,25408   ,162,162,162
BEGIN DESCRIPTION:
This cross section corresponds to cross section 25577 of the non-georeferenced CDC model which was the source of this model.
Copy of cross-section 25578.
Interpolated cross-section.
Effective flow limit set at Overton Levee in ROB.
---------------------------------------------------------------------
CDC FW110209-01 STONEGATE/CLEAR FORK MAIN STREET BRIDGE
CROSS-SECTION 25577 - 25739
DOWNSTREAM END.
---------------------------------------------------------------------
END DESCRIPTION:
XS GIS Cut Line= 3
2309614.717974336945423.78682027      2310039.99      6944709.45
2310621.025756466944392.80325632
#Sta/Elev= 30
    1000  580.06  1066.4  578.48  1088.6  578.67 1110.75  577.12 1308.15  576.45
 1344.48  575.77  1398.7  575.91 1487.29  574.38 1553.75  572.68 1576.22  574.86
  1664.5  577.96 1686.65  578.31  1797.4  579.34 1996.76  578.46  2063.2   577.9
  2107.5  574.91 2151.81  572.48 2171.43  566.25 2210.67  551.89 2231.17  548.23
 2273.93  544.95 2306.05  544.95 2350.51  548.35 2363.85  550.43 2370.49  551.74
 2410.43  567.72  2430.4  573.05 2451.29  574.06 2468.48  575.72 2493.06  580.16
#Mann= 3 ,-1,0
    1000     .06       0 2151.81    .035       0  2430.4     .06       0
#XS Ineff= 2 , 0
       0 2151.81  572.48  2430.4       0  573.05
Permanent Ineff=
       F       F
Bank Sta=2151.81,2430.4
XS Rating Curve= 0 ,0
Exp/Cntr=0.3,0.1

Type RM Length L Ch R = 1 ,25246   ,100,100,100
BEGIN DESCRIPTION:
This cross section corresponds to cross section 25421 of the non-georeferenced CDC model which was the source of this model.
50 feet upstream of channel dam.  Effective flow limit set at Overton Levee in ROB.
Channel data from 1975 USACE field survey.
END DESCRIPTION:
XS GIS Cut Line= 3
2309799.271659526945515.25360241   2310217.03807   6944811.30305
 2310700.73612846944526.29905733
#Sta/Elev= 30
    1000   579.8    1080   578.2    1100   576.3    1120     576    1240   575.6
    1360     576    1440     574    1480   572.4    1500   572.1    1520   574.7
    1540   575.9    1600     578    1620   578.3    1740   579.2    1960     578
    2000   574.9    2020   573.9    2040   572.3    2060     566    2100   551.2
    2120     548 2164.47   544.8 2195.47   544.8    2240     548    2260   551.4
    2300   567.6    2320   572.6    2340   573.8    2360   575.9    2380   579.6
#Mann= 3 ,0,0
    1000     .06       0    2040    .035       0    2320     .06       0
#XS Ineff= 2 , 0
       0    2040   572.3    2320       0   572.6
Permanent Ineff=
       F       F
Bank Sta=2040,2320
XS Rating Curve= 0 ,0
Exp/Cntr=0.3,0.1

Type RM Length L Ch R = 5 ,25148   ,,,
BEGIN DESCRIPTION:
channel dam
crest elevation 548.2
END DESCRIPTION:
Node Name=channel dam
IW Pilot Flow=0
#Inline Weir SE= 2
    2000   548.2    2400   548.2
IW Dist,WD,Coef,Skew,MaxSub,Min_El,Is_Ogee,SpillHt,DesHd
47.5,5,3,0,0.95,, 0 ,,,2,2,
Inline Weir Flap Gates= 0
IW Outlet Rating Curve= 0 ,False,,

Type RM Length L Ch R = 1 ,25146   ,860,860,627
BEGIN DESCRIPTION:
This cross section corresponds to cross section 25321 of the non-georeferenced CDC model which was the source of this model.
50 feet downstream of channel dam.  Effective flow limit set at Overton Levee in ROB.
Channel data from 1975 USACE field survey.
END DESCRIPTION:
XS GIS Cut Line= 3
2309890.661496436945557.19963767   2310289.92703   6944884.42298
2310753.163240266944611.47529393
#Sta/Elev= 30
    1000   579.7    1080   578.3    1120   576.7    1140     582    1340     582
    1360   579.6    1380   575.8    1500   573.2    1520   575.1    1540   576.2
    1600     578    1660   578.8    1740   579.1    1880   578.2    1900     578
    1920   576.6    1940     574    1960   573.3    1980   571.8    2040   551.9
    2060     548  2095.4   544.6  2124.4   544.6    2160     548    2180   548.8
    2240   569.3    2260     574    2280   574.3    2300     576    2320     580
#Mann= 3 ,0,0
    1000     .06       0    1980    .035       0    2240     .06       0
#XS Ineff= 2 , 0
       0    1980   571.8    2240       0   569.3
Permanent Ineff=
       F       F
Bank Sta=1980,2240
XS Rating Curve= 0 ,0
Exp/Cntr=0.3,0.1