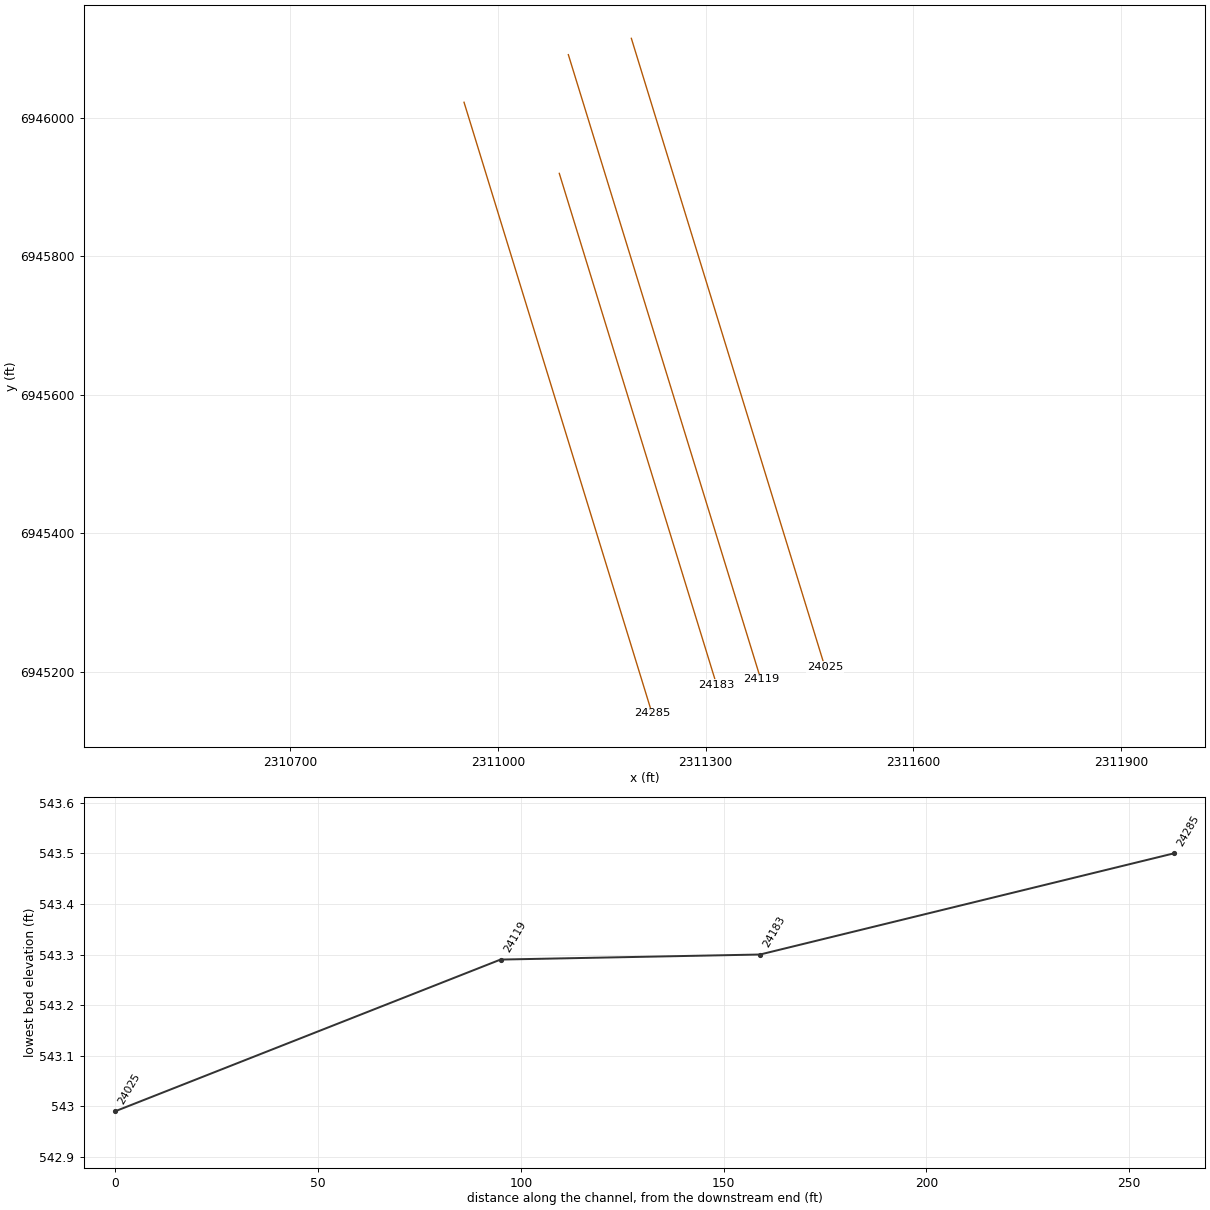
HEC-RAS study CDC_Consolidated_Model.prj: Upper Trinity CDC Consolidated Model

--- CDC_Consolidated_Model.g03 (geometry) --- (continued)

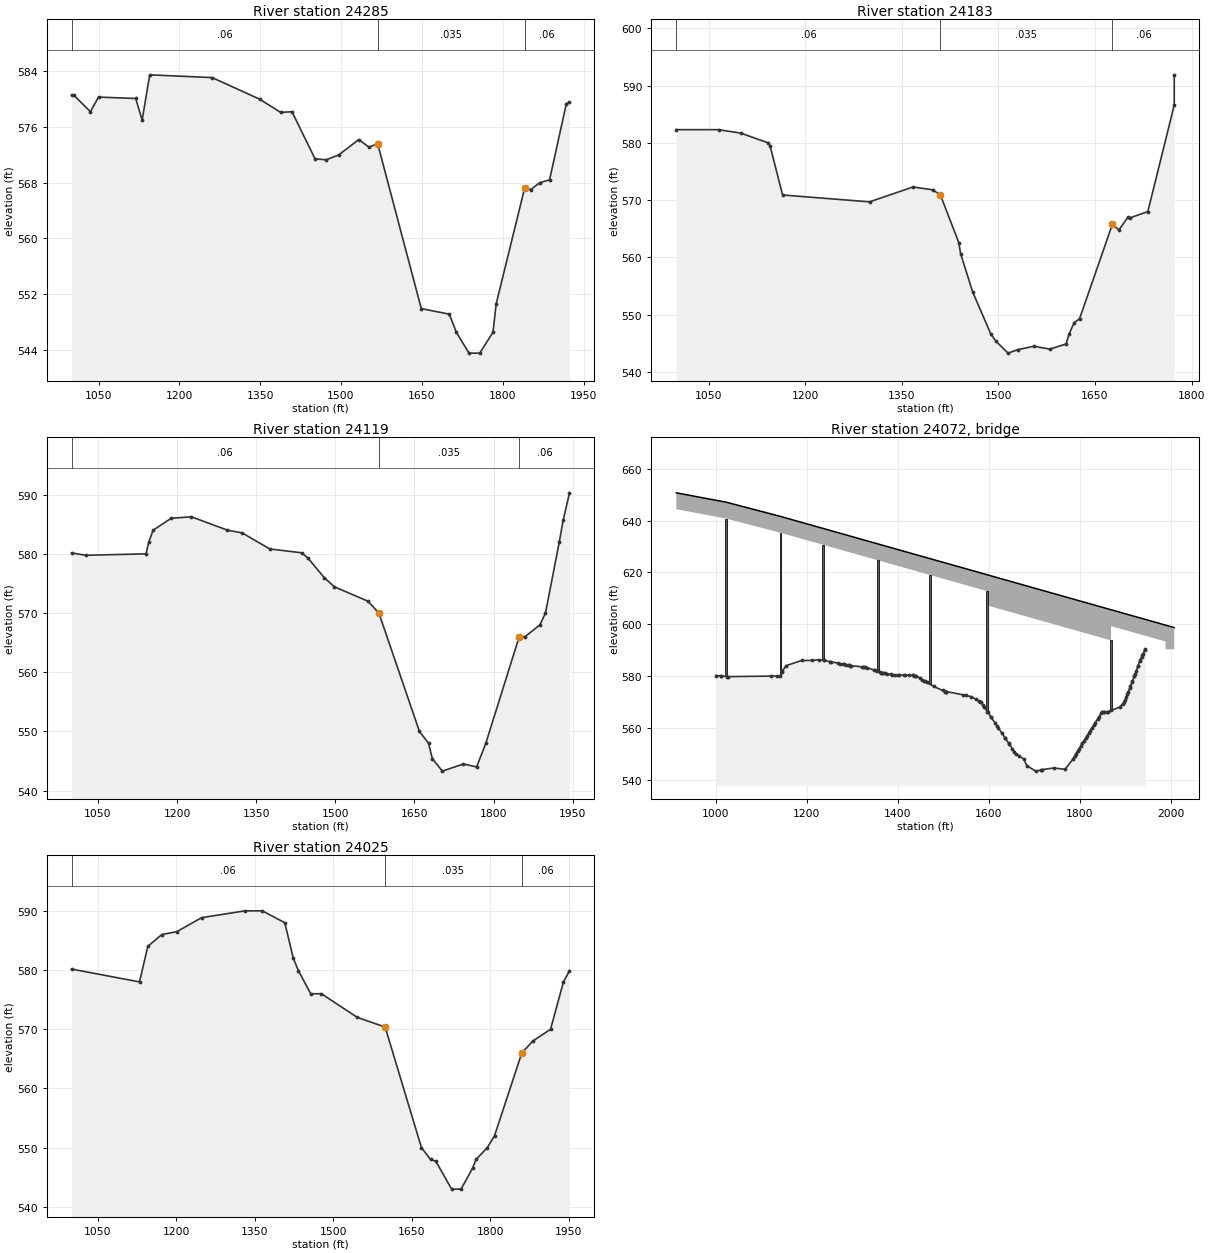
Type RM Length L Ch R = 1 ,24285   ,102,102,102
BEGIN DESCRIPTION:
This cross section corresponds to cross section 24456 of the non-georeferenced CDC model which was the source of this model.
102 feet upstream of Hulen Street.  Effective flow limit
set at Overton Levee in ROB.
Channel data from 1975 USACE field survey.
END DESCRIPTION:
XS GIS Cut Line= 2
   2310950.99788   6946022.53685   2311222.49012   6945139.79616
#Sta/Elev= 30
    1000   580.6    1004   580.6    1035   578.2    1050   580.3    1119   580.1
    1131     577    1145   583.5    1261   583.1    1349     580    1388   578.1
    1409   578.2    1452   571.4    1473   571.3    1496     572    1533   574.2
    1552   573.1    1568   573.6    1649   549.9    1701   549.1    1714   546.5
 1737.51   543.5 1757.51   543.5    1782   546.5    1788   550.6    1841   567.3
    1852     567    1869     568    1887   568.4    1918   579.3    1924   579.6
#Mann= 3 ,0,0
    1000     .06       0    1568    .035       0    1841     .06       0
#XS Ineff= 2 , 0
       0    1568   573.6    1841       0   567.3
Permanent Ineff=
       F       F
Bank Sta=1568,1841
XS Rating Curve= 0 ,0
Exp/Cntr=0.3,0.1

Type RM Length L Ch R = 1 ,24183   ,64,64,64
BEGIN DESCRIPTION:
This cross section corresponds to cross section 24355 of the non-georeferenced CDC model which was the source of this model.
Duplication of previous bridge cross-section without bridge piers.
One-foot upstream of Hulen Street.
Effective flow limit set at Overton Levee in ROB.
Channel data from 1975 USACE field survey.
END DESCRIPTION:
XS GIS Cut Line= 2
2311088.536827946945919.82977455  2311315.773221 6945180.9843092
#Sta/Elev= 30
    1000   582.3  1065.5   582.3    1100   581.7  1142.5     580  1145.5   579.5
    1165   570.9    1300   569.7  1367.5   572.3    1398   571.8    1410   570.9
  1438.5   562.6  1441.5   560.6    1460     554    1488   546.7    1496   545.4
    1515   543.3    1530   543.9    1555   544.5    1580     544    1605   544.9
    1610   546.7  1617.5   548.6    1626   549.3    1677   565.8    1687   564.8
    1701     567    1704   566.9    1732     568    1773   586.6    1773  591.87
#Mann= 3 ,0,0
    1000     .06       0    1410    .035       0    1677     .06       0
#XS Ineff= 2 , 0
       0    1410   570.9    1677       0   565.8
Permanent Ineff=
       F       F
Bank Sta=1410,1677
XS Rating Curve= 0 ,0
Exp/Cntr=0.5,0.3

Type RM Length L Ch R = 1 ,24119   ,95,95,95
BEGIN DESCRIPTION:
This cross section corresponds to cross section 24293 of the non-georeferenced CDC model which was the source of this model.
Upstream Hulen Street.
---------------------------------------------------------------------
CDC FW111809-01 SH121/SOUTHWEST PARKWAY
CROSS-SECTION 24191 - 24293
UPSTREAM END.
---------------------------------------------------------------------
END DESCRIPTION:
XS GIS Cut Line= 4
2311101.615438446946091.33791827      2311104.95      6946080.51
      2311376.13      6945199.942311379.464561566945189.11208173
#Sta/Elev= 30
    1000  580.16 1026.99  579.76  1141.2     580 1146.41     582 1154.68     584
 1188.71     586 1226.98  586.27 1295.54     584 1323.39  583.54 1375.78  580.83
 1436.16  580.18 1448.53  579.25  1478.9     576 1498.37  574.43 1561.93     572
 1582.65     570 1659.54     550  1676.8     548    1684   545.4    1703  543.29
    1743   544.5    1768     544 1785.39     548 1848.73     566 1859.72     566
  1887.9     568  1898.5     570 1924.66     582 1932.01  585.66 1944.04  590.31
#Mann= 3 ,0,0
    1000     .06       0 1582.65    .035       0 1848.73     .06       0
Bank Sta=1582.65,1848.73
XS Rating Curve= 0 ,0
Exp/Cntr=0.5,0.3

Type RM Length L Ch R = 3 ,24072   ,,,
BEGIN DESCRIPTION:
Hulen Street
Data from bridge plans.  Old Hulen Street bridge removed.  Part of SH 121/Southwest Parkway project.
Paved side slopes of concrete block under bridge.
END DESCRIPTION:
Node Name=Hulen Street
Bridge Culvert--1,0,-1,-1, 0
Deck Dist Width WeirC Skew NumUp NumDn MinLoCord MaxHiCord MaxSubmerge Is_Ogee
0.5,94,2.6,0, 13, 13, , , 0.95, 0, 0,0,,
     913    1023    1142    1236    1356    1471    1596    1596    1869    1869
    1989    1989    2008
  650.69  647.06  641.59  636.94  630.99  625.29   619.1   619.1  605.57  605.57
  599.63  599.63  598.68
  644.37  640.74  635.27  630.62  624.67  618.97  612.78  607.27  593.74  599.25
  593.31     520     520
     913    1023    1142    1236    1356    1471    1596    1596    1869    1869
    1989    1989    2008
  650.69  647.06  641.59  636.94  630.99  625.29   619.1   619.1  605.57  605.57
  599.63  599.63  598.68
  644.37 639.326  635.27  630.62  624.67  618.97  612.78  607.27  593.74  599.25
  593.31     520     520
Pier Skew, UpSta & Num, DnSta & Num=  ,1023, 2 ,1023, 2 , 0 , 0 , 0 ,,
       4       4
     520  640.74
       4       4
     520  640.74
Pier Skew, UpSta & Num, DnSta & Num=  ,1142, 2 ,1142, 2 , 0 , 0 , 0 ,,
       4       4
     520  635.27
       4       4
     520  635.27
Pier Skew, UpSta & Num, DnSta & Num=  ,1236, 2 ,1236, 2 , 0 , 0 , 0 ,,
     3.5     3.5
     520  630.62
     3.5     3.5
     520  630.62
Pier Skew, UpSta & Num, DnSta & Num=  ,1356, 2 ,1356, 2 , 0 , 0 , 0 ,,
     3.5     3.5
     520  624.67
     3.5     3.5
     520  624.67
Pier Skew, UpSta & Num, DnSta & Num=  ,1471, 2 ,1471, 2 , 0 , 0 , 0 ,,
     3.5     3.5
     520  618.97
     3.5     3.5
     520  618.97
Pier Skew, UpSta & Num, DnSta & Num=  ,1596, 2 ,1596, 2 , 0 , 0 , 0 ,,
       5       5
     520  612.78
       5       5
     520  612.78
Pier Skew, UpSta & Num, DnSta & Num=  ,1869, 2 ,1869, 2 , 0 , 0 , 0 ,,
       5       5
     520  607.27
       5       5
     520  607.27
BR Coef=-1 , 0 , 0 ,, 0 ,,,0.8,-1,,0,
WSPro=,,,, 1 ,,,, 0 ,,,, 0 ,,,,-1 ,-1 ,-1 , 0 , 0 , 0 , 0 , 0
BR U #Sta/Elev= 147
    1000  580.16 1011.18  580.01 1012.21     580 1025.37  579.78 1026.99  579.76
 1120.43     580 1134.63     580  1141.2     580  1145.4  581.63 1146.41     582
 1154.68     584 1188.71     586 1211.32     586 1226.98  586.27 1236.93  586.04
 1238.51     586 1251.75  585.52 1253.25  585.46 1268.91  584.93 1272.75   584.8
 1279.22   584.6 1281.81  584.52 1287.04  584.34 1293.14   584.1 1293.84  584.08
 1295.54     584 1298.18     584 1321.32  583.51 1323.39  583.54 1326.38  583.38
 1328.19  583.34 1332.32   583.2 1348.06  582.31 1350.52   582.2 1353.62     582
 1360.61  581.42 1362.84  581.29 1364.68  581.18 1366.32  581.11 1369.03  581.07
  1370.9  580.98 1375.78  580.83 1384.09  580.63  1387.6  580.54  1394.8  580.43
 1399.81   580.4 1402.39  580.34 1412.87  580.36 1416.13   580.3 1423.64  580.33
 1433.62  580.25 1434.54  580.24 1436.16  580.18 1438.27     580 1439.63     580
 1448.53  579.25 1453.96  578.62 1457.14  578.25 1459.31     578  1463.6  577.53
  1478.9     576 1498.37  574.43 1504.82     574 1505.34     574 1505.84     574
 1506.91     574  1542.4  572.76  1549.2  572.54 1561.93     572 1571.91  571.02
 1579.21  570.31 1581.09  570.14 1582.65     570 1587.27  568.79 1590.36     568
 1597.11  566.24 1598.06     566 1605.15  564.15 1605.74     564 1613.42     562
 1617.98  560.81 1621.11     560  1628.8     558  1636.5     556 1636.83  555.91
 1644.17     554 1644.82  553.83  1651.9     552 1656.61  550.76 1659.54     550
 1665.81  549.24  1676.8     548    1684   545.4    1703  543.29    1715   543.7
    1718   543.9    1743   544.5    1768     544 1785.39     548 1788.98  549.15
 1791.85     550 1795.38     551 1798.92     552  1802.7  553.06 1806.03     554
 1809.78  555.05 1813.19     556 1815.85  556.75  1820.3     558 1822.87  558.73
  1827.4     560  1830.8  560.96 1834.51     562 1839.93  563.52 1841.62     564
 1847.49  565.65 1848.73     566 1849.29     566 1853.18     566 1854.34     566
 1859.72     566 1861.84  566.15 1869.51   566.7  1887.9     568  1895.1  569.32
  1898.5     570 1900.08  570.71 1902.91     572 1904.94  572.93 1907.26     574
 1910.34   575.4 1911.66     576 1915.29  577.67 1916.02     578 1919.97  579.81
 1920.38     580 1922.12  580.82 1924.66     582 1927.76  583.67 1928.45     584
 1932.01  585.66 1932.79     586 1936.47  587.43 1937.86     588 1939.46  588.63
 1942.91     590 1944.04  590.31
BR U #Mann= 4
    1000     .06 1582.65    .018    1703    .035    1768    .018
BR D #Sta/Elev= 149
    1000  580.17 1005.35   580.1 1012.41  580.01 1013.09     580 1086.62  578.65
 1121.16  578.02 1122.46     578 1129.82     578 1134.29  579.76 1134.91     580
 1135.68   580.3 1138.47  581.34 1140.18     582 1144.44  583.57 1145.65     584
 1154.93  584.82 1160.84  585.25 1165.66  585.45 1168.38  585.63 1172.43     586
  1180.1     586 1184.34     586 1188.51  586.16 1189.58   586.2 1190.41  586.24
  1201.2   586.5 1207.98  586.88 1211.68  587.02 1220.54  587.54  1227.8  587.94
 1228.16  587.96 1229.04     588 1229.98     588    1231     588 1231.58     588
 1248.61  588.86 1267.01  589.15 1289.11  589.53 1290.21  589.53  1291.3  589.52
 1292.81   589.5    1296  589.44 1307.31   589.7 1307.84  589.69 1310.13  589.64
 1314.73  589.76 1315.34  589.75    1318  589.74 1318.36  589.73  1326.9  589.75
 1331.15     590 1332.44     590 1338.34     590  1362.6     590 1364.47  590.01
 1364.86     590 1385.99  589.15 1406.66     588 1407.36     588 1409.63  587.16
 1412.76     586 1413.12  585.87 1418.12     584 1420.26  583.24 1423.62     582
 1432.58  580.11 1432.93     580 1433.47  579.89 1436.56  579.35 1443.58   578.1
 1444.12     578  1450.4  576.98 1452.55  576.61 1454.17  576.37 1456.94     576
 1458.24     576 1459.22     576 1459.82     576 1472.82     576 1475.16     576
 1477.37     576 1509.98  574.13 1512.87     574 1531.76  572.86 1546.03     572
 1555.87  571.64 1597.74   570.4 1598.09   570.4 1598.89  570.41 1600.36     570
 1606.14  568.29 1607.13     568 1613.12  566.23 1613.91     566 1620.14  564.16
 1620.69     564 1627.46     562 1631.54   560.8 1634.26     560 1640.14  558.28
 1641.12     558 1641.76  557.81 1647.98     556 1649.25  555.62 1654.78     554
 1656.44  553.52 1661.62     552 1663.55  551.43 1668.46     550 1685.88     548
    1696   547.7    1704   546.5 1726.13  542.99 1744.13  542.99    1766   546.5
 1772.76     548 1777.07   548.4  1794.2     550 1802.86  551.22 1808.03     552
 1812.12  553.08 1815.59     554 1816.64  554.28 1823.12     556 1825.14  556.53
 1830.56     558 1831.73  558.32 1837.97     560 1842.92  561.33 1845.43     562
 1847.17  562.48 1852.83     564 1854.92  564.57  1860.2     566 1879.55  567.84
 1881.09     568 1891.89  568.63  1915.1     570 1918.54  571.12 1921.32     572
 1926.68  573.76 1927.42     574 1932.66  575.69  1933.6     576 1939.19  577.82
 1939.74     578 1950.49  579.99 1950.99  579.97 1951.29  579.89
BR D #Mann= 4
    1000     .06 1598.09    .018 1668.46    .035  1794.2    .018
BC Design=,, 0 ,, 0 ,,,,,,
BC Use User HTab Curves=0
BC User HTab FreeFlow(D)= 0

Type RM Length L Ch R = 1 ,24025   ,104,104,104
BEGIN DESCRIPTION:
This cross section corresponds to cross section 24191 of the non-georeferenced CDC model which was the source of this model.
Downstream Hulen Street.
---------------------------------------------------------------------
CDC FW111809-01 SH121/SOUTHWEST PARKWAY
CROSS-SECTION 24191 - 32940
DOWNSTREAM END.
---------------------------------------------------------------------
END DESCRIPTION:
XS GIS Cut Line= 2
     2311192.585   6946114.91789    2311472.1179   6945206.72188
#Sta/Elev= 30
    1000  580.17 1129.82     578 1145.65     584 1172.43     586  1201.2   586.5
 1248.61  588.86 1331.15     590 1364.47  590.01 1407.36     588 1423.62     582
 1433.47  579.89 1456.94     576 1477.37     576 1546.03     572 1598.09   570.4
 1600.36     570 1668.46     550 1685.88     548    1696   547.7 1726.13  542.99
 1744.13  542.99    1766   546.5 1772.76     548  1794.2     550 1808.03     552
  1860.2     566 1881.09     568  1915.1     570 1939.74     578 1951.29  579.89
#Mann= 3 ,0,0
    1000     .06       0 1598.09    .035       0  1860.2     .06       0
Bank Sta=1598.09,1860.2
XS Rating Curve= 0 ,0
Exp/Cntr=0.5,0.3