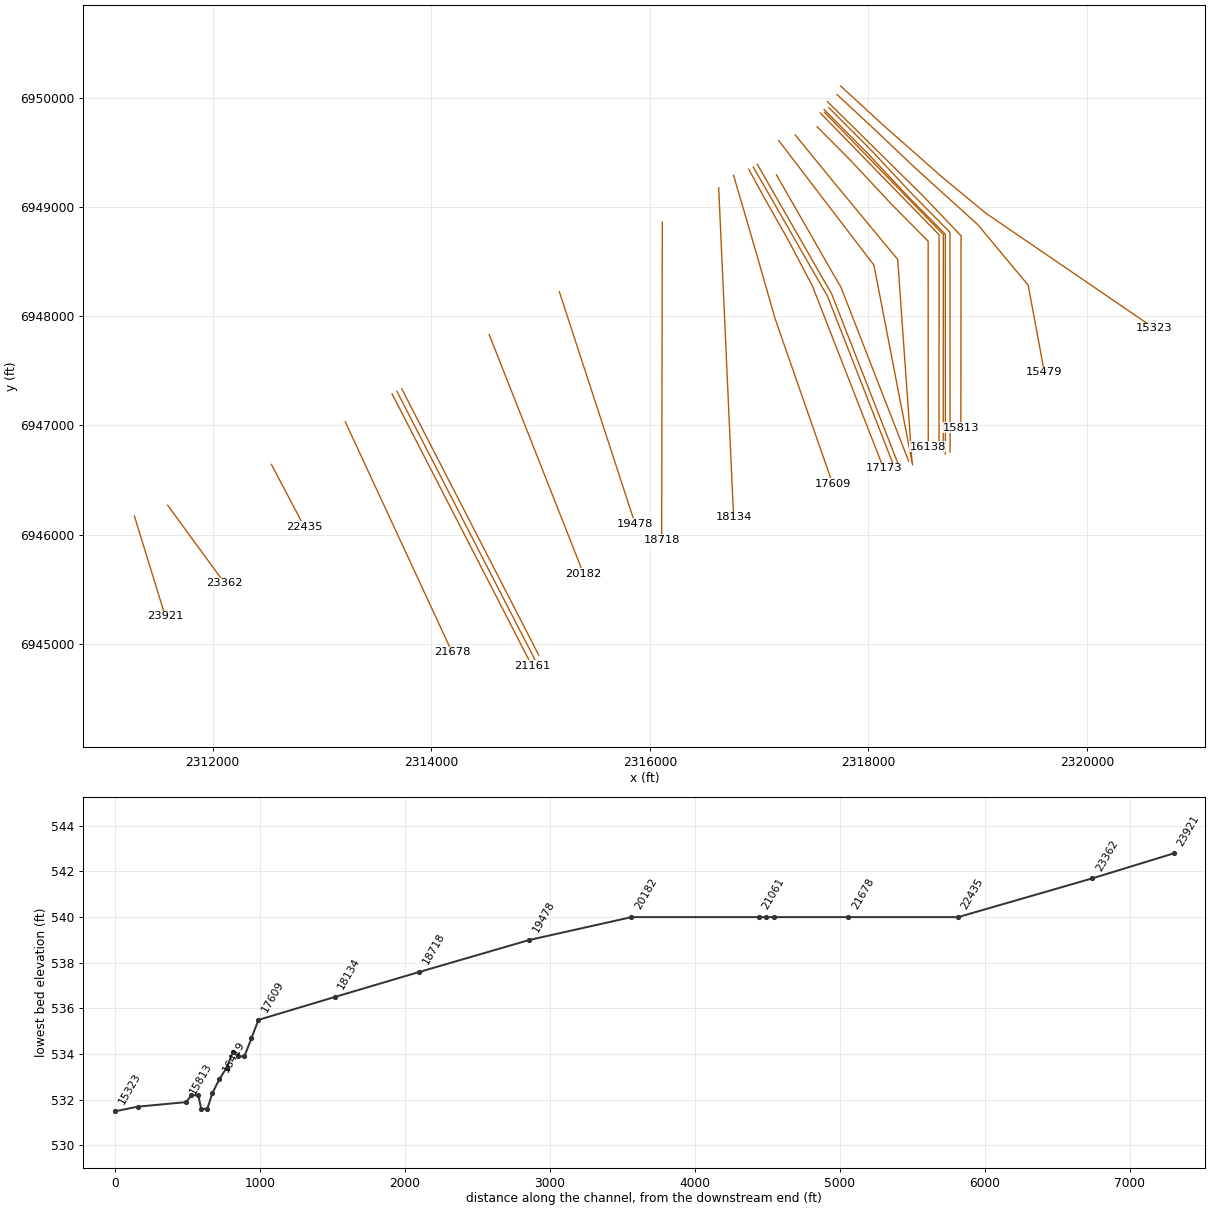
HEC-RAS study CDC_Consolidated_Model.prj: Upper Trinity CDC Consolidated Model

--- CDC_Consolidated_Model.g03 (geometry) --- (continued)

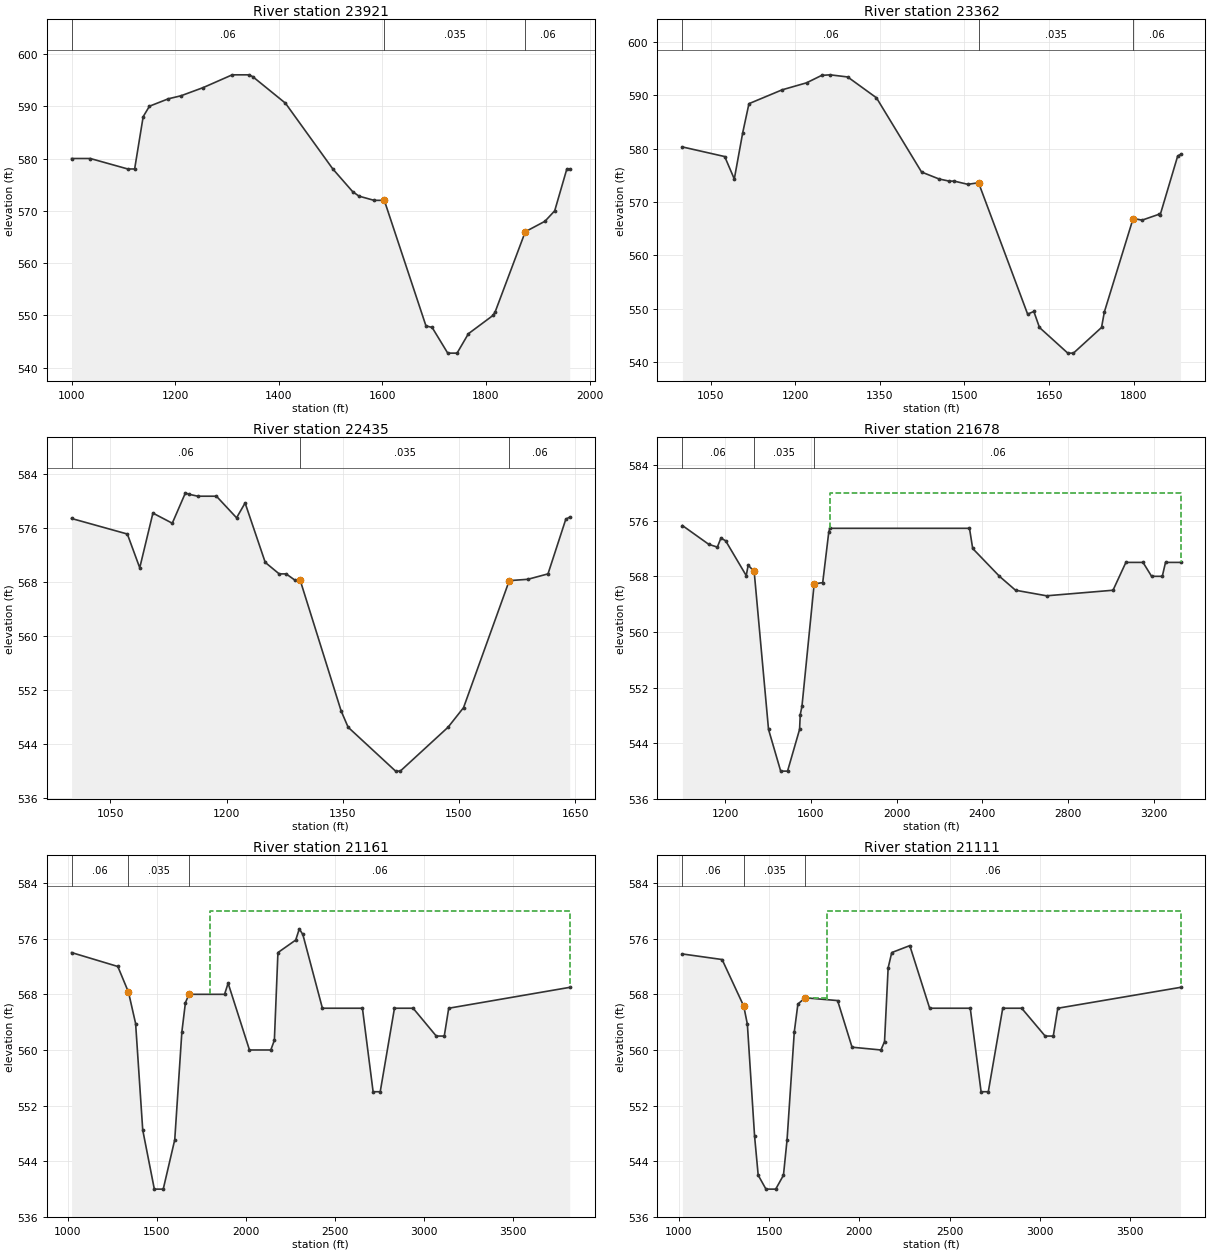
Type RM Length L Ch R = 1 ,23921   ,560,560,773
BEGIN DESCRIPTION:
This cross section corresponds to cross section 24091 of the non-georeferenced CDC model which was the source of this model.
Effective flow limit set at Overton Levee in ROB.
END DESCRIPTION:
XS GIS Cut Line= 4
2311283.936842156946169.78526674  2311285.597239 6946164.3906753
 2311565.1301398 6945256.19466532311566.790536656945250.80007386
#Sta/Elev= 30
    1000     580 1036.21     580  1108.5     578 1121.74     578 1138.21     588
  1150.3     590 1186.87  591.42 1211.38     592  1254.3  593.57  1310.1     596
    1343     596 1349.86  595.64 1412.83  590.58 1504.33     578 1542.36  573.69
 1554.68  572.81 1583.92     572 1603.69     572 1684.09     548    1696   547.7
 1726.13  542.79 1744.13  542.79    1766   546.5 1813.53     550  1817.8  550.71
 1875.82     566 1913.77     568  1932.6     570 1956.03     578 1961.53     578
#Mann= 3 ,0,0
    1000     .06       0 1603.69    .035       0 1875.82     .06       0
Bank Sta=1603.69,1875.82
XS Rating Curve= 0 ,0
Exp/Cntr=0.3,0.1

Type RM Length L Ch R = 1 ,23362   ,927,927,865
BEGIN DESCRIPTION:
This cross section corresponds to cross section 23535 of the non-georeferenced CDC model which was the source of this model.
Effective flow limit set at Overton Levee in ROB.
Channel data from 1975 USACE field survey.
END DESCRIPTION:
XS GIS Cut Line= 2
   2311588.30107   6946268.75715   2312108.92011   6945555.84815
#Sta/Elev= 30
    1000   580.3    1075   578.5    1092   574.3    1107     583    1118   588.4
    1177     591    1220   592.3    1247   593.7    1262   593.8    1293   593.4
    1344   589.5    1424   575.6    1455   574.3    1473   573.9    1482   573.9
    1506   573.3    1525   573.6    1612     549    1623   549.5    1633   546.5
 1683.19   541.7 1693.19   541.7    1743   546.5    1748   549.4    1799   566.9
    1815   566.6    1845   567.7    1847   567.6    1878   578.6    1883   578.9
#Mann= 3 ,0,0
    1000     .06       0    1525    .035       0    1799     .06       0
#XS Ineff= 2 , 0
       0    1525   573.6    1799       0   566.9
Permanent Ineff=
       F       F
Bank Sta=1525,1799
XS Rating Curve= 0 ,0
Exp/Cntr=0.3,0.1

Type RM Length L Ch R = 1 ,22435   ,756,756,732
BEGIN DESCRIPTION:
This cross section corresponds to cross section 22604 of the non-georeferenced CDC model which was the source of this model.
Effective flow limit set at Overton Levee in ROB.
Channel data from 1975 USACE field survey.
END DESCRIPTION:
XS GIS Cut Line= 2
   2312537.41597   6946642.98705   2312836.86189   6946074.46588
#Sta/Elev= 27
    1000   577.4    1072   575.1    1088   570.1    1105   578.2    1130   576.7
    1147   581.2    1151     581    1163   580.7    1187   580.7    1213   577.5
    1224   579.7    1250   570.9    1268   569.2    1277   569.2    1288   568.3
    1295   568.3    1348   548.9    1357   546.5  1418.3     540  1424.3     540
    1486   546.5    1506   549.4    1565   568.2    1589   568.4    1615   569.2
    1638   577.3    1643   577.6
#Mann= 3 ,0,0
    1000     .06       0    1295    .035       0    1565     .06       0
#XS Ineff= 2 , 0
       0    1295   568.3    1565       0   568.2
Permanent Ineff=
       F       F
Bank Sta=1295,1565
XS Rating Curve= 0 ,0
Exp/Cntr=0.3,0.1

Type RM Length L Ch R = 1 ,21678   ,517,517,537
BEGIN DESCRIPTION:
This cross section corresponds to cross section 21844 of the non-georeferenced CDC model which was the source of this model.
Effective flow limit set at Overton Levee in ROB.
Ground points added in ROB to account for storage within Colonial Golf Course - September 2007.
Channel data from 1975 USACE field survey.
END DESCRIPTION:
XS GIS Cut Line= 3
    2313213.6889   6947032.53089   2313502.85794   6946408.53312
 2314191.2589227 6944923.0328808
#Sta/Elev= 30
    1000   575.3    1123   572.6    1163   572.2    1180   573.5    1202   573.1
    1298   568.1    1307   569.6    1335   568.7    1402     546 1458.79     540
 1490.79     540    1547     546    1550   548.1    1558   549.3    1615   566.9
    1655   567.1    1683   574.3    1688   574.9    2340   574.9    2355     572
    2480     568    2555     566    2700   565.2    3010     566    3070     570
    3150     570    3190     568    3240     568    3255     570    3325     570
#Mann= 3 ,0,0
    1000     .06       0    1335    .035       0    1615     .06       0
#XS Ineff= 2 , 0
       0    1335   568.7    1688       0     580
Permanent Ineff=
       F       F
Bank Sta=1335,1615
XS Rating Curve= 0 ,0
Exp/Cntr=0.3,0.1

Type RM Length L Ch R = 1 ,21161   ,50,50,50
BEGIN DESCRIPTION:
This cross section corresponds to cross section 21329 of the non-georeferenced CDC model which was the source of this model.
50 feet upstream of channel dam.  Effective flow limits set at sta 1800 in ROB.
Ground points added in ROB to account for storage within Colonial Golf Course - September 2007.
Channel data from 1975 USACE field survey.
END DESCRIPTION:
XS GIS Cut Line= 3
   2313641.08896   6947289.48904   2314263.72092   6946078.55215
 2314921.4428998 6944799.3698082
#Sta/Elev= 30
    1020     574    1280     572    1340   568.3    1380   563.8    1420   548.5
 1485.25     540 1535.25     540    1600   547.1    1640   562.6    1660   566.8
    1680     568    1880     568    1900   569.6    2020     560    2140     560
    2160   561.4    2180     574    2280   575.8    2300   577.4    2320   576.6
    2430     566    2655     566    2715     554    2755     554    2835     566
    2940     566    3070     562    3115     562    3140     566    3820     569
#Mann= 3 ,0,0
    1020     .06       0    1340    .035       0    1680     .06       0
#XS Ineff= 3 ,-1
    1020    1340   568.3    1680    1800     568    1800    3820     580
Permanent Ineff=
       F       F       F
Bank Sta=1340,1680
XS Rating Curve= 0 ,0
Exp/Cntr=0.3,0.1

Type RM Length L Ch R = 1 ,21111   ,50,50,50
BEGIN DESCRIPTION:
This cross section corresponds to cross section 21279 of the non-georeferenced CDC model which was the source of this model.
Upstream of channel dam.
Effective flow limit set at sta 1820 in ROB.
Ground points added in ROB to account for storage within Colonial Golf Course - September 2007.
END DESCRIPTION:
XS GIS Cut Line= 3
   2313685.55508   6947312.35185   2314294.45905   6946128.11308
 2314947.6174008 6944857.8053138
#Sta/Elev= 30
    1020   573.8    1240     573    1360   566.3    1380   563.7    1420   547.6
    1440     542 1483.07     540 1537.07     540    1580     542    1600   547.1
    1640   562.6    1660   566.6    1700   567.5    1880   567.1    1960   560.4
    2120     560    2140   561.2    2160   571.8    2180     574    2280     575
    2390     566    2615     566    2675     554    2715     554    2795     566
    2900     566    3030     562    3075     562    3100     566    3780     569
#Mann= 3 ,0,0
    1020     .06       0    1360    .035       0    1700     .06       0
#XS Ineff= 3 ,-1
    1020    1360   566.3    1700    1820   567.5    1820    3780     580
Permanent Ineff=
       F       F       F
Bank Sta=1360,1700
XS Rating Curve= 0 ,0
Exp/Cntr=0.3,0.1

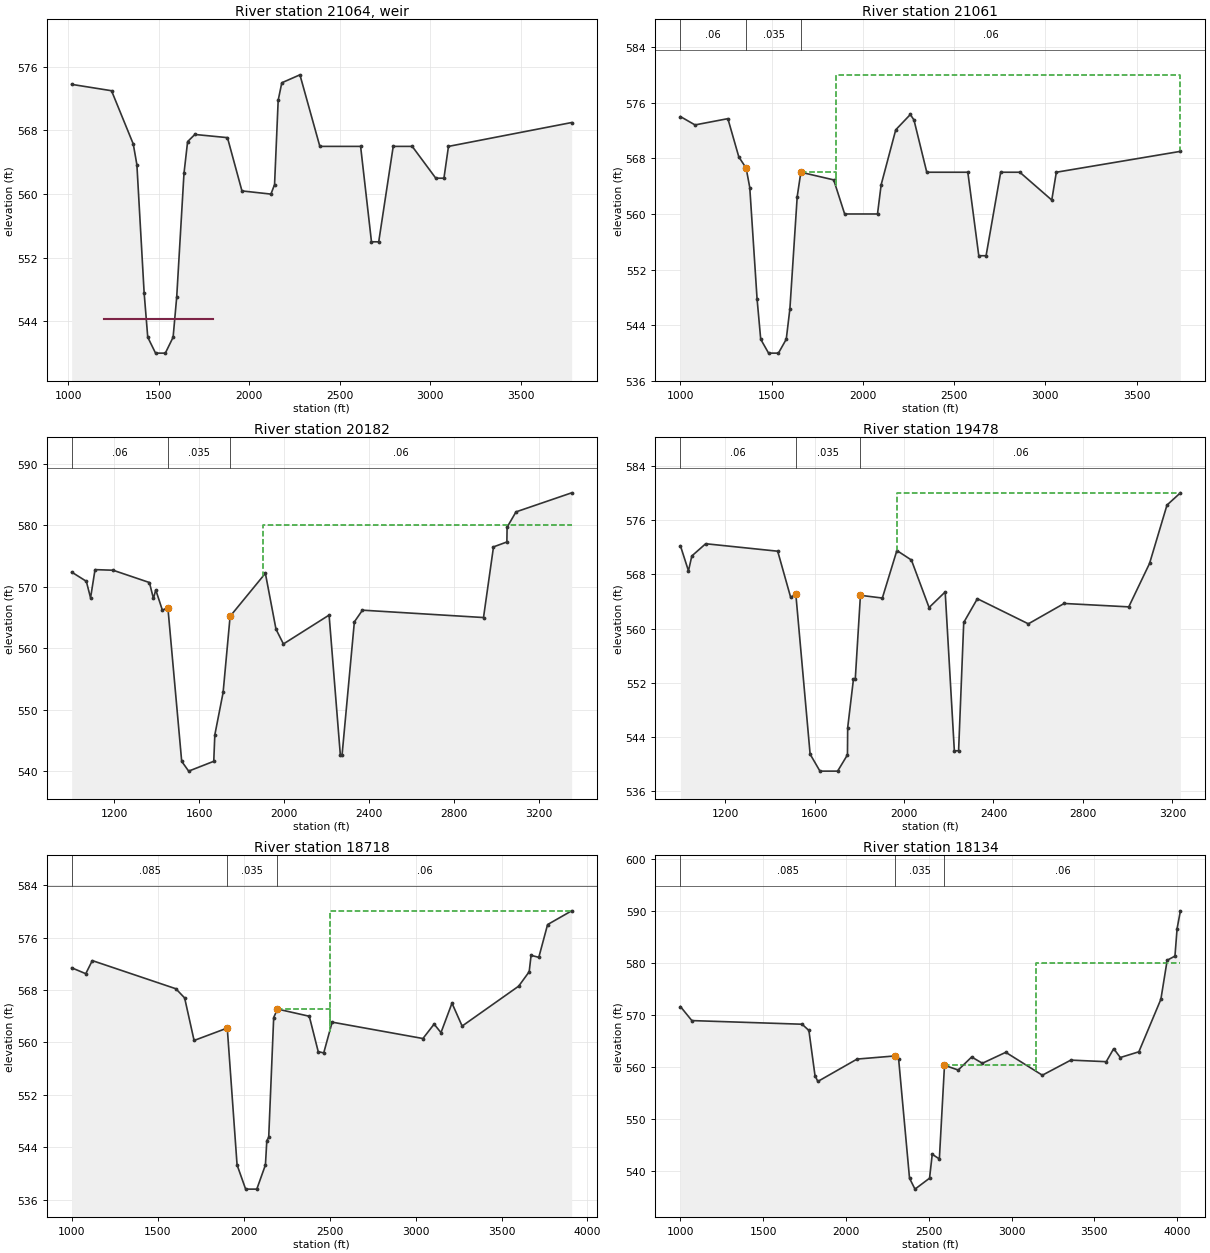
Type RM Length L Ch R = 5 ,21064   ,,,
BEGIN DESCRIPTION:
channel dam
crest elevation 544.3
END DESCRIPTION:
Node Name=channel dam
IW Pilot Flow=0
#Inline Weir SE= 2
    1200   544.3    1800   544.3
IW Dist,WD,Coef,Skew,MaxSub,Min_El,Is_Ogee,SpillHt,DesHd
1,5,3,0,0.95,, 0 ,,,2,2,
Inline Weir Flap Gates= 0
IW Outlet Rating Curve= 0 ,False,,

Type RM Length L Ch R = 1 ,21061   ,880,880,827
BEGIN DESCRIPTION:
This cross section corresponds to cross section 21239 of the non-georeferenced CDC model which was the source of this model.
36.5 feet downstream of channel dam.  Effective flow limit set at sta 1850 in ROB.
Ground points added in ROB to account for storage within Colonial Golf Course - September 2007.
Channel data from 1975 USACE field survey.
END DESCRIPTION:
XS GIS Cut Line= 3
   2313730.02087   6947335.21499   2314323.59186   6946180.79703
  2314982.937953 6944898.4550955
#Sta/Elev= 30
    1000     574    1080   572.8    1260   573.7    1320   568.2    1360   566.6
    1380   563.8    1420   547.8    1440     542 1483.07     540 1537.07     540
    1580     542    1600   546.4    1640   562.5    1660     566    1840   564.9
    1900     560    2080     560    2100   564.2    2180   572.1    2260   574.3
    2280   573.5    2350     566    2575     566    2635     554    2675     554
    2755     566    2860     566    3035     562    3060     566    3740     569
#Mann= 3 ,0,0
    1000     .06       0    1360    .035       0    1660     .06       0
#XS Ineff= 3 ,-1
    1850    3740     580    1000    1360   566.6    1660    1850     566
Permanent Ineff=
       F       F       F
Bank Sta=1360,1660
XS Rating Curve= 0 ,0
Exp/Cntr=0.3,0.1

Type RM Length L Ch R = 1 ,20182   ,704,704,699
BEGIN DESCRIPTION:
This cross section corresponds to cross section 20351 of the non-georeferenced CDC model which was the source of this model.
Effective flow limit set at sta 1000 in LOB at railroad track, at sta 1899 in ROB at levee.  Colonial Golf Course in ROB.
Channel data from 1975 USACE field survey.
END DESCRIPTION:
XS GIS Cut Line= 2
   2314530.13804   6947832.22187   2315393.24294   6945642.46805
#Sta/Elev= 30
    1000   572.4    1069   570.9    1089   568.2    1110   572.8    1195   572.7
    1366   570.7    1385   568.1    1396   569.5    1427   566.2    1453   566.6
    1518   541.6 1550.81     540    1669   541.6    1674   545.9    1713   552.8
    1746   565.2    1912   572.2    1962   563.1    1997   560.7    2212   565.4
    2265   542.6    2273   542.6    2331   564.3    2369   566.2    2939     565
    2986   576.5    3049   577.3    3050   579.7    3092   582.2    3354   585.3
#Mann= 3 ,0,0
    1000     .06       0    1453    .035       0    1746     .06       0
#XS Ineff= 3 ,-1
    1899    3354     580    1000    1453   566.6    1746    1899   565.2
Permanent Ineff=
       F       F       F
Bank Sta=1453,1746
XS Rating Curve= 0 ,0
Exp/Cntr=0.3,0.1

Type RM Length L Ch R = 1 ,19478   ,759,759,563
BEGIN DESCRIPTION:
This cross section corresponds to cross section 19645 of the non-georeferenced CDC model which was the source of this model.
Effective flow limit set at sta 1000 in LOB.  Colonial
Golf Course in ROB.  Effective flow limit set at sta 1968 at levee at Colonial Golf Course.
Channel data from 1975 USACE field survey.
END DESCRIPTION:
XS GIS Cut Line= 2
   2315172.24994   6948223.67614   2315865.72592   6946097.94385
#Sta/Elev= 30
    1000   572.2    1036   568.5    1051   570.7    1113   572.5    1435   571.4
    1493   564.6    1516   565.1    1580   541.5 1624.02     539 1703.02     539
    1747   541.4    1748   545.4    1774   552.6    1782   552.6    1805   564.9
    1903   564.5    1968   571.5    2033   570.1    2112   563.1    2184   565.4
    2225     542    2244     542    2267   560.9    2328   564.4    2556   560.7
    2716   563.7    3005   563.2    3098   569.6    3176   578.2    3236     580
#Mann= 3 ,0,0
    1000     .06       0    1516    .035       0    1805     .06       0
#XS Ineff= 3 ,-1
    1968    3236     580    1000    1516   565.1    1805    1968   564.9
Permanent Ineff=
       F       F       F
Bank Sta=1516,1805
XS Rating Curve= 0 ,0
Exp/Cntr=0.3,0.1

Type RM Length L Ch R = 1 ,18718   ,585,585,646
BEGIN DESCRIPTION:
This cross section corresponds to cross section 18867 of the non-georeferenced CDC model which was the source of this model.
Effective flow limit set at sta 1000 in LOB at railroad
track.  Colonial Golf Course in ROB.  Effective flow limit set at sta 2500 in ROB due to upstream levee at Colonial Golf Course.
Channel data from 1975 USACE field survey.
END DESCRIPTION:
XS GIS Cut Line= 2
   2316114.41505   6948861.57316   2316108.48593   6945953.61408
#Sta/Elev= 30
    1000   571.4    1082   570.5    1120   572.5    1606   568.2    1657   566.8
    1712   560.3    1905   562.2    1962   541.3 2011.82   537.6 2076.82   537.6
    2127   541.3    2135     545    2146   545.5    2175   563.8    2197   565.1
    2382     564    2434   558.6    2466   558.4    2515   563.1    3043   560.6
    3108   562.8    3148   561.5    3212     566    3271   562.5    3600   568.6
    3661   570.8    3672   573.3    3717     573    3768     578    3908   580.1
#Mann= 3 ,0,0
    1000    .085       0    1905    .035       0    2197     .06       0
#XS Ineff= 3 ,-1
    2500    3908     580    2197    2500   565.1    1000    1905   562.2
Permanent Ineff=
       F       F       F
Bank Sta=1905,2197
XS Rating Curve= 0 ,0
Exp/Cntr=0.3,0.1

Type RM Length L Ch R = 1 ,18134   ,525,525,1057
BEGIN DESCRIPTION:
This cross section corresponds to cross section 18275 of the non-georeferenced CDC model which was the source of this model.
Colonial Golf Course in ROB.  Ineffective flow limit set
at sta 3150 in ROB due to upstream levee at Colonial Golf Course.
Channel data from 1975 USACE field survey.
END DESCRIPTION:
XS GIS Cut Line= 2
   2316630.34611   6949175.74904   2316766.42884   6946158.98014
#Sta/Elev= 30
    1000   571.6    1069   568.9    1735   568.2    1776     567    1813   558.3
    1830   557.2    2067   561.5    2294   562.1    2318   561.5 2383.76   538.6
 2416.76   536.5 2504.76   538.6    2521   543.2    2564   542.3    2595   560.3
    2678   559.4    2759   561.9    2824   560.7    2965   562.8    3186   558.4
    3358   561.3    3572     561    3617   563.5    3657   561.8    3769   562.9
    3902     573    3940   580.5    3987   581.3    4000   586.6    4020     590
#Mann= 3 ,0,0
    1000    .085       0    2294    .035       0    2595     .06       0
#XS Ineff= 3 ,-1
    3150    4020     580    1000    2294   562.1    2595    3150   560.3
Permanent Ineff=
       F       F       F
Bank Sta=2294,2595
XS Rating Curve= 0 ,0
Exp/Cntr=0.3,0.1

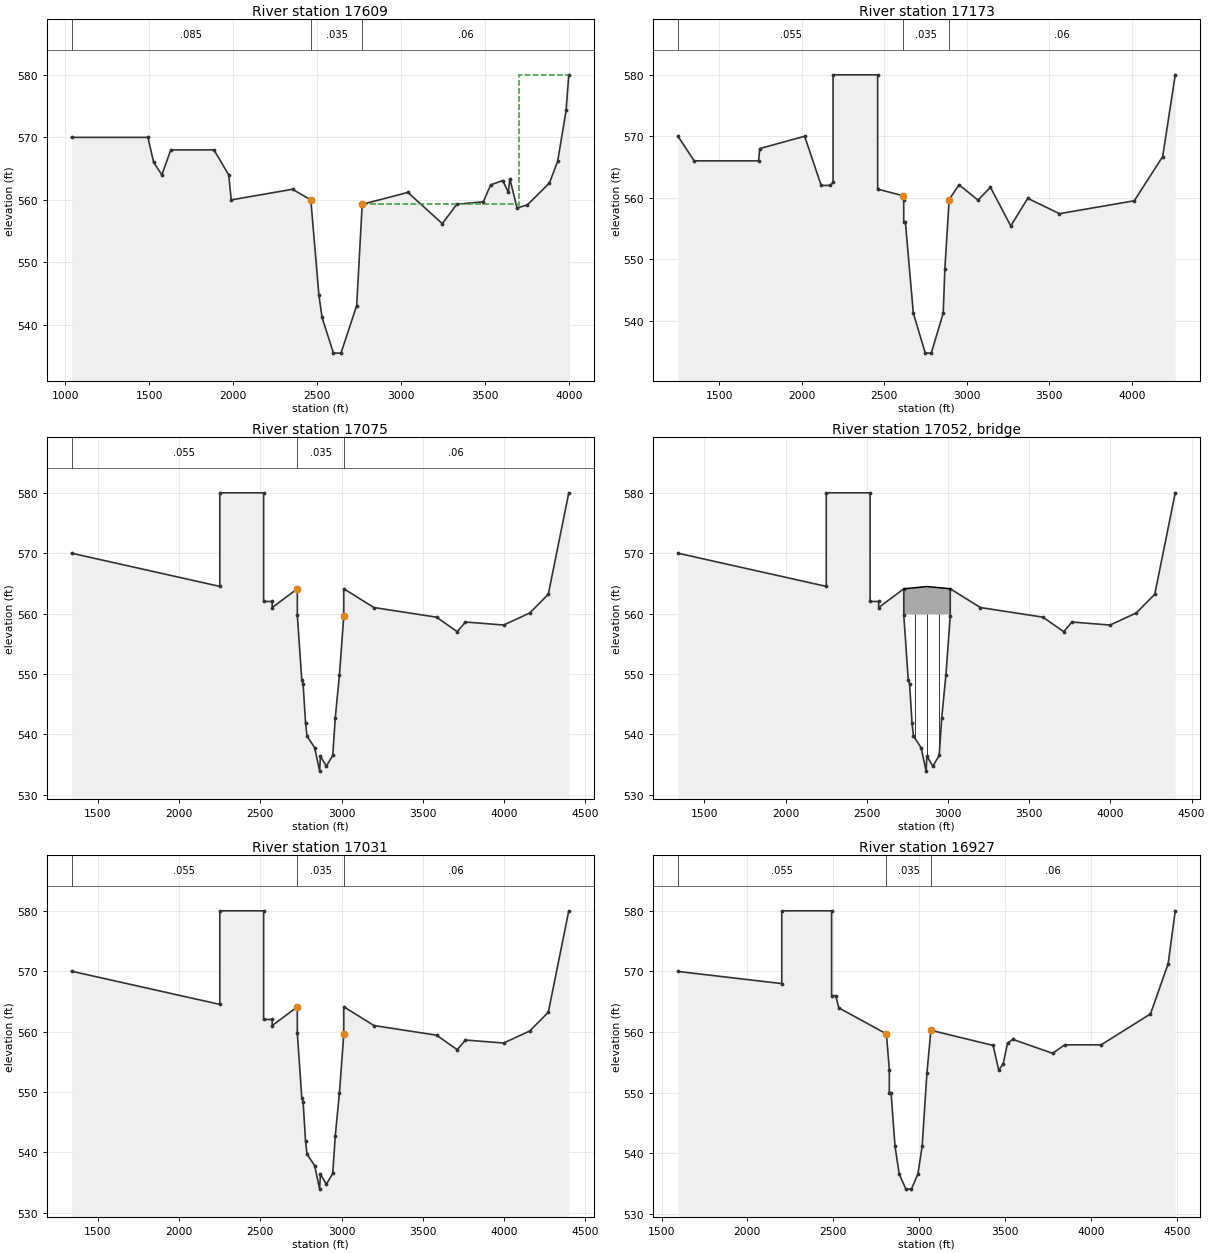
Type RM Length L Ch R = 1 ,17609   ,48,48,71
BEGIN DESCRIPTION:
This cross section corresponds to cross section 17746 of the non-georeferenced CDC model which was the source of this model.
Colonial Golf Course in ROB.  Ineffective flow limit
set at sta 3700 in ROB due to upstream levee at Colonial Golf Course.
Channel data from 1975 USACE field survey.
Upstream limit of Rogers Road trailhead project.
END DESCRIPTION:
XS GIS Cut Line= 5
   2316766.19787   6949290.86495   2316794.95503   6949192.33595
   2316979.32015   6948560.49109   2317147.53011   6947973.56608
   2317672.72591   6946466.81089
#Sta/Elev= 30
    1036     570    1491     570    1525     566    1574     564    1627     568
    1884     568    1972     564    1987     560    2352   561.7    2461     560
    2509   544.8    2528   541.2 2595.57   535.5 2640.57   535.5    2734   543.1
    2767   559.3    3039   561.2    3244   556.2    3330   559.3    3488   559.7
    3532   562.4    3604   563.1    3637   561.2    3646   563.4    3689   558.7
    3750   559.2    3882   562.7    3931   566.2    3981   574.3    3997     580
#Mann= 3 ,0,0
    1036    .085       0    2461    .035       0    2767     .06       0
#XS Ineff= 3 ,-1
    3700    3997     580    1036    2461     560    2767    3700   559.3
Permanent Ineff=
       F       F       F
Bank Sta=2461,2767
XS Rating Curve= 0 ,0
Exp/Cntr=0.3,0.1

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
Type RM Length L Ch R = 1 ,17173   ,49,49,52
BEGIN DESCRIPTION:
This cross section corresponds to cross section 17302 of the non-georeferenced CDC model which was the source of this model.
97 feet upstream of Rogers Road.
Ineffective flow areas defined in LOB due to structures.
Channel data from 1975 USACE field survey.
END DESCRIPTION:
XS GIS Cut Line= 5
2316905.110522556949345.94086529     2317049.445   6949080.44608
   2317268.24805   6948693.45801   2317486.17609   6948280.38174
2318139.296936066946606.04812376
#Sta/Elev= 30
    1251     570    1349     566    1739     566    1746     568    2018     570
    2118     562    2174     562    2190   562.5    2190     580    2460     580
    2460   561.4    2616   560.3    2618   559.6    2618     556    2628     556
    2676   541.2 2748.53   534.7 2784.53   534.7    2857   541.2    2867   548.4
    2893   559.7    2953   562.1    3068   559.6    3143   561.7    3266   555.4
    3369   559.9    3561   557.4    4014   559.5    4186   566.7    4262     580
#Mann= 3 ,0,0
    1251    .055       0    2616    .035       0    2893     .06       0
#XS Ineff= 2 , 0
       0    2616   560.3    2893       0   557.3
Permanent Ineff=
       F       F
Bank Sta=2616,2893
XS Rating Curve= 0 ,0
Exp/Cntr=0.3,0.1

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
Type RM Length L Ch R = 1 ,17075   ,44,44,44
BEGIN DESCRIPTION:
This cross section corresponds to cross section 17206 of the non-georeferenced CDC model which was the source of this model.
Upstream of Rogers Road.
END DESCRIPTION:
XS GIS Cut Line= 5
  2316947.084302 6949365.6321234 2317330.1232427 6948697.9339834
 2317527.5762527 6948352.1659734 2317625.9969927 6948182.6440034
 2318248.8641827 6946588.0789534
#Sta/Elev= 30
    1337     570    2250   564.5    2250     580    2520     580    2520     562
    2572     562    2573     561  2727.5   564.1  2727.5   559.7    2755     549
    2763   548.4    2778   541.9    2787   539.7    2834   537.8    2865   533.9
  2869.5   536.4    2906   534.7  2945.5   536.5    2961   542.7    2987   549.9
  3013.5   559.6  3013.5  564.11    3199     561    3585   559.4    3712     557
    3763   558.6    3998   558.1    4159   560.1    4273   563.2    4399     580
#Mann= 3 ,0,0
    1337    .055       0  2727.5    .035       0  3013.5     .06       0
#XS Ineff= 2 , 0
       0  2728.4     559  3012.8       0   558.8
Permanent Ineff=
       F       F
Bank Sta=2727.5,3013.5
XS Rating Curve= 0 ,0
Exp/Cntr=0.5,0.3

Type RM Length L Ch R = 3 ,17052   ,,,
BEGIN DESCRIPTION:
Rogers Road
Downstream face of bridge.  Bridge data from July 1975 survey.  Minimum low chord elev. 559.87.  Bridge width 43 feet. Ineffective flow areas defined in LOB due to structures.
Channel data from 1975 USACE field survey.
END DESCRIPTION:
Node Name=Rogers Road
Bridge Culvert--1,0,-1,-1, 0
Deck Dist Width WeirC Skew NumUp NumDn MinLoCord MaxHiCord MaxSubmerge Is_Ogee
2,41,2.6,0, 8, 8, , , 0.95, 0, ,,,
  2727.5  2796.5  2799.5  2869.5  2872.5  2942.5  2945.5  3013.5
   564.1  564.28  564.29  564.48  564.47  564.29  564.29  564.11
  559.87  559.87  559.87  559.87  559.87  559.87  559.87  559.87
  2727.5  2796.5  2799.5  2869.5  2872.5  2942.5  2945.5  3013.5
   564.1  564.28  564.29  564.48  564.47  564.29  564.29  564.11
  559.87  559.87  559.87  559.87  559.87  559.87  559.87  559.87
Pier Skew, UpSta & Num, DnSta & Num=  ,2798, 2 ,2798, 2 , 0 , 0 , 0 ,,
       3       3
     535     562
       3       3
     535     562
Pier Skew, UpSta & Num, DnSta & Num=  ,2871, 2 ,2871, 2 , 0 , 0 , 0 ,,
       3       3
     535     562
       3       3
     535     562
Pier Skew, UpSta & Num, DnSta & Num=  ,2944, 2 ,2944, 2 , 0 , 0 , 0 ,,
       3       3
     535     562
       3       3
     535     562
BR Coef= 1 , 0 , 0 ,1.05, 0 ,,,0.8,-1,0.5,1,
WSPro=,,,, 1 ,,,, 0 ,,,, 0 ,,,,-1 ,-1 ,-1 , 0 , 0 , 0 , 0 , 0
BC Design=,, 0 ,, 0 ,,,,,,
BC HTab HWMax=580
BC Use User HTab Curves=0
BC User HTab FreeFlow(D)= 0

Type RM Length L Ch R = 1 ,17031   ,34.67,34.67,45
BEGIN DESCRIPTION:
This cross section corresponds to cross section 17162 of the non-georeferenced CDC model which was the source of this model.
One-foot downstream of Rogers Road.  Duplication of following bridge cross-section without bridge piers.
Ineffective flow areas defined in LOB due to structures.
Channel data from 1975 USACE field survey.
END DESCRIPTION:
XS GIS Cut Line= 5
  2316983.749422 6949390.4178902 2317366.7883623 6948722.7197502
 2317564.2413723 6948376.9517402 2317662.6621123 6948207.4297702
 2318285.5293023 6946612.8647202
#Sta/Elev= 30
    1337     570    2250   564.5    2250     580    2520     580    2520     562
    2572     562    2573     561  2727.5   564.1  2727.5   559.7    2755     549
    2763   548.4    2778   541.9    2787   539.7    2834   537.8    2865   533.9
  2869.5   536.4    2906   534.7  2945.5   536.5    2961   542.7    2987   549.9
  3013.5   559.6  3013.5  564.11    3199     561    3585   559.4    3712     557
    3763   558.6    3998   558.1    4159   560.1    4273   563.2    4399     580
#Mann= 3 ,0,0
    1337    .055       0  2727.5    .035       0  3013.5     .06       0
#XS Ineff= 2 , 0
       0  2728.4     559  3012.8       0   557.1
Permanent Ineff=
       F       F
Bank Sta=2727.5,3013.5
XS Rating Curve= 0 ,0
Exp/Cntr=0.5,0.3

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
Type RM Length L Ch R = 1 ,16927   ,44.29,44.29,23.57
BEGIN DESCRIPTION:
This cross section corresponds to cross section 17057 of the non-georeferenced CDC model which was the source of this model.
106 feet downstream of Rogers Road.
Ineffective flow areas defined in LOB due to structures.
Channel data from 1975 USACE field survey.
END DESCRIPTION:
XS GIS Cut Line= 5
2317158.834296616949293.23900495   2317453.26802   6948779.99393
   2317650.72103   6948434.22592   2317749.14177   6948264.70395
      2318368.48      6946672.84
#Sta/Elev= 30
    1596     570    2200     568    2200     580    2490     580    2490     566
    2514     566    2532     564    2809   559.7    2826   553.8    2826     550
    2836     550    2859   541.2  2883.4   536.6  2922.4   534.1  2954.4   534.1
  2992.4   536.6    3017   541.2    3045   553.3    3068   560.3    3430   557.8
    3463   553.7    3489   554.8    3514   558.2    3545   558.8    3776   556.5
    3847   557.9    4059   557.9    4346     563    4449   571.3    4490     580
#Mann= 3 ,0,0
    1596    .055       0    2809    .035       0    3068     .06       0
#XS Ineff= 2 , 0
       0    2809   559.7    3068       0  556.71
Permanent Ineff=
       F       F
Bank Sta=2809,3068
XS Rating Curve= 0 ,0
Exp/Cntr=0.3,0.1

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
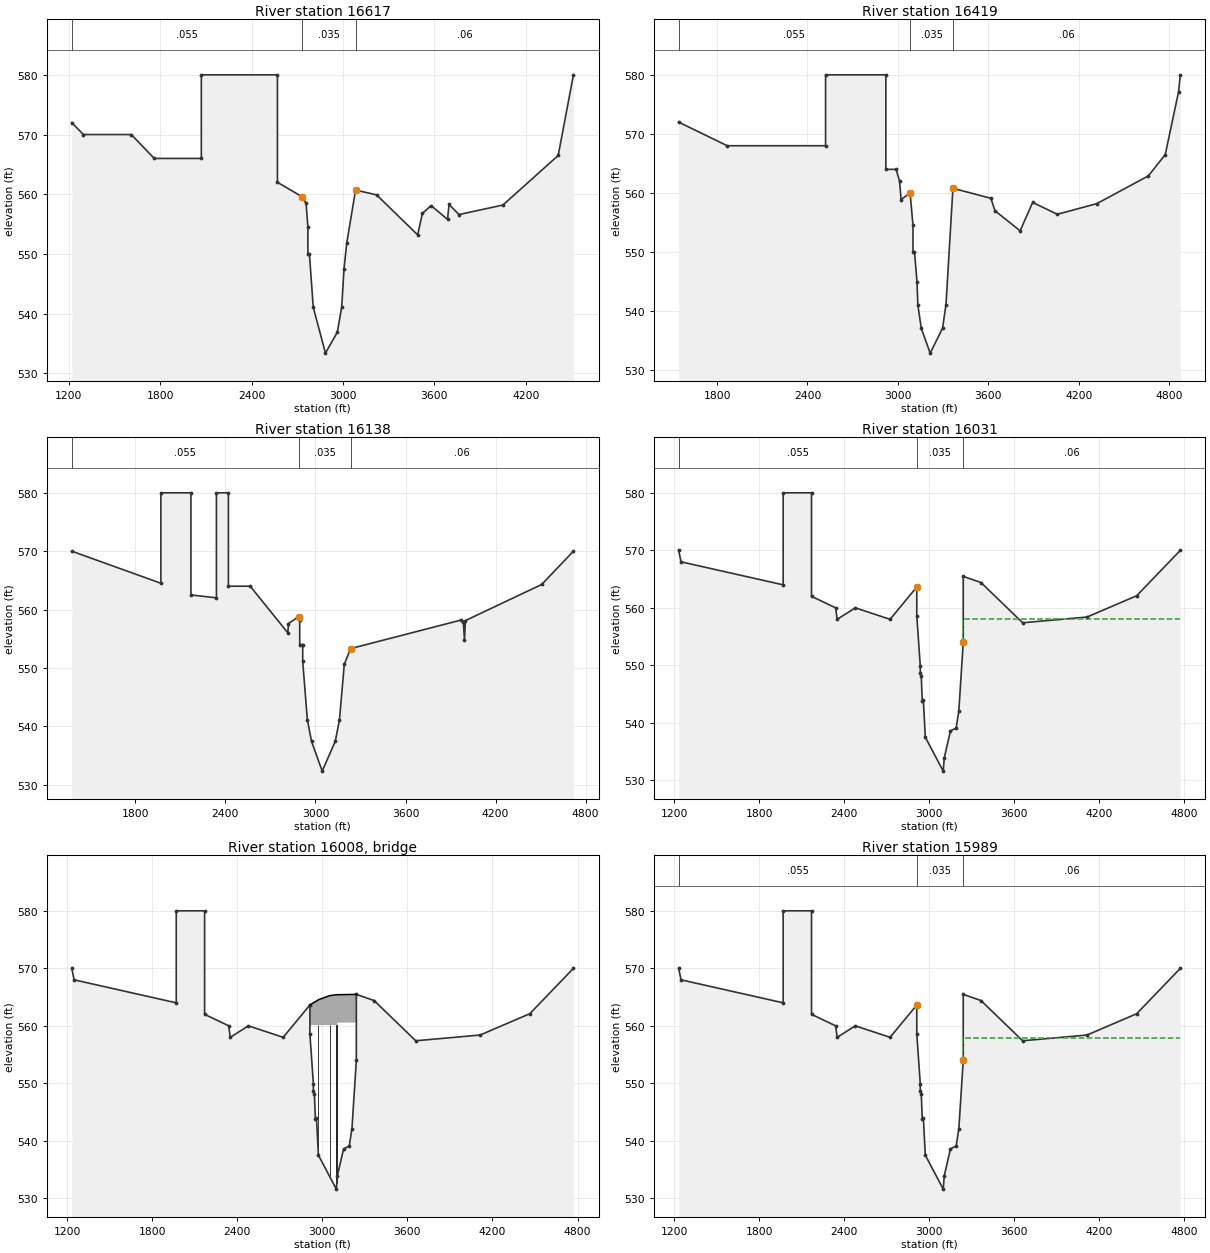
Type RM Length L Ch R = 1 ,16617   ,50,50,25
BEGIN DESCRIPTION:
This cross section corresponds to cross section 16746 of the non-georeferenced CDC model which was the source of this model.
Ineffective flow areas defined in LOB due to structures.
Channel data from 1975 USACE field survey.
END DESCRIPTION:
XS GIS Cut Line= 5
2317180.190599716949607.28885232      2317196.26   6949586.24593
   2318050.88592   6948467.11102   2318399.16901    6946666.5769
2318404.197329246946640.58178102
#Sta/Elev= 30
    1219     572    1296     570    1610     570    1761     566    2070     566
    2070     580    2570     580    2570     562    2731   559.6    2758   558.5
    2770   554.5    2770     550    2780     550    2805   541.1 2885.22   533.4
 2963.22   536.9    2992   541.1    3007   547.5    3025   551.8    3083   560.7
    3221   559.9    3491   553.2    3522   556.8    3579   558.1    3687   555.8
    3697   558.3    3762   556.6    4051   558.2    4414   566.5    4514     580
#Mann= 3 ,0,0
    1219    .055       0    2731    .035       0    3083     .06       0
#XS Ineff= 2 , 0
       0    2731   559.6    3083       0  556.65
Permanent Ineff=
       F       F
Bank Sta=2731,3083
XS Rating Curve= 0 ,0
Exp/Cntr=0.3,0.1

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
Type RM Length L Ch R = 1 ,16419   ,47,47,36
BEGIN DESCRIPTION:
This cross section corresponds to cross section 16547 of the non-georeferenced CDC model which was the source of this model.
Ineffective flow areas defined in LOB due to structures.
Channel data from 1975 USACE field survey.
END DESCRIPTION:
XS GIS Cut Line= 5
   2317330.55894   6949659.51284   2317635.78209   6949284.89089
   2318092.28216   6948731.35689   2318268.23686   6948520.10108
   2318399.15458   6946666.78064
#Sta/Elev= 30
    1545     572    1867     568    2520     568    2520     580    2920     580
    2920     564    2988     564    3011     562    3021   558.9    3081     560
    3100   554.5    3100     550    3110     550    3127   544.9    3132   541.1
 3155.04   537.1 3214.04   532.9 3296.04   537.1    3319   541.1    3365   560.8
    3617   559.1    3644     557    3811   553.6    3894   558.4    4058   556.4
    4320   558.2    4662   562.9    4774   566.5    4862   577.1    4874     580
#Mann= 3 ,0,0
    1545    .055       0    3081    .035       0    3365     .06       0
#XS Ineff= 2 , 0
       0    3081     560    3365       0   556.5
Permanent Ineff=
       F       F
Bank Sta=3081,3365
XS Rating Curve= 0 ,0
Exp/Cntr=0.3,0.1

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
Type RM Length L Ch R = 1 ,16138   ,36,36,38
BEGIN DESCRIPTION:
This cross section corresponds to cross section 16268 of the non-georeferenced CDC model which was the source of this model.
108 feet upstream of University Drive.
Ineffective flow areas defined in LOB due to structures.
Channel data from 1975 USACE field survey.
END DESCRIPTION:
XS GIS Cut Line= 5
2317530.107920766949735.34816572   2317844.52215   6949418.41096
   2318210.43514    6949026.3061   2318546.81504   6948686.24707
2318547.65724894 6946804.3247693
#Sta/Elev= 30
    1376     570    1970   564.5    1970     580    2170     580    2170   562.5
    2340     562    2340     580    2420     580    2420     564    2565     564
    2816     556    2820   557.6    2890   558.8    2895   558.2    2895     554
    2915     554    2915   551.1    2946   541.1 2973.86   537.4 3044.86   532.3
 3131.86   537.4    3160   541.1    3192   550.6    3234   553.3    3971   558.2
    3985   557.9    3993   554.8    3999   558.1    4508   564.3    4719     570
#Mann= 3 ,0,0
    1376    .055       0    2890    .035       0    3234     .06       0
#XS Ineff= 2 , 0
       0    2890   558.8    3234       0   553.3
Permanent Ineff=
       F       F
Bank Sta=2890,3234
XS Rating Curve= 0 ,0
Exp/Cntr=0.3,0.1

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
Type RM Length L Ch R = 1 ,16031   ,42,42,42
BEGIN DESCRIPTION:
This cross section corresponds to cross section 16161 of the non-georeferenced CDC model which was the source of this model.
END DESCRIPTION:
XS GIS Cut Line= 5
2317559.910063136949860.98069581     2317572.538     6949848.016
     2318646.756     6948745.151     2318646.756     6946782.911
     2318646.7566946764.81270928
#Sta/Elev= 30
    1233     570    1250     568    1970     564    1970     580    2170     580
    2170     562    2340     560    2351     558    2479     560    2724     558
  2912.5  563.63  2912.5   558.6    2937   549.9  2937.1   548.7    2944   548.2
    2951   543.8    2959   543.9  2972.5   537.5    3099   531.6    3106   533.9
    3150   538.6    3190   539.1    3209   542.1    3240     554    3240  565.47
    3365   564.4    3659   557.4    4113   558.4    4463   562.1    4771     570
#Mann= 3 ,0,0
    1233    .055       0  2912.5    .035       0    3240     .06       0
#XS Ineff= 2 , 0
       0  2912.5     560    3240       0  557.98
Permanent Ineff=
       F       F
Bank Sta=2912.5,3240
XS Rating Curve= 0 ,0
Exp/Cntr=0.5,0.3

Type RM Length L Ch R = 3 ,16008   ,,,
BEGIN DESCRIPTION:
University Drive - south bound
Downstream face of bridge.  Bridge data from July 1975 survey.  Upstream bridge: minimum low chord elev. 560.12.  Bridge width 40 feet.  Ineffective flow areas defined in LOB due to structures.
Channel data from 1975 USACE field survey.
END DESCRIPTION:
Node Name=University Drive
Bridge Culvert--1,0,-1,-1, 0
Deck Dist Width WeirC Skew NumUp NumDn MinLoCord MaxHiCord MaxSubmerge Is_Ogee
2,38,2.6,0, 9, 9, , , 0.95, 0, 0,0,,
  2912.5    2970  2972.5    3051  3053.5    3099    3106    3106    3240
  563.63  564.49  564.53  565.25  565.25  565.41  565.41  565.41  565.47
  560.12  560.12  560.12  560.12  560.12  560.12  560.12  560.56  560.56
  2912.5    2970  2972.5    3051  3053.5    3099    3106    3106    3240
  563.63  564.49  564.53  565.25  565.25  565.41  565.41  565.41  565.47
  560.12  560.12  560.12  560.12  560.12  560.12  560.12  560.56  560.56
Pier Skew, UpSta & Num, DnSta & Num=  ,2971.25, 2 ,2971.25, 2 , 0 , 0 , 0 ,,
     2.5     2.5
       0     561
     2.5     2.5
       0     561
Pier Skew, UpSta & Num, DnSta & Num=  ,3052.25, 2 ,3052.25, 2 , 0 , 0 , 0 ,,
     2.5     2.5
       0     561
     2.5     2.5
       0     561
Pier Skew, UpSta & Num, DnSta & Num=  ,3102.5, 2 ,3102.5, 2 , 0 , 0 , 0 ,,
       7       7
       0     561
       7       7
       0     561
BR Coef=-1 , 0 , 0 ,1.05, 0 ,,,0.8,-1,0.5,1,
WSPro=,,,, 1 ,,,, 0 ,,,, 0 ,,,,-1 ,-1 ,-1 , 0 , 0 , 0 , 0 , 0
BC Design=,, 0 ,, 0 ,,,,,,
BC HTab HWMax=580
BC Use User HTab Curves=0
BC User HTab FreeFlow(D)= 0

Type RM Length L Ch R = 1 ,15989   ,20,20,20
BEGIN DESCRIPTION:
This cross section corresponds to cross section 16120 of the non-georeferenced CDC model which was the source of this model.
Downstream of University Drive South.
END DESCRIPTION:
XS GIS Cut Line= 5
2317599.391096016949865.82642534     2317612.902     6949851.922
     2318685.819     6948747.755     2318684.517      6946788.12
2318684.504118726946768.73244201
#Sta/Elev= 30
    1233     570    1250     568    1970     564    1970     580    2170     580
    2170     562    2340     560    2351     558    2479     560    2724     558
  2912.5  563.63  2912.5   558.6    2937   549.9  2937.1   548.7    2944   548.2
    2951   543.8    2959   543.9  2972.5   537.5    3099   531.6    3106   533.9
    3150   538.6    3190   539.1    3209   542.1    3240     554    3240  565.47
    3365   564.4    3659   557.4    4113   558.4    4463   562.1    4771     570
#Mann= 3 ,0,0
    1233    .055       0  2912.5    .035       0    3240     .06       0
#XS Ineff= 2 , 0
       0  2912.5     560    3240       0  557.87
Permanent Ineff=
       F       F
Bank Sta=2912.5,3240
XS Rating Curve= 0 ,0
Exp/Cntr=0.5,0.3

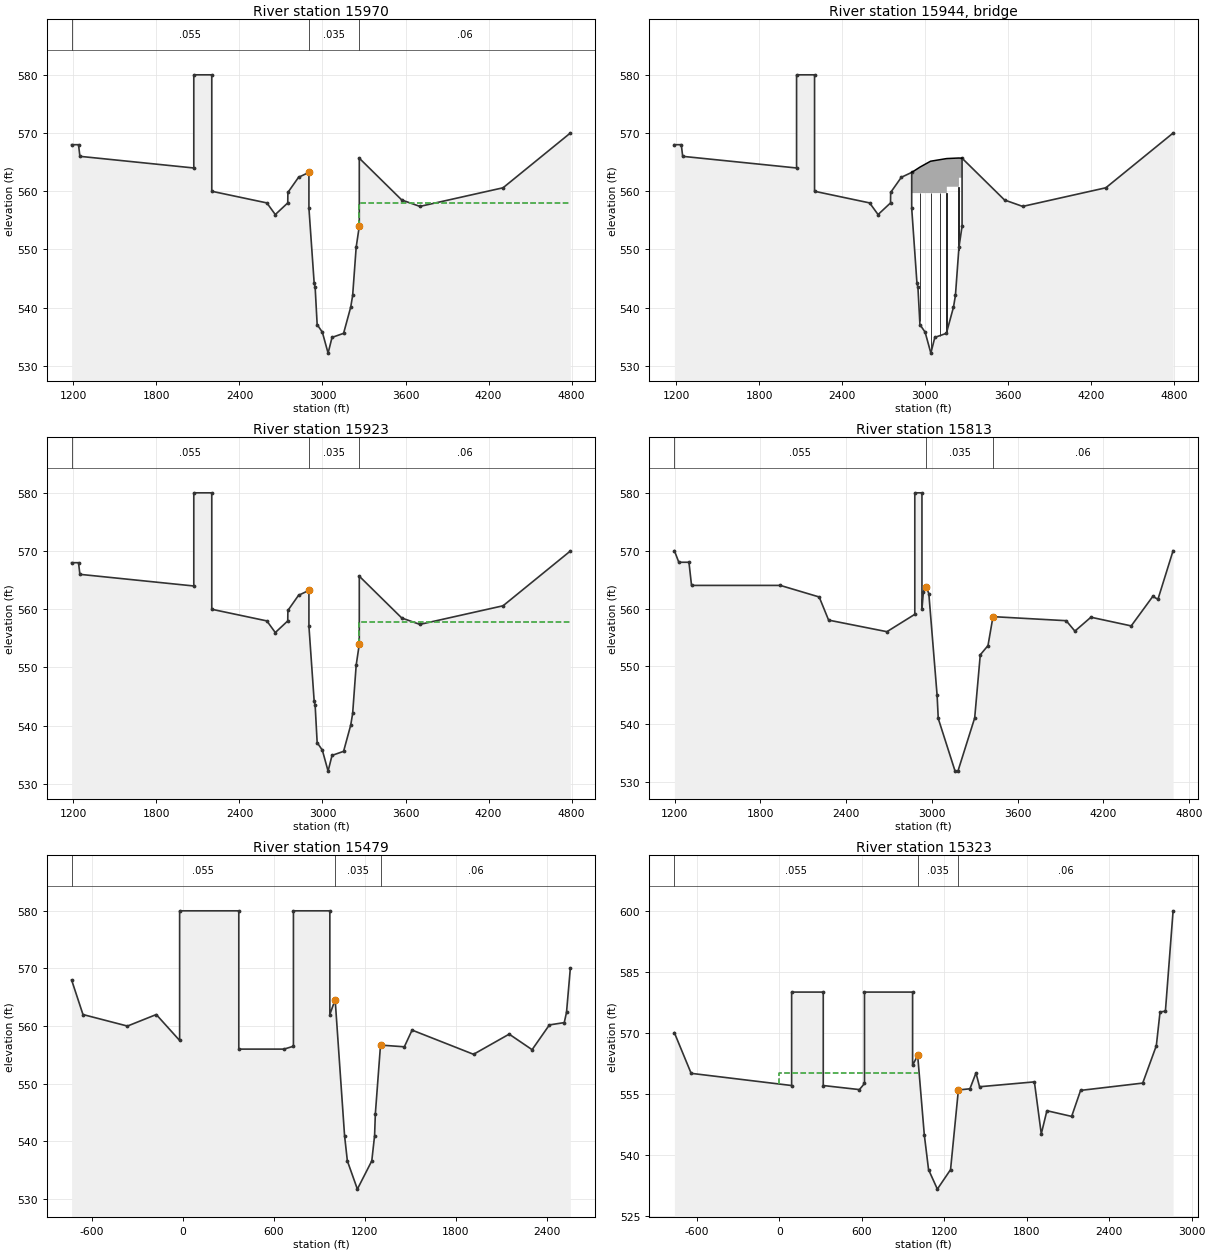
Type RM Length L Ch R = 1 ,15970   ,47,47,47
BEGIN DESCRIPTION:
This cross section corresponds to cross section 16100 of the non-georeferenced CDC model which was the source of this model.
END DESCRIPTION:
XS GIS Cut Line= 6
2317594.906185376949892.29728648 2318001.2283611 6949482.7146309
 2318367.1413511 6949090.6097709 2318703.5212511 6948750.5507409
 2318704.3982211 6946790.95459092318704.421862166946738.12845331
#Sta/Elev= 30
    1187     568    1237     568    1247     566    2070     564    2070     580
    2200     580    2200     560    2598     558    2659     556    2749     558
    2750   559.8    2827   562.4    2902  563.24    2902   557.1    2940   544.2
    2947   543.5  2961.5   537.1    2999   535.8  3040.5   532.2    3069   534.9
  3152.5   535.6    3204   540.1    3218   542.1  3243.5   550.4    3266     554
    3266  565.68    3573   558.5    3704   557.4    4305   560.6    4791     570
#Mann= 3 ,0,0
    1187    .055       0    2902    .035       0    3266     .06       0
#XS Ineff= 2 , 0
       0    2902     560    3266       0  557.93
Permanent Ineff=
       F       F
Bank Sta=2902,3266
XS Rating Curve= 0 ,0
Exp/Cntr=0.5,0.3

Type RM Length L Ch R = 3 ,15944   ,,,
BEGIN DESCRIPTION:
University Drive - north bound
Downstream face of bridge.  Bridge data from July 1975 survey, bridge plans.
Double bridges - both bridges represented.  Downstream bridge: minimum low chord elev. 559.69.  Bridge width 45 feet.  Ineffective flow areas defined in LOB due to structures.
Channel data from 1975 USACE field survey.
END DESCRIPTION:
Node Name=University Drive
Bridge Culvert--1,0,-1,-1, 0
Deck Dist Width WeirC Skew NumUp NumDn MinLoCord MaxHiCord MaxSubmerge Is_Ogee
1,43,2.6,0, 15, 15, , , 0.95, 0, 0,0,,
    2902    2950    2959  2961.5    3038  3040.5  3106.5    3109  3152.5    3156
    3156    3240  3243.5  3243.5    3266
  563.24  563.97  564.11  564.15  565.16  565.17  565.43  565.44  565.61  565.62
  565.62  565.71  565.71  565.71  565.68
  559.69  559.69  559.69  559.69  559.69  559.69  559.69  559.69  559.69  559.69
  560.78  560.78  560.78  562.33  562.33
    2902    2950    2959  2961.5    3038  3040.5  3106.5    3109  3152.5    3156
    3156    3240  3243.5  3243.5    3266
  563.24  563.97  564.11  564.15  565.16  565.17  565.43  565.44  565.61  565.62
  565.62  565.71  565.71  565.71  565.68
  559.69  559.69  559.69  559.69  559.69  559.69  559.69  559.69  559.69  559.69
  560.78  560.78  560.78  562.33  562.33
Pier Skew, UpSta & Num, DnSta & Num=  ,2960.25, 2 ,2960.25, 2 , 0 , 0 , 0 ,,
     2.5     2.5
       0     560
     2.5     2.5
       0     560
Pier Skew, UpSta & Num, DnSta & Num=  ,3039.25, 2 ,3039.25, 2 , 0 , 0 , 0 ,,
     2.5     2.5
       0     560
     2.5     2.5
       0     560
Pier Skew, UpSta & Num, DnSta & Num=  ,3107.75, 2 ,3107.75, 2 , 0 , 0 , 0 ,,
     2.5     2.5
       0     560
     2.5     2.5
       0     560
Pier Skew, UpSta & Num, DnSta & Num=  ,3154.25, 2 ,3154.25, 2 , 0 , 0 , 0 ,,
     3.5     3.5
       0     561
     3.5     3.5
       0     561
Pier Skew, UpSta & Num, DnSta & Num=  ,3241.75, 2 ,3241.75, 2 , 0 , 0 , 0 ,,
     3.5     3.5
       0     563
     3.5     3.5
       0     563
BR Coef=-1 , 0 , 0 ,1.05, 0 ,,,0.8,-1,0.5,1,
WSPro=,,,, 1 ,,,, 0 ,,,, 0 ,,,,-1 ,-1 ,-1 , 0 , 0 , 0 , 0 , 0
BC Design=,, 0 ,, 0 ,,,,,,
BC HTab HWMax=580
BC Use User HTab Curves=0
BC User HTab FreeFlow(D)= 0

Type RM Length L Ch R = 1 ,15923   ,36.33,36.33,32
BEGIN DESCRIPTION:
This cross section corresponds to cross section 16054 of the non-georeferenced CDC model which was the source of this model.
One-foot downstream of University Drive North.  Duplication of following bridge cross-section without bridge piers.
Ineffective flow areas defined in LOB due to structures.
Channel data from 1975 USACE field survey.
END DESCRIPTION:
XS GIS Cut Line= 6
2317638.01927849 6949909.6738694  2317675.223434  6949872.171174
 2318044.3414547  6949500.091214 2318410.2544447  6949107.986354
 2318746.6343447  6948767.9273242318747.534955766946755.50503662
#Sta/Elev= 30
    1187     568    1237     568    1247     566    2070     564    2070     580
    2200     580    2200     560    2598     558    2659     556    2749     558
    2750   559.8    2827   562.4    2902  563.24    2902   557.1    2940   544.2
    2947   543.5  2961.5   537.1    2999   535.8  3040.5   532.2    3069   534.9
  3152.5   535.6    3204   540.1    3218   542.1  3243.5   550.4    3266     554
    3266  565.68    3573   558.5    3704   557.4    4305   560.6    4791     570
#Mann= 3 ,0,0
    1187    .055       0    2902    .035       0    3266     .06       0
#XS Ineff= 2 , 0
       0    2902     560    3266       0  557.84
Permanent Ineff=
       F       F
Bank Sta=2902,3266
XS Rating Curve= 0 ,0
Exp/Cntr=0.5,0.3

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
Type RM Length L Ch R = 1 ,15813   ,334,334,1313
BEGIN DESCRIPTION:
This cross section corresponds to cross section 15948 of the non-georeferenced CDC model which was the source of this model.
107 feet downstream of University Drive.  Forest Park
area in ROB.  Ineffective flow areas defined in LOB due to structures.
Channel data from 1975 USACE field survey.
Downstream limit of Rogers Road trailhead project. PRoject consists of lower and upper trails and fishing pier.
END DESCRIPTION:
XS GIS Cut Line= 6
2317625.259720596949964.85558023   2318040.44204   6949555.05209
   2318509.97489   6949091.04088   2318847.85184   6948736.20399
   2318845.97094   6946981.083162318845.970493786946980.66677889
#Sta/Elev= 30
    1198     570    1229     568    1300     568    1318     564    1939     564
    2211     562    2277     558    2685     556    2880     559    2880     580
    2930     580    2930   559.9    2940   562.9    2958   563.8    2978   562.6
    3036     545    3044     541 3161.76   531.9 3181.76   531.9    3299   541.1
    3338     552    3392   553.6    3427   558.6    3939   557.9    4000   556.1
    4112   558.5    4394     557    4545   562.1    4581   561.6    4687     570
#Mann= 3 ,0,0
    1198    .055       0    2958    .035       0    3427     .06       0
#XS Ineff= 2 , 0
       0    2958     560    3427       0   556.3
Permanent Ineff=
       F       F
Bank Sta=2958,3427
XS Rating Curve= 0 ,0
Exp/Cntr=0.3,0.1

Type RM Length L Ch R = 1 ,15479   ,156,156,661
BEGIN DESCRIPTION:
This cross section corresponds to cross section 15613 of the non-georeferenced CDC model which was the source of this model.
Forest Park area in ROB.
Ineffective flow areas defined in LOB due to structures.
Channel data from 1975 USACE field survey.
END DESCRIPTION:
XS GIS Cut Line= 6
2317713.435885536950028.96856099   2318004.04611   6949759.11796
   2318435.84807   6949350.02986   2319001.02804   6948838.04696
   2319462.18099   6948283.821042319610.39107188 6947485.4434045
#Sta/Elev= 30
    -732     568    -657     562    -364     560    -174     562     -20   557.5
     -20     580     370     580     370     556     668     556     730   556.5
     730     580     970     580     970     562    1005   564.6    1067     541
 1085.46   536.6 1151.46   531.7 1246.46   536.6    1265     541    1270   544.8
    1304   556.7    1461   556.4    1512   559.3    1917   555.1    2152   558.6
    2303   555.9    2417   560.2    2515   560.6    2530   562.4    2555     570
#Mann= 3 ,0,0
    -732    .055       0    1005    .035       0    1304     .06       0
#XS Ineff= 2 , 0
       0    1005     560    1512       0  557.17
Permanent Ineff=
       F       F
Bank Sta=1005,1304
XS Rating Curve= 0 ,0
Exp/Cntr=0.3,0.1

Type RM Length L Ch R = 1 ,15323   ,491,491,1173
BEGIN DESCRIPTION:
This cross section corresponds to cross section 15442 of the non-georeferenced CDC model which was the source of this model.
Forest Park area in ROB.
Ineffective flow areas defined in LOB due to structures.
Channel data from 1975 USACE field survey.
END DESCRIPTION:
XS GIS Cut Line= 5
   2317745.28088   6950108.14908   2318127.78799   6949756.36206
   2318680.07987   6949268.90896   2319077.32907   6948940.89092
   2320617.25414   6947888.42386
#Sta/Elev= 30
    -763     570    -641     560      90     557      90     580     320     580
     320     557     583     556     620   557.5     620     580     970     580
     970     562    1007   564.4    1055   544.9 1086.07   536.3 1150.07   531.5
 1246.07   536.3    1303   555.9    1387   556.2    1431   560.1    1457   556.7
    1856   557.9    1906   545.1    1947   550.8    2127   549.4    2192   555.8
    2644   557.6    2743   566.8    2770   575.1    2809   575.3    2865     600
#Mann= 3 ,0,0
    -763    .055       0    1007    .035       0    1303     .06       0
#XS Ineff= 2 , 0
       0    1007     560    1414       0  557.22
Permanent Ineff=
       F       F
Bank Sta=1007,1303
XS Rating Curve= 0 ,0
Exp/Cntr=0.3,0.1