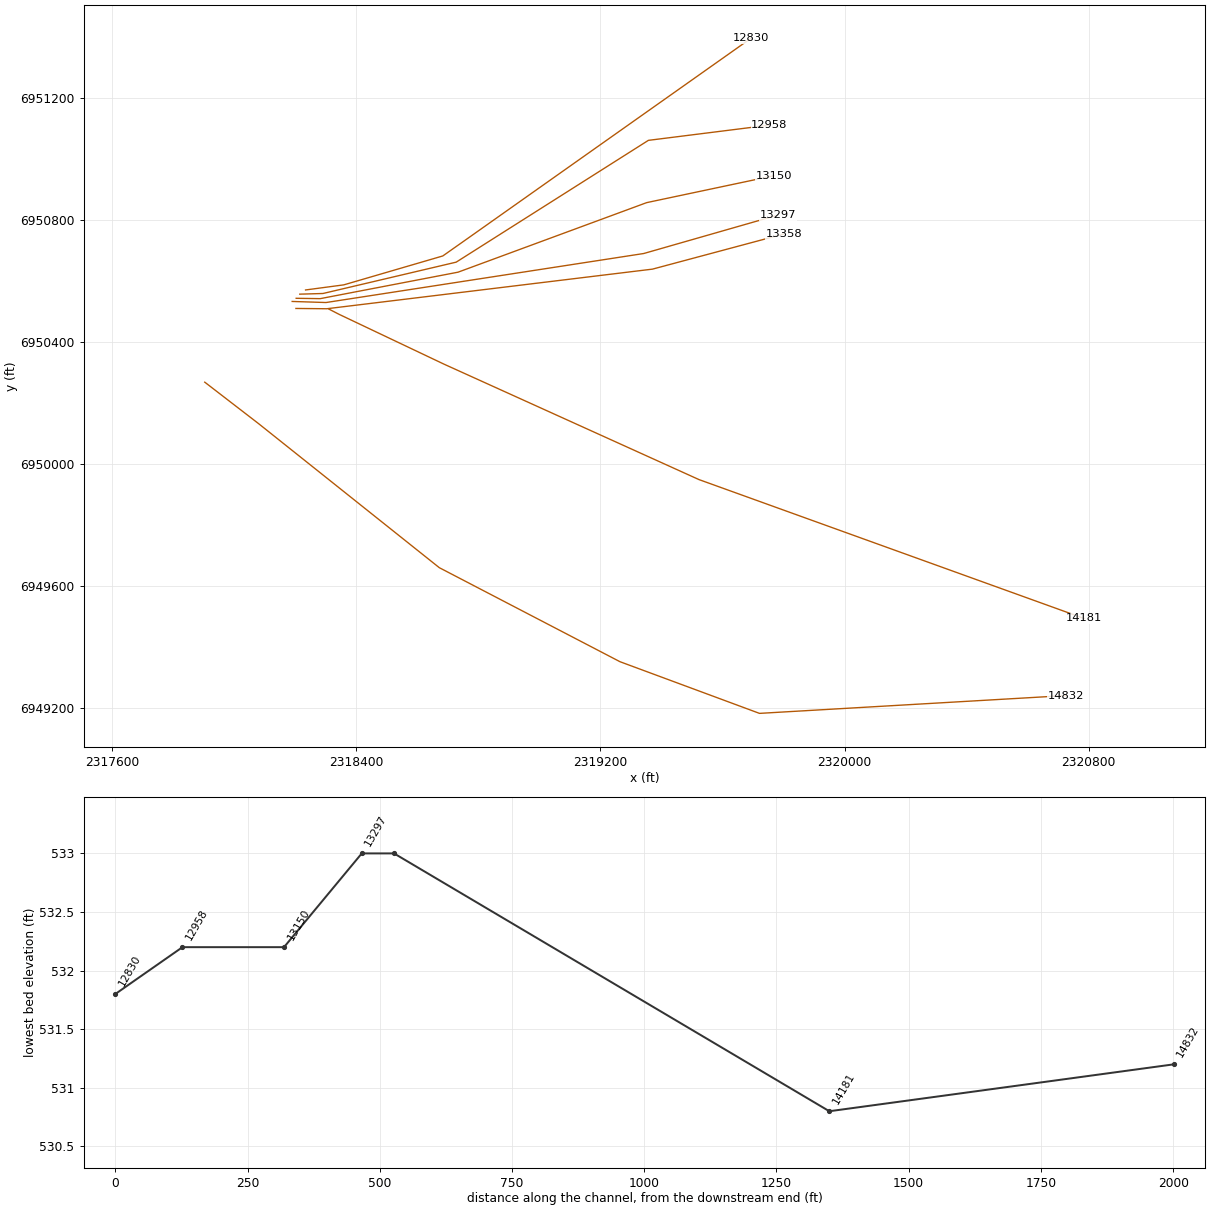
HEC-RAS study CDC_Consolidated_Model.prj: Upper Trinity CDC Consolidated Model

--- CDC_Consolidated_Model.g03 (geometry) --- (continued)

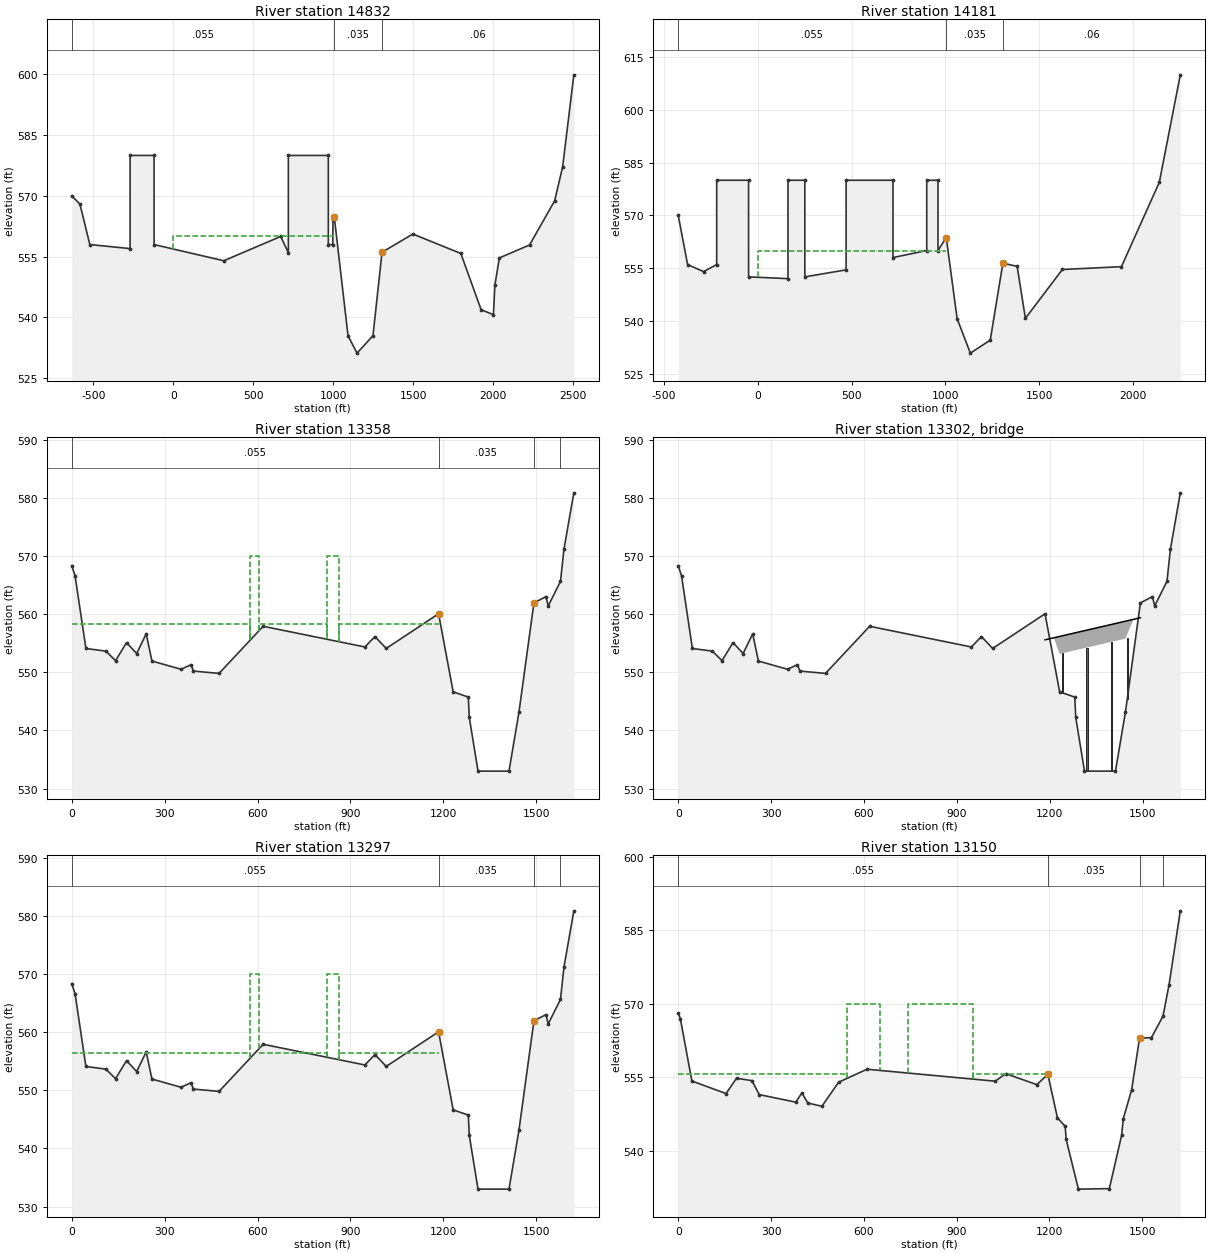
Type RM Length L Ch R = 1 ,14832   ,651,651,751
BEGIN DESCRIPTION:
This cross section corresponds to cross section 14949 of the non-georeferenced CDC model which was the source of this model.
Forest Park area in ROB.  Old Clear Fork channel in ROB.
Ineffective flow areas defined in LOB due to structures.
Channel data from 1975 USACE field survey.
END DESCRIPTION:
XS GIS Cut Line= 6
2317903.653431026950268.95445459   2318080.05909   6950132.94792
   2318672.07299   6949660.78285   2319264.10888   6949352.45505
   2319721.08796   6949183.104022320725.533828776949241.54996478
#Sta/Elev= 30
    -635     570    -584     568    -522     558    -270     557    -270     580
    -120     580    -120     558     316     554     672     560     720     556
     720     580     970     580     970     558     998     558     999     564
    1007   564.9 1093.33   535.5 1149.33   531.2 1249.33   535.5    1306   556.1
    1499   560.6    1799   555.8    1926   541.9    2003   540.7    2012     548
    2040   554.7    2229   557.9    2386   568.8    2436   577.2    2506   599.9
#Mann= 3 ,0,0
    -635    .055       0    1007    .035       0    1306     .06       0
#XS Ineff= 2 , 0
       0    1007     560    1389       0  556.86
Permanent Ineff=
       F       F
Bank Sta=1007,1306
XS Rating Curve= 0 ,0
Exp/Cntr=0.3,0.1

Type RM Length L Ch R = 1 ,14181   ,823,823,1175
BEGIN DESCRIPTION:
This cross section corresponds to cross section 14297 of the non-georeferenced CDC model which was the source of this model.
Forest Park area in ROB.  Old Clear Fork channel in ROB.
Ineffective flow areas defined in LOB due to structures.
Channel data from 1975 USACE field survey.
END DESCRIPTION:
XS GIS Cut Line= 6
      2318310.29      6950508.57     2318343.781   6950491.35894
    2318687.4099     6950328.043   2319522.80587   6949949.57886
   2320700.21395   6949524.753922320784.918225846949494.19145868
#Sta/Elev= 30
    -425     570    -375     556    -290     554    -220     556    -220     580
     -50     580     -50   552.5     160     552     160     580     250     580
     250   552.5     470   554.5     470     580     720     580     720     558
     900     560     900     580     960     580     960     560    1004   563.7
    1062   540.6 1132.66   530.8 1238.66   534.5    1306   556.4    1382   555.5
    1426   540.7    1623   554.6    1938   555.4    2140   579.4    2252     610
#Mann= 3 ,0,0
    -425    .055       0    1004    .035       0    1306     .06       0
#XS Ineff= 2 , 0
       0    1004     560    1306       0     555
Permanent Ineff=
       F       F
Bank Sta=1004,1306
XS Rating Curve= 0 ,0
Exp/Cntr=0.5,0.3

Type RM Length L Ch R = 1 ,13358   ,61,61,61
BEGIN DESCRIPTION:
This cross section corresponds to cross section 13401.58 of the non-georeferenced CDC model which was the source of this model.
Upstream of Miniature Railroad.
**********************************************
Upstream end of mapping for the Central City project.  The CDC Model (with modifications) is used upstream of this point.
**********************************************
END DESCRIPTION:
XS GIS Cut Line= 4
2318202.433139126950510.60491908 2318303.4609327 6950509.6702891
 2319370.6109747 6950639.55256742319800.850475176950754.78155973
#Sta/Elev= 30
       0  568.37    10.7   566.6   45.68  554.11  110.45  553.65  141.36  552.01
  176.88  555.12   209.5  553.24  240.43  556.63  258.85  551.95  352.94  550.53
  384.72  551.31  393.02  550.22  475.61  549.82   618.1  557.93  946.55  554.37
  979.19  556.16  1015.5  554.12 1184.59  560.08 1231.73  546.65 1280.65  545.74
 1283.79  542.24    1312     533    1412     533  1444.1   543.1 1492.58  561.96
 1531.39  563.04  1538.7  561.44 1578.33  565.66  1589.6  571.23 1621.46   580.9
#Mann= 4 ,-1,0
       0    .055       0 1184.59    .035       0 1492.58    .055       0
 1578.33     .15       0
#XS Ineff= 5 ,-1
  823.03  861.57     570  576.08  603.85     570       0  576.08   558.3
  603.85  823.03   558.3  861.57 1184.59   558.3
Permanent Ineff=
       F       F       F       F       F
Bank Sta=1184.59,1492.58
XS Rating Curve= 0 ,0
Exp/Cntr=0.5,0.3

Type RM Length L Ch R = 3 ,13302   ,,,
BEGIN DESCRIPTION:
Miniature Railroad
Data from bridge plans. Bridge is skewed - modeled bridge is a representation of the  skewed bridge projected across the river channel.
END DESCRIPTION:
Node Name=Miniature Railro
Bridge Culvert--1,0,-1,-1, 0
Deck Dist Width WeirC Skew NumUp NumDn MinLoCord MaxHiCord MaxSubmerge Is_Ogee
1,10,2.6,0, 2, 2, , , 0.95, 0, 0,0,,
 1184.59 1492.58
   555.6   559.4
   552.6   556.4
 1184.59 1492.58
   555.6   559.4
   552.6   556.4
Pier Skew, UpSta & Num, DnSta & Num=  ,1240, 2 ,1240, 2 , 0 , 0 , 0 ,,
     3.5     3.5
     450     554
     3.5     3.5
     450     554
Pier Skew, UpSta & Num, DnSta & Num=  ,1320, 2 ,1320, 2 , 0 , 0 , 0 ,,
     3.5     3.5
     450     556
     3.5     3.5
     450     556
Pier Skew, UpSta & Num, DnSta & Num=  ,1400, 2 ,1400, 2 , 0 , 0 , 0 ,,
     3.5     3.5
     450     556
     3.5     3.5
     450     556
Pier Skew, UpSta & Num, DnSta & Num=  ,1450, 2 ,1450, 2 , 0 , 0 , 0 ,,
     3.5     3.5
     450     556
     3.5     3.5
     450     556
BR Coef=-1 , 0 , 0 ,, 0 ,,,0.8,-1,,0,
WSPro=,,,, 1 ,,,, 0 ,,,, 0 ,,,,-1 ,-1 ,-1 , 0 , 0 , 0 , 0 , 0
BC Design=,, 0 ,, 0 ,,,,,,
BC Use User HTab Curves=0
BC User HTab FreeFlow(D)= 0

Type RM Length L Ch R = 1 ,13297   ,147,147,147
BEGIN DESCRIPTION:
This cross section corresponds to cross section 13389.58 of the non-georeferenced CDC model which was the source of this model.
Downstream of Miniature Railroad.
Copy of cross-section 13401.58
END DESCRIPTION:
XS GIS Cut Line= 4
 2318190.0711275 6950533.5706271  2318300.975837 6950530.0492809
 2319341.9315595 6950690.7510344 2319781.4438673 6950816.7424496
#Sta/Elev= 30
       0  568.37    10.7   566.6   45.68  554.11  110.45  553.65  141.36  552.01
  176.88  555.12   209.5  553.24  240.43  556.63  258.85  551.95  352.94  550.53
  384.72  551.31  393.02  550.22  475.61  549.82   618.1  557.93  946.55  554.37
  979.19  556.16  1015.5  554.12 1184.59  560.08 1231.73  546.65 1280.65  545.74
 1283.79  542.24    1312     533    1412     533  1444.1   543.1 1492.58  561.96
 1531.39  563.04  1538.7  561.44 1578.33  565.66  1589.6  571.23 1621.46   580.9
#Mann= 4 ,-1,0
       0    .055       0 1184.59    .035       0 1492.58    .055       0
 1578.33     .15       0
#XS Ineff= 5 ,-1
  823.03  861.57     570  576.08  603.85     570       0  576.08   556.5
  603.85  823.03   556.5  861.57 1184.59   556.5
Permanent Ineff=
       F       F       F       F       F
Bank Sta=1184.59,1492.58
XS Rating Curve= 0 ,0
Exp/Cntr=0.5,0.3

Type RM Length L Ch R = 1 ,13150   ,192,192,181
BEGIN DESCRIPTION:
This cross section corresponds to cross section 13253.36 of the non-georeferenced CDC model which was the source of this model.
END DESCRIPTION:
XS GIS Cut Line= 5
 2318203.2053612 6950543.8905581 2318281.9800391 6950542.7763229
  2318733.595832 6950629.5690866 2319351.5889127 6950857.5834798
 2319768.4874964 6950945.8471117
#Sta/Elev= 30
       0  568.11    6.85  566.97   44.08  554.25  154.49  551.69   188.4   554.8
  238.06  554.33  262.18  551.47  379.66  549.94  399.84  551.79  419.34  549.75
  464.53   549.1  518.62     554  610.37  556.65 1025.29  554.21 1058.82  555.75
 1159.51  553.51 1195.18  555.61 1226.23  546.73 1251.32     545 1254.36  542.35
    1294   532.2    1394   532.3 1433.81  543.19 1439.01  546.51 1466.31  552.51
 1491.67  562.96 1530.35  563.11 1567.67   567.5 1587.17   573.9 1623.52  588.95
#Mann= 4 ,-1,0
       0    .055       0 1195.18    .035       0 1491.67    .055       0
 1567.67     .15       0
#XS Ineff= 5 ,-1
  743.64  954.08     570  546.05  652.11     570       0  546.05  555.61
  652.11  743.64  555.61  954.08 1195.18  555.61
Permanent Ineff=
       F       F       F       F       F
Bank Sta=1195.18,1491.67
XS Rating Curve= 0 ,0
Exp/Cntr=0.3,0.1

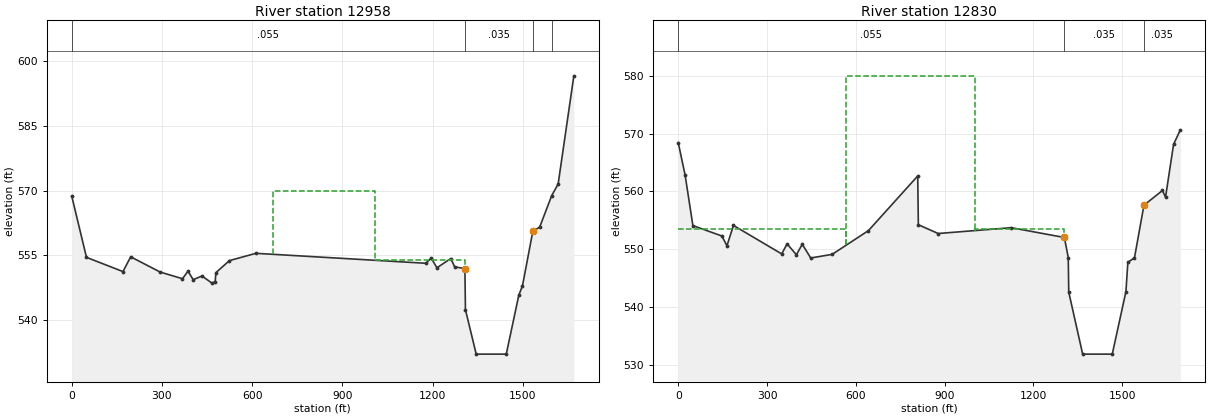
Type RM Length L Ch R = 1 ,12958   ,127,127,283
BEGIN DESCRIPTION:
This cross section corresponds to cross section 13062.82 of the non-georeferenced CDC model which was the source of this model.
END DESCRIPTION:
XS GIS Cut Line= 5
 2318214.9321194 6950557.4936909 2318290.9828521 6950559.6447677
 2318727.4254711 6950662.4199032 2319357.0484707 6951061.7114967
 2319753.6349163 6951111.6058985
#Sta/Elev= 30
       0  568.68    48.9  554.56  170.29  551.27  195.93  554.68  294.11  551.16
  368.22  549.62  386.65  551.38  403.72   549.4  433.13  550.25  465.96  548.62
   476.9  548.93  479.34  551.03  524.46  553.81  612.32  555.49 1177.79  553.19
 1195.44   554.4 1214.31  552.14 1260.46  554.29  1273.6  552.34 1307.42  551.98
 1309.19  542.48    1345   532.2    1445   532.2 1486.78  545.84 1498.88  547.97
 1533.42  560.62 1556.06  561.54  1596.1  568.82 1617.54   571.5 1669.73   596.5
#Mann= 4 ,-1,0
       0    .055       0 1307.42    .035       0 1533.42    .055       0
  1596.1     .15       0
#XS Ineff= 3 ,-1
  669.18 1007.63     570       0  669.18     554 1007.63 1307.42     554
Permanent Ineff=
       F       F       F
Bank Sta=1307.42,1533.42
XS Rating Curve= 0 ,0
Exp/Cntr=0.5,0.3

Type RM Length L Ch R = 1 ,12830   ,132,132,132
BEGIN DESCRIPTION:
This cross section corresponds to cross section 12901.55 of the non-georeferenced CDC model which was the source of this model.
Upstream of Rosedale Street.
At USGS gaging station 08048000 - Clear Fork at Trinity River Gage - located on left bank of Clear Fork at Fort Worth pumping station.  Gage datum elev. 532.91 MSL.
END DESCRIPTION:
Node Name=CF Gage
XS GIS Cut Line= 5
 2318233.9293414 6950571.2318326 2318359.2859677 6950587.9888604
  2318683.553314  6950682.742234 2318753.2063553 6950731.7946253
 2319692.9640904 6951396.1822523
#Sta/Elev= 30
       0  568.42   23.32  562.79   49.54  554.06  147.46  552.26  164.66  550.57
  186.68  554.09   349.6  549.16  368.07  550.89  399.33  549.01  419.24  550.83
  447.78  548.45  520.29  549.08   642.9  553.19  809.53  562.66   811.6  554.21
  878.59  552.69 1125.73   553.7 1305.16     552 1318.26  548.53 1319.95  542.54
    1367   531.8    1467   531.8 1513.21  542.61 1519.74   547.7 1542.14  548.49
 1574.14  557.59 1636.68  560.14 1647.14  558.98 1674.25  568.14 1697.04  570.62
#Mann= 3 ,0,0
       0    .055       0 1305.16    .035       0 1574.14    .035       0
#XS Ineff= 3 ,-1
  567.78 1003.13     580       0  567.78  553.44 1003.13 1305.16  553.44
Permanent Ineff=
       F       F       F
Bank Sta=1305.16,1574.14
XS Rating Curve= 0 ,0
Exp/Cntr=0.5,0.3