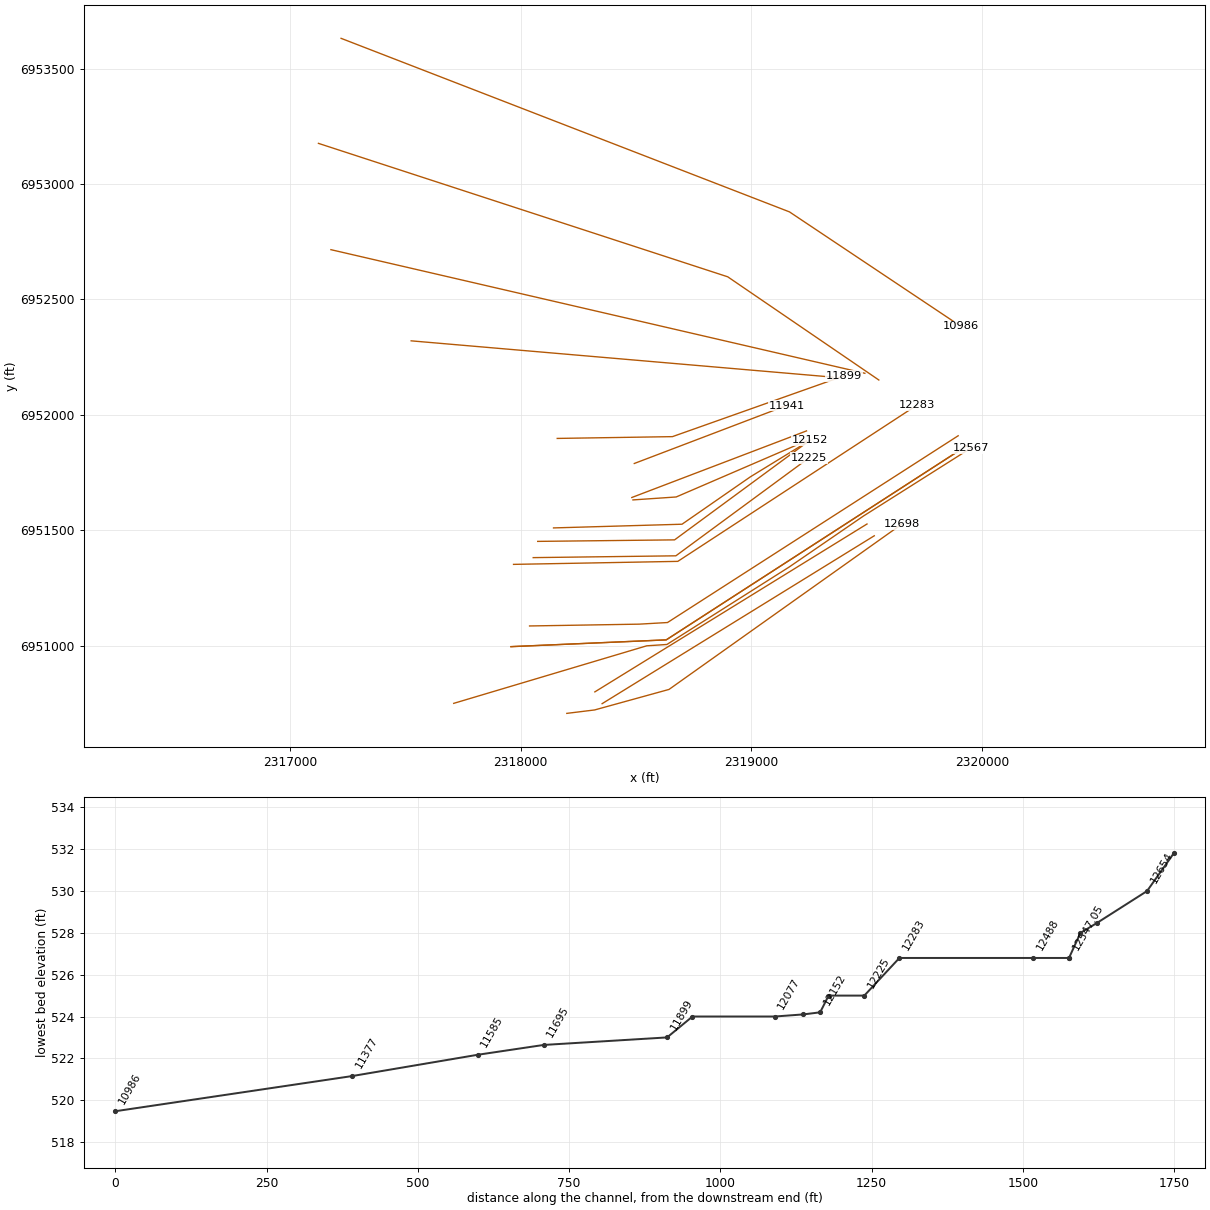
HEC-RAS study CDC_Consolidated_Model.prj: Upper Trinity CDC Consolidated Model

--- CDC_Consolidated_Model.g03 (geometry) --- (continued)

Type RM Length L Ch R = 3 ,12758   ,,,
BEGIN DESCRIPTION:
Rosedale Street and Vickery Connection
Data from TXDOT bridge plans.  Eastbound connection represented.
END DESCRIPTION:
Node Name=Rosedale Street
Bridge Culvert--1,0,-1,-1, 0
Deck Dist Width WeirC Skew NumUp NumDn MinLoCord MaxHiCord MaxSubmerge Is_Ogee
11,120,2.6,0, 14, 14, , , 0.95, 0, 0,0,,
       0   93.04  117.04  166.04  166.04  682.04  764.04  847.04 1017.04 1117.04
 1213.04 1321.04 1415.04 1697.04
     610     610     610     609     609     586     581     575     574     574
     574     574     576   577.3
     598     598     597     595     599     577     573     568   567.5     567
     567     568     568     568
       0   93.04  117.04  166.04  166.04  682.04  764.04  847.04 1017.04 1117.04
 1213.04 1321.04 1415.04 1697.04
     610     610     610     609     609     586     581     575     574     574
     574     574     576   577.3
     598     598     597     595     599     577     573     568   567.5     567
     567     568     568     568
Pier Skew, UpSta & Num, DnSta & Num=  ,102, 4 ,102, 4 , 0 , 0 , 0 ,,
     4.5     4.5       3       3
     500     577     577     605
     4.5     4.5       3       3
     500     577     577     605
Pier Skew, UpSta & Num, DnSta & Num=  ,127, 4 ,127, 4 , 0 , 0 , 0 ,,
     4.5     4.5       3       3
     500     577     577     605
     4.5     4.5       3       3
     500     577     577     605
Pier Skew, UpSta & Num, DnSta & Num=  ,157, 4 ,157, 4 , 0 , 0 , 0 ,,
     4.5     4.5       3       3
     500     577     577     605
     4.5     4.5       3       3
     500     577     577     605
Pier Skew, UpSta & Num, DnSta & Num=  ,192, 2 ,192, 2 , 0 , 0 , 0 ,,
     3.5     3.5
     500     605
     3.5     3.5
     500     605
Pier Skew, UpSta & Num, DnSta & Num=  ,207, 2 ,207, 2 , 0 , 0 , 0 ,,
     3.5     3.5
     500     605
     3.5     3.5
     500     605
Pier Skew, UpSta & Num, DnSta & Num=  ,217, 2 ,217, 2 , 0 , 0 , 0 ,,
     3.5     3.5
     500     605
     3.5     3.5
     500     605
Pier Skew, UpSta & Num, DnSta & Num=  ,292, 2 ,292, 2 , 0 , 0 , 0 ,,
     3.5     3.5
     500     605
     3.5     3.5
     500     605
Pier Skew, UpSta & Num, DnSta & Num=  ,387, 2 ,387, 2 , 0 , 0 , 0 ,,
     3.5     3.5
     500     605
     3.5     3.5
     500     605
Pier Skew, UpSta & Num, DnSta & Num=  ,497, 2 ,497, 2 , 0 , 0 , 0 ,,
     3.5     3.5
     500     605
     3.5     3.5
     500     605
Pier Skew, UpSta & Num, DnSta & Num=  ,597, 2 ,597, 2 , 0 , 0 , 0 ,,
       3       3
     500     605
       3       3
     500     605
Pier Skew, UpSta & Num, DnSta & Num=  ,682, 2 ,682, 2 , 0 , 0 , 0 ,,
       3       3
     500     605
       3       3
     500     605
Pier Skew, UpSta & Num, DnSta & Num=  ,764, 2 ,764, 2 , 0 , 0 , 0 ,,
       3       3
     500     605
       3       3
     500     605
Pier Skew, UpSta & Num, DnSta & Num=  ,847, 2 ,847, 2 , 0 , 0 , 0 ,,
       3       3
     500     605
       3       3
     500     605
Pier Skew, UpSta & Num, DnSta & Num=  ,932, 2 ,932, 2 , 0 , 0 , 0 ,,
       3       3
     500     605
       3       3
     500     605
Pier Skew, UpSta & Num, DnSta & Num=  ,1017, 2 ,1017, 2 , 0 , 0 , 0 ,,
       3       3
     500     605
       3       3
     500     605
Pier Skew, UpSta & Num, DnSta & Num=  ,1117, 2 ,1117, 2 , 0 , 0 , 0 ,,
     3.5     3.5
     500     605
     3.5     3.5
     500     605
Pier Skew, UpSta & Num, DnSta & Num=  ,1213, 2 ,1213, 2 , 0 , 0 , 0 ,,
     3.5     3.5
     500     605
     3.5     3.5
     500     605
Pier Skew, UpSta & Num, DnSta & Num=  ,1317, 2 ,1317, 2 , 0 , 0 , 0 ,,
     3.5     3.5
     500     605
     3.5     3.5
     500     605
Pier Skew, UpSta & Num, DnSta & Num=  ,1415, 2 ,1415, 2 , 0 , 0 , 0 ,,
     3.5     3.5
     500     605
     3.5     3.5
     500     605
Pier Skew, UpSta & Num, DnSta & Num=  ,1507, 2 ,1507, 2 , 0 , 0 , 0 ,,
     3.5     3.5
     500     605
     3.5     3.5
     500     605
Pier Skew, UpSta & Num, DnSta & Num=  ,1603, 2 ,1603, 2 , 0 , 0 , 0 ,,
       3       3
     500     605
       3       3
     500     605
BR Coef=-1 , 0 , 0 ,, 0 ,,,0.8,-1,,0,
WSPro=,,,, 1 ,,,, 0 ,,,, 0 ,,,,-1 ,-1 ,-1 , 0 , 0 , 0 , 0 , 0
BC Design=,, 0 ,, 0 ,,,,,,
BC Use User HTab Curves=0
BC User HTab FreeFlow(D)= 0

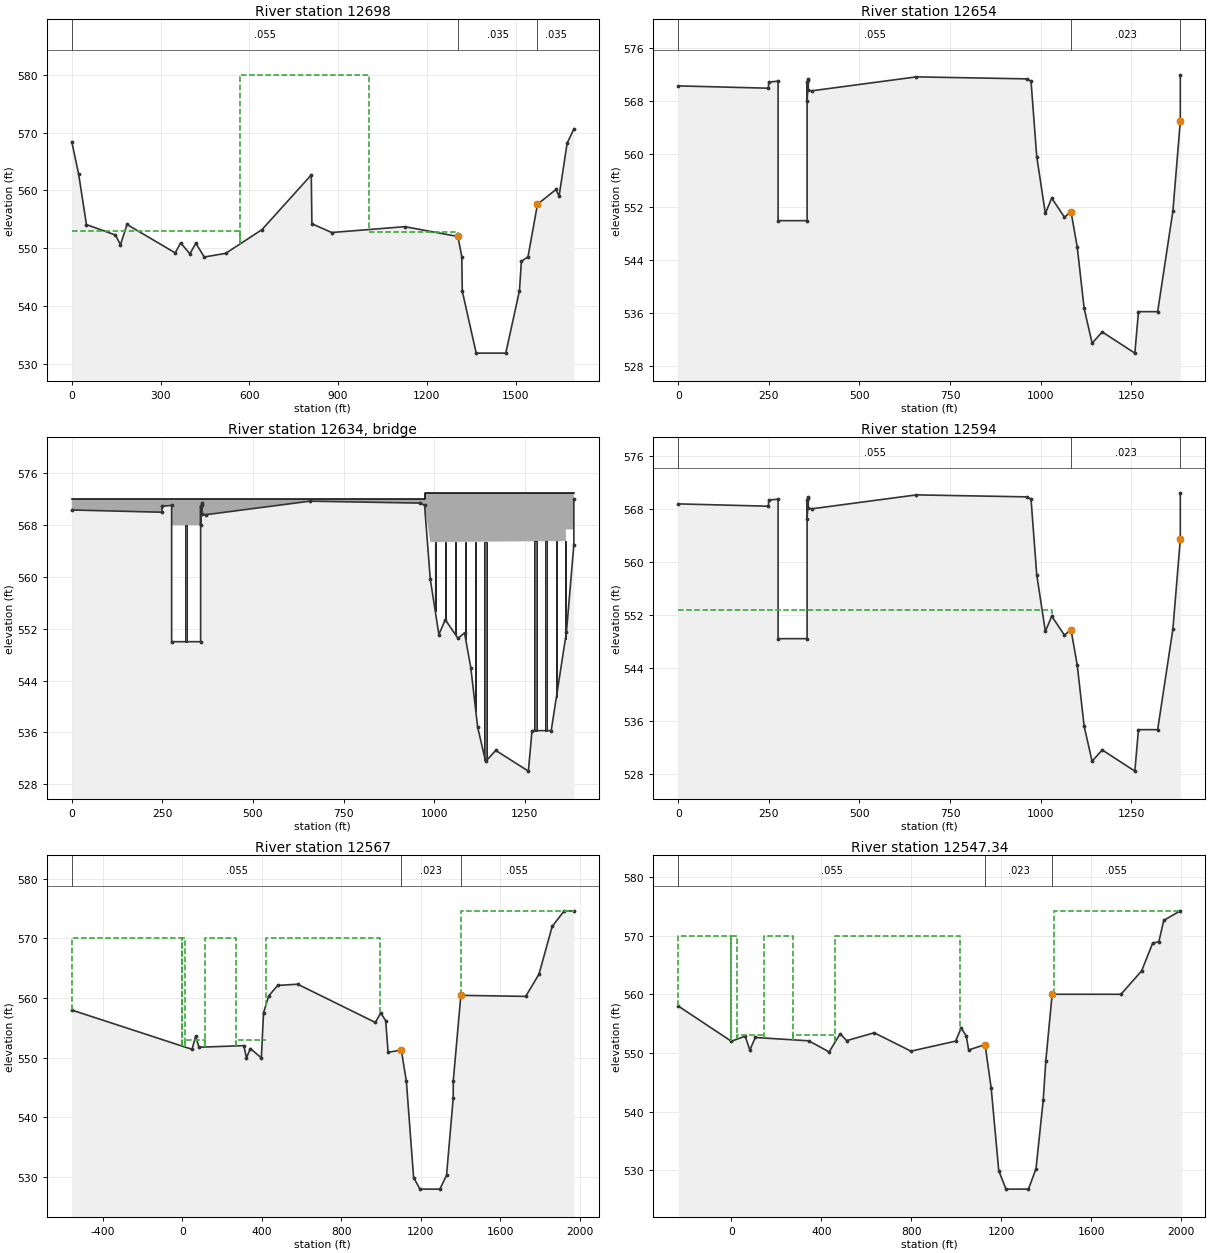
Type RM Length L Ch R = 1 ,12698   ,44,44,44
BEGIN DESCRIPTION:
This cross section corresponds to cross section 12860.85 of the non-georeferenced CDC model which was the source of this model.
Downstream of Rosedale Street.
Copy of cross-section 12901.55
END DESCRIPTION:
XS GIS Cut Line= 4
     2318200.256     6950706.091     2318320.685     6950720.913
     2318643.065     6950809.845     2319652.819     6951526.863
#Sta/Elev= 30
       0  568.42   23.32  562.79   49.54  554.06  147.46  552.26  164.66  550.57
  186.68  554.09   349.6  549.16  368.07  550.89  399.33  549.01  419.24  550.83
  447.78  548.45  520.29  549.08   642.9  553.19  809.53  562.66   811.6  554.21
  878.59  552.69 1125.73   553.7 1305.16     552 1318.26  548.53 1319.95  542.54
    1367   531.8    1467   531.8 1513.21  542.61 1519.74   547.7 1542.14  548.49
 1574.14  557.59 1636.68  560.14 1647.14  558.98 1674.25  568.14 1697.04  570.62
#Mann= 3 ,0,0
       0    .055       0 1305.16    .035       0 1574.14    .035       0
#XS Ineff= 3 ,-1
  567.78 1003.13     580       0  567.78   552.9 1003.13 1305.16   552.7
Permanent Ineff=
       F       F       F
Bank Sta=1305.16,1574.14
XS Rating Curve= 0 ,0
Exp/Cntr=0.5,0.3

Type RM Length L Ch R = 1 ,12654   ,83,83,83
BEGIN DESCRIPTION:
This cross section corresponds to cross section 12733.65 of the non-georeferenced CDC model which was the source of this model.
Upstream of Union Pacific Railroad.
Copy of cross-section 12673.49..
---------------------------------------------------------------------
CDC FW072209-1 UNION PACIFIC RAILROAD BRIDGE
CROSS-SECTION 12617.5 - 12733.65
UPSTREAM END.
---------------------------------------------------------------------
END DESCRIPTION:
XS GIS Cut Line= 2
 2318353.2774795 6950748.1628615 2319532.4170336 6951475.5693008
#Sta/Elev= 30
       0  570.35  248.65     570  249.85  570.93  275.56  571.06  275.56     550
  355.56     550  355.56   570.9   355.6     568  358.75  571.36  358.95  571.18
  358.95  569.66  370.36  569.62  657.13  571.71  961.51  571.41  973.51  571.08
  989.24  559.68 1013.03   551.1 1030.66   553.4 1065.84  550.52 1083.79  551.38
 1101.07     546    1120   536.8    1142   531.5    1170   533.2    1260     530
    1270  536.26    1323  536.26    1365  551.46 1385.46     565 1385.46  572.02
#Mann= 3 ,0,0
       0    .055       0 1083.79    .023       0 1385.46    .055       0
#XS Ineff= 2 , 0
       0 1030.66     553               0
Permanent Ineff=
       F       F
Bank Sta=1083.79,1385.46
XS Rating Curve= 0 ,0
Exp/Cntr=0.5,0.3

Type RM Length L Ch R = 3 ,12634   ,,,
BEGIN DESCRIPTION:
Union Pacific Railroad
Two parallel bridges represented as one bridge.  Older upstream bridge data from USACE 1975 survey, Fort Worth Floodway as-builts plans. Newer downstream bridge data from bridge plans.
END DESCRIPTION:
Node Name=UP RR
Bridge Culvert--1,0,-1,-1, 0
Deck Dist Width WeirC Skew NumUp NumDn MinLoCord MaxHiCord MaxSubmerge Is_Ogee
1.15,81,2.6,0, 12, 12, , , 0.95, 0, 0,0,,
       0  275.56  275.56  355.56  355.56  973.51  973.51  1363.5  1363.5    1385
    1385 1385.46
     572     572     572     572     572     572     573     573     573     573
     573     573
     450     450     568     568     450     450  565.39  565.55  567.35  567.35
     450     450
       0  275.56  275.56  355.56  355.56  973.51  973.51  1363.5  1363.5    1385
    1385 1385.46
     572     572     572     572     572     572     573     573     573     573
     573     573
     450     450     568     568     450     450  565.39  565.55  567.35  567.35
     450     450
Pier Skew, UpSta & Num, DnSta & Num=  ,315.56, 2 ,315.56, 2 , 0 , 0 , 0 ,,
       4       4
     450     571
       4       4
     450     571
Pier Skew, UpSta & Num, DnSta & Num=  ,1003, 2 ,1003, 2 , 0 , 0 , 0 ,,
       3       3
     450     568
       3       3
     450     568
Pier Skew, UpSta & Num, DnSta & Num=  ,1031, 2 ,1031, 2 , 0 , 0 , 0 ,,
       3       3
     450     568
       3       3
     450     568
Pier Skew, UpSta & Num, DnSta & Num=  ,1059, 2 ,1059, 2 , 0 , 0 , 0 ,,
       3       3
     450     568
       3       3
     450     568
Pier Skew, UpSta & Num, DnSta & Num=  ,1087, 2 ,1087, 2 , 0 , 0 , 0 ,,
       3       3
     450     568
       3       3
     450     568
Pier Skew, UpSta & Num, DnSta & Num=  ,1115, 2 ,1115, 2 , 0 , 0 , 0 ,,
       3       3
     450     568
       3       3
     450     568
Pier Skew, UpSta & Num, DnSta & Num=  ,1141.3, 2 ,1141.3, 2 , 0 , 0 , 0 ,,
       8     6.5
     536     568
       8     6.5
     536     568
Pier Skew, UpSta & Num, DnSta & Num=  ,1280.3, 2 ,1280.3, 2 , 0 , 0 , 0 ,,
       8     6.5
     536     568
       8     6.5
     536     568
Pier Skew, UpSta & Num, DnSta & Num=  ,1309.76, 2 ,1309.76, 2 , 0 , 0 , 0 ,,
     5.5     5.5
     450     570
     5.5     5.5
     450     570
Pier Skew, UpSta & Num, DnSta & Num=  ,1337.5, 2 ,1337.5, 2 , 0 , 0 , 0 ,,
       4       4
     450     567
       4       4
     450     567
Pier Skew, UpSta & Num, DnSta & Num=  ,1362, 2 ,1362, 2 , 0 , 0 , 0 ,,
       3       3
     450  565.55
       3       3
     450  565.55
BR Coef=-1 , 0 , 0 ,, 0 ,,,0.8,-1,,0,
WSPro=,,,, 1 ,,,, 0 ,,,, 0 ,,,,-1 ,-1 ,-1 , 0 , 0 , 0 , 0 , 0
BC Design=,, 0 ,, 0 ,,,,,,
BC Use User HTab Curves=0
BC User HTab FreeFlow(D)= 0

Type RM Length L Ch R = 1 ,12594   ,27,27,27
BEGIN DESCRIPTION:
This cross section corresponds to cross section 12650.65 of the non-georeferenced CDC model which was the source of this model.
Downstream of Union Pacific Railroad.
Added cross-section from ground points generated through centerline of railroad bridge.
Data from Fort Worth Floodway as-builts.
END DESCRIPTION:
XS GIS Cut Line= 2
 2318321.7758014 6950799.2278909 2319500.9153555 6951526.6343302
#Sta/Elev= 30
       0  568.82  248.65  568.47  249.85   569.4  275.56  569.53  275.56  548.47
  355.56  548.47  355.56  569.37   355.6  566.47  358.75  569.83  358.95  569.65
  358.95  568.13  370.36  568.09  657.13  570.18  961.51  569.88  973.51  569.55
  989.24  558.15 1013.03  549.57 1030.66  551.87 1065.84  548.99 1083.79  549.85
 1101.07  544.47    1120  535.27    1142  529.97    1170  531.67    1260  528.47
    1270  534.73    1323  534.73    1365  549.93 1385.46  563.47 1385.46  570.49
#Mann= 3 ,0,0
       0    .055       0 1083.79    .023       0 1385.46    .055       0
#XS Ineff= 2 , 0
       0 1030.66  552.75               0
Permanent Ineff=
       F       F
Bank Sta=1083.79,1385.46
XS Rating Curve= 0 ,0
Exp/Cntr=0.5,0.3

Type RM Length L Ch R = 1 ,12567   ,19,19,19
BEGIN DESCRIPTION:
This cross section corresponds to cross section 12643.73 of the non-georeferenced CDC model which was the source of this model.
END DESCRIPTION:
XS GIS Cut Line= 6
2317710.292266236950749.49188663 2318546.5320128 6950998.8029055
 2318633.9443146 6951004.6242821 2319163.1561204 6951339.8461205
 2319485.2754863  6951560.921661 2319949.3936592 6951854.5120687
#Sta/Elev= 30
    -556     558    49.2  551.42   67.23  553.61   84.27  551.77  309.89  552.04
  322.93     550  342.87  551.54     398     550   409.1  557.55  434.74  560.35
  479.94  562.12  580.54  562.33  971.68  555.92  998.71  557.51 1023.69  556.22
 1035.79  550.92 1102.22   551.3  1127.8  546.06 1164.15  529.94 1196.34     528
 1296.34     528 1329.89  530.31 1363.52  543.26 1363.79  546.15 1401.93  560.46
 1728.19  560.29 1795.03     564 1861.42     572  1920.9  574.57 1970.53  574.62
#Mann= 3 ,0,0
    -556    .055       0 1102.22    .023       0 1401.93    .055       0
#XS Ineff= 8 ,-1
 1401.93 1970.53 574.617  115.07  272.54     570       0   12.88     570
  419.42  996.46     570    -556       0     570  272.54  419.42     553
  996.46    1030     553   12.88  115.07     553
Permanent Ineff=
       F       F       F       F       F       F       F       F
Bank Sta=1102.22,1401.93
XS Rating Curve= 0 ,0
Exp/Cntr=0.3,0.1

Type RM Length L Ch R = 1 ,12547.34,0.29,0.29,0.29
BEGIN DESCRIPTION:
This cross section corresponds to cross section 12625.52 of the non-georeferenced CDC model which was the source of this model.
END DESCRIPTION:
XS GIS Cut Line= 3
2317958.157291336950995.05459171  2318631.137271 6951024.4174808
  2319940.155942 6951870.2317947
#Sta/Elev= 30
    -236     558       0     552   61.93  552.86   82.29  550.49  106.58  552.64
  344.34  552.07  435.02  550.18   484.4  553.29  512.75   552.1  635.38  553.44
  798.83  550.31  997.44  552.02 1021.88  554.25 1045.07  552.88 1055.08  550.51
 1128.31  551.43 1155.46     544 1189.11  529.94  1221.3   526.8  1321.3   526.8
 1354.85  530.31 1386.94     542 1398.24  548.58 1426.41     560 1732.52     560
 1824.49     564 1873.55  568.72 1900.93  568.96 1922.83  572.59 1996.35  574.22
#Mann= 3 ,0,0
    -236    .055       0 1128.31    .023       0 1426.41    .055       0
#XS Ineff= 8 ,-1
  1435.6 1996.35 574.215  143.47  274.17     570       0   27.31     570
  463.04  1017.7     570    -236       0     570  274.17  463.04     553
  1017.7 1021.88     553   27.31  143.47     553
Permanent Ineff=
       F       F       F       F       F       F       F       F
Bank Sta=1128.31,1426.41
XS Rating Curve= 0 ,0
Exp/Cntr=0.3,0.1

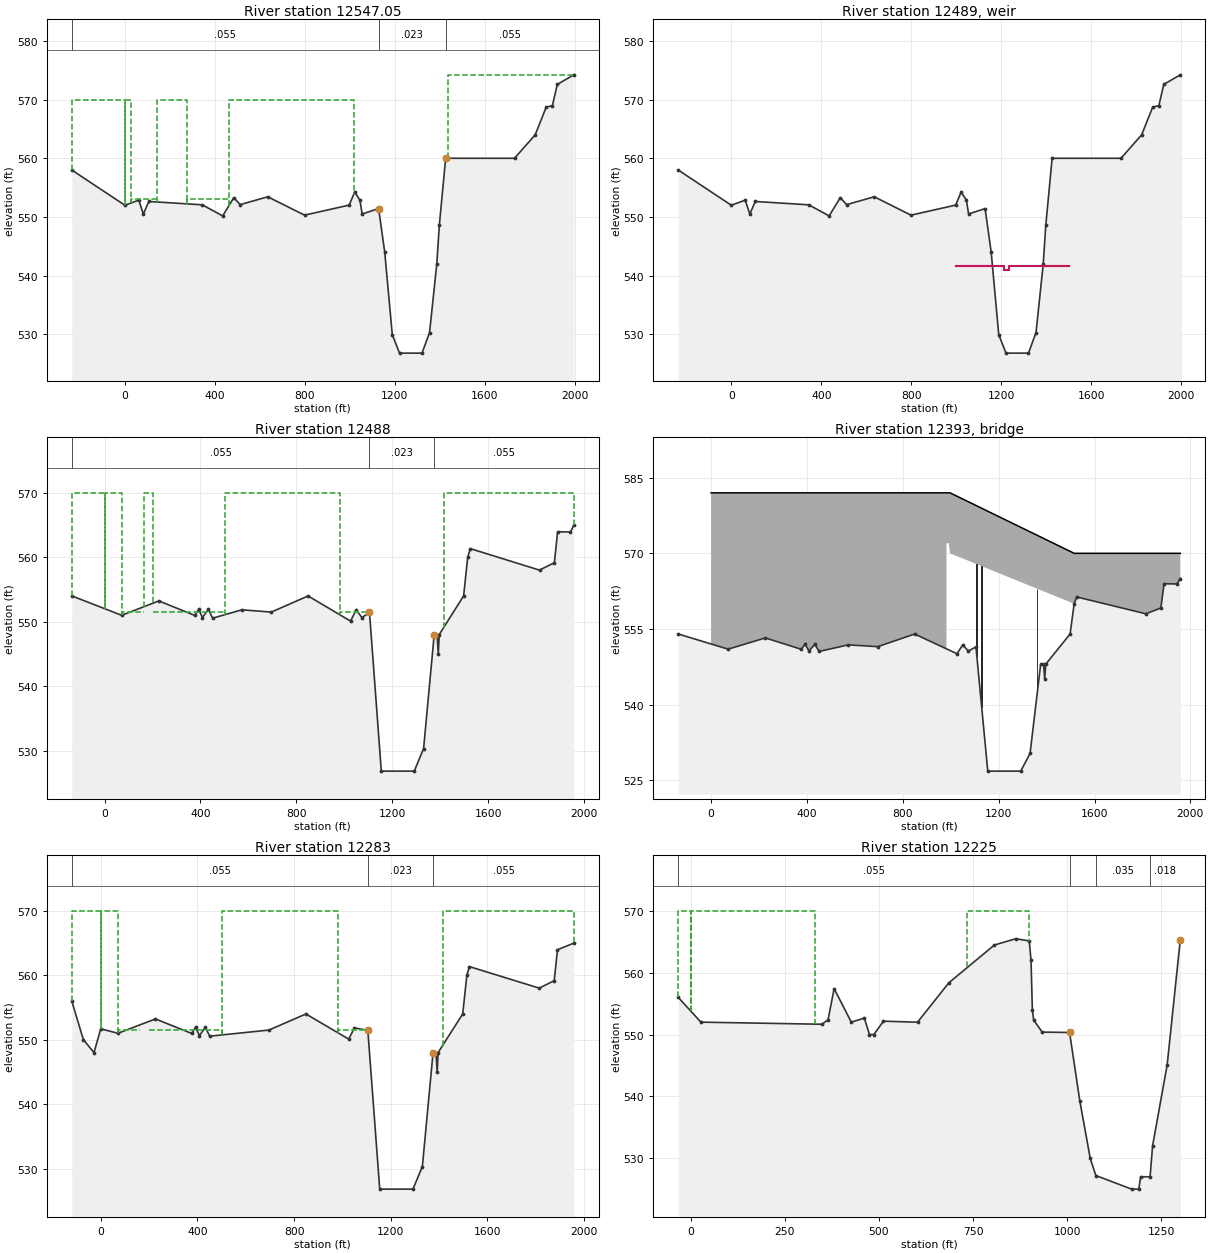
Type RM Length L Ch R = 1 ,12547.05,59,59,59
BEGIN DESCRIPTION:
This cross section corresponds to cross section 12617.75 of the non-georeferenced CDC model which was the source of this model.
Upstream of City Dam No. 2
Copy of cross-section 12625.52.
---------------------------------------------------------------------
CDC FW072209-1 UNION PACIFIC RAILROAD BRIDGE
CROSS-SECTION 12617.5 - 12733.65
DOWNSTREAM END.
---------------------------------------------------------------------
END DESCRIPTION:
XS GIS Cut Line= 4
2317958.194015856950995.31537125    2318193.9699     6951005.598
    2318630.9793    6951024.6568     2319939.957    6951870.4428
#Sta/Elev= 30
    -236     558       0     552   61.93  552.86   82.29  550.49  106.58  552.64
  344.34  552.07  435.02  550.18   484.4  553.29  512.75   552.1  635.38  553.44
  798.83  550.31  997.44  552.02 1021.88  554.25 1045.07  552.88 1055.08  550.51
 1128.31  551.43 1155.46     544 1189.11  529.94  1221.3   526.8  1321.3   526.8
 1354.85  530.31 1386.94     542 1398.24  548.58 1426.41     560 1732.52     560
 1824.49     564 1873.55  568.72 1900.93  568.96 1922.83  572.59 1996.35  574.22
#Mann= 3 ,0,0
    -236    .055       0 1128.31    .023       0 1426.41    .055       0
#XS Ineff= 8 ,-1
  1435.6 1996.35 574.215  143.47  274.17     570       0   27.31     570
  463.04  1017.7     570    -236       0     570  274.17  463.04     553
  1017.7 1021.88     553   27.31  143.47     553
Permanent Ineff=
       F       F       F       F       F       F       F       F
Bank Sta=1128.31,1426.41
XS Rating Curve= 0 ,0
Exp/Cntr=0.5,0.3

Type RM Length L Ch R = 5 ,12489   ,,,
BEGIN DESCRIPTION:
City Dam No. 2
Ogee weir.  Structure weir length 224.7 feet.  Crest elev. 541.6 feet, notch length 20 feet - minimum weir crest elev. 541.0
Data from project plans, design computations.
END DESCRIPTION:
Node Name=City Dam No. 2
IW Pilot Flow=0
#Inline Weir SE= 6
    1000   541.6 1212.83   541.6 1212.83     541 1232.83     541 1232.83   541.6
    1500   541.6
IW Dist,WD,Coef,Skew,MaxSub,Min_El,Is_Ogee,SpillHt,DesHd
1,2,3.88,0,0.95,,-1 ,14.8,15,0,0,
Inline Weir Flap Gates= 0
IW Outlet Rating Curve= 0 ,False,,

Type RM Length L Ch R = 1 ,12488   ,221,221,241
BEGIN DESCRIPTION:
This cross section corresponds to cross section 12568.12 of the non-georeferenced CDC model which was the source of this model.
Upstream of SH121/Southwest Parkway.
---------------------------------------------------------------------
CDC FW111809-01 SH121/SOUTHWEST PARKWAY
CROSS-SECTION 12348 - 12568.12
UPSTREAM END.
---------------------------------------------------------------------
Channel side slopes from bridge plans.  Concrete paved side slopes.
END DESCRIPTION:
XS GIS Cut Line= 5
2318038.868479026951084.82499069 2318175.8498825 6951087.0822236
  2318513.444089 6951092.6452324 2318636.5410854 6951099.6855913
 2319895.8869056 6951908.8822088
#Sta/Elev= 30
    -137     554   71.14  550.99  226.28  553.22  376.07  550.97   392.3  551.94
  408.29  550.64  433.05  551.92  450.66  550.54  572.73  551.84   695.7  551.49
  849.07  553.99    1026  550.09 1049.85  551.83 1073.85  550.62 1105.22  551.44
  1154.5   526.8    1292   526.8    1331  530.31 1375.22     548 1387.22     548
 1392.22     545 1396.22     548    1498     554    1515     560  1525.8  561.34
 1814.62     558 1876.67  559.16 1890.11  563.96 1943.69  563.92 1957.85  564.99
#Mann= 3 ,0,0
    -137    .055       0 1105.22    .023       0 1375.22    .055       0
#XS Ineff= 8 ,-1
 1414.73 1957.85     570  503.07  982.21     570       0      72     570
     163     200     570    -137       0     570     200  503.07  551.44
  982.21 1105.22  551.44      72     163  551.44
Permanent Ineff=
       F       F       F       F       F       F       F       F
Bank Sta=1105.22,1375.22
XS Rating Curve= 0 ,0
Exp/Cntr=0.5,0.3

Type RM Length L Ch R = 3 ,12393   ,,,
BEGIN DESCRIPTION:
SH 121/Southwest Parkway
Data from bridge plans.  Concrete paved side slopes.  12-foot bike trail on right side slope.
END DESCRIPTION:
Node Name=SH 121/Southwest
Bridge Culvert--1,0,-1,-1, 0
Deck Dist Width WeirC Skew NumUp NumDn MinLoCord MaxHiCord MaxSubmerge Is_Ogee
0.1,220,2.6,0, 8, 8, , , 0.98, 0, 0,0,,
       0     982     982     992     997    1515    1515 1957.85
     582     582     582     582     582     570     570     570
     520     520     572     572     570     560     520     520
       0     982     982     992     997    1515    1515 1957.85
     582     582     582     582     582     570     570     570
     520     520     572     572     570     560     520     520
Pier Skew, UpSta & Num, DnSta & Num=  ,1109, 2 ,1109, 2 , 0 , 0 , 0 ,,
    3.25    3.25
     500     575
    3.25    3.25
     500     575
Pier Skew, UpSta & Num, DnSta & Num=  ,1129, 2 ,1129, 2 , 0 , 0 , 0 ,,
    3.25    3.25
     500     575
    3.25    3.25
     500     575
Pier Skew, UpSta & Num, DnSta & Num=  ,1360, 2 ,1360, 2 , 0 , 0 , 0 ,,
    3.25    3.25
     500     575
    3.25    3.25
     500     575
BR Coef=-1 , 0 , 0 ,, 0 ,,,0.8,-1,,0,
WSPro=,,,, 1 ,,,, 0 ,,,, 0 ,,,,-1 ,-1 ,-1 , 0 , 0 , 0 , 0 , 0
BC Design=,, 0 ,, 0 ,,,,,,
BC Use User HTab Curves=0
BC User HTab FreeFlow(D)= 0

Type RM Length L Ch R = 1 ,12283   ,58,58,73
BEGIN DESCRIPTION:
This cross section corresponds to cross section 12348 of the non-georeferenced CDC model which wa
Downstream of SH121/Southwest Parkway.
---------------------------------------------------------------------
CDC FW111809-01 SH121/SOUTHWEST PARKWAY
CROSS-SECTION 12348 - 12568.12
DOWNSTREAM END
-------------------------------------------------------------------
Copy of cross-section 12568.12.  Modified portion of ineffective flow area.  Channel side slopes from bridge plans.  Concrete paved side slopes.
END DESCRIPTION:
XS GIS Cut Line= 4
2317969.500094016951351.65405871      2318089.48      6951353.85
       2318681.2      6951364.68      2319716.37      6952040.94
#Sta/Elev= 30
    -120     556     -72     550     -28     548       0  551.69   71.14  550.99
  226.28  553.22  376.07  550.97   392.3  551.94  408.29  550.64  433.05  551.92
  450.66  550.54   695.7  551.49  849.07  553.99    1026  550.09 1049.85  551.83
 1105.22  551.44  1154.5   526.8    1292   526.8    1331  530.31 1375.22     548
 1387.22     548 1392.22     545 1396.22     548    1498     554    1515     560
  1525.8  561.34 1814.62     558 1876.67  559.16 1890.11  563.96 1957.85  564.99
#Mann= 3 ,0,0
    -120    .055       0 1105.22    .023       0 1375.22    .055       0
#XS Ineff= 7 ,-1
 1414.73 1957.85     570  503.07  982.21     570       0      72     570
    -120       0     570      72     163  551.44     200  503.07  551.44
  982.21 1105.22  551.44
Permanent Ineff=
       F       F       F       F       F       F       F
Bank Sta=1105.22,1375.22
XS Rating Curve= 0 ,0
Exp/Cntr=0.5,0.3

Type RM Length L Ch R = 1 ,12225   ,59,59,59
BEGIN DESCRIPTION:
This cross section corresponds to cross section 12303.75 of the non-georeferenced CDC model which was the source of this model.
Upstream of Vickery Boulevard.
Copy of cross-section 12244.75
END DESCRIPTION:
XS GIS Cut Line= 4
2318054.640104516951380.90997541 2318087.6374574 6951381.3279494
 2318672.7053095 6951388.7389422 2319248.7763257 6951812.5790409
#Sta/Elev= 30
     -33     556   27.27     552  348.79  551.66  364.84  552.38  380.99  557.41
   426.6     552   461.2  552.66   474.8     550  486.47     550  512.09  552.16
  602.48  551.99  685.58  558.36  806.59  564.47  863.51  565.49   899.2  565.13
  903.84     562   907.4     554   910.9  552.33  933.51  550.39 1006.24  550.33
 1033.43  539.27    1061     530    1076   527.2    1171     525    1190     525
    1195     527    1220     527 1226.73     532 1265.39  545.08 1300.31  565.36
#Mann= 4 ,-1,0
     -33    .055       0 1006.24    .018       0    1076    .035       0
    1220    .018       0
#XS Ineff= 5 ,-1
       0     329     570     735   899.3     570     -33       0     570
   899.3 1006.24  550.33     329     735  550.33
Permanent Ineff=
       F       F       F       F       F
Bank Sta=1006.24,1300.31
XS Rating Curve= 0 ,0
Exp/Cntr=0.5,0.3

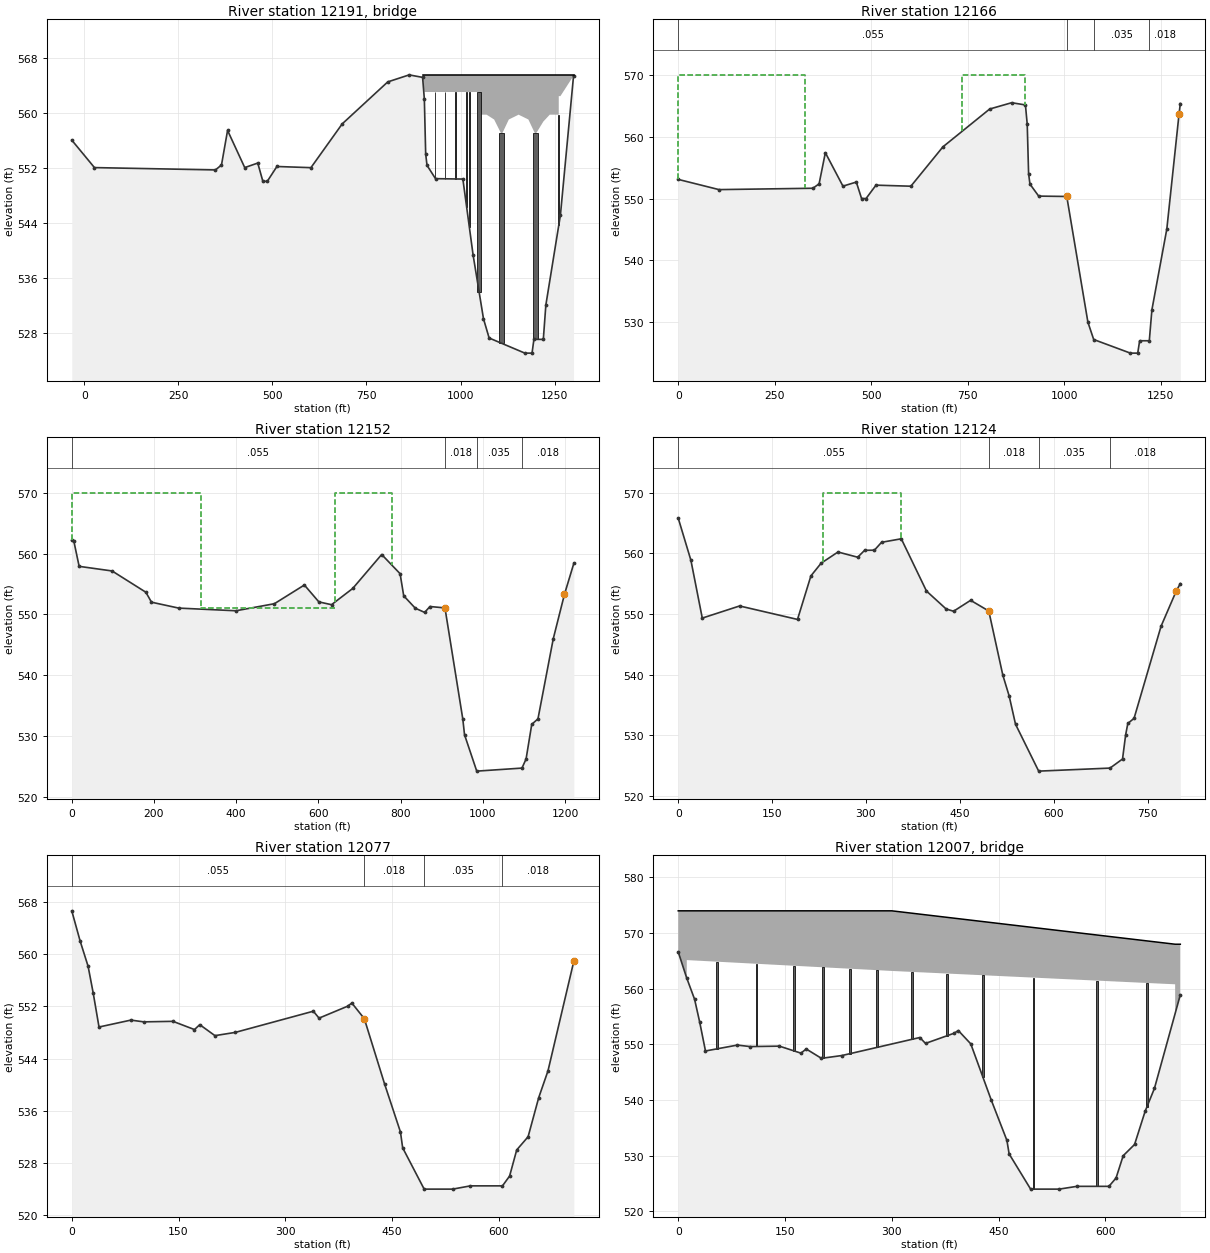
Type RM Length L Ch R = 3 ,12191   ,,,
BEGIN DESCRIPTION:
Vickery Boulevard
Bridge data from USACE 1975 survey, Fort Worth Floodway as-built plans.
END DESCRIPTION:
Node Name=Vickery Blvd.
Bridge Culvert--1,0,-1,-1, 0
Deck Dist Width WeirC Skew NumUp NumDn MinLoCord MaxHiCord MaxSubmerge Is_Ogee
0.22,50,2.6,0, 18, 18, , , 0.95, 0, 0,0,,
   899.3   899.3  1049.3  1049.3  1069.3  1089.3 1107.55 1111.05  1128.3  1154.3
  1180.3 1197.55 1201.05 1220.05 1237.05 1261.05 1261.05  1301.1
   565.5   565.5   565.5   565.5   565.5   565.5   565.5   565.5   565.5   565.5
   565.5   565.5   565.5   565.5   565.5   565.5   565.5   565.5
     450     563     563   559.7   559.7     559     557     557     559   559.7
     559     557     557   558.7   559.7   559.7   562.4   562.4
   899.3   899.3  1049.3  1049.3  1069.3  1089.3 1107.55 1111.05  1128.3  1154.3
  1180.3 1197.55 1201.05 1220.05 1237.05 1261.05 1261.05  1301.1
   565.5   565.5   565.5   565.5   565.5   565.5   565.5   565.5   565.5   565.5
   565.5   565.5   565.5   565.5   565.5   565.5   565.5   565.5
     450     563     563   559.7   559.7     559     557     557     559   559.7
     559     557     557   558.7   559.7   559.7   562.4   562.4
Pier Skew, UpSta & Num, DnSta & Num=  ,932.2, 2 ,932.2, 2 , 0 , 0 , 0 ,,
     1.5     1.5
     450     564
     1.5     1.5
     450     564
Pier Skew, UpSta & Num, DnSta & Num=  ,959.3, 2 ,959.3, 2 , 0 , 0 , 0 ,,
     1.5     1.5
     450     564
     1.5     1.5
     450     564
Pier Skew, UpSta & Num, DnSta & Num=  ,987.3, 2 ,987.3, 2 , 0 , 0 , 0 ,,
     1.5     1.5
     450     564
     1.5     1.5
     450     564
Pier Skew, UpSta & Num, DnSta & Num=  ,1016.3, 2 ,1016.3, 2 , 0 , 0 , 0 ,,
     1.5     1.5
     450     564
     1.5     1.5
     450     564
Pier Skew, UpSta & Num, DnSta & Num=  ,1023.3, 2 ,1023.3, 2 , 0 , 0 , 0 ,,
     1.5     1.5
     450     564
     1.5     1.5
     450     564
Pier Skew, UpSta & Num, DnSta & Num=  ,1049.3, 4 ,1049.3, 4 , 0 , 0 , 0 ,,
      10      10       5       5
     450   543.2   543.2     564
      10      10       5       5
     450   543.2   543.2     564
Pier Skew, UpSta & Num, DnSta & Num=  ,1109.3, 5 ,1109.3, 5 , 0 , 0 , 0 ,,
      12      12       8       4     3.5
     450     536     537     537     557
      12      12       8       4     3.5
     450     536     537     537     557
Pier Skew, UpSta & Num, DnSta & Num=  ,1199.3, 5 ,1199.3, 5 , 0 , 0 , 0 ,,
      12      12       8       4     3.5
     450     536     537     537     557
      12      12       8       4     3.5
     450     536     537     537     557
Pier Skew, UpSta & Num, DnSta & Num=  ,1261.05, 2 ,1261.05, 2 , 0 , 0 , 0 ,,
       3       3
     450     563
       3       3
     450     563
BR Coef=-1 , 0 , 0 ,, 0 ,,,0.8,-1,,0,
WSPro=,,,, 1 ,,,, 0 ,,,, 0 ,,,,-1 ,-1 ,-1 , 0 , 0 , 0 , 0 , 0
BC Design=,, 0 ,, 0 ,,,,,,
BC Use User HTab Curves=0
BC User HTab FreeFlow(D)= 0

Type RM Length L Ch R = 1 ,12166   ,14,14,2
BEGIN DESCRIPTION:
This cross section corresponds to cross section 12244.75 of the non-georeferenced CDC model which was the source of this model.
Downstream of Vickery Boulevard.
Added cross-section from ground points generated through centerline of Vickery Boulevard roadway and bridge.
END DESCRIPTION:
XS GIS Cut Line= 3
      2318074.13      6951451.26   2318667.18547 6951457.8435625
2319236.834409436951876.95864493
#Sta/Elev= 30
       0  553.09  105.53  551.44  348.79  551.66  364.84  552.38  380.99  557.41
   426.6     552   461.2  552.66   474.8     550  486.47     550  512.09  552.16
  602.48  551.99  685.58  558.36  806.59  564.47  863.51  565.49   899.2  565.13
  903.84     562   907.4     554   910.9  552.33  933.51  550.39 1006.24  550.33
    1061     530    1076   527.2    1171     525    1190     525    1195     527
    1220     527 1226.73     532 1265.39  545.08 1296.95  563.61 1300.31  565.36
#Mann= 4 ,-1,0
       0    .055       0 1006.24    .018       0    1076    .035       0
    1220    .018       0
#XS Ineff= 4 ,-1
       0     329     570     735   899.3     570     329     735  550.33
   899.3 1006.24  550.33
Permanent Ineff=
       F       F       F       F
Bank Sta=1006.24,1296.95
XS Rating Curve= 0 ,0
Exp/Cntr=0.5,0.3

Type RM Length L Ch R = 1 ,12152   ,28,28,6
BEGIN DESCRIPTION:
This cross section corresponds to cross section 12228.18 of the non-georeferenced CDC model which was the source of this model.
END DESCRIPTION:
XS GIS Cut Line= 6
 2318142.7654589  6951509.620043 2318699.4036551   6951525.62562
  2318995.905853 6951731.1550193  2319216.822207 6951866.5175384
 2319254.7147512 6951889.73551272319254.716116656951889.73634935
#Sta/Elev= 30
       0  562.21    5.18     562   17.93   557.9   98.09  557.14  180.21  553.64
  193.92     552  260.12  551.03  399.27  550.59  492.77  551.75  565.73  554.83
  601.01  552.05  631.79  551.59   683.3  554.26  753.79  559.85  798.57  556.69
  807.36  553.05  835.57  551.01  858.24  550.32  871.25  551.29   907.7  551.06
  951.15  532.74  955.27  530.19     985   524.2    1095   524.7    1105   526.2
 1118.78   531.9 1133.89   532.8 1171.16     546 1198.28 553.279 1221.17   558.4
#Mann= 4 ,-1,0
       0    .055       0   907.7    .018       0     985    .035       0
    1095    .018       0
#XS Ineff= 4 ,-1
       0  315.47     570  639.86  778.58     570  315.47  639.86  551.06
  778.58   907.7  551.06
Permanent Ineff=
       F       F       F       F
Bank Sta=907.7,1198.28
XS Rating Curve= 0 ,0
Exp/Cntr=0.3,0.1

Type RM Length L Ch R = 1 ,12124   ,47,47,37
BEGIN DESCRIPTION:
This cross section corresponds to cross section 12195.16 of the non-georeferenced CDC model which was the source of this model.
END DESCRIPTION:
XS GIS Cut Line= 4
 2318486.8607319 6951630.9371151 2318674.2212916 6951643.7060301
 2319216.5305218 6951877.5712053 2319238.5227554 6951887.0551257
#Sta/Elev= 30
       0  565.82   20.26  558.87   38.41  549.34   98.08  551.34  190.59  549.12
  212.02   556.3  228.31  558.39  255.26  560.24  286.79  559.38  297.83  560.52
  313.48  560.54  324.91  561.84  356.44  562.42  396.69   553.8  428.14  550.84
  439.98  550.47  467.23  552.27  496.25  550.51  518.68  539.94  528.83  536.49
  538.97  531.84     576   524.1     690   524.6     710   526.1     715   530.1
  718.46  531.96  728.43  532.81  771.57     548     796 553.842  802.33  555.03
#Mann= 4 ,-1,0
       0    .055       0  496.25    .018       0     576    .035       0
     690    .018       0
#XS Ineff= 3 ,-1
  230.81  356.44     570       0  230.81  550.51  356.44  496.25  550.51
Permanent Ineff=
       F       F       F
Bank Sta=496.25,796
XS Rating Curve= 0 ,0
Exp/Cntr=0.5,0.3

Type RM Length L Ch R = 1 ,12077   ,136,136,135
BEGIN DESCRIPTION:
This cross section corresponds to cross section 12145.68 of the non-georeferenced CDC model which was the source of this model.
Upstream of IH 30.
Copy of cross-section 12010.59
END DESCRIPTION:
XS GIS Cut Line= 2
  2318481.854387 6951641.3820168 2319238.8104213 6951929.9597273
#Sta/Elev= 30
       0  566.61   11.71     562   22.94  558.12   30.15     554   38.26  548.82
   83.06  549.88  101.09  549.61  142.12  549.69  172.36  548.43  179.78  549.18
  201.12   547.5   229.8     548  339.33  551.24  347.34  550.18  387.35     552
  393.43  552.49  410.91   550.1  439.64  540.02  461.69  532.75  464.79  530.33
     495     524     535     524     560   524.5     605   524.5     615     526
     625     530  640.99  532.02  655.88     538  668.93  542.11  705.25  558.91
#Mann= 4 ,-1,0
       0    .055       0  410.91    .018       0     495    .035       0
     605    .018       0
#XS Ineff= 2 , 0
       0  410.91   550.1               0
Permanent Ineff=
       F       F
Bank Sta=410.91,705.25
XS Rating Curve= 0 ,0
Exp/Cntr=0.5,0.3

Type RM Length L Ch R = 3 ,12007   ,,,
BEGIN DESCRIPTION:
IH 30
Bridge data from USACE 1975 survey.  Double bridges - total bridge width set at 132 feet.
END DESCRIPTION:
Node Name=IH 30
Bridge Culvert--1,0,-1,-1, 0
Deck Dist Width WeirC Skew NumUp NumDn MinLoCord MaxHiCord MaxSubmerge Is_Ogee
0.68,132,2.6,0, 7, 7, , , 0.95, 0, 0,0,,
       0      12      12     300     698     698  705.25
     574     574     574     574     568     568     568
     450     450  565.15   563.2   560.8     450     450
       0      12      12     300     698     698  705.25
     574     574     574     574     568     568     568
     450     450  565.15   563.2   560.8     450     450
Pier Skew, UpSta & Num, DnSta & Num=  ,54, 2 ,54, 2 , 0 , 0 , 0 ,,
     2.5     2.5
     450     570
     2.5     2.5
     450     570
Pier Skew, UpSta & Num, DnSta & Num=  ,110, 2 ,110, 2 , 0 , 0 , 0 ,,
     2.5     2.5
     450     570
     2.5     2.5
     450     570
Pier Skew, UpSta & Num, DnSta & Num=  ,163, 2 ,163, 2 , 0 , 0 , 0 ,,
     2.5     2.5
     450     570
     2.5     2.5
     450     570
Pier Skew, UpSta & Num, DnSta & Num=  ,203, 2 ,203, 2 , 0 , 0 , 0 ,,
     2.5     2.5
     450     570
     2.5     2.5
     450     570
Pier Skew, UpSta & Num, DnSta & Num=  ,241, 2 ,241, 2 , 0 , 0 , 0 ,,
     2.5     2.5
     450     570
     2.5     2.5
     450     570
Pier Skew, UpSta & Num, DnSta & Num=  ,279, 2 ,279, 2 , 0 , 0 , 0 ,,
     2.5     2.5
     450     570
     2.5     2.5
     450     570
Pier Skew, UpSta & Num, DnSta & Num=  ,328, 2 ,328, 2 , 0 , 0 , 0 ,,
     2.5     2.5
     450     570
     2.5     2.5
     450     570
Pier Skew, UpSta & Num, DnSta & Num=  ,378, 2 ,378, 2 , 0 , 0 , 0 ,,
     2.5     2.5
     450     570
     2.5     2.5
     450     570
Pier Skew, UpSta & Num, DnSta & Num=  ,428, 2 ,428, 2 , 0 , 0 , 0 ,,
     2.5     2.5
     450     570
     2.5     2.5
     450     570
Pier Skew, UpSta & Num, DnSta & Num=  ,499, 2 ,499, 2 , 0 , 0 , 0 ,,
     2.5     2.5
     450     570
     2.5     2.5
     450     570
Pier Skew, UpSta & Num, DnSta & Num=  ,588, 2 ,588, 2 , 0 , 0 , 0 ,,
     2.5     2.5
     450     570
     2.5     2.5
     450     570
Pier Skew, UpSta & Num, DnSta & Num=  ,658, 2 ,658, 2 , 0 , 0 , 0 ,,
     2.5     2.5
     450     570
     2.5     2.5
     450     570
BR Coef=-1 , 0 , 0 ,, 0 ,,,0.8,-1,,0,
WSPro=,,,, 1 ,,,, 0 ,,,, 0 ,,,,-1 ,-1 ,-1 , 0 , 0 , 0 , 0 , 0
BC Design=,, 0 ,, 0 ,,,,,,
BC Use User HTab Curves=0
BC User HTab FreeFlow(D)= 0

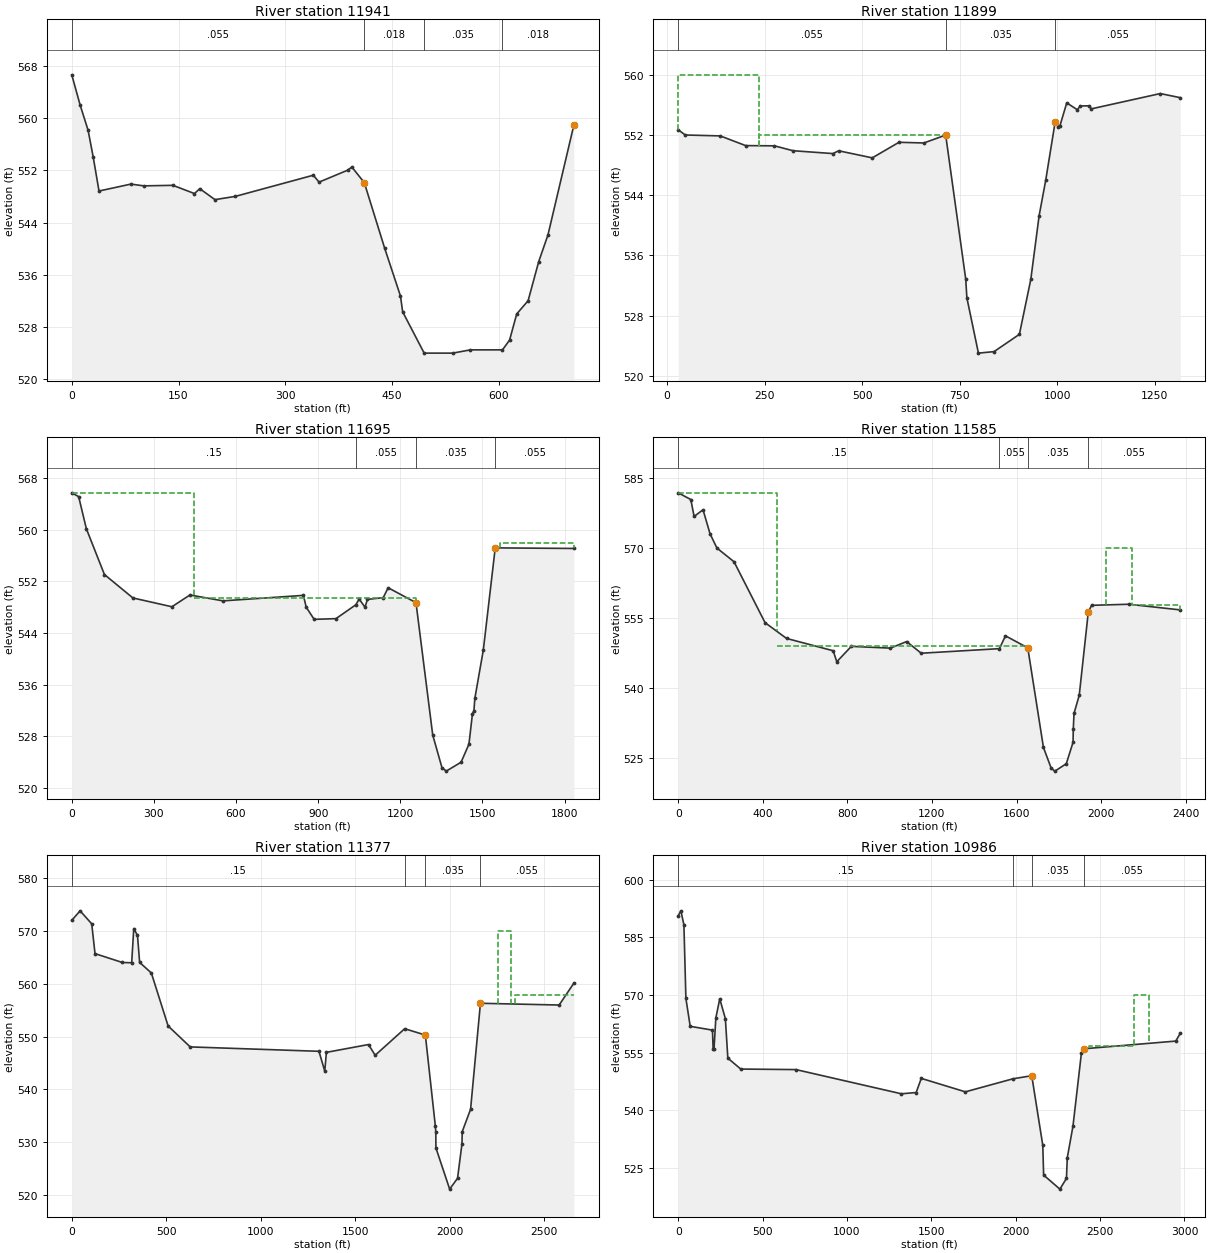
Type RM Length L Ch R = 1 ,11941   ,42,42,35
BEGIN DESCRIPTION:
This cross section corresponds to cross section 12010.59 of the non-georeferenced CDC model which was the source of this model.
Downstream of IH 30.
Added cross-section from ground points generated through centerline of IH 30 bridge.
END DESCRIPTION:
XS GIS Cut Line= 2
 2318492.6729042 6951788.7952679   2319151.78703 6952039.6781495
#Sta/Elev= 30
       0  566.61   11.71     562   22.94  558.12   30.15     554   38.26  548.82
   83.06  549.88  101.09  549.61  142.12  549.69  172.36  548.43  179.78  549.18
  201.12   547.5   229.8     548  339.33  551.24  347.34  550.18  387.35     552
  393.43  552.49  410.91   550.1  439.64  540.02  461.69  532.75  464.79  530.33
     495     524     535     524     560   524.5     605   524.5     615     526
     625     530  640.99  532.02  655.88     538  668.93  542.11  705.25  558.91
#Mann= 4 ,-1,0
       0    .055       0  410.91    .018       0     495    .035       0
     605    .018       0
#XS Ineff= 2 , 0
       0  410.91   550.1               0
Permanent Ineff=
       F       F
Bank Sta=410.91,705.25
XS Rating Curve= 0 ,0
Exp/Cntr=0.5,0.3

Type RM Length L Ch R = 1 ,11899   ,204,204,93
BEGIN DESCRIPTION:
This cross section corresponds to cross section 11968.02 of the non-georeferenced CDC model which was the source of this model.
END DESCRIPTION:
XS GIS Cut Line= 4
2318158.747006786951897.36863873 2318658.0279994 6951905.1023652
 2319268.5432429 6952121.3835267 2319400.4316943 6952168.1063362
#Sta/Elev= 30
   28.53  552.69   46.62     552  136.17  551.88  201.32  550.59   275.2  550.56
  322.73  549.91  425.08  549.53  439.81   549.9  525.88  548.96  594.33  551.03
  658.08  550.94  714.06  551.99  765.49  532.82  768.36  530.36     798     523
     838   523.2     903   525.5  932.24   532.8  953.63  541.29  970.55     546
  994.81  553.79 1002.48   553.1 1007.13  553.26 1024.38  556.27 1051.58  555.36
 1058.93  555.86 1080.85  555.88 1087.72  555.48 1264.26  557.51 1315.48  556.96
#Mann= 3 ,-1,0
   28.53    .055       0  714.06    .035       0  994.81    .055       0
#XS Ineff= 3 ,-1
   28.53  236.65     560 1024.38 1315.48  556.27  236.65  714.06  551.99
Permanent Ineff=
       F       F       F
Bank Sta=714.06,994.81
XS Rating Curve= 0 ,0
Exp/Cntr=0.3,0.1

Type RM Length L Ch R = 1 ,11695   ,109,109,61
BEGIN DESCRIPTION:
This cross section corresponds to cross section 11768.63 of the non-georeferenced CDC model which was the source of this model.
Trinity Park in LOB.
END DESCRIPTION:
XS GIS Cut Line= 2
 2317525.8898544 6952320.1670954 2319353.2404957 6952162.8628841
#Sta/Elev= 30
       0  565.71   25.18  565.12   53.22  560.16  119.22  553.07  223.36  549.44
  365.73  548.08   431.7   549.9  552.47  548.99  846.07  549.84   856.5     548
  885.46  546.13   965.1  546.24 1037.92  548.39 1049.88  549.28  1071.3     548
  1079.9  549.21 1137.85  549.49 1155.73  551.02 1257.49  548.71 1318.59  528.23
  1352.2   523.2 1367.88  522.64 1422.23  524.02 1450.92  526.82 1463.59  531.47
  1469.1     532  1472.5  533.91 1503.49  541.39 1546.93  557.19 1834.11   557.1
#Mann= 4 ,-1,0
       0     .15       0 1037.92    .055       0 1257.49    .035       0
 1546.93    .055       0
#XS Ineff= 3 ,-1
       0  448.15 565.709 1565.26 1834.11  557.91  448.15 1257.49   549.5
Permanent Ineff=
       F       F       F
Bank Sta=1257.49,1546.93
XS Rating Curve= 0 ,0
Exp/Cntr=0.3,0.1

Type RM Length L Ch R = 1 ,11585   ,208,208,120
BEGIN DESCRIPTION:
This cross section corresponds to cross section 11657.13 of the non-georeferenced CDC model which was the source of this model.
Trinity Park in LOB.
END DESCRIPTION:
XS GIS Cut Line= 4
  2317178.170303 6952715.1799998  2319067.700578 6952277.7505465
 2319479.5680122 6952182.4025391 2319491.7069374 6952179.5923574
#Sta/Elev= 30
       0  581.84   59.53   580.4   75.03  576.77  117.28  578.21  150.37  573.07
  182.96     570  263.92  567.06   410.7     554  512.34  550.62  732.83  547.98
   749.9  545.62  818.72  548.92 1003.52  548.54 1080.15  549.95 1149.36  547.45
 1519.11  548.43 1547.75  551.18 1653.28   548.6 1727.33  527.25 1764.37  522.76
 1781.65  522.17 1835.45  523.76 1867.38  528.35  1868.5  531.14 1871.95  534.53
 1896.71  538.45  1939.5  556.28 1954.92  557.72 2130.57  557.95 2374.72  556.74
#Mann= 4 ,-1,0
       0     .15       0 1519.11    .055       0 1653.28    .035       0
  1939.5    .055       0
#XS Ineff= 5 ,-1
       0  466.54 581.836 2023.76  2148.4     570 1954.92 2023.76  557.72
  2148.4 2374.72  557.72  466.54 1653.28  549.03
Permanent Ineff=
       F       F       F       F       F
Bank Sta=1653.28,1939.5
XS Rating Curve= 0 ,0
Exp/Cntr=0.3,0.1

Type RM Length L Ch R = 1 ,11377   ,391,391,415
BEGIN DESCRIPTION:
This cross section corresponds to cross section 11428.19 of the non-georeferenced CDC model which was the source of this model.
Trinity Park in LOB.
END DESCRIPTION:
XS GIS Cut Line= 5
 2317124.1707968 6953175.7743634 2318897.4349452 6952597.6177512
 2319228.7571247 6952371.3489153 2319550.1174824 6952151.8832757
 2319552.1158562 6952150.5185324
#Sta/Elev= 30
       0  571.97    44.2  573.77   105.6  571.31  123.05  565.68  267.95     564
  317.15  563.95   328.2  570.41  347.82  569.12  359.32  564.02  421.23  562.02
  510.05     552  627.01  548.04 1308.57  547.21 1339.29  543.46 1347.97  547.01
 1570.89  548.49 1605.99  546.46 1762.47  551.48 1871.82  550.28 1924.47  533.17
 1927.06     532 1927.85  528.93  2000.5  521.15 2042.23   523.2 2065.67  529.71
 2067.06  532.02 2111.23  536.24 2163.46  556.29 2580.09  555.96 2657.92  560.09
#Mann= 4 ,-1,0
       0     .15       0 1762.47    .055       0 1871.82    .035       0
 2163.46    .055       0
#XS Ineff= 3 ,-1
 2255.38 2325.21     570  2344.6 2657.92  557.78       0 1871.82  550.28
Permanent Ineff=
       F       F       F
Bank Sta=1871.82,2163.46
XS Rating Curve= 0 ,0
Exp/Cntr=0.3,0.1

Type RM Length L Ch R = 1 ,10986   ,69,69,49
BEGIN DESCRIPTION:
This cross section corresponds to cross section 11035.45 of the non-georeferenced CDC model which was the source of this model.
Trinity Park in LOB.
END DESCRIPTION:
XS GIS Cut Line= 6
 2317222.2500694 6953630.8197191 2319164.9093393 6952878.9182549
 2319876.3871487 6952403.8503494 2319895.6896152 6952390.9617081
 2319906.9667809 6952383.4317199  2319907.141394 6952383.3151272
#Sta/Elev= 30
       0  590.65    15.8   591.9   33.67  588.25   45.41   569.1   70.93  561.84
  202.98  560.85  206.66     556  212.11     556  222.89     564  246.03  569.01
  279.33  563.83  293.98  553.56  370.49  550.72  697.91  550.58 1322.68  544.28
 1410.03  544.61 1440.45  548.29  1701.7  544.79 1982.33  548.17 2095.08  548.99
 2160.52  530.86 2165.56  523.13 2261.86  519.47 2300.84  522.26 2305.72  527.63
 2339.42  535.86 2389.55  554.91 2404.97     556 2948.83     558 2975.58  560.05
#Mann= 4 ,-1,0
       0     .15       0 1982.33    .055       0 2095.08    .035       0
 2404.97    .055       0
#XS Ineff= 4 ,-1
 2702.62 2787.14     570 2433.28 2702.62  556.61 2787.14 2975.58  556.61
       0 2095.08  548.88
Permanent Ineff=
       F       F       F       F
Bank Sta=2095.08,2404.97
XS Rating Curve= 0 ,0
Exp/Cntr=0.3,0.1