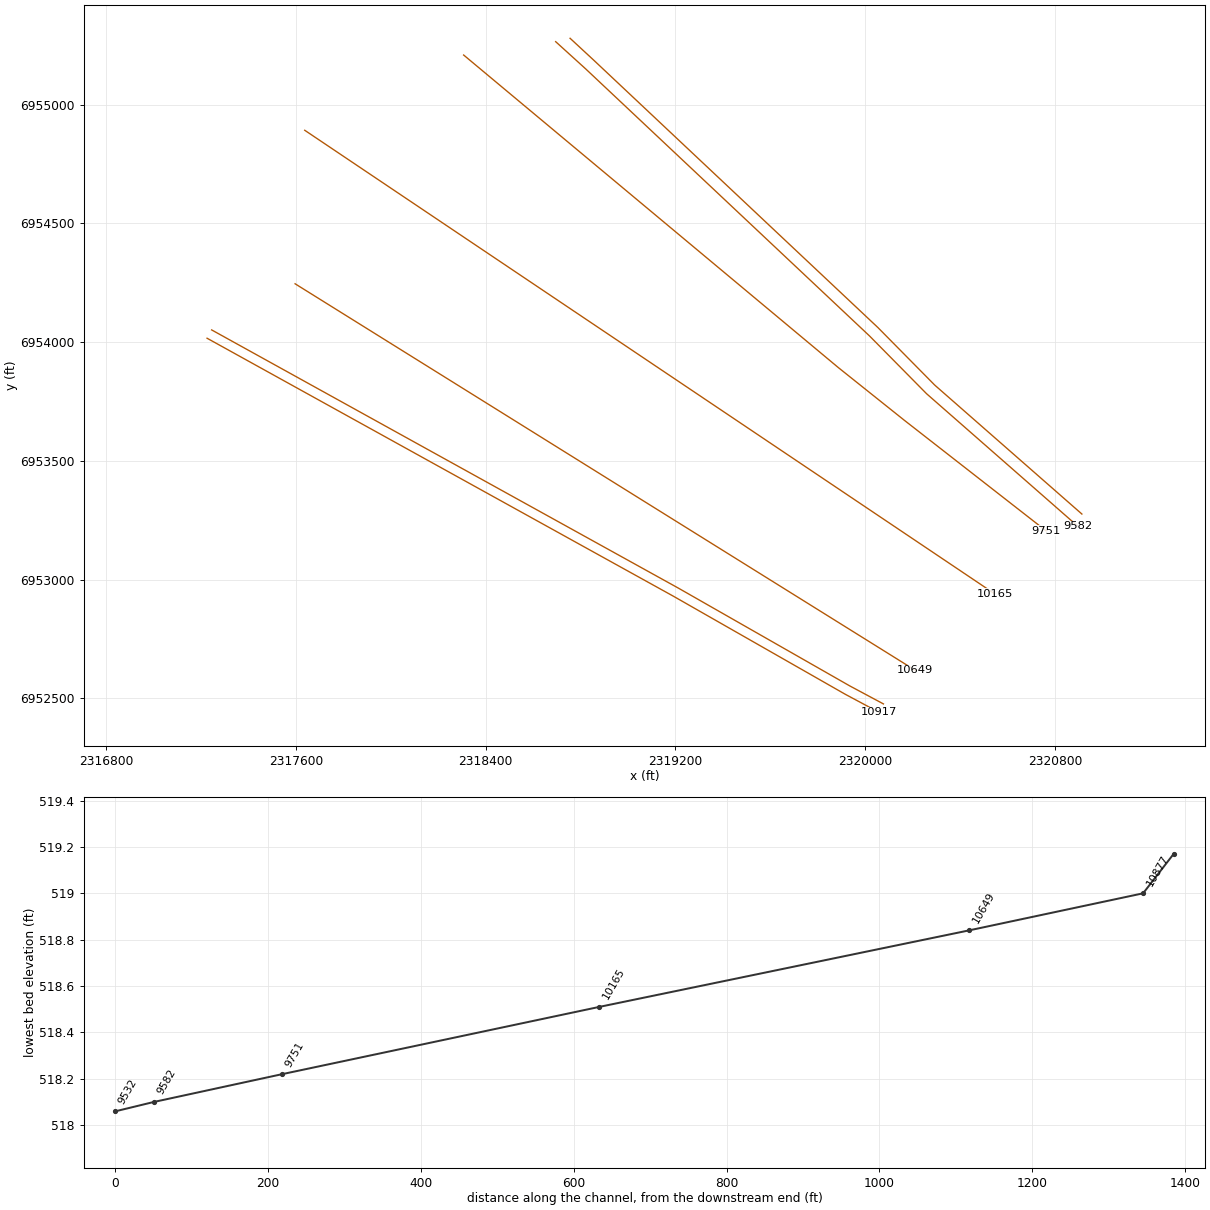
HEC-RAS study CDC_Consolidated_Model.prj: Upper Trinity CDC Consolidated Model

--- CDC_Consolidated_Model.g03 (geometry) --- (continued)

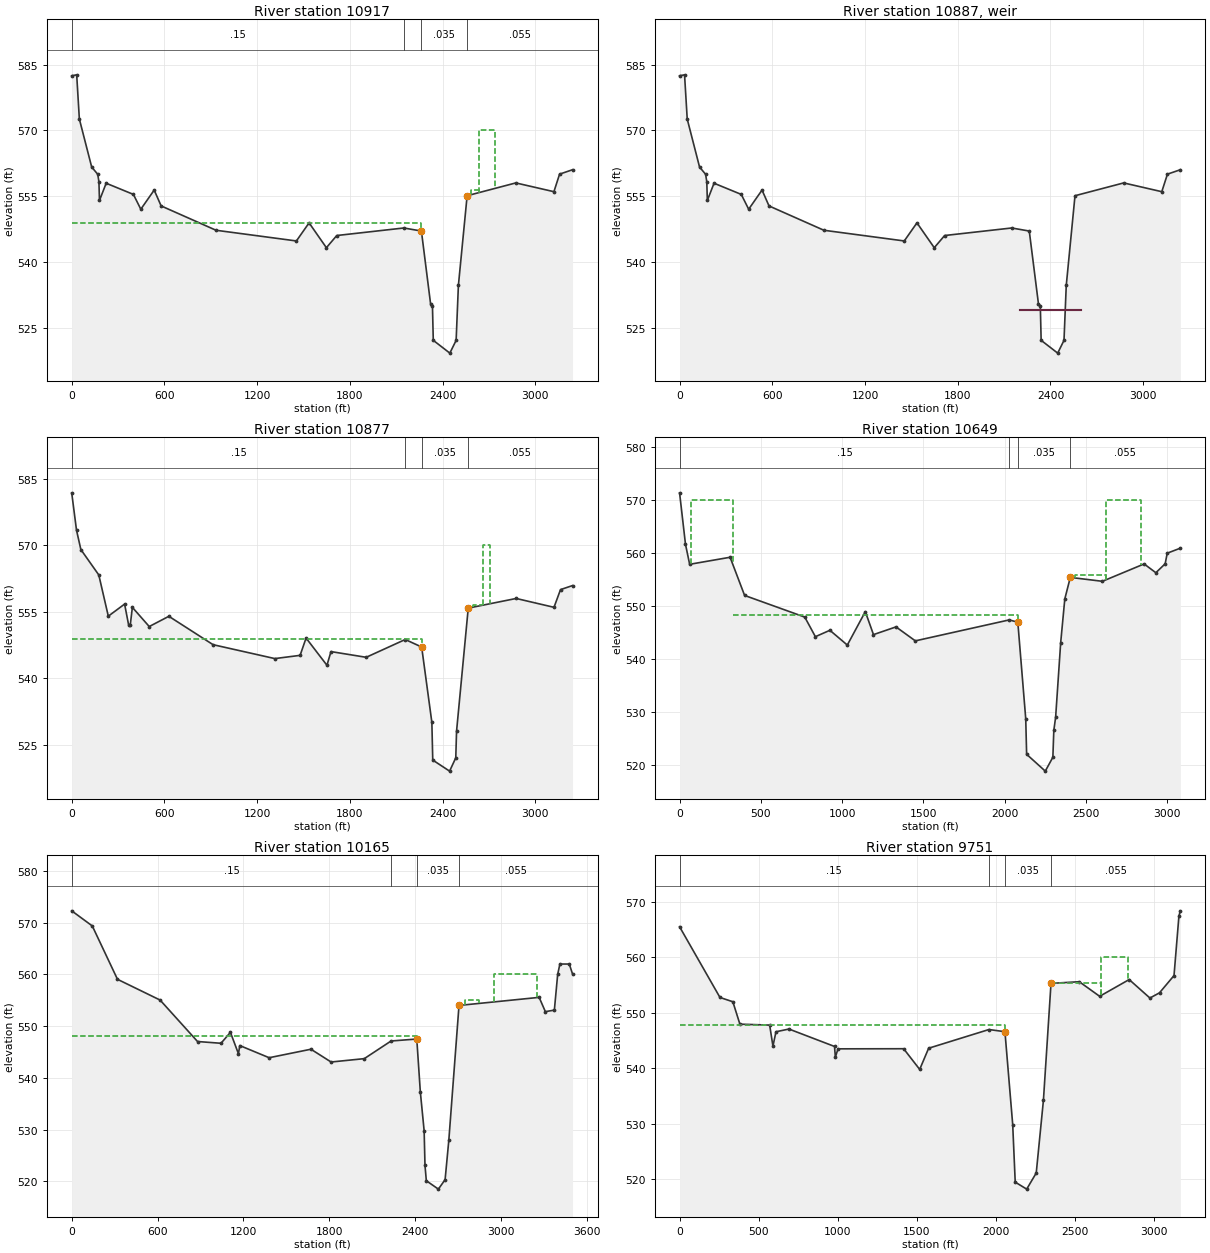
Type RM Length L Ch R = 1 ,10917   ,40,40,40
BEGIN DESCRIPTION:
This cross section corresponds to cross section 10966.91 of the non-georeferenced CDC model which was the source of this model.
Upstream of Trinity Park channel dam.
Trinity Park in LOB.
END DESCRIPTION:
XS GIS Cut Line= 6
 2317225.8276783 6954016.4661771 2319192.1408844 6952929.4019893
 2319916.0681097 6952516.6554387  2319974.306162 6952485.5358298
 2320011.9845233 6952465.4023292 2320057.8298096 6952440.9048173
#Sta/Elev= 30
       0  582.45   32.26  582.66   49.52  572.57  129.25  561.63   168.4  559.97
  176.16  558.26  179.68     554  223.01  557.93  399.27  555.38   447.2     552
  533.73  556.37  578.78  552.75  934.01   547.2 1454.12  544.76  1536.1  548.89
 1648.12  543.22 1715.36     546 2149.34  547.72 2263.02  547.02 2322.46   530.4
 2334.47     530 2339.85  522.09 2447.03  519.17 2487.77  522.09 2502.33   534.6
 2558.96  555.08 2873.96     558 3120.53     556 3157.13     560 3240.85  561.01
#Mann= 4 ,-1,0
       0     .15       0 2149.34    .055       0 2263.02    .035       0
 2558.96    .055       0
#XS Ineff= 5 ,-1
 2634.71 2737.69     570 2581.56 2634.71  556.32 2737.69 3240.85  556.32
       0 2263.02  548.96 2263.02 2558.96     529
Permanent Ineff=
       F       F       F       F       T
Bank Sta=2263.02,2558.96
XS Rating Curve= 0 ,0
Exp/Cntr=0.3,0.1

Type RM Length L Ch R = 5 ,10887   ,,,
BEGIN DESCRIPTION:
Trinity Park channel dam
Data from TRWD survey May 2007.
END DESCRIPTION:
Node Name=channel dam
IW Pilot Flow=0
#Inline Weir SE= 2
    2200     529    2600     529
IW Dist,WD,Coef,Skew,MaxSub,Min_El,Is_Ogee,SpillHt,DesHd
10.51,20,3,0,0.95,, 0 ,,,2,2,
Inline Weir Flap Gates= 0
IW Outlet Rating Curve= 0 ,False,,

Type RM Length L Ch R = 1 ,10877   ,228,228,198
BEGIN DESCRIPTION:
This cross section corresponds to cross section 10926.89 of the non-georeferenced CDC model which was the source of this model.
Downstream of Trinity Park channel dam.
Trinity Park in LOB.
END DESCRIPTION:
XS GIS Cut Line= 6
 2317245.1807574 6954051.4727374 2319211.7241999 6952964.2812454
  2319935.403558 6952551.6759999 2320066.0003195 6952481.8914709
 2320072.7475951 6952478.2860565 2320076.6811911 6952476.1841349
#Sta/Elev= 30
       0  581.86   31.13  573.41   59.26  569.05  175.29  563.31   236.8     554
  342.23  556.73  368.36     552  378.91     552  392.48  555.99   501.6  551.66
  628.64  553.97  914.72  547.56 1314.26  544.42 1477.75  545.15 1516.43  549.06
 1651.45  542.91 1677.59     546 1905.36  544.71 2158.03  548.73 2264.31  547.03
  2330.3     530    2336   521.5    2445     519    2485     522    2490     528
 2565.66  555.82  2875.8     558 3120.54     556 3162.63     560 3240.28  560.91
#Mann= 4 ,-1,0
       0     .15       0 2158.03    .055       0 2264.31    .035       0
 2565.66    .055       0
#XS Ineff= 4 ,-1
 2664.29 2706.51     570 2595.88 2664.29  556.56 2706.51 3240.28  556.56
       0 2264.31   548.8
Permanent Ineff=
       F       F       F       F
Bank Sta=2264.31,2565.66
XS Rating Curve= 0 ,0
Exp/Cntr=0.3,0.1

Type RM Length L Ch R = 1 ,10649   ,484,484,459
BEGIN DESCRIPTION:
This cross section corresponds to cross section 10698.88 of the non-georeferenced CDC model which was the source of this model.
Trinity Park in LOB.
END DESCRIPTION:
XS GIS Cut Line= 2
 2317596.8431069 6954245.8233566  2320210.993655 6952617.5981467
#Sta/Elev= 30
       0   571.4   36.39  561.68   61.98   557.9  310.71  559.23  399.92  552.02
  769.98  547.93  835.19  544.23  924.39  545.44 1031.54  542.65 1142.24  548.96
 1192.43  544.62 1331.05  546.08 1449.77  543.44  2027.4   547.4 2080.09  546.96
 2128.78  528.73 2134.27  522.02 2249.01  518.84 2295.64  521.46 2301.48  526.53
 2312.66  529.02 2343.76  543.12 2369.05  551.36 2402.88  555.43 2600.21  554.69
 2856.85  557.97 2928.95  556.31 2986.23     558 2998.97     560 3079.76  560.95
#Mann= 4 ,-1,0
       0     .15       0  2027.4    .055       0 2080.09    .035       0
 2402.88    .055       0
#XS Ineff= 5 ,-1
   69.34   325.9     570   325.9 2080.09   548.3 2431.39 2619.36  555.96
 2619.36 2835.28     570 2835.28 3079.76  555.96
Permanent Ineff=
       F       F       F       F       F
Bank Sta=2080.09,2402.88
XS Rating Curve= 0 ,0
Exp/Cntr=0.3,0.1

Type RM Length L Ch R = 1 ,10165   ,415,415,348
BEGIN DESCRIPTION:
This cross section corresponds to cross section 10214.95 of the non-georeferenced CDC model which was the source of this model.
Trinity Park in LOB.
END DESCRIPTION:
XS GIS Cut Line= 3
 2317637.5045891 6954892.3395618 2320471.6323015 6952989.7084276
 2320544.7946652 6952940.5924367
#Sta/Elev= 30
       0  572.28  143.85  569.36  320.03  559.05  618.01  555.04  879.82  547.03
 1043.83  546.69 1109.84   548.8 1165.99  544.66 1175.02  546.25 1380.54   543.9
 1672.85  545.54 1813.67  543.07  2045.7  543.72 2233.01  547.13 2412.84  547.51
 2437.56  537.32 2464.27  529.78 2470.16  523.09  2479.6  520.13  2563.8  518.51
 2610.85  520.34 2636.96     528 2708.06     554 3268.39  555.56 3311.85   552.8
 3374.77   553.1 3397.97     560 3413.55     562 3478.93     562 3501.67   560.1
#Mann= 4 ,-1,0
       0     .15       0 2233.01    .055       0 2412.84    .035       0
 2708.06    .055       0
#XS Ineff= 4 ,-1
 2949.49 3253.65     560 2752.58 2849.49  555.12 3253.65 3501.67  555.12
       0 2412.84   548.1
Permanent Ineff=
       F       F       F       F
Bank Sta=2412.84,2708.06
XS Rating Curve= 0 ,0
Exp/Cntr=0.3,0.1

Type RM Length L Ch R = 1 ,9751    ,168,168,115
BEGIN DESCRIPTION:
This cross section corresponds to cross section 9801.369 of the non-georeferenced CDC model which was the source of this model.
Trinity Park in LOB.
END DESCRIPTION:
XS GIS Cut Line= 5
 2318307.3098006 6955209.3325384 2319886.8499979 6953892.6030224
 2320164.4989993 6953671.0906031 2320762.5950414 6953204.8764495
2320762.596342616953204.87543521
#Sta/Elev= 30
       0  565.52  255.73  552.77  337.25     552  381.86  547.96  570.24  547.79
  590.99     544  610.22  546.59  692.53  547.08  980.76  543.94  986.19     542
 1002.72  543.51 1418.28  543.53 1519.87   539.8 1576.54  543.62 1958.05  546.99
 2059.45   546.6  2108.6  529.86 2124.56  519.48 2197.19  518.22 2257.57  521.13
 2303.06  534.23 2351.09  555.31 2530.07  555.61 2658.99  552.98 2845.79     556
 2977.13  552.67  3037.8  553.61 3129.66  556.72 3160.75  567.45 3169.91  568.39
#Mann= 4 ,-1,0
       0     .15       0 1958.05    .055       0 2059.45    .035       0
 2351.09    .055       0
#XS Ineff= 4 ,-1
    2670    2838     560 2351.09    2670  555.31    2838 3169.91  555.31
       0 2059.45  547.86
Permanent Ineff=
       F       F       F       F
Bank Sta=2059.45,2351.09
XS Rating Curve= 0 ,0
Exp/Cntr=0.3,0.1

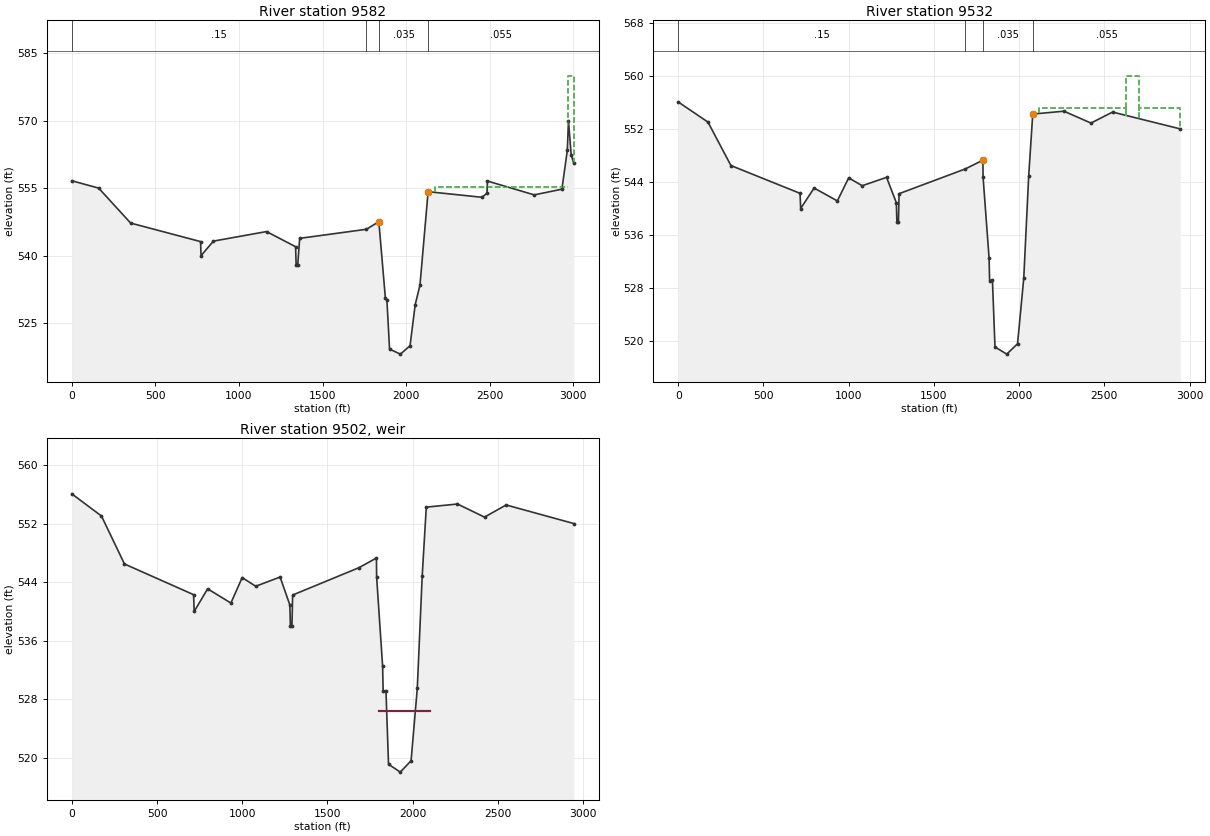
Type RM Length L Ch R = 1 ,9582    ,50,50,50
BEGIN DESCRIPTION:
This cross section corresponds to cross section 9629.433 of the non-georeferenced CDC model which was the source of this model.
Trinity Park in LOB.
END DESCRIPTION:
XS GIS Cut Line= 6
2318695.179130666955265.58417965 2318821.1630508 6955151.3980124
 2320018.3036934 6954025.8358644 2320258.6623088 6953782.6104431
 2320880.2801865 6953238.29326392320896.251163436953224.30834257
#Sta/Elev= 30
       0  556.66  160.75  555.03  352.16  547.25  770.32  543.13  773.11     540
  847.27  543.24 1164.84  545.36 1338.53  541.99 1341.83     538 1351.49     538
 1362.98  543.85 1762.25  545.87 1836.37  547.56 1875.55  530.56 1884.64  530.11
  1900.6  519.22  1965.1   518.1    2023  519.96  2053.9  529.11  2082.5  533.46
 2131.05  554.23 2452.48  552.99  2483.3  553.88 2485.86   556.6 2765.73  553.52
 2931.17  554.79 2963.67  563.44 2970.39  570.02 2986.66  562.43 3002.64  560.51
#Mann= 4 ,-1,0
       0     .15       0 1762.25    .055       0 1836.37    .035       0
 2131.05    .055       0
#XS Ineff= 3 ,-1
 2969.13 3002.64     580 2170.75 2969.13  555.19       0 1836.37  547.56
Permanent Ineff=
       T       F       F
Bank Sta=1836.37,2131.05
XS Rating Curve= 0 ,0
Exp/Cntr=0.3,0.1

Type RM Length L Ch R = 1 ,9532    ,40,40,40
BEGIN DESCRIPTION:
This cross section corresponds to cross section 9579.344 of the non-georeferenced CDC model which was the source of this model.
Upstream of Trinity Park channel dam.
Trinity Park in LOB.
END DESCRIPTION:
XS GIS Cut Line= 5
2318755.914262976955279.83566943 2318855.4125275 6955187.8256601
 2320053.2223595 6954061.6342512 2320292.9585847  6953819.038739
 2320913.21913496953275.91009639
#Sta/Elev= 30
       0  556.06  174.28  553.03  309.12  546.48  714.65  542.29   718.1     540
  796.94  543.09  933.35  541.15  999.67  544.62 1079.32  543.44 1222.02   544.7
 1279.29  540.89 1282.62     538 1291.61     538 1295.55  542.24 1684.03  545.97
 1787.11  547.29 1788.29  544.69 1823.42  532.52  1826.5  529.14  1843.1  529.18
 1858.05  519.14 1927.04  518.06 1990.38  519.62 2026.78  529.49 2055.57  544.83
 2079.51  554.24 2262.48  554.67 2421.07  552.88 2547.83  554.54 2945.13     552
#Mann= 4 ,-1,0
       0     .15       0 1684.03    .055       0 1787.11    .035       0
 2079.51    .055       0
#XS Ineff= 5 ,-1
 2629.39 2700.87     560 2118.37 2629.39   555.2 2700.87 2945.13   555.2
       0 1787.11  547.29 1787.11 2079.51  526.42
Permanent Ineff=
       F       F       F       F       T
Bank Sta=1787.11,2079.51
XS Rating Curve= 0 ,0
Exp/Cntr=0.3,0.1

Type RM Length L Ch R = 5 ,9502    ,,,
BEGIN DESCRIPTION:
Trinity Park channel dam
Structure reconstructed by TRWD.  Structure survey data from TRWD May 2007.
END DESCRIPTION:
Node Name=channel dam
IW Pilot Flow=0
#Inline Weir SE= 2
    1800  526.42    2100  526.42
IW Dist,WD,Coef,Skew,MaxSub,Min_El,Is_Ogee,SpillHt,DesHd
11.71,20,3,0,0.95,, 0 ,,,2,2,
Inline Weir Flap Gates= 0
IW Outlet Rating Curve= 0 ,False,,