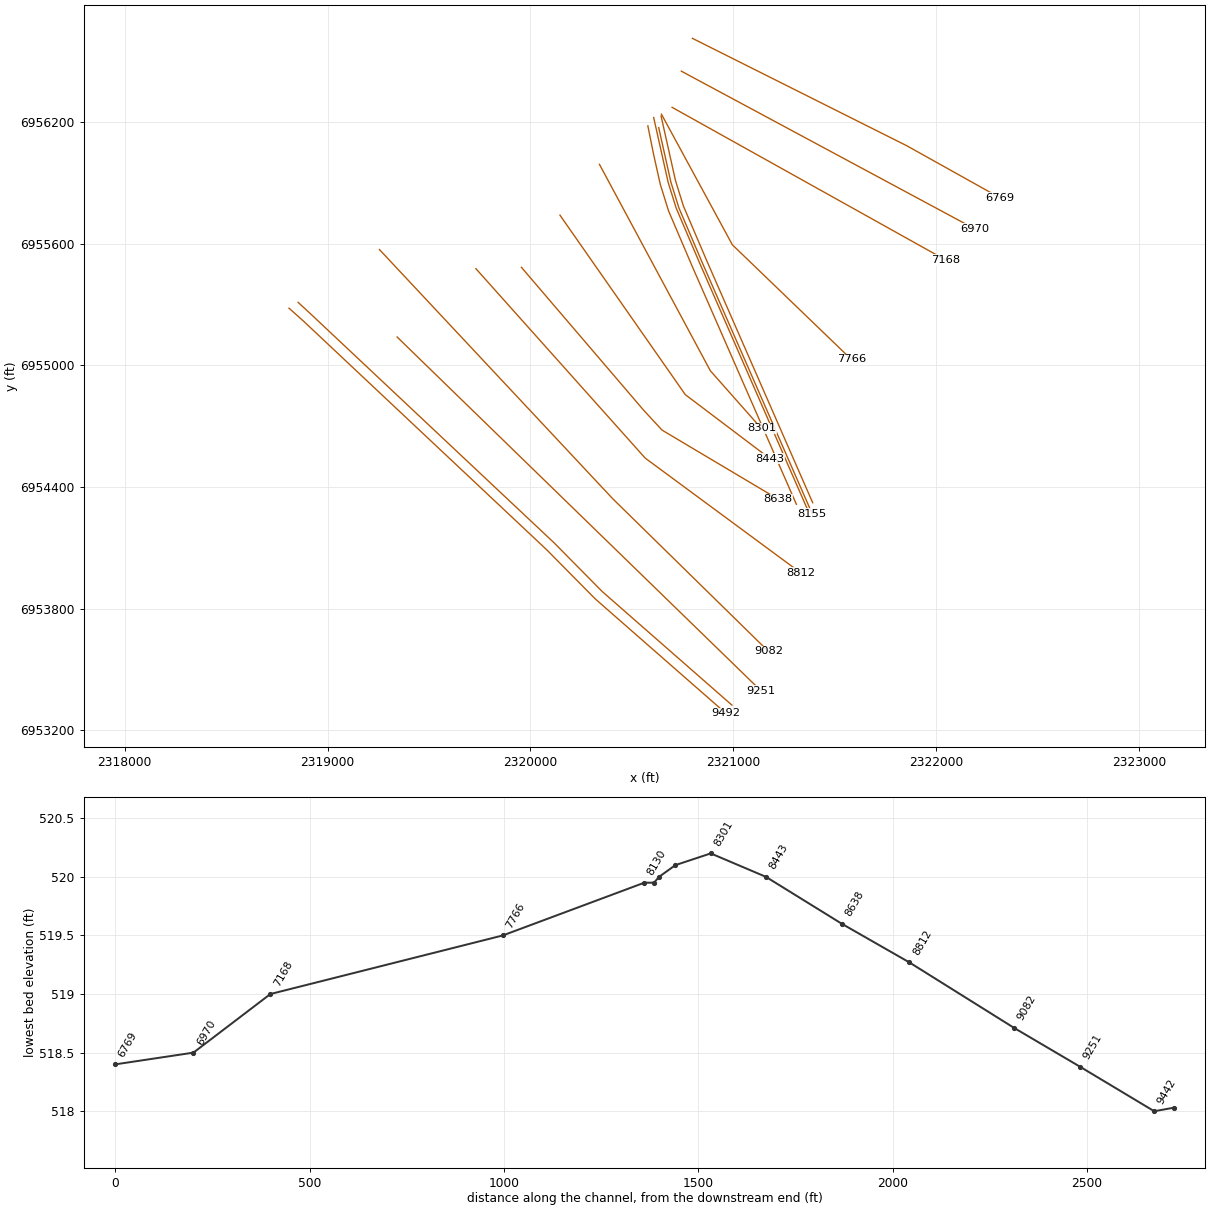
HEC-RAS study CDC_Consolidated_Model.prj: Upper Trinity CDC Consolidated Model

--- CDC_Consolidated_Model.g03 (geometry) --- (continued)

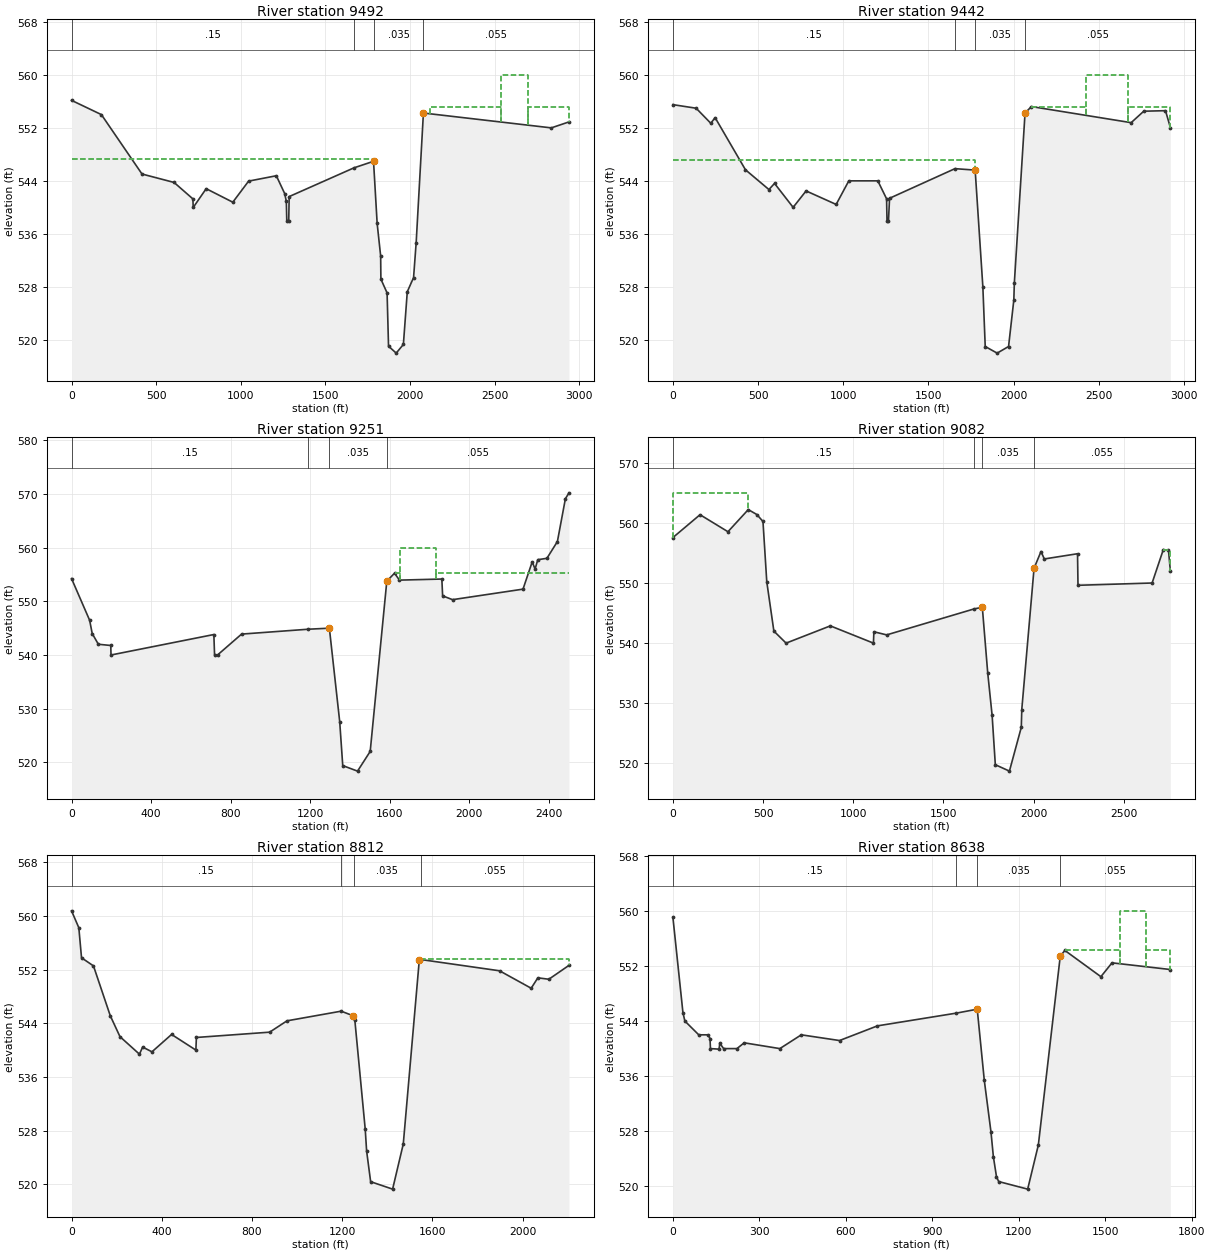
Type RM Length L Ch R = 1 ,9492    ,50,50,50
BEGIN DESCRIPTION:
This cross section corresponds to cross section 9539.207 of the non-georeferenced CDC model which was the source of this model.
Downstream of Trinity Park channel dam.
Trinity Park in LOB.
END DESCRIPTION:
XS GIS Cut Line= 6
2318809.891885326955282.15949627 2318882.8122125 6955216.9676746
 2320081.1574478 6954090.2730125 2320320.3956054  6953848.181272
 2320939.5703328 6953306.00363182320964.491077836953284.18189049
#Sta/Elev= 30
       0  556.15  176.43     554  416.33  545.04  605.79  543.77  716.99  541.29
  718.99     540  795.56  542.83  952.85  540.79 1046.22  543.97 1210.03  544.78
 1259.25   542.1 1269.06  540.92 1271.74     538 1283.21     538 1285.95  541.64
 1668.54  545.97 1784.28  546.96 1805.68  537.59 1826.35  532.69 1827.79  529.19
 1864.42  527.11 1872.92  519.08 1918.26  518.03 1960.68  519.34 1983.72  527.29
 2020.85  529.42 2036.27   534.7    2079  554.24 2834.72     552 2939.13   552.9
#Mann= 4 ,-1,0
       0     .15       0 1668.54    .055       0 1784.28    .035       0
    2079    .055       0
#XS Ineff= 4 ,-1
 2536.99 2696.88     560 2117.41 2536.99   555.2 2696.88 2939.13   555.2
       0 1784.28  547.29
Permanent Ineff=
       F       F       F       F
Bank Sta=1784.28,2079
XS Rating Curve= 0 ,0
Exp/Cntr=0.3,0.1

Type RM Length L Ch R = 1 ,9442    ,191,191,190
BEGIN DESCRIPTION:
This cross section corresponds to cross section 9489.013 of the non-georeferenced CDC model which was the source of this model.
Trinity Park in LOB.
Large mound of material removed in LOB.
END DESCRIPTION:
XS GIS Cut Line= 6
2318854.798034016955311.01836388 2318917.0616893 6955253.3953223
 2320116.0761139 6954126.0713993 2320354.6918813 6953884.6095679
  2320972.509303 6953343.62044522320993.824788636953324.95563349
#Sta/Elev= 30
       0   555.5  136.37  554.96   222.3  552.69  247.69  553.54  425.82  545.67
  563.43  542.69  596.44  543.61  705.56     540  781.63  542.48  958.06  540.44
 1032.38     544 1202.59     544 1254.08  541.29 1256.48     538 1265.23     538
 1271.55  541.37 1655.41  545.84 1773.95  545.62 1819.14     528    1833     519
    1903     518    1970     519 2000.82     526 2004.02  528.64 2066.78  554.25
 2104.47  555.21 2689.52  552.78 2763.46  554.51 2891.06  554.59 2919.59  552.05
#Mann= 4 ,-1,0
       0     .15       0 1655.41    .055       0 1773.95    .035       0
 2066.78    .055       0
#XS Ineff= 4 ,-1
  2423.4  2673.8     560 2104.47  2423.4  555.21  2673.8 2919.59  555.21
       0 1773.95   547.1
Permanent Ineff=
       F       F       F       F
Bank Sta=1773.95,2066.78
XS Rating Curve= 0 ,0
Exp/Cntr=0.3,0.1

Type RM Length L Ch R = 1 ,9251    ,169,169,146
BEGIN DESCRIPTION:
This cross section corresponds to cross section 9296.469 of the non-georeferenced CDC model which was the source of this model.
Trinity Park in LOB.
END DESCRIPTION:
XS GIS Cut Line= 2
  2319342.920824 6955140.0556297 2321136.2750413 6953396.3788009
#Sta/Elev= 30
       0  554.23   90.93  546.47  103.94     544  134.76     542  197.31  541.77
  198.45     540  715.61  543.81   719.2     540  734.09     540  854.98  543.89
 1191.12   544.8 1296.44  544.99 1348.39   527.6 1363.73  519.41 1438.06  518.38
 1501.75  522.05 1585.29  553.75 1623.99  555.22 1648.92  553.94 1862.03  554.14
 1865.95  551.01  1915.8   550.3 2270.16  552.26 2316.38  557.34 2330.91     556
 2344.35  557.74 2390.35     558 2443.04  561.12 2483.26  569.09 2501.31  570.19
#Mann= 4 ,-1,0
       0     .15       0 1191.12    .055       0 1296.44    .035       0
 1585.29    .055       0
#XS Ineff= 4 ,-1
    1650    1834     560 1623.99    1650  555.22    1834 2501.31  555.22
       0 1296.44  544.99
Permanent Ineff=
       F       F       F       F
Bank Sta=1296.44,1585.29
XS Rating Curve= 0 ,0
Exp/Cntr=0.3,0.1

Type RM Length L Ch R = 1 ,9082    ,270,270,309
BEGIN DESCRIPTION:
This cross section corresponds to cross section 9127.056 of the non-georeferenced CDC model which was the source of this model.
Trinity Park in LOB.
END DESCRIPTION:
XS GIS Cut Line= 4
2319255.672426436955571.34268952 2320406.3546697  6954342.329088
 2321155.8022237 6953607.59008672321173.78254905 6953589.9626407
#Sta/Elev= 30
       0  557.56  150.41  561.36  305.19  558.53  417.88  562.21  465.42  561.39
  499.38  560.24  520.49  550.19  559.85     542  627.55     540  872.94  542.87
 1111.92     540 1114.39  541.89  1185.3  541.37    1670  545.69 1715.66  545.96
 1745.65  535.03 1769.99  527.99 1787.75  519.78 1865.94  518.71  1931.8     526
 1934.46  528.96 2002.59  552.46 2041.08  555.24 2059.31     554  2243.6  554.87
 2246.18  549.62 2657.13     550 2719.34  555.56 2747.98  555.44 2758.32     552
#Mann= 4 ,-1,0
       0     .15       0    1670    .055       0 1715.66    .035       0
 2002.59    .055       0
#XS Ineff= 4 ,-1
       0  417.88     565  417.88 1715.66  545.96 2041.08 2719.18  555.24
 2719.18 2758.32  555.55
Permanent Ineff=
       T       F       F       T
Bank Sta=1715.66,2002.59
XS Rating Curve= 0 ,0
Exp/Cntr=0.3,0.1

Type RM Length L Ch R = 1 ,8812    ,174,174,217
BEGIN DESCRIPTION:
This cross section corresponds to cross section 8852.849 of the non-georeferenced CDC model which was the source of this model.
Effective flow limit in LOB set at Clear Fork Levee Loop.
Trinity Park in LOB.
END DESCRIPTION:
XS GIS Cut Line= 3
 2319731.3537127 6955477.0562256 2320566.2875426 6954542.8542166
 2321333.2002633 6953977.1455366
#Sta/Elev= 30
       0  560.76    32.3  558.24   44.27  553.76   97.27  552.55  171.78  545.12
  214.81     542  301.11  539.39  315.34  540.45  356.58  539.74  443.66  542.33
  551.37     540  553.65  541.88  878.52  542.67  955.41  544.36 1195.61   545.8
 1246.14  545.15 1250.98  544.82 1256.32  544.44 1302.34  528.21 1308.54  524.95
 1326.37  520.38 1423.78  519.27  1471.1     526    1542  553.37 1548.56   553.5
 1898.05  551.82 2038.24  549.22 2067.88  550.77 2116.61  550.56 2205.92  552.63
#Mann= 4 ,-1,0
       0     .15       0 1195.61    .055       0 1250.98    .035       0
 1548.56    .055       0
#XS Ineff= 2 ,-1
 1549.38 2205.92  553.51       0 1246.14  545.15
Permanent Ineff=
       F       F
Bank Sta=1246.14,1542
XS Rating Curve= 0 ,0
Exp/Cntr=0.3,0.1

Type RM Length L Ch R = 1 ,8638    ,195,195,143
BEGIN DESCRIPTION:
This cross section corresponds to cross section 8679.124 of the non-georeferenced CDC model which was the source of this model.
Effective flow limit in LOB set at Clear Fork Levee Loop.
Trinity Park in LOB.
END DESCRIPTION:
XS GIS Cut Line= 4
 2319956.0632545 6955483.3638728 2320557.9514559 6954779.7550082
 2320649.2104942 6954681.0226214 2321221.3525699   6954340.65067
#Sta/Elev= 30
       0  559.05   34.83  545.21    41.5     544   89.69     542   122.2     542
  128.69  541.46  130.25     540   160.2  539.92   162.6  540.78  176.01     540
  222.17     540  247.38  540.84  371.07     540  445.52     542  578.16  541.17
  709.66   543.3  983.53  545.15 1055.97  545.72  1080.5  535.38 1103.63  527.91
    1112   524.3  1122.8   521.4  1130.4   520.7    1231   519.6 1267.99     526
 1344.07  553.42 1360.04  554.25 1485.04  550.44 1523.63  552.45  1726.1  551.48
#Mann= 4 ,-1,0
       0     .15       0  983.53    .055       0 1055.97    .035       0
 1344.07    .055       0
#XS Ineff= 4 ,-1
    1550    1641     560 1360.04    1550  554.25    1641  1726.1  554.25
       0 1055.97     545
Permanent Ineff=
       F       F       F       F
Bank Sta=1055.97,1344.07
XS Rating Curve= 0 ,0
Exp/Cntr=0.3,0.1

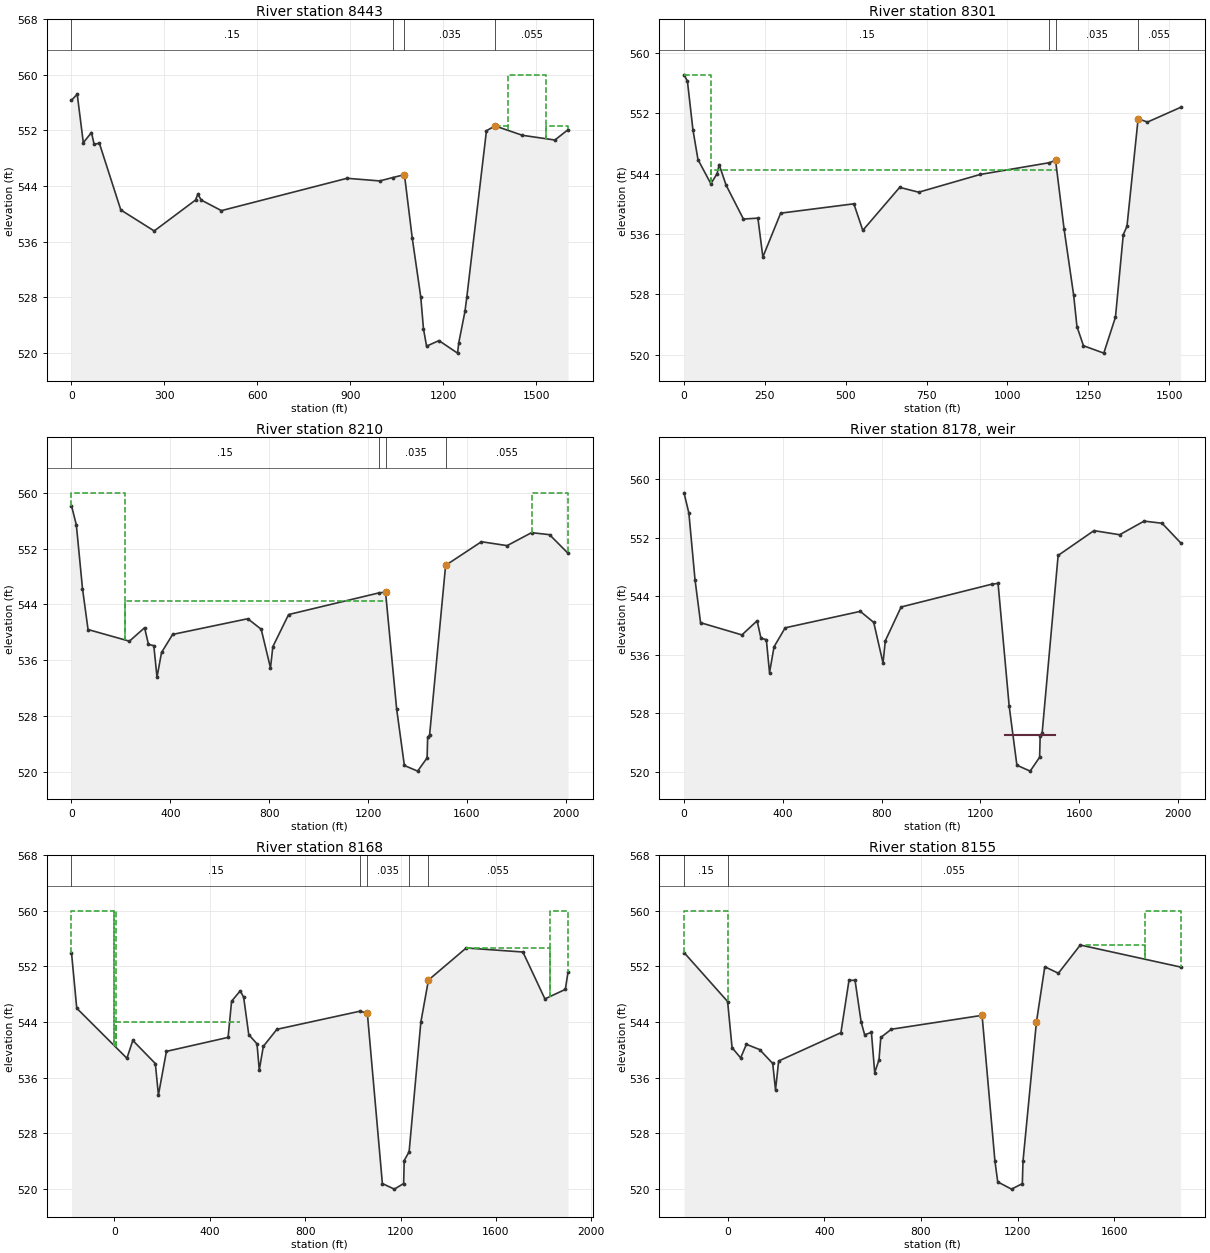
Type RM Length L Ch R = 1 ,8443    ,142,142,81
BEGIN DESCRIPTION:
This cross section corresponds to cross section 8482.235 of the non-georeferenced CDC model which was the source of this model.
Effective flow limit in LOB set at Clear Fork Levee Loop.
Trinity Park in LOB.
END DESCRIPTION:
XS GIS Cut Line= 4
 2320145.8922438 6955740.8074278 2320755.7871228 6954867.5487038
 2320763.6635146 6954856.0087534 2321181.4069465 6954540.3787866
#Sta/Elev= 30
       0  556.35   18.52  557.21   38.12  550.25   64.56  551.71   73.04     550
   89.85  550.18  159.13  540.58  266.94  537.56  400.24     542  407.87  542.84
  418.88     542  483.85  540.48  889.43  545.13  994.92  544.75 1037.27  545.24
 1074.58  545.65 1099.58  536.61 1127.24  528.07    1136   523.5    1146     521
    1186   521.8    1246     520    1250   521.5 1269.93     526  1275.8     528
 1339.26  551.96 1366.81  552.66 1455.16  551.31 1560.21  550.63  1602.7  552.12
#Mann= 4 ,-1,0
       0     .15       0 1037.27    .055       0 1074.58    .035       0
 1366.81    .055       0
#XS Ineff= 4 ,-1
  1409.7  1532.7     560 1366.81  1409.7  552.66  1532.7  1602.7  552.66
       0 1074.58   545.1
Permanent Ineff=
       F       F       F       F
Bank Sta=1074.58,1366.81
XS Rating Curve= 0 ,0
Exp/Cntr=0.3,0.1

Type RM Length L Ch R = 1 ,8301    ,91,91,29
BEGIN DESCRIPTION:
This cross section corresponds to cross section 8334.659 of the non-georeferenced CDC model which was the source of this model.
Effective flow limit in LOB set at Clear Fork Levee Loop.
Trinity Park in LOB.
END DESCRIPTION:
XS GIS Cut Line= 3
 2320340.5994961 6955991.4347673  2320887.686642 6954973.3118564
 2321139.2526874 6954689.0421331
#Sta/Elev= 30
       0   557.1   10.52  556.27   27.53  549.84   43.15  545.87   82.97  542.66
  102.26     544  108.65   545.2  130.06  542.48   183.7  537.98  228.47   538.1
  243.82  532.95   298.8  538.76  525.12     540  552.83  536.48  666.82  542.18
  725.69  541.54  915.58  543.89 1129.29  545.45 1148.79  545.77  1175.2  536.65
  1204.8  527.88 1214.96  523.73 1235.04  521.18 1297.95   520.2 1334.09  524.98
 1358.18  535.91 1369.68  537.03 1404.12  551.28 1433.03  550.84  1535.4  552.79
#Mann= 4 ,-1,0
       0     .15       0 1129.29    .055       0 1148.79    .035       0
 1404.12    .055       0
#XS Ineff= 3 ,-1
       0    81.9 557.104 1404.12  1535.4  551.28    81.9 1148.79   544.5
Permanent Ineff=
       F       F       F
Bank Sta=1148.79,1404.12
XS Rating Curve= 0 ,0
Exp/Cntr=0.3,0.1

Type RM Length L Ch R = 1 ,8210    ,42,42,42
BEGIN DESCRIPTION:
This cross section corresponds to cross section 8244.969 of the non-georeferenced CDC model which was the source of this model.
Upstream of Trinity Park channel dam.
Effective flow limit in LOB set at Clear Fork Levee Loop.
Trinity Park in LOB.
END DESCRIPTION:
XS GIS Cut Line= 6
2320579.273189796956181.28605985 2320608.1992498 6956037.9701292
  2320640.562629 6955893.0667917  2320681.204147 6955762.3551419
 2320796.9989165 6955490.99382352321311.672043286954315.28831615
#Sta/Elev= 30
       0  558.16   19.63   555.4   44.52  546.28      67   540.4  234.35  538.73
  295.86  540.66   311.6  538.26  333.22  538.09  346.13  533.56  364.45  537.11
   409.5   539.7  713.56  541.95  767.94  540.44  805.51  534.89  814.94  537.94
  878.82  542.55 1245.19  545.66  1271.2  545.77 1316.11  529.02 1347.42  520.91
 1401.11   520.1 1439.44     522 1441.64  524.93  1449.5  525.28 1514.36   549.6
 1659.29  552.99 1763.35  552.43 1862.26  554.29 1935.11     554 2010.02  551.33
#Mann= 4 ,-1,0
       0     .15       0 1245.19    .055       0  1271.2    .035       0
 1514.36    .055       0
#XS Ineff= 4 ,-1
       0  216.27     560  216.27  1271.2   544.5  1271.2 1514.36     525
 1863.37 2010.02     560
Permanent Ineff=
       F       F       T       F
Bank Sta=1271.2,1514.36
XS Rating Curve= 0 ,0
Exp/Cntr=0.3,0.1

Type RM Length L Ch R = 5 ,8178    ,,,
BEGIN DESCRIPTION:
Trinity Park channel dam
Structure reconstructed by TRWD.  Structure survey data from TRWD May 2007.
END DESCRIPTION:
Node Name=channel dam
IW Pilot Flow=0
#Inline Weir SE= 2
    1300     525    1500     525
IW Dist,WD,Coef,Skew,MaxSub,Min_El,Is_Ogee,SpillHt,DesHd
10.2,20,3,0,0.95,, 0 ,,,2,2,
Inline Weir Flap Gates= 0
IW Outlet Rating Curve= 0 ,False,,

Type RM Length L Ch R = 1 ,8168    ,13,13,13
BEGIN DESCRIPTION:
This cross section corresponds to cross section 8204.815 of the non-georeferenced CDC model which was the source of this model.
Downstream of Trinity Park channel dam.
Effective flow limit in LOB set at Clear Fork Levee Loop.
Trinity Park in LOB.
END DESCRIPTION:
XS GIS Cut Line= 6
2320608.002714746956222.35893287 2320647.2375395 6956046.6890358
 2320679.2444154 6955903.3815372 2320718.7949033 6955776.1786587
 2320833.7164339 6955506.86405882321366.925562566954288.81517753
#Sta/Elev= 30
    -180     554    -158     546   52.43  538.81   77.11  541.37  171.57  538.05
  184.52  533.53  218.09   539.8  476.74  541.81  491.39  547.01  527.71   548.5
  542.01  547.58  563.39  542.21  597.97  540.88  607.49  537.12   624.5  540.52
   681.4  542.97 1030.62  545.58 1060.72  545.28 1123.79   520.8 1173.79     520
    1213   520.8 1215.25  524.11  1235.9  525.37 1285.13     544 1316.99  550.05
 1475.26  554.66 1713.18  554.08 1805.38  547.34 1891.08  548.71  1902.5  551.25
#Mann= 5 ,-1,0
    -180     .15       0 1030.62    .055       0 1060.72    .035       0
  1235.9    .025       0 1316.99    .055       0
#XS Ineff= 6 ,-1
       0    5.68     560    1827  1902.5     560    -180       0     560
 1475.26    1827  554.66    5.68     527     544     527    1040     544
Permanent Ineff=
       F       F       F       F       F       F
Bank Sta=1060.72,1316.99
XS Rating Curve= 0 ,0
Exp/Cntr=0.5,0.3

Type RM Length L Ch R = 1 ,8155    ,25,25,25
BEGIN DESCRIPTION:
This cross section corresponds to cross section 8192.064 of the non-georeferenced CDC model which was the source of this model.
Upstream of BNSF Railroad.
Copy of cross-section 8167.88.
Effective flow limit in LOB set at Clear Fork Levee Loop.
Trinity Park in LOB.
END DESCRIPTION:
XS GIS Cut Line= 6
 2320632.82721746956172.43842845 2320660.0074916 6956050.8115116
 2320692.8043789 6955904.0512451 2320732.3548669 6955776.8483665
 2320847.2763975 6955507.53376662321389.684432656954268.47114592
#Sta/Elev= 30
    -180     554     .25  546.95   18.74  540.31   54.16  538.84   78.02  540.79
  132.48  540.04  186.78  538.04  198.44  534.22  211.39  538.39  468.84  542.46
   502.3     550  527.29     550  552.53     544  566.98  542.17  594.98   542.5
  608.61  536.73  626.35  538.54  633.76  541.78  677.72  542.96 1052.65  544.96
 1105.79     524  1117.4  520.99  1174.4  519.95  1219.2  520.74  1221.8  523.94
 1277.42  543.99 1312.04  551.95 1368.22  551.02 1458.79  555.08 1873.61  551.91
#Mann= 2 ,-1,0
    -180     .15       0     .25    .055       0
#XS Ineff= 5 ,-1
    -180     .25     560     .25     527     543 1480.53    1725  555.09
    1725 1873.61     560     527 1052.65     543
Permanent Ineff=
       F       F       F       F       F
Bank Sta=1052.65,1277.42
XS Rating Curve= 0 ,0
Exp/Cntr=0.5,0.3

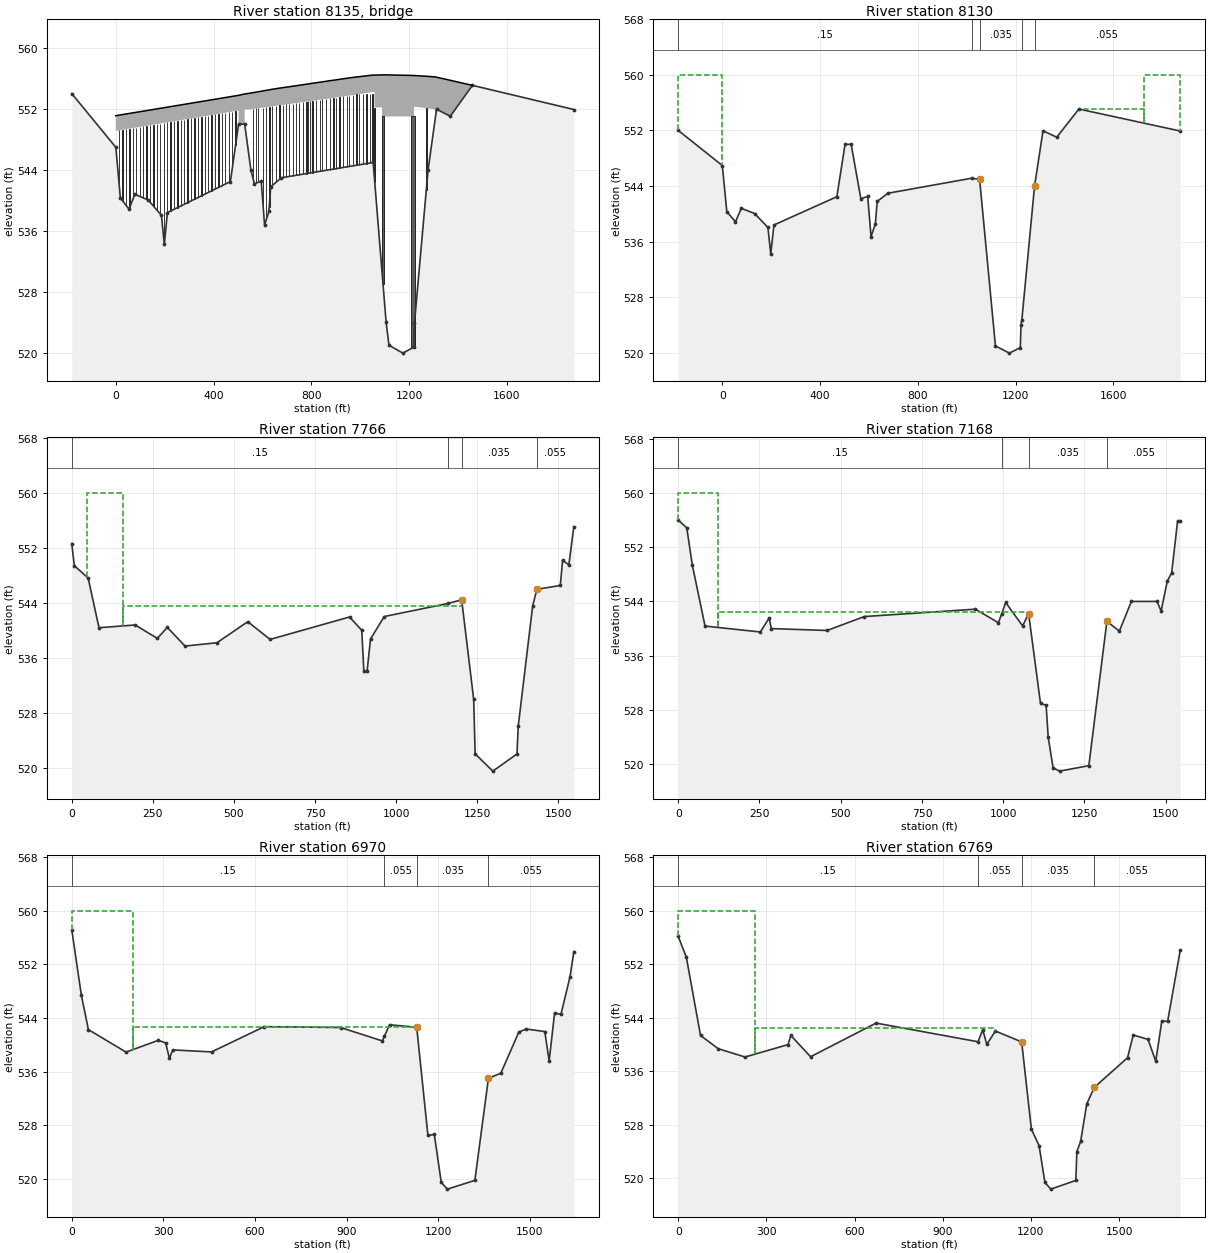
Type RM Length L Ch R = 3 ,8135    ,,,
BEGIN DESCRIPTION:
BNSF Railroad
Main channel bridge: bridge data from 1975 USACE survey, low chord elev. 551.0, length 761 feet.  Left bank relief bridge: data from USACE May 2007 field measurement.
END DESCRIPTION:
Node Name=BNSF RR
Bridge Culvert--1,0,-1,-1, 0
Deck Dist Width WeirC Skew NumUp NumDn MinLoCord MaxHiCord MaxSubmerge Is_Ogee
6.07,10,2.6,0, 54, 54, , , 0.95, 0, 0,0,,
       0   502.3   502.3  527.29  527.29  545.04  557.04  558.04  571.04  572.04
  584.04  585.04  599.04  600.04  612.04  613.04  624.04  629.04  639.04  640.04
  652.04  653.04  666.04  667.04  738.04  748.04  878.04  888.04  954.04  955.04
  968.04  969.04  982.04  983.04 1015.04 1019.04 1050.04 1051.04 1058.04 1058.04
 1060.54 1089.04 1089.04 1097.04 1211.04 1220.04 1220.04 1266.04 1267.04 1269.04
 1270.04 1306.04  1306.4 1458.79
   551.1  553.77  553.77  553.95  553.95  554.03   554.1   554.1  554.18  554.18
  554.25  554.25  554.33  554.34  554.41  554.41  554.47   554.5  554.56  554.56
  554.63  554.63   554.7   554.7  555.03  555.08   555.7  555.74  556.05  556.06
  556.11  556.11  556.17  556.17  556.29   556.3  556.42  556.42  556.42  556.42
  556.43  556.45  556.45  556.46  556.38  556.37  556.37  556.28  556.28  556.27
  556.27  556.19  556.19  555.08
   549.1  551.77     550     550  551.95  551.91  551.96  551.97  552.02  552.03
  552.08  552.08  552.14  552.15   552.2  552.21  552.25  552.28  552.32  552.32
  552.38  552.38  552.44  552.44  552.75   552.8  553.38  553.43  553.73  553.74
   553.8   553.8  553.87  553.87  554.02  554.04  554.19   554.2  554.23  552.17
  552.17  552.18     551     551     551     551  552.29   552.1  552.09  552.08
  552.08  551.93     546     546
       0   502.3   502.3  527.29  527.29  545.04  557.04  558.04  571.04  572.04
  584.04  585.04  599.04  600.04  612.04  613.04  624.04  629.04  639.04  640.04
  652.04  653.04  666.04  667.04  738.04  748.04  878.04  888.04  954.04  955.04
  968.04  969.04  982.04  983.04 1015.04 1019.04 1050.04 1051.04 1058.04 1058.04
 1060.54 1089.04 1089.04 1097.04 1211.04 1220.04 1220.04 1266.04 1267.04 1269.04
 1270.04 1306.04  1306.4 1458.79
   551.1  553.77  553.77  553.95  553.95  554.03   554.1   554.1  554.18  554.18
  554.25  554.25  554.33  554.34  554.41  554.41  554.47   554.5  554.56  554.56
  554.63  554.63   554.7   554.7  555.03  555.08   555.7  555.74  556.05  556.06
  556.11  556.11  556.17  556.17  556.29   556.3  556.42  556.42  556.42  556.42
  556.43  556.45  556.45  556.46  556.38  556.37  556.37  556.28  556.28  556.27
  556.27  556.19  556.19  555.08
   549.1  551.77     550     550  551.95  551.91  551.96  551.97  552.02  552.03
  552.08  552.08  552.14  552.15   552.2  552.21  552.25  552.28  552.32  552.32
  552.38  552.38  552.44  552.44  552.75   552.8  553.38  553.43  553.73  553.74
   553.8   553.8  553.87  553.87  554.02  554.04  554.19   554.2  554.23  552.17
  552.17  552.18     551     551     551     551  552.29   552.1  552.09  552.08
  552.08  551.93     546     546
Pier Skew, UpSta & Num, DnSta & Num=  ,560.04, 2 ,560.04, 2 , 0 , 0 , 0 ,,
       1       1
     500     553
       1       1
     500     553
Pier Skew, UpSta & Num, DnSta & Num=  ,575.04, 2 ,575.04, 2 , 0 , 0 , 0 ,,
       1       1
     500     553
       1       1
     500     553
Pier Skew, UpSta & Num, DnSta & Num=  ,582.04, 2 ,582.04, 2 , 0 , 0 , 0 ,,
       1       1
     500     553
       1       1
     500     553
Pier Skew, UpSta & Num, DnSta & Num=  ,602.04, 2 ,602.04, 2 , 0 , 0 , 0 ,,
       1       1
     500     553
       1       1
     500     553
Pier Skew, UpSta & Num, DnSta & Num=  ,615.04, 2 ,615.04, 2 , 0 , 0 , 0 ,,
       1       1
     500     553
       1       1
     500     553
Pier Skew, UpSta & Num, DnSta & Num=  ,627.54, 2 ,627.54, 2 , 0 , 0 , 0 ,,
       5       5
     500     553
       5       5
     500     553
Pier Skew, UpSta & Num, DnSta & Num=  ,640.04, 2 ,640.04, 2 , 0 , 0 , 0 ,,
       1       1
     500     553
       1       1
     500     553
Pier Skew, UpSta & Num, DnSta & Num=  ,655.04, 2 ,655.04, 2 , 0 , 0 , 0 ,,
       1       1
     500     553
       1       1
     500     553
Pier Skew, UpSta & Num, DnSta & Num=  ,670.04, 2 ,670.04, 2 , 0 , 0 , 0 ,,
       1       1
     500     553
       1       1
     500     553
Pier Skew, UpSta & Num, DnSta & Num=  ,682.54, 2 ,682.54, 2 , 0 , 0 , 0 ,,
       1       1
     500     553
       1       1
     500     553
Pier Skew, UpSta & Num, DnSta & Num=  ,697.54, 2 ,697.54, 2 , 0 , 0 , 0 ,,
       1       1
     500     553
       1       1
     500     553
Pier Skew, UpSta & Num, DnSta & Num=  ,710.04, 2 ,710.041, 2 , 0 , 0 , 0 ,,
       1       1
     500     553
       1       1
     500     553
Pier Skew, UpSta & Num, DnSta & Num=  ,725.04, 2 ,725.041, 2 , 0 , 0 , 0 ,,
       1       1
     500     553
       1       1
     500     553
Pier Skew, UpSta & Num, DnSta & Num=  ,737.54, 2 ,737.541, 2 , 0 , 0 , 0 ,,
       1       1
     500     553
       1       1
     500     553
Pier Skew, UpSta & Num, DnSta & Num=  ,750.04, 2 ,750.04, 2 , 0 , 0 , 0 ,,
       1       1
     500     553
       1       1
     500     553
Pier Skew, UpSta & Num, DnSta & Num=  ,765.04, 2 ,765.04, 2 , 0 , 0 , 0 ,,
       1       1
     500   553.5
       1       1
     500   553.5
Pier Skew, UpSta & Num, DnSta & Num=  ,780.04, 2 ,780.04, 2 , 0 , 0 , 0 ,,
       1       1
     500   553.5
       1       1
     500   553.5
Pier Skew, UpSta & Num, DnSta & Num=  ,787.5, 2 ,787.5, 2 , 0 , 0 , 0 ,,
       1       1
     500     553
       1       1
     500     553
Pier Skew, UpSta & Num, DnSta & Num=  ,795.04, 2 ,795.04, 2 , 0 , 0 , 0 ,,
       1       1
     500   553.5
       1       1
     500   553.5
Pier Skew, UpSta & Num, DnSta & Num=  ,805.04, 2 ,805.041, 2 , 0 , 0 , 0 ,,
       1       1
     500   553.5
       1       1
     500   553.5
Pier Skew, UpSta & Num, DnSta & Num=  ,820.04, 2 ,820.041, 2 , 0 , 0 , 0 ,,
       1       1
     500   553.5
       1       1
     500   553.5
Pier Skew, UpSta & Num, DnSta & Num=  ,835.04, 2 ,835.041, 2 , 0 , 0 , 0 ,,
       1       1
     500   553.5
       1       1
     500   553.5
Pier Skew, UpSta & Num, DnSta & Num=  ,845.04, 2 ,845.041, 2 , 0 , 0 , 0 ,,
       1       1
     500   553.5
       1       1
     500   553.5
Pier Skew, UpSta & Num, DnSta & Num=  ,860.04, 2 ,860.041, 2 , 0 , 0 , 0 ,,
       1       1
     500   553.5
       1       1
     500   553.5
Pier Skew, UpSta & Num, DnSta & Num=  ,877.54, 2 ,877.541, 2 , 0 , 0 , 0 ,,
       1       1
     500   553.5
       1       1
     500   553.5
Pier Skew, UpSta & Num, DnSta & Num=  ,890.04, 2 ,890.041, 2 , 0 , 0 , 0 ,,
       1       1
     500   553.5
       1       1
     500   553.5
Pier Skew, UpSta & Num, DnSta & Num=  ,900.04, 2 ,900.041, 2 , 0 , 0 , 0 ,,
       1       1
     500     554
       1       1
     500     554
Pier Skew, UpSta & Num, DnSta & Num=  ,915.04, 2 ,915.041, 2 , 0 , 0 , 0 ,,
       1       1
     500     554
       1       1
     500     554
Pier Skew, UpSta & Num, DnSta & Num=  ,930.04, 2 ,930.04, 2 , 0 , 0 , 0 ,,
       1       1
     500     554
       1       1
     500     554
Pier Skew, UpSta & Num, DnSta & Num=  ,945.04, 2 ,945.041, 2 , 0 , 0 , 0 ,,
       1       1
     500     554
       1       1
     500     554
Pier Skew, UpSta & Num, DnSta & Num=  ,955.04, 2 ,955.041, 2 , 0 , 0 , 0 ,,
       1       1
     500     554
       1       1
     500     554
Pier Skew, UpSta & Num, DnSta & Num=  ,970.04, 2 ,970.04, 2 , 0 , 0 , 0 ,,
       1       1
     500     554
       1       1
     500     554
Pier Skew, UpSta & Num, DnSta & Num=  ,985.04, 2 ,985.04, 2 , 0 , 0 , 0 ,,
       1       1
     500     554
       1       1
     500     554
Pier Skew, UpSta & Num, DnSta & Num=  ,995.04, 2 ,995.04, 2 , 0 , 0 , 0 ,,
       1       1
     500     554
       1       1
     500     554
Pier Skew, UpSta & Num, DnSta & Num=  ,1010.04, 2 ,1010.04, 2 , 0 , 0 , 0 ,,
       1       1
     500     554
       1       1
     500     554
Pier Skew, UpSta & Num, DnSta & Num=  ,1025.04, 2 ,1025.04, 2 , 0 , 0 , 0 ,,
       1       1
     500     554
       1       1
     500     554
Pier Skew, UpSta & Num, DnSta & Num=  ,1040.04, 2 ,1040.04, 2 , 0 , 0 , 0 ,,
       1       1
     500     554
       1       1
     500     554
Pier Skew, UpSta & Num, DnSta & Num=  ,1050.04, 2 ,1050.041, 2 , 0 , 0 , 0 ,,
       1       1
     500     554
       1       1
     500     554
Pier Skew, UpSta & Num, DnSta & Num=  ,1059.29, 2 ,1059.29, 2 , 0 , 0 , 0 ,,
     2.5     2.5
     500     554
     2.5     2.5
     500     554
Pier Skew, UpSta & Num, DnSta & Num=  ,1093.04, 2 ,1093.04, 2 , 0 , 0 , 0 ,,
       8       8
     500     553
       8       8
     500     553
Pier Skew, UpSta & Num, DnSta & Num=  ,1216.04, 4 ,1216.04, 4 , 0 , 0 , 0 ,,
    14.5    14.5       8       8
     500   525.5   525.5     553
    14.5    14.5       8       8
     500   525.5   525.5     553
Pier Skew, UpSta & Num, DnSta & Num=  ,1270.04, 2 ,1270.04, 2 , 0 , 0 , 0 ,,
       2       2
     500     554
       2       2
     500     554
Pier Skew, UpSta & Num, DnSta & Num=  ,14, 2 ,14, 2 , 0 , 0 , 0 ,,
     1.5     1.5
  519.95  554.23
     1.5     1.5
  519.95  554.23
Pier Skew, UpSta & Num, DnSta & Num=  ,28, 2 ,28, 2 , 0 , 0 , 0 ,,
     1.5     1.5
  519.95  554.23
     1.5     1.5
  519.95  554.23
Pier Skew, UpSta & Num, DnSta & Num=  ,42, 2 ,42, 2 , 0 , 0 , 0 ,,
     1.5     1.5
  519.95  554.23
     1.5     1.5
  519.95  554.23
Pier Skew, UpSta & Num, DnSta & Num=  ,56, 2 ,56, 2 , 0 , 0 , 0 ,,
     1.5     1.5
  519.95  554.23
     1.5     1.5
  519.95  554.23
Pier Skew, UpSta & Num, DnSta & Num=  ,70, 2 ,70, 2 , 0 , 0 , 0 ,,
     1.5     1.5
  519.95  554.23
     1.5     1.5
  519.95  554.23
Pier Skew, UpSta & Num, DnSta & Num=  ,84, 2 ,84, 2 , 0 , 0 , 0 ,,
     1.5     1.5
  519.95  554.23
     1.5     1.5
  519.95  554.23
Pier Skew, UpSta & Num, DnSta & Num=  ,98, 2 ,98, 2 , 0 , 0 , 0 ,,
     1.5     1.5
  519.95  554.23
     1.5     1.5
  519.95  554.23
Pier Skew, UpSta & Num, DnSta & Num=  ,112, 2 ,112, 2 , 0 , 0 , 0 ,,
     1.5     1.5
  519.95  554.23
     1.5     1.5
  519.95  554.23
Pier Skew, UpSta & Num, DnSta & Num=  ,126, 2 ,126, 2 , 0 , 0 , 0 ,,
     1.5     1.5
  519.95  554.23
     1.5     1.5
  519.95  554.23
Pier Skew, UpSta & Num, DnSta & Num=  ,140, 2 ,140, 2 , 0 , 0 , 0 ,,
     1.5     1.5
  519.95  554.23
     1.5     1.5
  519.95  554.23
Pier Skew, UpSta & Num, DnSta & Num=  ,154, 2 ,154, 2 , 0 , 0 , 0 ,,
     1.5     1.5
  519.95  554.23
     1.5     1.5
  519.95  554.23
Pier Skew, UpSta & Num, DnSta & Num=  ,168, 2 ,168, 2 , 0 , 0 , 0 ,,
     1.5     1.5
  519.95  554.23
     1.5     1.5
  519.95  554.23
Pier Skew, UpSta & Num, DnSta & Num=  ,182, 2 ,182, 2 , 0 , 0 , 0 ,,
     1.5     1.5
  519.95  554.23
     1.5     1.5
  519.95  554.23
Pier Skew, UpSta & Num, DnSta & Num=  ,196, 2 ,196, 2 , 0 , 0 , 0 ,,
     1.5     1.5
  519.95  554.23
     1.5     1.5
  519.95  554.23
Pier Skew, UpSta & Num, DnSta & Num=  ,210, 2 ,210, 2 , 0 , 0 , 0 ,,
     1.5     1.5
  519.95  554.23
     1.5     1.5
  519.95  554.23
Pier Skew, UpSta & Num, DnSta & Num=  ,224, 2 ,224, 2 , 0 , 0 , 0 ,,
     1.5     1.5
  519.95  554.23
     1.5     1.5
  519.95  554.23
Pier Skew, UpSta & Num, DnSta & Num=  ,238, 2 ,238, 2 , 0 , 0 , 0 ,,
     1.5     1.5
  519.95  554.23
     1.5     1.5
  519.95  554.23
Pier Skew, UpSta & Num, DnSta & Num=  ,252, 2 ,252, 2 , 0 , 0 , 0 ,,
     1.5     1.5
  519.95  554.23
     1.5     1.5
  519.95  554.23
Pier Skew, UpSta & Num, DnSta & Num=  ,266, 2 ,266, 2 , 0 , 0 , 0 ,,
     1.5     1.5
  519.95  554.23
     1.5     1.5
  519.95  554.23
Pier Skew, UpSta & Num, DnSta & Num=  ,280, 2 ,280, 2 , 0 , 0 , 0 ,,
     1.5     1.5
  519.95  554.23
     1.5     1.5
  519.95  554.23
Pier Skew, UpSta & Num, DnSta & Num=  ,294, 2 ,294, 2 , 0 , 0 , 0 ,,
     1.5     1.5
  519.95  554.23
     1.5     1.5
  519.95  554.23
Pier Skew, UpSta & Num, DnSta & Num=  ,308, 2 ,308, 2 , 0 , 0 , 0 ,,
     1.5     1.5
  519.95  554.23
     1.5     1.5
  519.95  554.23
Pier Skew, UpSta & Num, DnSta & Num=  ,322, 2 ,322, 2 , 0 , 0 , 0 ,,
     1.5     1.5
  519.95  554.23
     1.5     1.5
  519.95  554.23
Pier Skew, UpSta & Num, DnSta & Num=  ,336, 2 ,336, 2 , 0 , 0 , 0 ,,
     1.5     1.5
  519.95  554.23
     1.5     1.5
  519.95  554.23
Pier Skew, UpSta & Num, DnSta & Num=  ,350, 2 ,350, 2 , 0 , 0 , 0 ,,
     1.5     1.5
  519.95  554.23
     1.5     1.5
  519.95  554.23
Pier Skew, UpSta & Num, DnSta & Num=  ,364, 2 ,364, 2 , 0 , 0 , 0 ,,
     1.5     1.5
  519.95  554.23
     1.5     1.5
  519.95  554.23
Pier Skew, UpSta & Num, DnSta & Num=  ,378, 2 ,378, 2 , 0 , 0 , 0 ,,
     1.5     1.5
  519.95  554.23
     1.5     1.5
  519.95  554.23
Pier Skew, UpSta & Num, DnSta & Num=  ,392, 2 ,392, 2 , 0 , 0 , 0 ,,
     1.5     1.5
  519.95  554.23
     1.5     1.5
  519.95  554.23
Pier Skew, UpSta & Num, DnSta & Num=  ,406, 2 ,406, 2 , 0 , 0 , 0 ,,
     1.5     1.5
  519.95  554.23
     1.5     1.5
  519.95  554.23
Pier Skew, UpSta & Num, DnSta & Num=  ,420, 2 ,420, 2 , 0 , 0 , 0 ,,
     1.5     1.5
  519.95  554.23
     1.5     1.5
  519.95  554.23
Pier Skew, UpSta & Num, DnSta & Num=  ,434, 2 ,434, 2 , 0 , 0 , 0 ,,
     1.5     1.5
  519.95  554.23
     1.5     1.5
  519.95  554.23
Pier Skew, UpSta & Num, DnSta & Num=  ,448, 2 ,448, 2 , 0 , 0 , 0 ,,
     1.5     1.5
  519.95  554.23
     1.5     1.5
  519.95  554.23
Pier Skew, UpSta & Num, DnSta & Num=  ,462, 2 ,462, 2 , 0 , 0 , 0 ,,
     1.5     1.5
  519.95  554.23
     1.5     1.5
  519.95  554.23
Pier Skew, UpSta & Num, DnSta & Num=  ,476, 2 ,476, 2 , 0 , 0 , 0 ,,
     1.5     1.5
  519.95  554.23
     1.5     1.5
  519.95  554.23
Pier Skew, UpSta & Num, DnSta & Num=  ,490, 2 ,490, 2 , 0 , 0 , 0 ,,
     1.5     1.5
  519.95  554.23
     1.5     1.5
  519.95  554.23
BR Coef=-1 , 0 , 0 ,, 0 ,,,0.8,-1,,0,
WSPro=,,,, 1 ,,,, 0 ,,,, 0 ,,,,-1 ,-1 ,-1 , 0 , 0 , 0 , 0 , 0
BC Design=,, 0 ,, 0 ,,35,14,14,14,1.5
BC Use User HTab Curves=0
BC User HTab FreeFlow(D)= 0

Type RM Length L Ch R = 1 ,8130    ,364,364,737
BEGIN DESCRIPTION:
This cross section corresponds to cross section 8167.880 of the non-georeferenced CDC model which was the source of this model.
Downstream of BNSF Railroad.
Effective flow limit in LOB set at Clear Fork Levee Loop.
Effective flow limit in LOB set at Water Works Levee.
Trinity Park in LOB.
Rock riprap and concrete paving on right bank slope from downstream cross-section to up[stream channel dam.
END DESCRIPTION:
XS GIS Cut Line= 6
2320644.508806036956229.67286777  2320683.743618 6956054.0028004
 2320715.5722421 6955911.4932213  2320754.577215 6955786.0447284
 2320869.0621262 6955517.75348772321392.196538286954322.71891204
#Sta/Elev= 30
    -180     552     .25  546.95   18.74  540.31   54.16  538.84   78.02  540.79
  132.48  540.04  186.78  538.04  198.44  534.22  211.39  538.39  468.84  542.46
   502.3     550  527.29     550  566.98  542.17  594.98   542.5  608.61  536.73
  626.35  538.54  633.76  541.78  677.72  542.96 1019.68  545.12 1052.65  544.96
  1117.4  520.99  1174.4  519.95  1219.2  520.74  1221.8  523.94 1225.51  524.74
 1277.42  543.99 1312.04  551.95 1368.22  551.02 1458.79  555.08 1873.61  551.91
#Mann= 5 ,-1,0
    -180     .15       0 1019.68    .055       0 1052.65    .035       0
 1225.51    .025       0 1277.42    .055       0
#XS Ineff= 5 ,-1
    1725 1873.61     560    -180       0     560 1480.53    1725  555.09
       0     527     543     527 1052.65     543
Permanent Ineff=
       F       F       F       F       F
Bank Sta=1052.65,1277.42
XS Rating Curve= 0 ,0
Exp/Cntr=0.5,0.3

Type RM Length L Ch R = 1 ,7766    ,598,598,735
BEGIN DESCRIPTION:
This cross section corresponds to cross section 7791.853 of the non-georeferenced CDC model which was the source of this model.
Effective flow limit in LOB set at Clear Fork Levee Loop.
Effective flow limit in LOB set at Water Works Levee.
Trinity Park in LOB.
END DESCRIPTION:
XS GIS Cut Line= 3
2320646.349912686956238.84453246  2320995.966579 6955594.8138381
2321582.839015096955029.41237148
#Sta/Elev= 30
       0  552.62    7.85   549.4   50.44   547.6   83.93  540.37  195.63  540.77
  263.77  538.82  294.65  540.42  349.03   537.7  447.47  538.18   542.5  541.25
  611.43  538.67   856.3  541.93   893.9     540   900.5     534  910.28     534
  920.91  538.73  963.42     542 1159.86   543.9 1201.88  544.44 1238.96  529.95
 1243.43     522  1298.2   519.5 1372.43     522 1376.19     526 1420.89  543.58
  1433.8  545.96 1506.02  546.52 1512.98  550.18 1532.29  549.52 1547.73  555.07
#Mann= 4 ,-1,0
       0     .15       0 1159.86    .055       0 1201.88    .035       0
  1433.8    .055       0
#XS Ineff= 2 ,-1
    47.7  158.85     560  158.85 1201.88   543.6
Permanent Ineff=
       F       F
Bank Sta=1201.88,1433.8
XS Rating Curve= 0 ,0
Exp/Cntr=0.3,0.1

Type RM Length L Ch R = 1 ,7168    ,198,198,204
BEGIN DESCRIPTION:
This cross section corresponds to cross section 7194.381 of the non-georeferenced CDC model which was the source of this model.
Effective flow limit in LOB set at Clear Fork Levee Loop.
Effective flow limit in LOB set at Water Works Levee.
Trinity Park in LOB.
END DESCRIPTION:
XS GIS Cut Line= 2
 2320698.8124336 6956272.5812615 2322047.9338491  6955519.756648
#Sta/Elev= 30
       0  555.99   26.28  554.84   43.37  549.35   82.47  540.37  252.72   539.5
  279.63  541.55  286.43     540  458.19  539.72  572.18  541.77  914.43  542.86
  985.19  540.86  995.41  542.18 1007.64  543.85 1059.74  540.39 1078.13  542.22
 1114.74  528.97 1132.03   528.7  1138.4     524 1153.45   519.5 1173.45     519
 1263.45   519.8 1319.03  541.06  1357.5  539.63 1394.37     544 1473.18     544
  1485.9  542.59 1504.63  546.95 1518.46  548.25 1536.61  555.86 1544.95  555.87
#Mann= 4 ,-1,0
       0     .15       0  995.41    .055       0 1078.13    .035       0
 1319.03    .055       0
#XS Ineff= 2 ,-1
       0  122.76     560  122.76 1078.13   542.5
Permanent Ineff=
       F       F
Bank Sta=1078.13,1319.03
XS Rating Curve= 0 ,0
Exp/Cntr=0.3,0.1

Type RM Length L Ch R = 1 ,6970    ,201,201,200
BEGIN DESCRIPTION:
This cross section corresponds to cross section 6696.185 of the non-georeferenced CDC model which was the source of this model.
Effective flow limit in LOB set at Clear Fork Levee Loop.
Effective flow limit in LOB set at Water Works Levee.
Trinity Park in LOB.
END DESCRIPTION:
XS GIS Cut Line= 2
 2320744.4680748 6956450.8315387 2322192.1879614 6955672.8052456
#Sta/Elev= 30
       0  557.19   31.13  547.48   54.38  542.29   177.7  538.93  283.33  540.69
  307.51   540.3  319.62     538  330.46  539.26  457.61  538.96  630.28  542.73
  879.97   542.6 1016.62   540.6  1023.1  541.28 1040.26  543.01 1129.16  542.63
 1165.86   526.5 1186.77  526.66  1209.5   519.5  1229.5   518.5  1319.5   519.8
 1363.96  535.03 1404.65  535.79 1463.29   541.9 1486.95  542.38 1548.42     542
 1562.73  537.62 1580.47  544.75 1601.32  544.57 1630.94  550.16 1643.54  553.92
#Mann= 4 ,-1,0
       0     .15       0  1023.1    .055       0 1129.16    .035       0
 1363.96    .055       0
#XS Ineff= 2 ,-1
       0  199.36     560  199.36 1129.16  542.63
Permanent Ineff=
       F       F
Bank Sta=1129.16,1363.96
XS Rating Curve= 0 ,0
Exp/Cntr=0.3,0.1

Type RM Length L Ch R = 1 ,6769    ,40,40,40
BEGIN DESCRIPTION:
This cross section corresponds to cross section 6795.375 of the non-georeferenced CDC model which was the source of this model.
Upstream of Trinity Park channel dam.
Effective flow limit in LOB set at Clear Fork Levee Loop.
Effective flow limit in LOB set at Water Works Levee.
Trinity Park in LOB.
END DESCRIPTION:
XS GIS Cut Line= 3
 2320798.9380358 6956612.7608307 2321855.3766364 6956083.4633345
 2322315.4712471 6955826.6407436
#Sta/Elev= 30
       0  556.17   27.48  553.09   75.83  541.37  136.18  539.39  227.25  538.15
  373.48     540  383.36  541.37   450.3  538.19  673.25  543.22 1020.17  540.43
 1036.16  542.22 1050.11  540.03 1079.31  542.03 1168.68  540.41 1201.72  527.36
  1227.9  524.91 1247.75   519.4 1267.75   518.4    1353   519.7 1356.49     524
 1369.27  525.52  1390.2  531.12 1415.82  533.61 1529.07  538.04 1548.33  541.44
 1598.78  540.78 1624.92  537.51 1645.65  543.54 1665.29  543.46 1708.54  554.16
#Mann= 4 ,-1,0
       0     .15       0 1020.17    .055       0 1168.68    .035       0
 1415.82    .055       0
#XS Ineff= 3 ,-1
       0  259.74     560  259.74 1078.68   542.5 1168.68 1415.82   522.3
Permanent Ineff=
       F       F       T
Bank Sta=1168.68,1415.82
XS Rating Curve= 0 ,0
Exp/Cntr=0.3,0.1