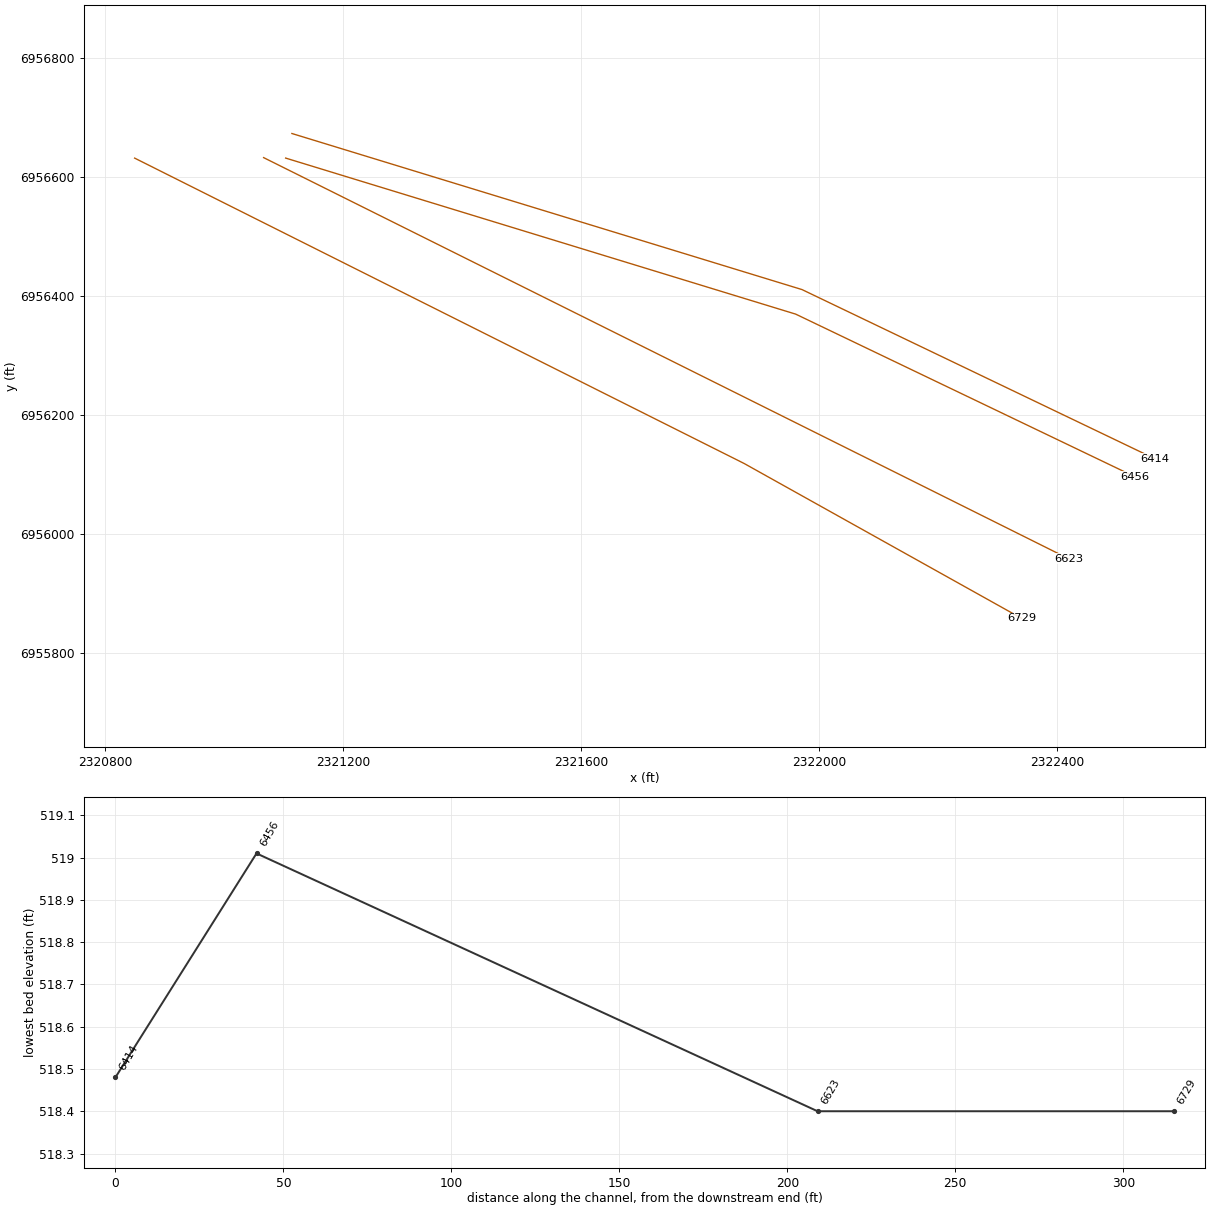
HEC-RAS study CDC_Consolidated_Model.prj: Upper Trinity CDC Consolidated Model

--- CDC_Consolidated_Model.g03 (geometry) --- (continued)

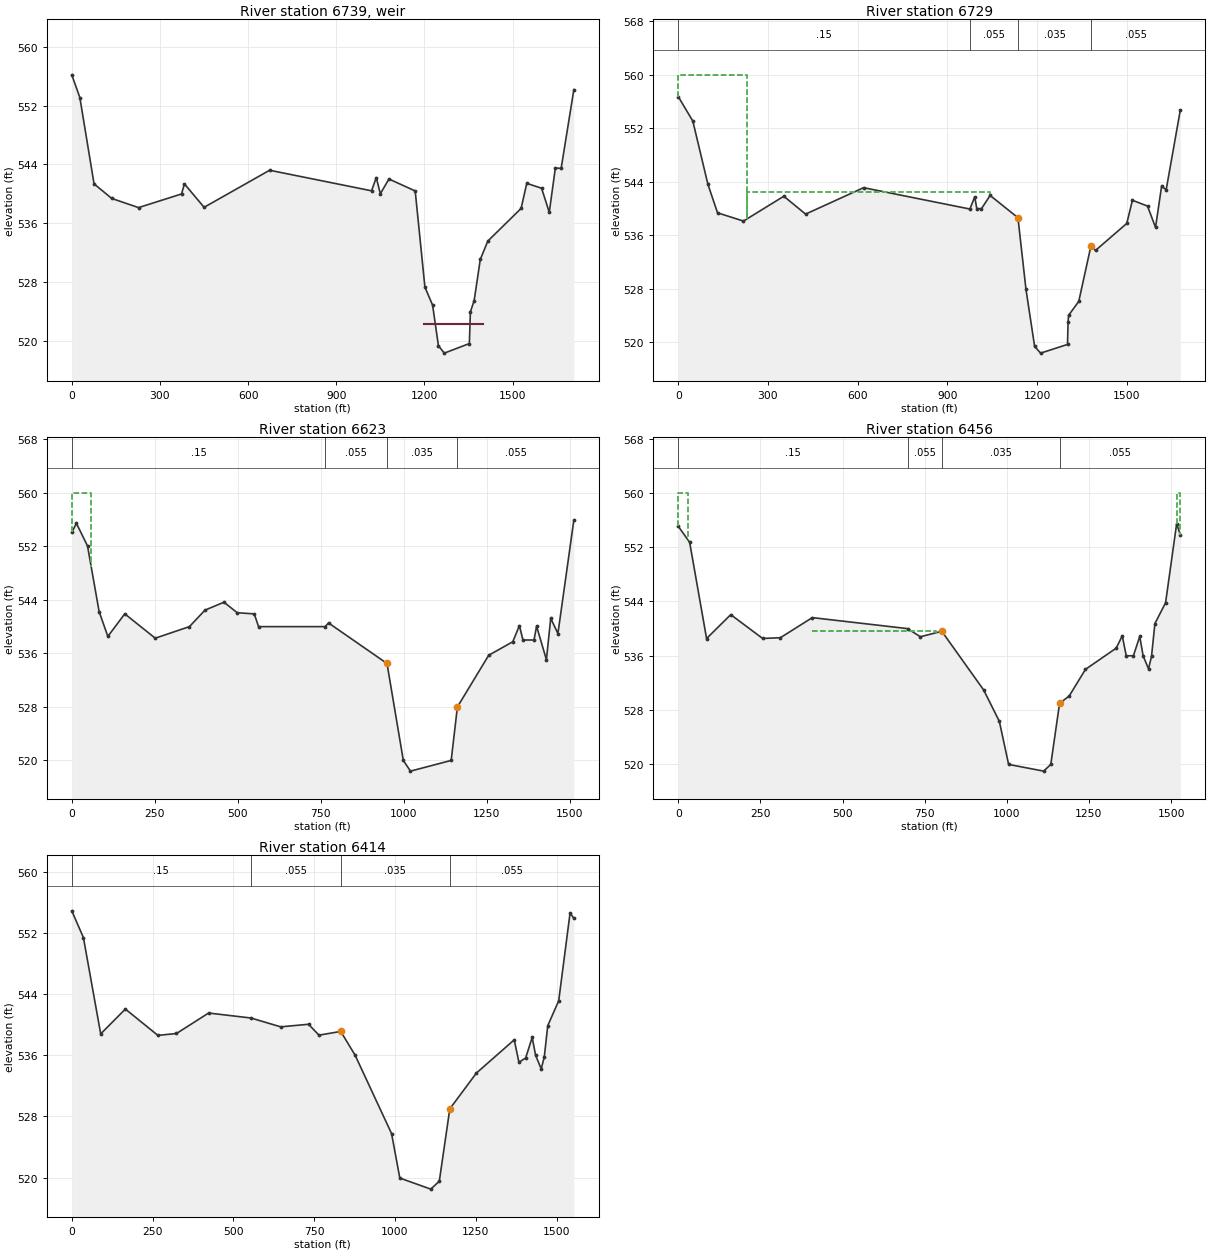
Type RM Length L Ch R = 5 ,6739    ,,,
BEGIN DESCRIPTION:
Trinity Park channel dam
Structure reconstructed by TRWD.  Survey data from TRWD May 2007.
END DESCRIPTION:
Node Name=channel dam
IW Pilot Flow=0
#Inline Weir SE= 2
    1200   522.3    1400   522.3
IW Dist,WD,Coef,Skew,MaxSub,Min_El,Is_Ogee,SpillHt,DesHd
13.36,20,3,0,0.95,, 0 ,,,2,2,
Inline Weir Flap Gates= 0
IW Outlet Rating Curve= 0 ,False,,

Type RM Length L Ch R = 1 ,6729    ,106,106,119
BEGIN DESCRIPTION:
This cross section corresponds to cross section 6755.375 of the non-georeferenced CDC model which was the source of this model.
Downstream of Trinity Park channel dam.
Effective flow limit in LOB set at Clear Fork Levee Loop.
Effective flow limit in LOB set at Water Works Levee.
Trinity Park in LOB.
END DESCRIPTION:
XS GIS Cut Line= 3
 2320849.7142326 6956632.0604991 2321874.0929356 6956118.8256204
 2322340.1630619 6955858.6678429
#Sta/Elev= 30
       0  556.75   48.75  553.09   99.28  543.63  131.51  539.37  218.26  538.14
  353.14  541.85  426.06  539.18  620.03  543.13  975.63  539.94  991.73  541.75
  998.78     540 1014.45     540 1043.37  541.97 1136.39  538.64 1163.26  527.92
  1192.2   519.4  1212.2   518.4  1302.2   519.7    1304     523 1305.82  524.05
 1339.81  526.13 1380.58  534.43 1395.83  533.75 1500.51  537.79 1519.26  541.25
  1569.8  540.38 1596.65  537.19 1616.83  543.32 1632.29  542.83 1679.52  554.73
#Mann= 4 ,-1,0
       0     .15       0  975.63    .055       0 1136.39    .035       0
 1380.58    .055       0
#XS Ineff= 2 ,-1
       0  231.37     560  231.37 1043.37   542.5
Permanent Ineff=
       F       F
Bank Sta=1136.39,1380.58
XS Rating Curve= 0 ,0
Exp/Cntr=0.3,0.1

Type RM Length L Ch R = 1 ,6623    ,167,167,185
BEGIN DESCRIPTION:
This cross section corresponds to cross section 6650.128 of the non-georeferenced CDC model which was the source of this model.
Effective flow limit in LOB set at Clear Fork Levee Loop.
Effective flow limit in LOB set at Water Works Levee.
Trinity Park in LOB.
END DESCRIPTION:
XS GIS Cut Line= 4
 2321066.4973425 6956632.9008101 2322317.2900947 6956009.7091124
 2322399.1968025 6955968.9001293 2322419.8547963 6955958.6075447
#Sta/Elev= 30
       0  554.09   14.02  555.44   47.44  552.06   82.42  542.24  108.64  538.54
  159.62  541.91  251.39  538.27  354.34     540  401.06  542.46  458.32  543.65
  498.29  542.08  549.69   541.9  562.51     540  763.12     540  773.22  540.55
  949.37  534.49  998.48     520    1020   518.4 1142.62     520 1161.37     528
 1255.62  535.72 1328.14  537.74 1348.13  540.15 1358.75     538 1392.05     538
  1399.8  540.07 1429.43  535.05 1442.35  541.24 1464.09  538.97 1512.03  555.92
#Mann= 4 ,-1,0
       0     .15       0  763.12    .055       0  949.37    .035       0
 1161.37    .055       0
#XS Ineff= 3 ,-1
       0   58.45     560   58.45  478.32     542 1348.13 1512.03  540.15
Permanent Ineff=
       F       F       F
Bank Sta=949.37,1161.37
XS Rating Curve= 0 ,0
Exp/Cntr=0.3,0.1

Type RM Length L Ch R = 1 ,6456    ,42,42,68
BEGIN DESCRIPTION:
This cross section corresponds to cross section 6482.044 of the non-georeferenced CDC model which was the source of this model.
Effective flow limit in LOB set at Clear Fork Levee Loop.
Effective flow limit in LOB set at Water Works Levee.
Trinity Park in LOB.
END DESCRIPTION:
XS GIS Cut Line= 3
 2321103.5022665 6956632.1273921 2321960.9341838 6956369.7928697
 2322530.4534314 6956096.7357618
#Sta/Elev= 30
       0  555.08   34.75  552.71   86.27  538.54  159.84  542.06  256.89  538.55
  310.93  538.66  408.02  541.62  697.96     540  737.22   538.8  802.23  539.61
  929.81  530.95  977.35  526.35 1005.64     520  1112.3  519.01 1134.01     520
 1160.71  528.98 1190.27  530.09  1239.6     534 1333.03  537.12  1351.6  538.94
 1363.65     536 1385.45     536  1404.8  538.85 1415.01     536 1431.58  534.07
  1440.7  535.95 1450.93  540.74 1483.42  543.81 1517.13  555.45 1528.26  553.81
#Mann= 4 ,-1,0
       0     .15       0  697.96    .055       0  802.23    .035       0
 1160.71    .055       0
#XS Ineff= 5 ,-1
       0   29.78     560 1517.13 1528.26     560   29.78     406  541.28
  1351.6 1517.13  538.94     406  785.24   539.7
Permanent Ineff=
       F       T       F       F       F
Bank Sta=802.23,1160.71
XS Rating Curve= 0 ,0
Exp/Cntr=0.5,0.3

Type RM Length L Ch R = 1 ,6414    ,18,18,29
BEGIN DESCRIPTION:
This cross section corresponds to cross section 6440 of the non-georeferenced CDC model which was the source of this model.
Effective flow limit in LOB set at Clear Fork Levee Loop.
Effective flow limit in LOB set at Water Works Levee.
Trinity Park in LOB.
Interpolated cross-section.
---------------------------------------------------------------------
CDC FW040910-01 TILLEY (LANCASTER) PEDESTRIAN BRIDGE
CROSS-SECTION 6273 - 6440
UPSTREAM END.
-----------------------------------------------------
END DESCRIPTION:
XS GIS Cut Line= 4
2321114.046940116956673.422515362321971.478857416956411.08799296
2322540.998105016956138.030885062322563.910733346956127.04538096
#Sta/Elev= 30
       0  554.94   36.06  551.43   89.51  538.82  165.85  542.07  266.54  538.62
  324.06  538.87  423.35  541.55   554.3   540.9  646.59  539.74  732.77  540.08
  764.92  538.65  832.38  539.14  876.88  536.02  989.69  525.75  1015.1  519.93
 1110.93  518.48 1137.35  519.52 1169.85     529 1252.23  533.69 1369.19  538.04
 1383.71   535.1 1404.54  535.66 1424.75  538.35 1435.41     536 1452.71  534.23
 1462.23   535.8 1472.92  539.89 1506.85  543.16 1542.05  554.68 1553.67  553.95
#Mann= 4 ,-1,0
       0     .15       0   554.3    .055       0  832.38    .035       0
 1169.85    .055       0
Bank Sta=832.38,1169.85
XS Rating Curve= 0 ,0
Exp/Cntr=0.5,0.3