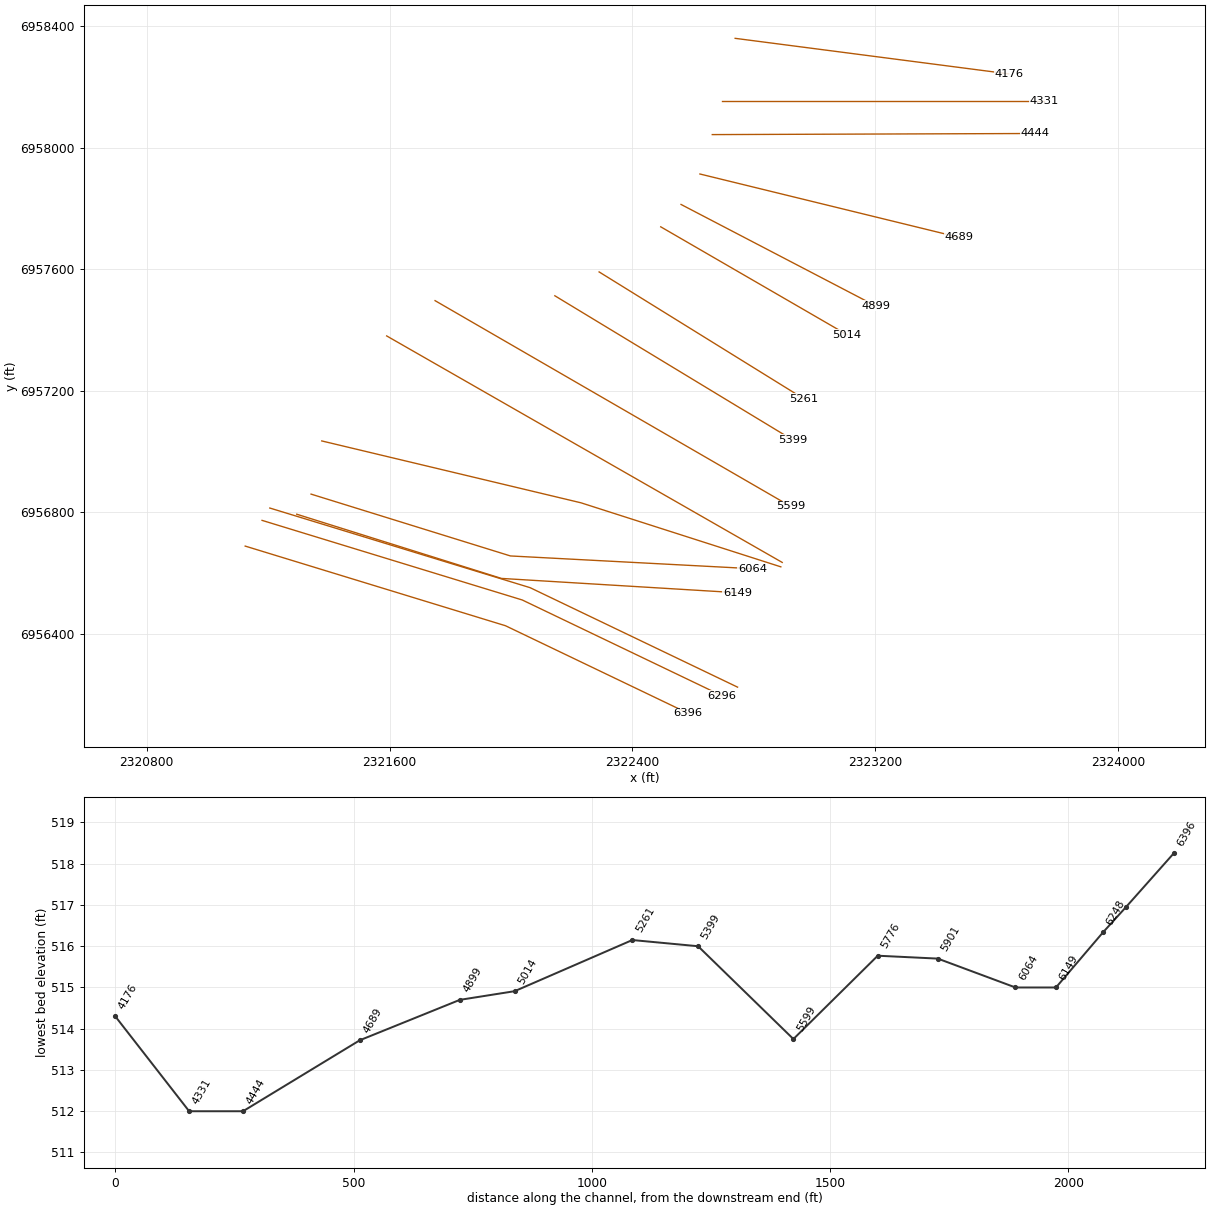
HEC-RAS study CDC_Consolidated_Model.prj: Upper Trinity CDC Consolidated Model

--- CDC_Consolidated_Model.g03 (geometry) --- (continued)

Type RM Length L Ch R = 3 ,6403    ,,,
BEGIN DESCRIPTION:
Tilley Pedestrian Bridge
Data from bridge plans.  Concrete paving under bridge at river side slopes.
END DESCRIPTION:
Node Name=Tilley pedestria
Bridge Culvert--1,0,-1,-1, 0
Deck Dist Width WeirC Skew NumUp NumDn MinLoCord MaxHiCord MaxSubmerge Is_Ogee
2.5,13,2.6,0, 37, 37, , , 0.98, 0, 0,0,,
     822     872     922     932     942     952     962     972     982     992
    1002    1012    1022    1022    1032    1042    1052    1062    1072    1082
    1092    1102    1112    1122    1122    1132    1142    1152    1162    1172
    1182    1192    1202    1212    1222    1272    1322
  537.32  537.32  537.32  537.32  537.52  537.72  538.07  538.42  538.92  539.42
  540.12  540.92  541.52  541.52  542.42  543.52  544.12  544.42  544.62  544.42
  544.12  543.52  542.42  541.52  541.52  540.92  540.12  539.42  538.92  538.42
  538.07  537.72  537.52  537.32  537.32  537.32  537.32
  534.32  534.32  534.32  534.32  534.52  534.72  535.07  535.42  535.92  536.42
  537.12  537.92  538.52  535.69  536.59  537.69  538.29  538.59  538.79  538.59
  538.29  537.69  536.59  535.69  538.52  537.92  537.12  536.42  535.92  535.42
  535.07  534.72  534.52  534.32  534.32  534.32  534.32
     822     872     922     932     942     952     962     972     982     992
    1002    1012    1022    1022    1032    1042    1052    1062    1072    1082
    1092    1102    1112    1122    1122    1132    1142    1152    1162    1172
    1182    1192    1202    1212    1222    1272    1322
  537.32  537.32  537.32  537.32  537.52  537.72  538.07  538.42  538.92  539.42
  540.12  540.92  541.52  541.52  542.42  543.52  544.12  544.42  544.62  544.42
  544.12  543.52  542.42  541.52  541.52  540.92  540.12  539.42  538.92  538.42
  538.07  537.72  537.52  537.32  537.32  537.32  537.32
  534.32  534.32  534.32  534.32  534.52  534.72  535.07  535.42  535.92  536.42
  537.12  537.92  538.52  535.69  536.59  537.69  538.29  538.59  538.79  538.59
  538.29  537.69  536.59  535.69  538.52  537.92  537.12  536.42  535.92  535.42
  535.07  534.72  534.52  534.32  534.32  534.32  534.32
Pier Skew, UpSta & Num, DnSta & Num=  ,1057, 2 ,1070, 2 , 0 , 0 , 0 ,,
       2       2
     518     540
       2       2
     518     540
Pier Skew, UpSta & Num, DnSta & Num=  ,1067, 2 ,1080, 2 , 0 , 0 , 0 ,,
       2       2
     518     540
       2       2
     518     540
Pier Skew, UpSta & Num, DnSta & Num=  ,1077, 2 ,1090, 2 , 0 , 0 , 0 ,,
       2       2
     518     540
       2       2
     518     540
Pier Skew, UpSta & Num, DnSta & Num=  ,1087, 2 ,1100, 2 , 0 , 0 , 0 ,,
       2       2
     518     540
       2       2
     518     540
BR Coef=-1 , 0 , 0 ,, 0 ,,,0.8,-1,,0,
WSPro=,,,, 1 ,,,, 0 ,,,, 0 ,,,,-1 ,-1 ,-1 , 0 , 0 , 0 , 0 , 0
BR U #Sta/Elev= 495
       0  554.94     .74  554.91    2.45  554.82    5.03  554.56   11.36  553.93
   12.22  553.86   13.13  553.77   13.43  553.75   14.17  553.67   15.33  553.51
   16.27  553.39   18.88  553.03   19.93  552.91   22.36  552.59   23.02  552.52
    25.1  552.28   29.94  551.86   30.56  551.79   31.35  551.68   32.67  551.57
   34.01  551.51   36.06  551.43   37.11  551.21   37.87  551.02   38.77  550.84
   40.23  550.47   42.24     550   43.01  549.81   44.24  549.52   46.05  549.07
   47.23  548.75   47.87  548.59   49.67   548.1   50.35  547.92    51.8   547.6
   53.12  547.29   55.94  546.66   58.06  546.16   59.63  545.77   60.58  545.52
   63.38  544.82   64.32  544.59   65.89  544.19   68.04  543.66   69.11  543.38
   71.41  542.95   73.66  542.44   75.48  542.06   75.58  542.03   77.52   541.6
   80.35     541   84.43  540.05    87.9  539.24   89.01  538.96   89.51  538.82
   92.33   538.9   101.6  539.15  110.51  539.32  111.07  539.32  113.69  539.67
  118.65  540.27  120.89  540.41   122.8  540.52  126.01  540.72  129.02  540.84
  130.98  540.95  133.34  541.09  134.45  541.16  141.64  541.64  144.92  541.66
  148.36  541.69  148.83  541.69  150.33  541.72  156.25  541.91  157.38  541.96
  161.27  542.01  163.86  542.03  165.27  542.02  165.85  542.07  167.25  542.02
  168.27  541.99  169.66  541.94  171.43  541.91  172.63  541.86  176.23  541.75
  178.31  541.68  181.77  541.55  184.54  541.43  188.12  541.26  191.63  541.09
  192.55  541.04  197.14   540.8  199.24   540.7  204.63  540.45  206.29  540.35
  208.15  540.26  211.46  540.08  212.85  540.05  216.99  539.93  218.39   539.9
   220.2  539.87  224.99   539.8  226.68  539.76  234.14  539.62  248.93  539.17
  255.41  538.99  257.59  538.92  266.54  538.62  287.44  538.71  304.91  538.78
  310.22   538.8  314.56  538.81  316.57  538.82  320.31  538.82   321.6  538.83
  324.06  538.87  327.81  538.95  330.24  538.99  330.43     539  334.29  539.08
  337.25  539.15   346.8  539.41  368.15  540.06  382.66  540.51  387.82  540.64
  421.33  541.53  423.35  541.55  428.73  541.55  430.58  541.54  432.47  541.54
  436.05  541.52  437.71   541.5  443.06  541.47  471.01   541.6   486.4  541.58
  493.78  541.56  497.72  541.56  502.42  541.57  508.73  541.41  509.55  541.41
  512.39  541.39   514.6  541.37  518.71   541.3  519.04  541.29  529.08  541.14
  541.05  540.94     551  540.91  551.92   540.9   554.3   540.9  555.55  540.89
  559.44  540.88  560.68  540.88  562.37   540.9  563.05   540.9  567.19  540.94
  569.47  540.85  574.56  540.68  580.39  540.56   585.3  540.47  585.65  540.46
  587.18  540.44  587.81  540.44   589.9  540.41   590.6  540.41  594.51  540.37
   608.5   540.3  614.26  540.23   618.7  540.23  621.61  540.21  625.47  540.24
   627.1  540.22  627.44  540.23  630.56  540.28  634.29  540.33  635.03  540.32
   639.9  540.04  640.44     540  641.33  539.95  642.94  539.83  643.99  539.76
  646.08  539.75  646.59  539.74  648.24  539.76  649.07  539.76  650.74  539.78
  651.46  539.78  653.01   539.8  653.85   539.8  656.65  539.83  657.61  539.83
   658.1  539.84  659.69  539.85  660.22  539.86  661.02  539.86  664.12  539.89
  664.68  539.89  669.18  540.15  673.12  540.37  675.22  540.27  677.11  540.17
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BR U #Mann= 7
       0     .15   554.3    .055  832.38    .035  888.17    .014  1015.1    .035
 1137.35    .014 1268.37    .055
BR D #Sta/Elev= 495
       0  554.88    2.49  554.74    5.11  554.48   10.41  553.94   11.54  553.83
   12.41  553.76   13.01  553.69   13.64  553.64   14.39  553.56   16.52  553.24
   19.17  552.83   20.24  552.69   22.71  552.33   25.49  551.96    30.4  551.44
   31.03  551.36   31.84  551.23   33.18  551.09   34.54     551   36.62  550.88
   37.69  550.65   38.46  550.46   39.37  550.27   40.12  550.07   44.93  548.91
   46.76  548.45   47.96  548.12   48.84   547.9   50.72  547.38   51.13  547.29
    52.6     547   53.94  546.71   54.64  546.58   56.34  546.23   56.81  546.14
   58.96  545.68   60.56  545.32   61.52  545.09   64.36  544.44   65.32  544.23
   66.91  543.87    69.5  543.29   70.18  543.12   72.52  542.73    74.8  542.26
   76.65  541.91   78.72  541.49    81.6  540.94   85.74  540.07   88.23  539.55
   89.26  539.33    90.9  538.94   93.76  539.02  103.18  539.29  112.23  539.48
  112.79  539.48  115.45  539.81  120.49  540.39  122.77  540.53  124.71  540.64
  127.97  540.84  131.02  540.94  133.01  541.03  135.41  541.15  136.53  541.22
  143.84  541.66  147.17  541.68  150.66  541.71  151.14  541.71  152.66  541.74
  158.68  541.95  159.82  542.01  163.77  542.04   166.4  542.05  166.55  542.04
  167.84  542.03  168.42  542.07  170.88  541.99  172.29  541.93  174.14   541.9
   174.7  541.86  181.08  541.65  184.59  541.51   187.4  541.38  191.04   541.2
  195.54  540.97   200.2  540.71  202.33  540.61  206.51   540.4  207.81  540.34
  207.84  540.33  209.49  540.23  211.38  540.14  213.97  539.99  214.74  539.95
  216.15  539.92  220.36   539.8  221.78  539.77  223.62  539.75  228.48  539.69
   230.2  539.66  237.77  539.54  252.79  539.14  259.37  538.98  261.59  538.92
  270.68  538.65   291.9  538.77  309.64  538.85  312.08  538.87  315.03  538.88
  319.44  538.89  321.48   538.9  325.28   538.9  327.62  538.92  330.55  538.98
  331.02  538.98   332.9  539.02  335.36  539.06  336.99   539.1  339.48  539.14
  342.48  539.21  352.18  539.46  373.86  540.09   388.6  540.52  393.84  540.64
  427.87   541.5  429.92  541.52  438.56  541.52  439.18  541.51  442.82  541.49
   444.5  541.47  449.94  541.44  478.32  541.54  493.95   541.5  501.44  541.47
  510.22  541.47  513.05  541.41  515.77  541.33  517.46  541.32  520.34  541.29
  522.59  541.26  526.76  541.19  527.09  541.18  537.29  541.02  540.92  540.95
  549.45   540.8   560.1  540.81  560.49   540.8  561.55  540.81   562.9  540.81
  564.17  540.81  568.12  540.82  569.38  540.82  571.79  540.87  575.99  540.95
  577.62  540.88  578.31  540.84  583.48  540.63  585.49  540.59   589.4   540.5
  594.38   540.4  594.74  540.38  596.29  540.36  596.93  540.36  598.22  540.33
  599.77  540.32  603.74  540.27  617.94  540.19  623.79  540.12   628.3  540.12
  631.26   540.1  635.18  540.13  636.83  540.11  637.18  540.12  640.35  540.17
  644.13  540.21  644.89   540.2  649.83  539.93  651.28  539.84  652.92  539.72
  653.99  539.66  656.11  539.64  656.63  539.63   658.3  539.66  660.34  539.67
  661.22  539.69  663.49  539.71  664.62  539.73  665.97  539.74  666.84  539.76
  668.84  539.77  670.47   539.8  671.28   539.8  674.43  539.84     675  539.84
  679.57   540.1  681.78  540.22  683.57  540.33   685.7  540.24  687.62  540.15
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BR D #Mann= 7
       0     .15   562.9    .055   845.3    .035  894.61    .014 1019.16    .035
 1138.78    .014 1276.94    .055
BC Design=,, 0 ,, 0 ,,,,,,
BC Use User HTab Curves=0
BC User HTab FreeFlow(D)= 0

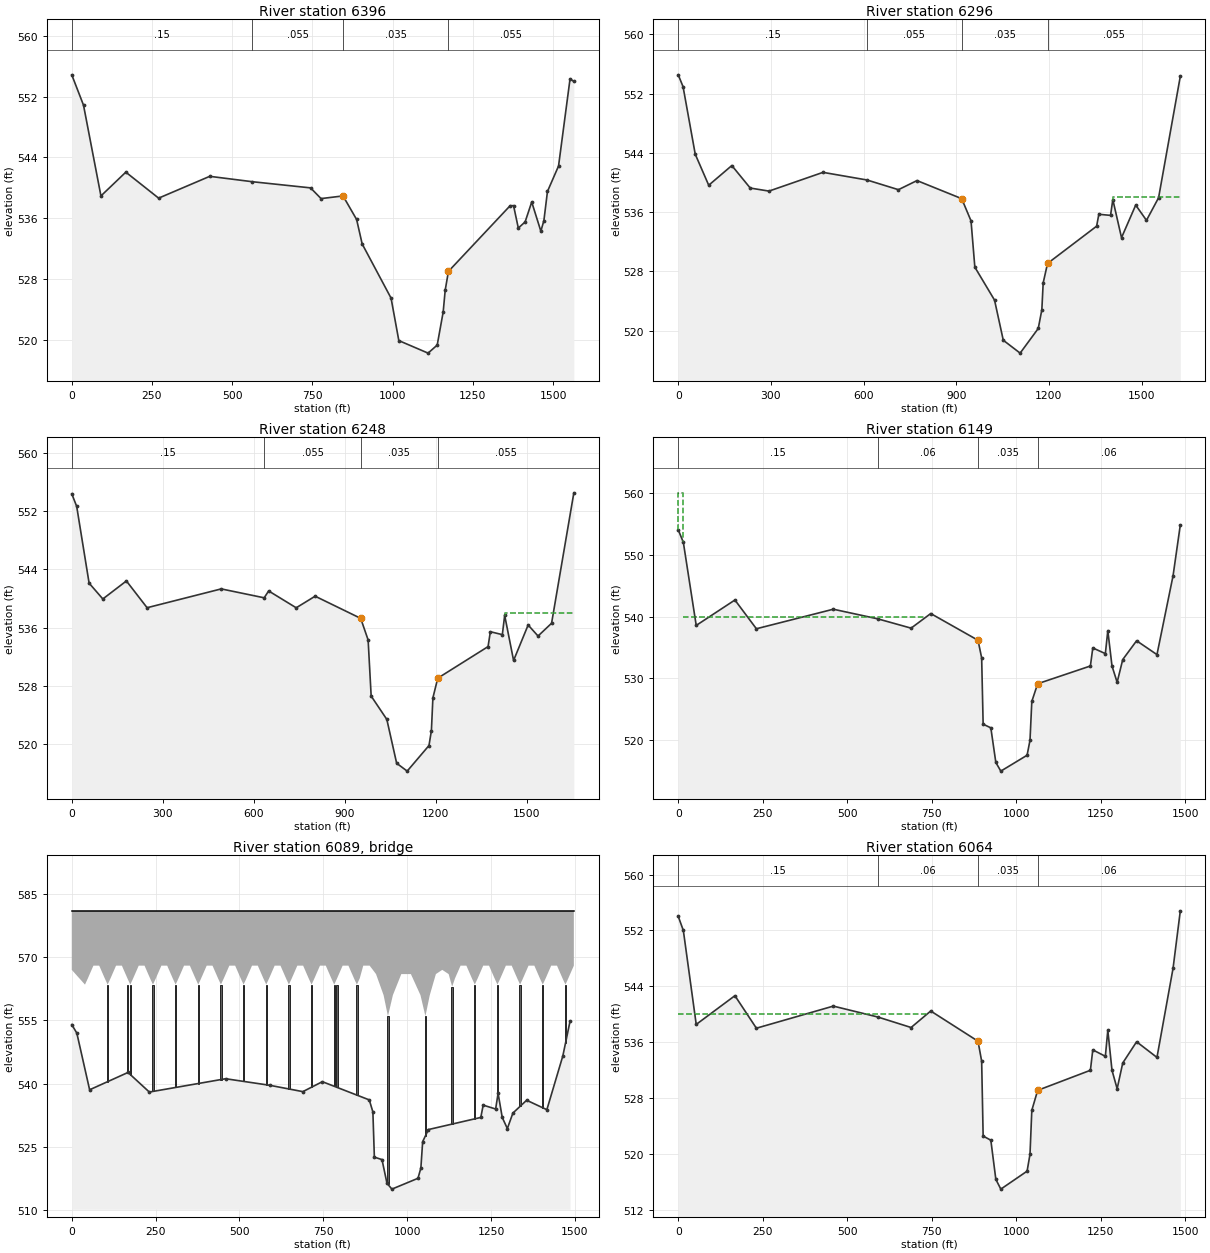
Type RM Length L Ch R = 1 ,6396    ,100,100,164
BEGIN DESCRIPTION:
This cross section corresponds to cross section 6422 of the non-georeferenced CDC model which was the source of this model.
Effective flow limit in LOB set at Clear Fork Levee Loop.
Effective flow limit in LOB set at Water Works Levee.
Trinity Park in LOB.
Interpolated cross-section.
END DESCRIPTION:
XS GIS Cut Line= 4
2321124.627604256956688.193429842321982.059521556956425.85890744
2322551.578769156956152.801799542322584.311095336956137.10822226
#Sta/Elev= 30
       0  554.88   36.62  550.88    90.9  538.94  168.42  542.07  270.68  538.65
  429.92  541.52   562.9  540.81  744.14     540  776.79  538.59   845.3  538.94
  887.64  535.84  904.95  532.62  994.98  525.49 1019.16   519.9 1110.34  518.25
 1138.78  519.31 1157.44  523.68 1163.69  526.54 1173.77  529.01 1365.95  537.65
 1376.73  537.66 1391.51  534.71 1412.72  535.52  1433.3  538.14 1461.77   534.3
 1471.23   535.7 1482.34  539.53 1516.89  542.88 1552.73  554.35 1564.56  554.01
#Mann= 4 ,-1,0
       0     .15       0   562.9    .055       0   845.3    .035       0
 1173.77    .055       0
Bank Sta=845.3,1173.77
XS Rating Curve= 0 ,0
Exp/Cntr=0.5,0.3

Type RM Length L Ch R = 1 ,6296    ,48,48,77
BEGIN DESCRIPTION:
This cross section corresponds to cross section 6321 of the non-georeferenced CDC model which was the source of this model.
Effective flow limit in LOB set at Clear Fork Levee Loop.
Effective flow limit in LOB set at Water Works Levee.
Trinity Park in LOB.
Interpolated cross-section.
END DESCRIPTION:
XS GIS Cut Line= 4
 2321180.08376416956772.95082626 2322037.51568146956510.61630386
  2322607.0349296956237.559195962322694.871092186956195.44597716
#Sta/Elev= 30
       0  554.53   15.62  552.93   55.07  543.81    98.7  539.62  173.53  542.28
  233.16  539.24  293.89  538.83  468.72  541.36  611.17  540.33  712.94  539.02
  773.06  540.25  917.79  537.81  948.02  534.81  960.38  528.56 1024.15  524.11
 1052.45  518.69 1107.03  516.95  1165.7  520.28 1177.31   522.8 1181.65  526.43
 1195.75  529.06 1354.67  534.09  1361.9   535.7 1399.77  535.55 1407.17  537.68
 1435.29  532.54 1481.27  536.94 1516.11  534.88 1555.31  537.93 1625.67  554.33
#Mann= 4 ,-1,0
       0     .15       0  611.17    .055       0  917.79    .035       0
 1195.75    .055       0
#XS Ineff= 2 , 0
                         1406.38          538.07
Permanent Ineff=
       F       F
Bank Sta=917.79,1195.75
XS Rating Curve= 0 ,0
Exp/Cntr=0.3,0.1

Type RM Length L Ch R = 1 ,6248    ,99,99,161
BEGIN DESCRIPTION:
This cross section corresponds to cross section 6273 of the non-georeferenced CDC model which was the source of this model.
Effective flow limit in LOB set at Clear Fork Levee Loop.
Effective flow limit in LOB set at Water Works Levee.
Trinity Park in LOB.
Interpolated cross-section.
---------------------------------------------------------------------
CDC FW040910-01 TILLEY (LANCASTER) PEDESTRIAN BRIDGE
CROSS-SECTION 6273 - 6440
DOWNSTREAM END
--------------------------------------------------
END DESCRIPTION:
XS GIS Cut Line= 4
2321205.684228266956813.593525862322063.116145566956551.25900346
2322632.635393166956278.201895562322746.657307216956223.53386771
#Sta/Elev= 30
       0  554.36   16.21  552.63   57.13  542.11   102.4  539.94  180.04  542.41
  248.24  538.74  492.58  541.32  634.11   540.1  648.87  541.04   739.7  538.73
  802.08  540.32  952.24  537.28  976.71  534.32  986.72  526.63 1038.35  523.43
 1070.73  517.42 1105.46  516.34 1177.29  519.85 1185.26  521.89 1190.18  526.38
 1206.19  529.08 1371.99  533.41 1379.53  535.45 1419.04  535.05 1426.76  537.69
  1456.1  531.51 1504.07  536.37 1536.74  534.86 1581.31  536.61 1654.71  554.49
#Mann= 4 ,-1,0
       0     .15       0  634.11    .055       0  952.24    .035       0
 1206.19    .055       0
#XS Ineff= 2 , 0
                         1426.88          538.07
Permanent Ineff=
       F       F
Bank Sta=952.24,1206.19
XS Rating Curve= 0 ,0
Exp/Cntr=0.5,0.3

Type RM Length L Ch R = 1 ,6149    ,85,85,75
BEGIN DESCRIPTION:
This cross section corresponds to cross section 6172.783 of the non-georeferenced CDC model which was the source of this model.
Upstream of Lancaster Avenue.
Copy of cross-section 6085.75
Effective flow limit in LOB set at Clear Fork Levee Loop, set in ROB at Water Works Levee.
Trinity Park in LOB.
This is upper end of Clear Fork bathymetry developed for the Central City project.  From this point upstream, bathymetry from 1975 USACE cross-section survey data used.
END DESCRIPTION:
XS GIS Cut Line= 3
2321294.361250946956793.24606963      2321968.76      6956581.72
2322746.102236156956534.59171968
#Sta/Elev= 30
       0  554.02  15.095     552  53.217  538.56 167.706  542.67 231.229  538.02
 458.829  541.18 590.664  539.62 688.984  538.12 747.111  540.48 886.983  536.16
 897.765  533.31 902.173  522.59 924.924     522 939.741   516.4 954.473     515
1032.224  517.571040.841     5201046.176  526.271063.488  529.131219.511     532
1226.612  534.921263.782     5341271.057  537.721283.432     5321298.666  529.36
1315.214  533.041356.229  536.081416.488  533.841464.103  546.591485.563  554.81
#Mann= 4 ,-1,0
       0     .15       0 590.664     .06       0 886.983    .035       0
1063.488     .06       0
#XS Ineff= 3 ,-1
       0  14.142     560  14.142 733.619     5401271.0571485.563  537.72
Permanent Ineff=
       F       F       F
Bank Sta=886.983,1063.488
XS Rating Curve= 0 ,0
Skew Angle= 30
Exp/Cntr=0.5,0.3

Type RM Length L Ch R = 3 ,6089    ,,,
BEGIN DESCRIPTION:
Lancaster Avenue
Bridge data bridge plans, 1975 USACE survey.  Bridge piers and stairway structures represented.
END DESCRIPTION:
Node Name=Lancaster Avenue
Bridge Culvert--1,0,-1,-1, 0
Deck Dist Width WeirC Skew NumUp NumDn MinLoCord MaxHiCord MaxSubmerge Is_Ogee
19.23,50,2.6,30, 106, 106, , , 0.95, 0, 0,0,,
       0       0  39.404  48.064  64.519  81.839  98.294 106.954 115.614 132.069
 149.389 165.844 174.504 183.164 199.619 216.939 233.394 242.054 250.714 267.169
 284.489 300.944 309.604 318.264 334.719 352.039 368.494 377.154 385.814 402.269
 419.589 436.044 444.704 453.364 469.819 487.139 503.594 512.254 520.914 537.369
 554.689 571.144 579.804 588.464 604.919 622.239 638.694 647.354 656.014 672.469
 689.789 706.244 714.904 723.564 740.019 757.339 773.794 782.454 791.114 807.569
 824.889 841.344 850.004 858.664 869.056 888.109 907.162 929.678 942.669 957.391
 982.5061011.0851039.6631054.3861067.3761085.5631104.6151123.668 1134.06 1142.72
1159.1751176.495 1192.95 1201.611210.2711226.7251244.045  1260.5 1269.16 1277.82
1294.2751311.595 1328.05 1336.71 1345.371361.8251379.145  1395.6 1404.26 1412.92
1429.3751446.695 1463.15 1471.81 1480.471496.925
     581     581     581     581     581     581     581     581     581     581
     581     581     581     581     581     581     581     581     581     581
     581     581     581     581     581     581     581     581     581     581
     581     581     581     581     581     581     581     581     581     581
     581     581     581     581     581     581     581     581     581     581
     581     581     581     581     581     581     581     581     581     581
     581     581     581     581     581     581     581     581     581     581
     581     581     581     581     581     581     581     581     581     581
     581     581     581     581     581     581     581     581     581     581
     581     581     581     581     581     581     581     581     581     581
     581     581     581     581     581     581
     500     567   563.5     565     568     568     565   563.5     565     568
     568     565   563.5     565     568     568     565   563.5     565     568
     568     565   563.5     565     568     568     565   563.5     565     568
     568     565   563.5     565     568     568     565   563.5     565     568
     568     565   563.5     565     568     568     565   563.5     565     568
     568     565   563.5     565     568     568     565   563.5     565     568
     568     565   563.5     565     568     568     566     561     556     561
     566     566     561     556     561     566     567     566     563     565
     568     568     565   563.5     565     568     568     565   563.5     565
     568     568     565   563.5     565     568     568     565   563.5     565
     568     568     565   563.5     565     568
       0       0  39.404  48.064  64.519  81.839  98.294 106.954 115.614 132.069
 149.389 165.844 174.504 183.164 199.619 216.939 233.394 242.054 250.714 267.169
 284.489 300.944 309.604 318.264 334.719 352.039 368.494 377.154 385.814 402.269
 419.589 436.044 444.704 453.364 469.819 487.139 503.594 512.254 520.914 537.369
 554.689 571.144 579.804 588.464 604.919 622.239 638.694 647.354 656.014 672.469
 689.789 706.244 714.904 723.564 740.019 757.339 773.794 782.454 791.114 807.569
 824.889 841.344 850.004 858.664 869.056 888.109 907.162 929.678 942.669 957.391
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Pier Skew, UpSta & Num, DnSta & Num=  ,25.981, 2 ,25.981, 2 , 0 , 0 , 0 ,,
      30      30
     500     575
      30      30
     500     575
Pier Skew, UpSta & Num, DnSta & Num=  ,106.954, 2 ,106.954, 2 , 0 , 0 , 0 ,,
       4       4
     500   563.5
       4       4
     500   563.5
Pier Skew, UpSta & Num, DnSta & Num=  ,165.844, 2 ,165.844, 2 , 0 , 0 , 0 ,,
       4       4
     500   563.5
       4       4
     500   563.5
Pier Skew, UpSta & Num, DnSta & Num=  ,174.504, 2 ,174.504, 2 , 0 , 0 , 0 ,,
       4       4
     500   563.5
       4       4
     500   563.5
Pier Skew, UpSta & Num, DnSta & Num=  ,242.054, 2 ,242.054, 2 , 0 , 0 , 0 ,,
       4       4
     500   563.5
       4       4
     500   563.5
Pier Skew, UpSta & Num, DnSta & Num=  ,309.604, 2 ,309.604, 2 , 0 , 0 , 0 ,,
       4       4
     500   563.5
       4       4
     500   563.5
Pier Skew, UpSta & Num, DnSta & Num=  ,377.154, 2 ,377.154, 2 , 0 , 0 , 0 ,,
       4       4
     500   563.5
       4       4
     500   563.5
Pier Skew, UpSta & Num, DnSta & Num=  ,444.704, 2 ,444.704, 2 , 0 , 0 , 0 ,,
       4       4
     500   563.5
       4       4
     500   563.5
Pier Skew, UpSta & Num, DnSta & Num=  ,512.254, 2 ,512.254, 2 , 0 , 0 , 0 ,,
       4       4
     500   563.5
       4       4
     500   563.5
Pier Skew, UpSta & Num, DnSta & Num=  ,579.804, 2 ,579.804, 2 , 0 , 0 , 0 ,,
       4       4
     500   563.5
       4       4
     500   563.5
Pier Skew, UpSta & Num, DnSta & Num=  ,647.354, 2 ,647.354, 2 , 0 , 0 , 0 ,,
       4       4
     500   563.5
       4       4
     500   563.5
Pier Skew, UpSta & Num, DnSta & Num=  ,714.904, 2 ,714.904, 2 , 0 , 0 , 0 ,,
       4       4
     500   563.5
       4       4
     500   563.5
Pier Skew, UpSta & Num, DnSta & Num=  ,782.454, 2 ,782.454, 2 , 0 , 0 , 0 ,,
       4       4
     500   563.5
       4       4
     500   563.5
Pier Skew, UpSta & Num, DnSta & Num=  ,791.114, 2 ,791.114, 2 , 0 , 0 , 0 ,,
       4       4
     500   563.5
       4       4
     500   563.5
Pier Skew, UpSta & Num, DnSta & Num=  ,850.004, 2 ,850.004, 2 , 0 , 0 , 0 ,,
     4.5     4.5
     500   563.5
     4.5     4.5
     500   563.5
Pier Skew, UpSta & Num, DnSta & Num=  ,942.669, 2 ,942.669, 2 , 0 , 0 , 0 ,,
     4.5     4.5
     500     556
     4.5     4.5
     500     556
Pier Skew, UpSta & Num, DnSta & Num=  ,1054.386, 2 ,1054.386, 2 , 0 , 0 , 0 ,,
     4.5     4.5
     500     556
     4.5     4.5
     500     556
Pier Skew, UpSta & Num, DnSta & Num=  ,1134.06, 2 ,1134.06, 2 , 0 , 0 , 0 ,,
     4.5     4.5
     500     563
     4.5     4.5
     500     563
Pier Skew, UpSta & Num, DnSta & Num=  ,1201.61, 2 ,1201.61, 2 , 0 , 0 , 0 ,,
       4       4
     500   563.5
       4       4
     500   563.5
Pier Skew, UpSta & Num, DnSta & Num=  ,1269.16, 2 ,1269.16, 2 , 0 , 0 , 0 ,,
       4       4
     500   563.5
       4       4
     500   563.5
Pier Skew, UpSta & Num, DnSta & Num=  ,1336.71, 2 ,1336.71, 2 , 0 , 0 , 0 ,,
       4       4
     500   563.5
       4       4
     500   563.5
Pier Skew, UpSta & Num, DnSta & Num=  ,1404.26, 2 ,1404.26, 2 , 0 , 0 , 0 ,,
       4       4
     500   563.5
       4       4
     500   563.5
Pier Skew, UpSta & Num, DnSta & Num=  ,1471.81, 2 ,1471.81, 2 , 0 , 0 , 0 ,,
       4       4
     500   563.5
       4       4
     500   563.5
BR Coef=-1 , 0 , 0 ,, 0 ,,,0.8,-1,,0,
WSPro=,,,, 1 ,,,, 0 ,,,, 0 ,,,,-1 ,-1 ,-1 , 0 , 0 , 0 , 0 , 0
BC Design=,, 0 ,, 0 ,,,,,,
BC Use User HTab Curves=0
BC User HTab FreeFlow(D)= 0

Type RM Length L Ch R = 1 ,6064    ,163,163,85
BEGIN DESCRIPTION:
This cross section corresponds to cross section 6085.75 of the non-georeferenced CDC model which was the source of this model.
Downstream of Lancaster Avenue.
Effective flow limit in LOB set at Clear Fork Levee Loop.
Effective flow limit in ROB set at Water Works Levee.
Trinity Park in LOB.
END DESCRIPTION:
XS GIS Cut Line= 3
2321341.486396536956859.47269657      2321998.37      6956655.74
2322795.074754736956613.74479211
#Sta/Elev= 30
       0  554.02  15.095     552  53.217  538.56 167.706  542.67 231.229  538.02
 458.829  541.18 590.664  539.62 688.984  538.12 747.111  540.48 886.983  536.16
 897.765  533.31 902.173  522.59 924.924     522 939.741   516.4 954.473     515
1032.224  517.571040.841     5201046.176  526.271063.488  529.131219.511     532
1226.612  534.921263.782     5341271.057  537.721283.432     5321298.666  529.36
1315.214  533.041356.229  536.081416.488  533.841464.103  546.591485.563  554.81
#Mann= 4 ,-1,0
       0     .15       0 590.664     .06       0 886.983    .035       0
1063.488     .06       0
#XS Ineff= 2 , 0
       0 733.619     5401271.057       0  537.72
Permanent Ineff=
       F       F
Bank Sta=886.983,1063.488
XS Rating Curve= 0 ,0
Skew Angle= 30
Exp/Cntr=0.5,0.3

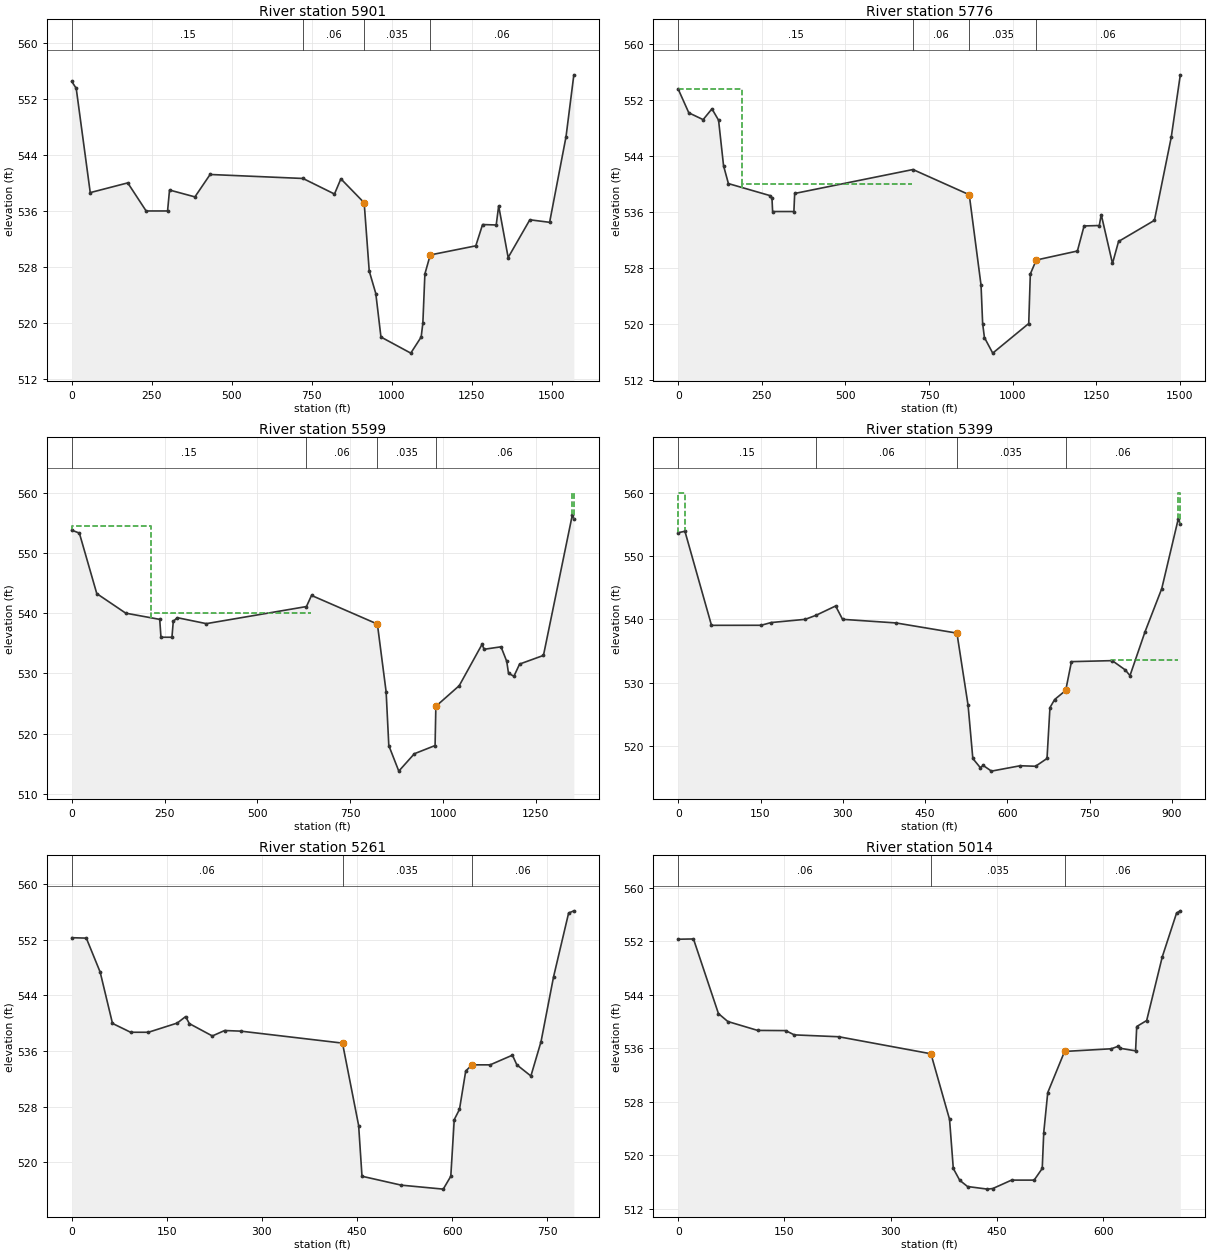
Type RM Length L Ch R = 1 ,5901    ,126,126,73
BEGIN DESCRIPTION:
This cross section corresponds to cross section 5925.721 of the non-georeferenced CDC model which was the source of this model.
Effective flow limit in LOB set at Clear Fork Levee Loop.
Effective flow limit in ROB set at Water Works Levee.
Trinity Park in LOB.
END DESCRIPTION:
XS GIS Cut Line= 3
 2321376.8412065 6957034.6485175 2322230.9654203 6956830.7609785
 2322889.2044946 6956619.8645824
#Sta/Elev= 30
       0  554.49    13.9  553.51   57.72  538.62  174.97  540.01  232.44     536
  299.45     536  305.55  538.99  384.93  538.01   432.4  541.21  722.83  540.64
  821.15  538.42  841.14  540.59  913.94  537.17  929.76  527.42   950.3  524.21
  966.39     518 1059.62   515.7 1092.11     518 1097.41     520 1103.74  527.01
 1120.46  529.72 1262.83  531.02 1284.05  534.06 1326.65     534 1334.34  536.73
    1364  529.35 1431.76  534.74 1493.59  534.38 1544.84  546.59 1569.32  555.44
#Mann= 4 ,-1,0
       0     .15       0  722.83     .06       0  913.94    .035       0
 1120.46     .06       0
#XS Ineff= 2 , 0
       0  746.78     540 1334.34       0  536.73
Permanent Ineff=
       F       F
Bank Sta=913.94,1120.46
XS Rating Curve= 0 ,0
Exp/Cntr=0.3,0.1

Type RM Length L Ch R = 1 ,5776    ,177,177,175
BEGIN DESCRIPTION:
This cross section corresponds to cross section 5799.004 of the non-georeferenced CDC model which was the source of this model.
Effective flow limit in LOB set at Clear Fork Levee Loop.
Effective flow limit in ROB set at Water Works Levee.
Trinity Park in LOB.
END DESCRIPTION:
XS GIS Cut Line= 2
 2321590.6550968 6957380.6170539  2322893.797166 6956634.3733636
#Sta/Elev= 30
       0  553.48   31.65   550.1   74.46  549.13  100.85  550.67  120.63  549.05
  135.55  542.54  150.07  539.99  274.13  538.28  280.34  537.95  282.26     536
  345.94     536  348.29  538.58  702.04     542  870.41   538.4  905.67  525.48
  910.47     520  915.78     518  940.65  515.77 1048.31     520 1053.08  527.08
 1070.87  529.07 1193.89  530.36 1213.87  533.94 1259.36     534  1265.2  535.56
 1298.82  528.58 1316.94  531.72 1424.27  534.74 1474.51   546.6 1501.69  555.53
#Mann= 4 ,-1,0
       0     .15       0  702.04     .06       0  870.41    .035       0
 1070.87     .06       0
#XS Ineff= 3 ,-1
       0  192.09 553.484  192.09     700     540  1265.2 1501.69  535.56
Permanent Ineff=
       F       F       F
Bank Sta=870.41,1070.87
XS Rating Curve= 0 ,0
Exp/Cntr=0.3,0.1

Type RM Length L Ch R = 1 ,5599    ,200,200,194
BEGIN DESCRIPTION:
This cross section corresponds to cross section 5622.383 of the non-georeferenced CDC model which was the source of this model.
Effective flow limit in LOB set at Clear Fork Levee Loop.
Effective flow limit in ROB set at Water Works Levee.
Trinity Park in LOB.
END DESCRIPTION:
XS GIS Cut Line= 2
 2321750.1053289 6957496.7937358 2322920.6177599 6956819.5685864
#Sta/Elev= 30
       0  553.79   20.44  553.31   67.37  543.25  145.41     540   236.9  538.97
  240.23     536  269.81     536  273.42  538.65  284.24  539.25  362.42  538.26
  632.07   541.1  645.75  542.95  823.17  538.19  846.72  526.92  853.92     518
  880.84  513.75  922.71  516.64  978.56     518  980.66  524.52  1043.6  527.95
 1105.13  534.83 1110.61     534 1156.19  534.41 1171.54     532 1176.34     530
 1190.98  529.52 1206.19  531.54 1270.46  532.98 1348.18  556.31 1352.31  555.65
#Mann= 4 ,-1,0
       0     .15       0  632.07     .06       0  823.17    .035       0
  980.66     .06       0
#XS Ineff= 3 ,-1
  1348.3 1352.31     560       0  213.87 554.416  213.87     645     540
Permanent Ineff=
       T       F       F
Bank Sta=823.17,980.66
XS Rating Curve= 0 ,0
Exp/Cntr=0.3,0.1

Type RM Length L Ch R = 1 ,5399    ,138,138,136
BEGIN DESCRIPTION:
This cross section corresponds to cross section 5422.282 of the non-georeferenced CDC model which was the source of this model.
Effective flow limit in LOB set at Clear Fork Levee Loop.
Effective flow limit in ROB set at Water Works Levee.
Trinity Park in LOB.
END DESCRIPTION:
XS GIS Cut Line= 3
 2322144.7631559 6957512.8196658  2322927.405844 6957038.5498316
 2322927.7067329 6957038.3689871
#Sta/Elev= 30
       0   553.7   12.21  553.92   60.63  539.05   151.2  539.06  169.37  539.49
  231.61     540   251.3  540.64  286.97  542.11  299.61     540  396.94  539.43
  508.17  537.82  528.54  526.38  537.15     518  550.76  516.55  556.03   516.9
  571.13     516  623.47  516.85  651.55  516.77  672.43     518  677.78  526.04
  686.33  527.32  706.49  528.76     717  533.31  791.31  533.47  815.15     532
  823.71   531.1  851.01     538  881.63  544.85  911.78  555.89  915.48  555.01
#Mann= 4 ,-1,0
       0     .15       0   251.3     .06       0  508.17    .035       0
  706.49     .06       0
#XS Ineff= 3 ,-1
       0   12.21     560  911.78  915.48     560  789.03  911.78   533.5
Permanent Ineff=
       T       T       F
Bank Sta=508.17,706.49
XS Rating Curve= 0 ,0
Exp/Cntr=0.3,0.1

Type RM Length L Ch R = 1 ,5261    ,247,247,258
BEGIN DESCRIPTION:
This cross section corresponds to cross section 5284.416 of the non-georeferenced CDC model which was the source of this model.
Effective flow limit in LOB set at Clear Fork Levee Loop.
Effective flow limit in ROB set at Water Works Levee.
END DESCRIPTION:
XS GIS Cut Line= 3
 2322290.5398619 6957591.4411122 2322946.0849372 6957185.2342601
 2322963.8432145 6957174.1857658
#Sta/Elev= 30
       0  552.26   22.96   552.2    44.8  547.32   64.24  539.95   92.85  538.68
  120.92  538.68  166.38     540  179.59  540.93  185.54  539.92  221.76  538.15
  241.19  538.93  266.71  538.84  427.13  537.12  452.59  525.28  457.87     518
  519.92  516.72  586.06  516.15  597.98     518   603.4  526.13  611.69  527.61
  621.54  533.12  631.52     534  660.04     534  695.22  535.39  702.18     534
  724.36   532.4  740.33  537.33  760.12  546.65  783.85   555.8  792.11  556.12
#Mann= 3 ,-1,0
       0     .06       0  427.13    .035       0  631.52     .06       0
Bank Sta=427.13,631.52
XS Rating Curve= 0 ,0
Exp/Cntr=0.3,0.1

Type RM Length L Ch R = 1 ,5014    ,115,115,132
BEGIN DESCRIPTION:
This cross section corresponds to cross section 5037.092 of the non-georeferenced CDC model which was the source of this model.
Effective flow limit in LOB set at Clear Fork Levee Loop.
Effective flow limit in ROB set at Water Works Levee.
END DESCRIPTION:
XS GIS Cut Line= 2
 2322493.5415873 6957740.0248612  2323107.149676 6957384.7496414
#Sta/Elev= 30
       0  552.32   21.53  552.36   56.76  541.19   70.05     540  112.09  538.67
   151.7  538.64  163.87     538  226.76  537.72  356.86  535.17  383.14  525.36
  388.45     518  397.57  516.23  408.55   515.3  436.72  514.91  444.25     515
  470.74  516.26  502.61  516.26  514.04     518  516.19  523.38  521.82  529.36
  545.61  535.52  611.57  535.92  621.11  536.29  623.91     536  645.87  535.61
  647.48  539.25  661.53  540.15  683.59  549.69  703.79  556.25  709.04  556.57
#Mann= 3 ,-1,0
       0     .06       0  356.86    .035       0  545.61     .06       0
Bank Sta=356.86,545.61
XS Rating Curve= 0 ,0
Exp/Cntr=0.3,0.1

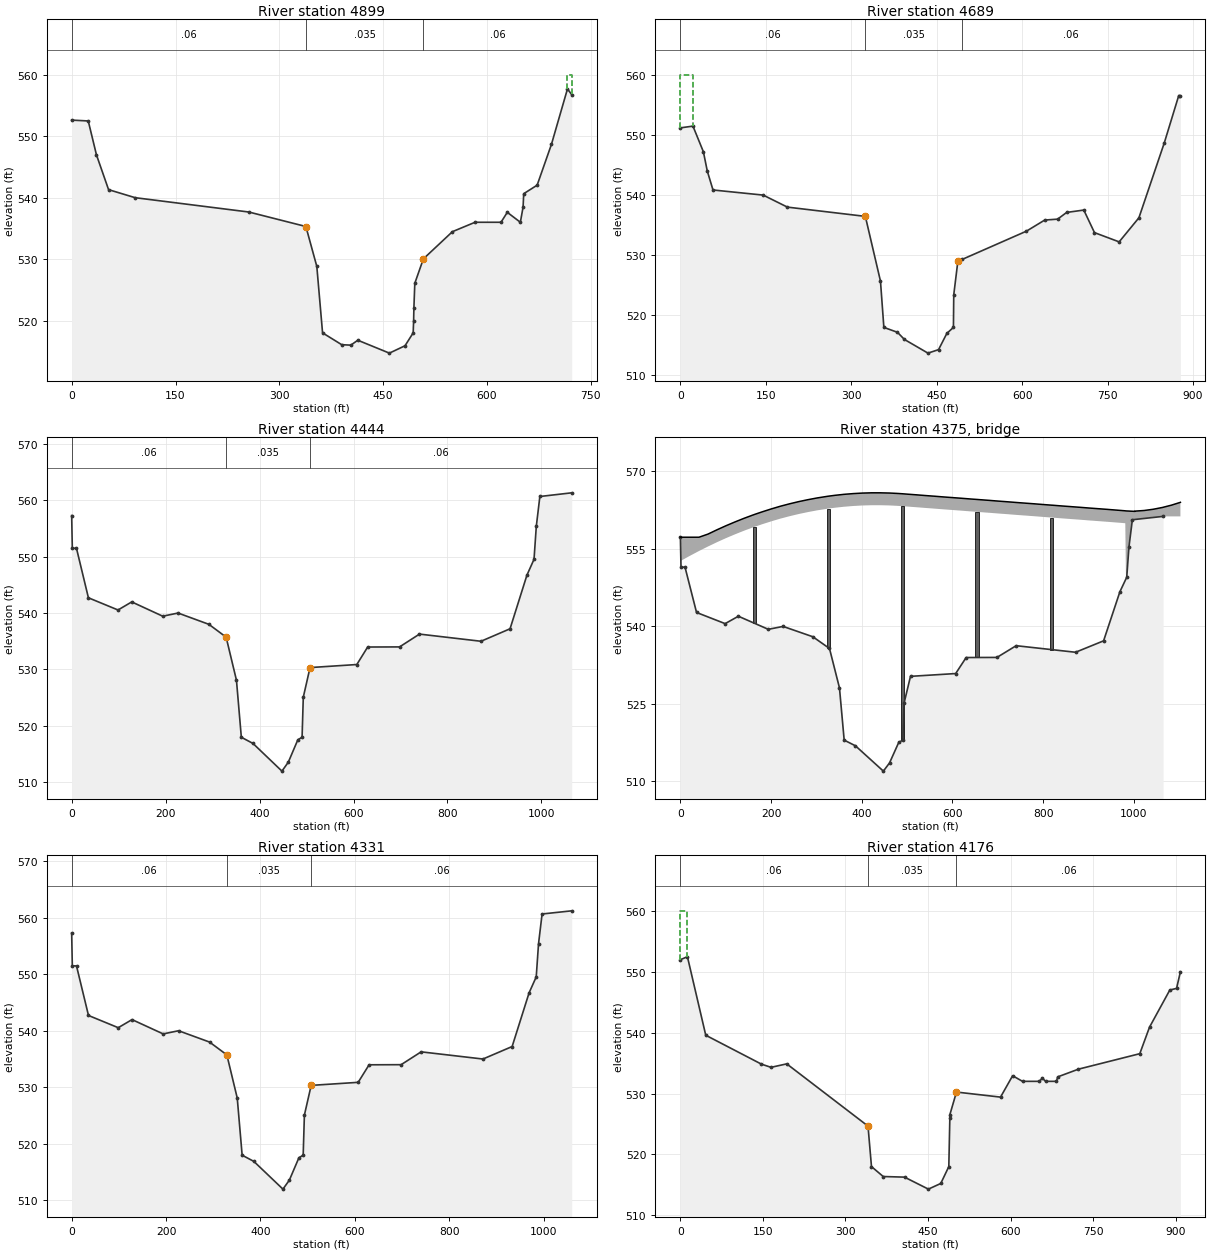
Type RM Length L Ch R = 1 ,4899    ,210,210,315
BEGIN DESCRIPTION:
This cross section corresponds to cross section 4920.554 of the non-georeferenced CDC model which was the source of this model.
Effective flow limit in LOB set at Clear Fork Levee Loop.
Effective flow limit in ROB set at Water Works Levee.
END DESCRIPTION:
XS GIS Cut Line= 2
  2322560.430701 6957813.7147635 2323200.9359994 6957479.8348039
#Sta/Elev= 30
       0  552.63   23.95  552.49   35.82  546.97    53.3  541.31   91.76     540
  255.87  537.67  338.33  535.31  354.12  528.81  362.42     518  390.12  516.07
  403.25     516  413.34   516.8  458.96   514.7  481.52   515.9  493.32     518
  493.97     520  494.34     522  495.67  526.07  508.03  530.04     550  534.47
  582.69     536  620.19     536  629.26  537.62  648.14     536  652.08  538.48
  652.99  540.65  672.38  542.04  692.98  548.66   716.2  557.71   722.3  556.77
#Mann= 3 ,-1,0
       0     .06       0  338.33    .035       0  508.03     .06       0
#XS Ineff= 2 , 0
       0                   716.2       0     560
Permanent Ineff=
       F       T
Bank Sta=338.33,508.03
XS Rating Curve= 0 ,0
Exp/Cntr=0.3,0.1

Type RM Length L Ch R = 1 ,4689    ,245,245,348
BEGIN DESCRIPTION:
This cross section corresponds to cross section 4701.715 of the non-georeferenced CDC model which was the source of this model.
Effective flow limit in LOB set at Clear Fork Levee Loop.
Effective flow limit in ROB set at Water Works Levee.
END DESCRIPTION:
XS GIS Cut Line= 2
 2322622.6520831 6957914.0298958 2323475.5548515 6957705.5044419
#Sta/Elev= 30
       0  551.18   22.08  551.47   40.41   547.2   47.24     544   57.27  540.85
   145.4     540  187.92     538  324.78  536.46  351.35  525.69   357.3     518
  381.23  517.18  393.31     516  434.74  513.72  453.33   514.3  467.88     517
  479.46     518  480.01  523.41  487.24     529  494.68   529.3   607.6     534
  639.76  535.85  662.36     536  678.31  537.12   708.4  537.51  727.12  533.76
  770.43  532.22  805.17  536.23   849.8  548.71  875.12  556.56  878.02  556.49
#Mann= 3 ,-1,0
       0     .06       0  324.78    .035       0  494.68     .06       0
#XS Ineff= 2 , 0
       0   22.08     560               0
Permanent Ineff=
       T       F
Bank Sta=324.78,487.24
XS Rating Curve= 0 ,0
Exp/Cntr=0.5,0.3

Type RM Length L Ch R = 1 ,4444    ,113,113,110
BEGIN DESCRIPTION:
This cross section corresponds to cross section 4460.321 of the non-georeferenced CDC model which was the source of this model.
Upstream of 7th Street.
Copy of cross-section 4346.114
Effective flow limit in LOB set at Clear Fork Levee Loop.
END DESCRIPTION:
XS GIS Cut Line= 3
  2322663.331196 6958043.8410829 2323534.6548541 6958046.8198355
 2323727.7237333 6958047.4798708
#Sta/Elev= 30
       0  557.26    1.36  551.49   10.28  551.45   35.63   542.7   98.66  540.54
  127.89  541.97  193.86  539.44  226.48     540   292.1     538  328.78  535.73
  350.79   528.1  361.16     518  386.01   516.9  447.58     512  461.19  513.59
  481.45  517.55  490.48     518  493.05  525.09   507.4  530.34  606.99  530.88
  630.09  533.98  697.99     534  740.38  536.27  871.33     535  933.16  537.21
  969.12  546.71  984.21  549.52  989.06  555.36  996.63  560.64  1064.4  561.29
#Mann= 3 ,-1,0
       0     .06       0  328.78    .035       0   507.4     .06       0
Bank Sta=328.78,507.4
XS Rating Curve= 0 ,0
Exp/Cntr=0.5,0.3

Type RM Length L Ch R = 3 ,4375    ,,,
BEGIN DESCRIPTION:
7th Street
Data from bridge plans and hydraulic report 2010.
------------------------------
CDC FW062310-01
------------------------------
END DESCRIPTION:
Node Name=7th Street
Bridge Culvert--1,0,-1,-1, 0
Deck Dist Width WeirC Skew NumUp NumDn MinLoCord MaxHiCord MaxSubmerge Is_Ogee
19.05,88,2.6,0, 65, 65, , , 0.98, 0, 0,0,,
       0       1      21      41      61      81     101     121     141     161
   163.5     181     201     221     241     261     281     301     321     327
     341     361     381     401     421     441     461     481     491     501
     521     541     561     581     601     621     641     654     661     681
     701     721     741     761     781     801   817.5     821     841     861
     881     901     921     941     961     981     981  982.55 1002.55 1002.55
 1022.55 1042.55 1062.55 1082.55 1102.55
  557.26  557.26  557.26  557.26  557.87  558.71   559.5  560.24  560.94  561.59
  561.67  562.19  562.75  563.27  563.73  564.15  564.52  564.85  565.13  565.21
  565.37  565.56   565.7   565.8  565.85  565.85  565.81  565.72  565.66  565.59
  565.46  565.32  565.19  565.05  564.92  564.79  564.65  564.57  564.52  564.39
  564.25  564.12  563.98  563.85  563.72  563.58  563.47  563.45  563.31  563.18
  563.05  562.91  562.78  562.65  562.51  562.37  562.37  562.35  562.26  562.31
  562.43  562.67  563.01  563.46  564.01
  552.65  552.69  553.66  554.59  555.47  556.31   557.1  557.84  558.54  559.19
  559.27  559.79  560.35  560.87  561.33  561.75  562.12  562.45  562.73  562.81
  562.97  563.16   563.3   563.4  563.45  563.45  563.41  563.32  563.26  563.19
  563.06  562.92  562.79  562.65  562.52  562.39  562.25  562.17  562.12  561.99
  561.85  561.72  561.58  561.45  561.32  561.18  561.07  561.05  560.91  560.78
  560.65  560.51  560.38  560.25  560.11  559.97
       0       1      21      41      61      81     101     121     141     161
   163.5     181     201     221     241     261     281     301     321     327
     341     361     381     401     421     441     461     481     491     501
     521     541     561     581     601     621     641     654     661     681
     701     721     741     761     781     801   817.5     821     841     861
     881     901     921     941     961     981     981  982.55 1002.55 1002.55
 1022.55 1042.55 1062.55 1082.55 1102.55
  557.26  557.26  557.26  557.26  557.87  558.71   559.5  560.24  560.94  561.59
  561.67  562.19  562.75  563.27  563.73  564.15  564.52  564.85  565.13  565.21
  565.37  565.56   565.7   565.8  565.85  565.85  565.81  565.72  565.66  565.59
  565.46  565.32  565.19  565.05  564.92  564.79  564.65  564.57  564.52  564.39
  564.25  564.12  563.98  563.85  563.72  563.58  563.47  563.45  563.31  563.18
  563.05  562.91  562.78  562.65  562.51  562.37  562.37  562.35  562.26  562.31
  562.43  562.67  563.01  563.46  564.01
  552.65  552.69  553.66  554.59  555.47  556.31   557.1  557.84  558.54  559.19
  559.27  559.79  560.35  560.87  561.33  561.75  562.12  562.45  562.73  562.81
  562.97  563.16   563.3   563.4  563.45  563.45  563.41  563.32  563.26  563.19
  563.06  562.92  562.79  562.65  562.52  562.39  562.25  562.17  562.12  561.99
  561.85  561.72  561.58  561.45  561.32  561.18  561.07  561.05  560.91  560.78
  560.65  560.51  560.38  560.25  560.11  559.97
Pier Skew, UpSta & Num, DnSta & Num=  ,163.5, 2 ,163.5, 2 , 0 , 0 , 0 ,,
       7       7
     510     565
       7       7
     510     565
Pier Skew, UpSta & Num, DnSta & Num=  ,327, 2 ,327, 2 , 0 , 0 , 0 ,,
       7       7
     510     565
       7       7
     510     565
Pier Skew, UpSta & Num, DnSta & Num=  ,490.5, 2 ,490.5, 2 , 0 , 0 , 0 ,,
       7       7
     510     565
       7       7
     510     565
Pier Skew, UpSta & Num, DnSta & Num=  ,654, 2 ,654, 2 , 0 , 0 , 0 ,,
       7       7
     510     565
       7       7
     510     565
Pier Skew, UpSta & Num, DnSta & Num=  ,817.5, 2 ,817.5, 2 , 0 , 0 , 0 ,,
       7       7
  535.27     565
       7       7
  535.27     565
BR Coef=-1 , 0 , 0 ,, 0 ,,,0.8,-1,,0,
WSPro=,,,, 1 ,,,, 0 ,,,, 0 ,,,,-1 ,-1 ,-1 , 0 , 0 , 0 , 0 , 0
BC Design=,, 0 ,, 0 ,,,,,,
BC Use User HTab Curves=0
BC User HTab FreeFlow(D)= 0

Type RM Length L Ch R = 1 ,4331    ,155,155,116
BEGIN DESCRIPTION:
This cross section corresponds to cross section 4346.114 of the non-georeferenced CDC model which was the source of this model.
Downstream of 7th Street.
Effective flow limit in LOB set at Clear Fork Levee Loop.
END DESCRIPTION:
XS GIS Cut Line= 2
 2322696.0002607 6958155.65520022323755.35167257 6958155.6552002
#Sta/Elev= 30
       0  557.26    1.36  551.49   10.28  551.45   35.63   542.7   98.66  540.54
  127.89  541.97  193.86  539.44  226.48     540   292.1     538  328.78  535.73
  350.79   528.1  361.16     518  386.01   516.9  447.58     512  461.19  513.59
  481.45  517.55  490.48     518  493.05  525.09   507.4  530.34  606.99  530.88
  630.09  533.98  697.99     534  740.38  536.27  871.33     535  933.16  537.21
  969.12  546.71  984.21  549.52  989.06  555.36  996.63  560.64 1059.35   561.2
#Mann= 3 ,-1,0
       0     .06       0  328.78    .035       0   507.4     .06       0
Bank Sta=328.78,507.4
XS Rating Curve= 0 ,0
Exp/Cntr=0.5,0.3

Type RM Length L Ch R = 1 ,4176    ,149,149,139
BEGIN DESCRIPTION:
This cross section corresponds to cross section 4191.802 of the non-georeferenced CDC model which was the source of this model.
Effective flow limit in LOB set at Clear Fork Levee Loop.
END DESCRIPTION:
XS GIS Cut Line= 3
 2322738.7456673 6958360.9657713 2323633.0028308 6958244.8343329
2323639.944541126958243.93285753
#Sta/Elev= 30
       0  551.97   12.78  552.47   46.11  539.57  147.41  534.82  164.77   534.3
  193.29  534.87  340.99  524.65   347.3     518  368.63  516.37  407.32  516.27
  450.73   514.3  473.23  515.23  487.85     518  489.74     526  489.78  526.53
  501.76  530.24  581.86  529.41  603.82  532.92  621.79     532  652.14     532
  657.97  532.52  663.75     532  683.56     532   685.7  532.73  723.49     534
  834.94  536.54  852.63   540.9  889.54     547  901.77  547.26  908.77     550
#Mann= 3 ,-1,0
       0     .06       0  340.99    .035       0  501.76     .06       0
#XS Ineff= 2 , 0
       0   12.78     560  901.77       0  908.77
Permanent Ineff=
       T       F
Bank Sta=340.99,501.76
XS Rating Curve= 0 ,0
Exp/Cntr=0.3,0.1