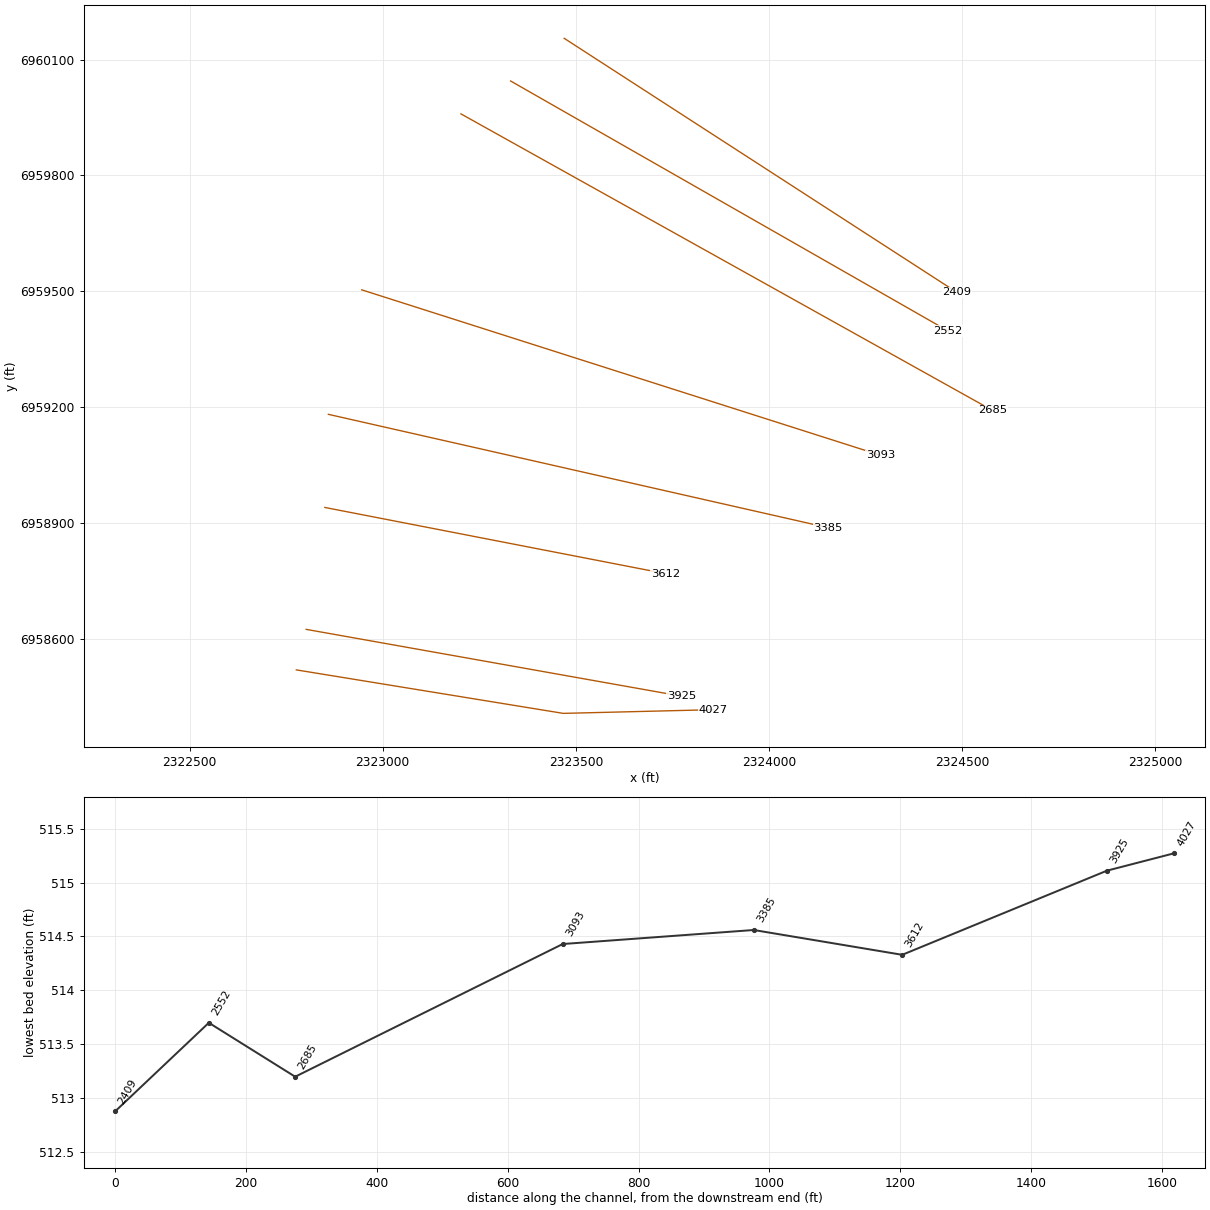
HEC-RAS study CDC_Consolidated_Model.prj: Upper Trinity CDC Consolidated Model

--- CDC_Consolidated_Model.g03 (geometry) --- (continued)

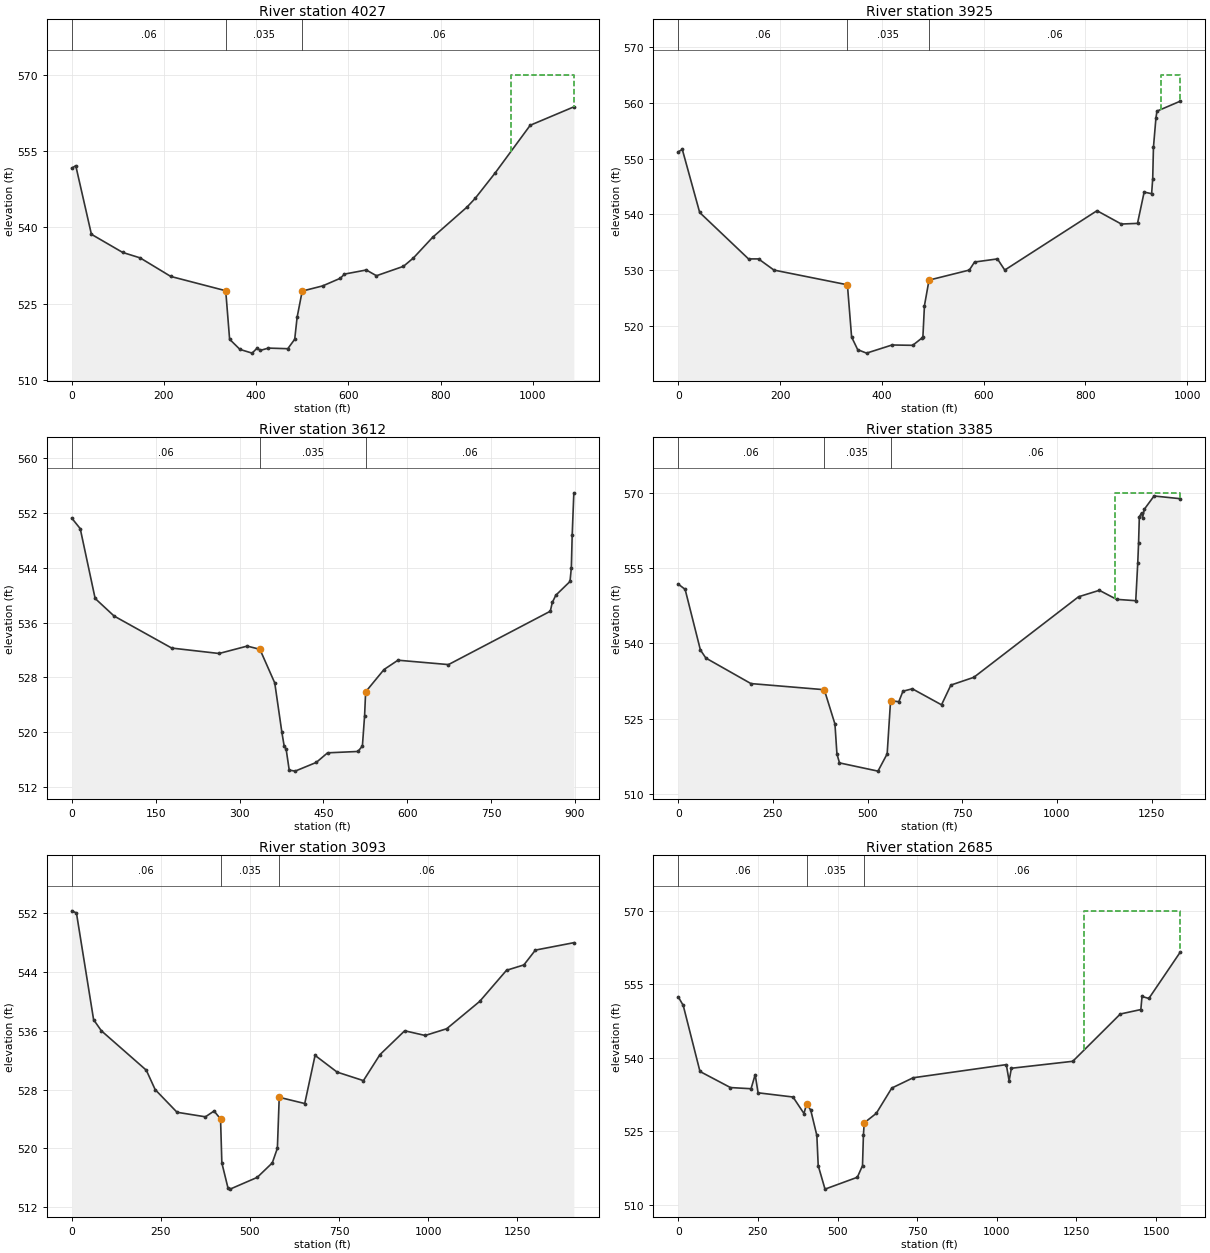
Type RM Length L Ch R = 1 ,4027    ,102,102,97
BEGIN DESCRIPTION:
This cross section corresponds to cross section 4042.460 of the non-georeferenced CDC model which was the source of this model.
Effective flow limit in LOB set at Clear Fork Levee Loop.
Pier 1 site in ROB - ineffective flow due to buildings.
END DESCRIPTION:
XS GIS Cut Line= 3
  2322776.288717 6958519.8445608 2323467.3844416 6958407.2679151
 2323855.9508569  6958416.822725
#Sta/Elev= 30
       0  551.64    8.66  552.13   42.59  538.64  110.42  535.07  148.27     534
  214.74  530.35  333.88  527.54  342.32     518  364.77     516  391.13  515.27
  402.38  516.29  408.51   515.8  426.61  516.26  468.48  516.14  483.52     518
  488.74  522.33  499.75  527.47  544.09  528.49  582.65     530   591.3  530.81
  638.76  531.62   660.8  530.49  719.37  532.34  741.13     534  782.49  538.03
  857.28     544  874.87   545.7   918.2   550.7  994.27  560.08 1088.89   563.7
#Mann= 3 ,-1,0
       0     .06       0  333.88    .035       0  499.75     .06       0
#XS Ineff= 2 , 0
       0                  951.74       0     570
Permanent Ineff=
       F       F
Bank Sta=333.88,499.75
XS Rating Curve= 0 ,0
Exp/Cntr=0.3,0.1

Type RM Length L Ch R = 1 ,3925    ,313,313,307
BEGIN DESCRIPTION:
This cross section corresponds to cross section 3940.902 of the non-georeferenced CDC model which was the source of this model.
Effective flow limit in LOB set at Clear Fork Levee Loop.
Pier 1 site in ROB - ineffective flow due to buildings.
END DESCRIPTION:
XS GIS Cut Line= 2
 2322801.9818527 6958624.7176216 2323773.1415975 6958451.8574167
#Sta/Elev= 30
       0   551.2    8.01  551.62   42.16  540.32   138.1     532  157.74     532
  188.02     530  332.37  527.36  340.61     518  352.59  515.73  369.95  515.11
  420.14  516.57  460.62  516.51  479.28  517.85  480.67     518  483.74  523.63
  492.73   528.2  571.88     530  582.18  531.44  627.12     532  641.53     530
  822.73  540.64   870.6  538.25  902.31  538.37  915.37  543.98  930.07  543.69
  932.21  546.41  933.64     552  938.54  557.27  940.54  558.49  986.42  560.28
#Mann= 3 ,-1,0
       0     .06       0  332.37    .035       0  492.73     .06       0
#XS Ineff= 2 , 0
       0                  947.61       0     565
Permanent Ineff=
       F       F
Bank Sta=332.37,492.73
XS Rating Curve= 0 ,0
Exp/Cntr=0.3,0.1

Type RM Length L Ch R = 1 ,3612    ,227,227,215
BEGIN DESCRIPTION:
This cross section corresponds to cross section 3628.557 of the non-georeferenced CDC model which was the source of this model.
Effective flow limit in LOB set at Clear Fork Levee Loop.
Pier 1 site in ROB.
END DESCRIPTION:
XS GIS Cut Line= 2
 2322850.1678902 6958940.3722196 2323731.5950794 6958769.1682646
#Sta/Elev= 30
       0  551.26   15.14  549.72   41.81  539.53   75.67  536.97  178.77  532.29
  263.41   531.5  313.72  532.58  336.47  532.11  363.02   527.2  375.75     520
  379.84     518  383.38  517.53  388.89  514.48  399.51  514.33  437.26   515.6
   457.5     517  511.74   517.2  519.77     518   523.7  522.44  525.55   525.9
   558.4  529.16  583.36  530.52   673.7  529.88  855.79  537.67  859.38  538.95
  865.62     540  891.04  542.01  893.41     544  894.94  548.78   897.9  554.95
#Mann= 3 ,-1,0
       0     .06       0  336.47    .035       0  525.55     .06       0
Bank Sta=336.47,525.55
XS Rating Curve= 0 ,0
Exp/Cntr=0.3,0.1

Type RM Length L Ch R = 1 ,3385    ,292,292,268
BEGIN DESCRIPTION:
This cross section corresponds to cross section 3405.202 of the non-georeferenced CDC model which was the source of this model.
Effective flow limit in LOB set at Clear Fork Levee Loop.
Pier 1 site in ROB - ineffective flow due to buildings.
END DESCRIPTION:
XS GIS Cut Line= 2
 2322859.3190085 6959181.4511015 2324152.1530734 6958888.1983998
#Sta/Elev= 30
       0  551.82    18.2  550.77    58.5   538.7   73.01  537.08  191.92     532
  385.61  530.78  413.79  523.94  419.01     518  425.76   516.2   527.4  514.56
  551.65     518  560.63  528.58  582.41  528.39  593.33  530.48  618.07  530.96
  695.19  527.77  719.86   531.7  780.57  533.25 1056.94  549.29 1111.89  550.58
 1157.47  548.78 1208.03  548.51 1213.29     556 1215.47     560 1217.49  565.23
 1223.21     566 1226.01  565.08 1230.93  566.76 1256.34  569.37 1325.68  568.83
#Mann= 3 ,-1,0
       0     .06       0  385.61    .035       0  560.63     .06       0
#XS Ineff= 2 , 0
       0                 1154.25       0     570
Permanent Ineff=
       F       F
Bank Sta=385.61,560.63
XS Rating Curve= 0 ,0
Exp/Cntr=0.3,0.1

Type RM Length L Ch R = 1 ,3093    ,409,409,342
BEGIN DESCRIPTION:
This cross section corresponds to cross section 3113.178 of the non-georeferenced CDC model which was the source of this model.
At Sump 23C outfall.
Upstream of old Clear Fork channel (right bank).
Effective flow limit in LOB set at Clear Fork Levee Loop.
Pier 1 site in ROB.
END DESCRIPTION:
XS GIS Cut Line= 3
 2322945.6707451 6959503.7454782 2324259.7275226 6959084.6958177
2324287.975946516959075.68746079
#Sta/Elev= 30
       0  552.34   13.11  552.05   61.27  537.51   83.05     536  209.16  530.63
     234  527.99  295.39   524.9  375.11  524.28  399.26  525.07  417.49  523.99
  421.16     518  438.55  514.55  444.23  514.43  520.42  516.03  562.67     518
  576.99     520  582.16  526.94  653.74  526.09  682.75  532.65  744.62  530.37
  818.41  529.21  864.82  532.75  934.25     536  991.77  535.36 1052.15  536.28
 1144.64     540 1219.93  544.24 1268.68  544.97 1300.98  546.99 1408.91     548
#Mann= 3 ,-1,0
       0     .06       0  417.49    .035       0  582.16     .06       0
#XS Ineff= 2 , 0
       0                 1362.92       0
Permanent Ineff=
       F       F
Bank Sta=417.49,582.16
XS Rating Curve= 0 ,0
Exp/Cntr=0.3,0.1

Type RM Length L Ch R = 1 ,2685    ,132,132,126
BEGIN DESCRIPTION:
This cross section corresponds to cross section 2689.521 of the non-georeferenced CDC model which was the source of this model.
Downstream of old Clear Fork channel (right bank).
Effective flow limit in LOB set at Clear Fork Levee Loop.
END DESCRIPTION:
XS GIS Cut Line= 3
 2323202.4162016 6959959.3206627 2323203.0318506 6959958.9855495
 2324578.9392467 6959191.4076583
#Sta/Elev= 30
       0  552.44   15.64   550.7   68.28  537.21  163.96  533.93  228.59  533.69
  241.54  536.56  250.67  532.86  360.36     532  394.74  528.63  403.09  530.63
  416.03  529.31  435.18  524.15  439.44     518  460.81   513.2   562.3  515.62
  578.52     518  581.31  524.15   583.9  526.73  621.71  528.66  670.44  533.83
  737.51  535.93 1029.92  538.61 1038.78  535.29 1045.89  537.87 1238.66  539.29
 1387.89  548.94 1452.32  549.85 1456.01  552.53 1477.43  552.11 1576.23  561.59
#Mann= 3 ,-1,0
       0     .06       0  403.09    .035       0   583.9     .06       0
#XS Ineff= 2 , 0
       0                    1274       0     570
Permanent Ineff=
       F       F
Bank Sta=403.09,583.9
XS Rating Curve= 0 ,0
Exp/Cntr=0.3,0.1

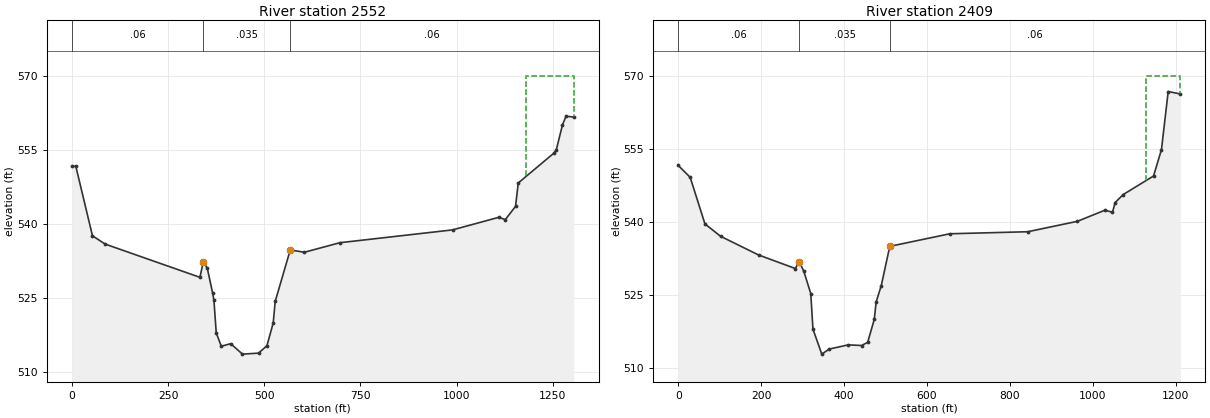
Type RM Length L Ch R = 1 ,2552    ,143,143,121
BEGIN DESCRIPTION:
This cross section corresponds to cross section 2556.313 of the non-georeferenced CDC model which was the source of this model.
Effective flow limit in LOB set at Clear Fork Levee Loop.
END DESCRIPTION:
XS GIS Cut Line= 2
 2323331.1515262 6960044.4123218 2324463.6028757 6959397.2973205
#Sta/Elev= 30
       0  551.68   10.39  551.74   53.75  537.64   86.76  535.96  332.85  529.24
  341.89  532.39  352.08  531.07  366.11     526  369.25  524.62  375.32     518
  388.39   515.3  412.97  515.81  443.41   513.7  485.09   513.9  507.03   515.4
  523.29     520  528.48  524.36  567.54  534.77  604.27  534.31  696.56  536.24
  989.08  538.83 1109.44  541.38 1126.18  540.91 1152.82  543.59 1159.95  548.33
 1251.45  554.29 1258.46  554.95 1274.65  560.04 1283.94  561.82  1304.3  561.66
#Mann= 3 ,-1,0
       0     .06       0  341.89    .035       0  567.54     .06       0
#XS Ineff= 2 , 0
       0                    1180       0     570
Permanent Ineff=
       F       F
Bank Sta=341.89,567.54
XS Rating Curve= 0 ,0
Exp/Cntr=0.3,0.1

Type RM Length L Ch R = 1 ,2409    ,216,216,213
BEGIN DESCRIPTION:
This cross section corresponds to cross section 2412.767 of the non-georeferenced CDC model which was the source of this model.
Effective flow limit in LOB set at Clear Fork Levee Loop.
END DESCRIPTION:
XS GIS Cut Line= 2
 2323469.8137206 6960154.8823564 2324486.5750478 6959497.1648142
#Sta/Elev= 30
       0  551.61   28.79  549.17   64.46   539.6  102.06  537.07  193.79  533.23
   282.4  530.45  291.78  531.89  302.82   529.9  319.67   525.3  324.95     518
  346.25  512.88  364.23  513.92  409.98  514.78  442.29  514.65  456.92   515.3
  472.81     520  477.35  523.59  489.64  526.93   510.2     535  654.99  537.58
  842.98     538  962.76  540.14 1029.15  542.42 1047.36     542  1053.9     544
 1073.33  545.64 1146.38  549.44 1165.49  554.85 1181.72  566.78 1210.95  566.28
#Mann= 3 ,-1,0
       0     .06       0  291.78    .035       0   510.2     .06       0
#XS Ineff= 2 , 0
       0                    1128       0     570
Permanent Ineff=
       F       F
Bank Sta=291.78,510.2
XS Rating Curve= 0 ,0
Exp/Cntr=0.3,0.1