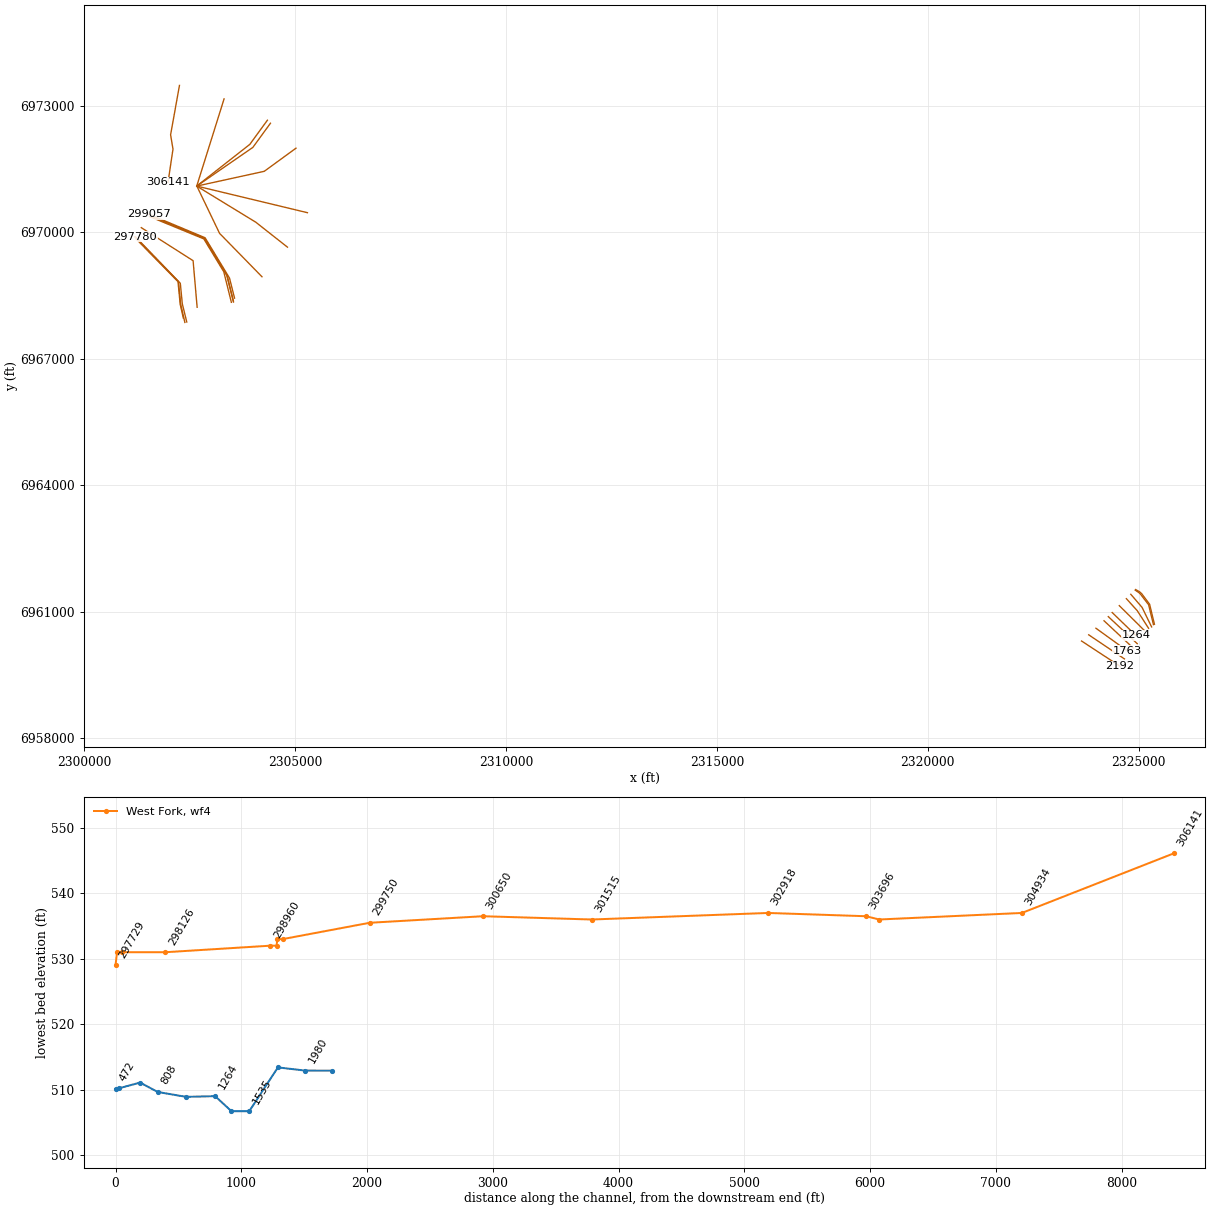
HEC-RAS study CDC_Consolidated_Model.prj: Upper Trinity CDC Consolidated Model

--- CDC_Consolidated_Model.g03 (geometry) --- (continued)

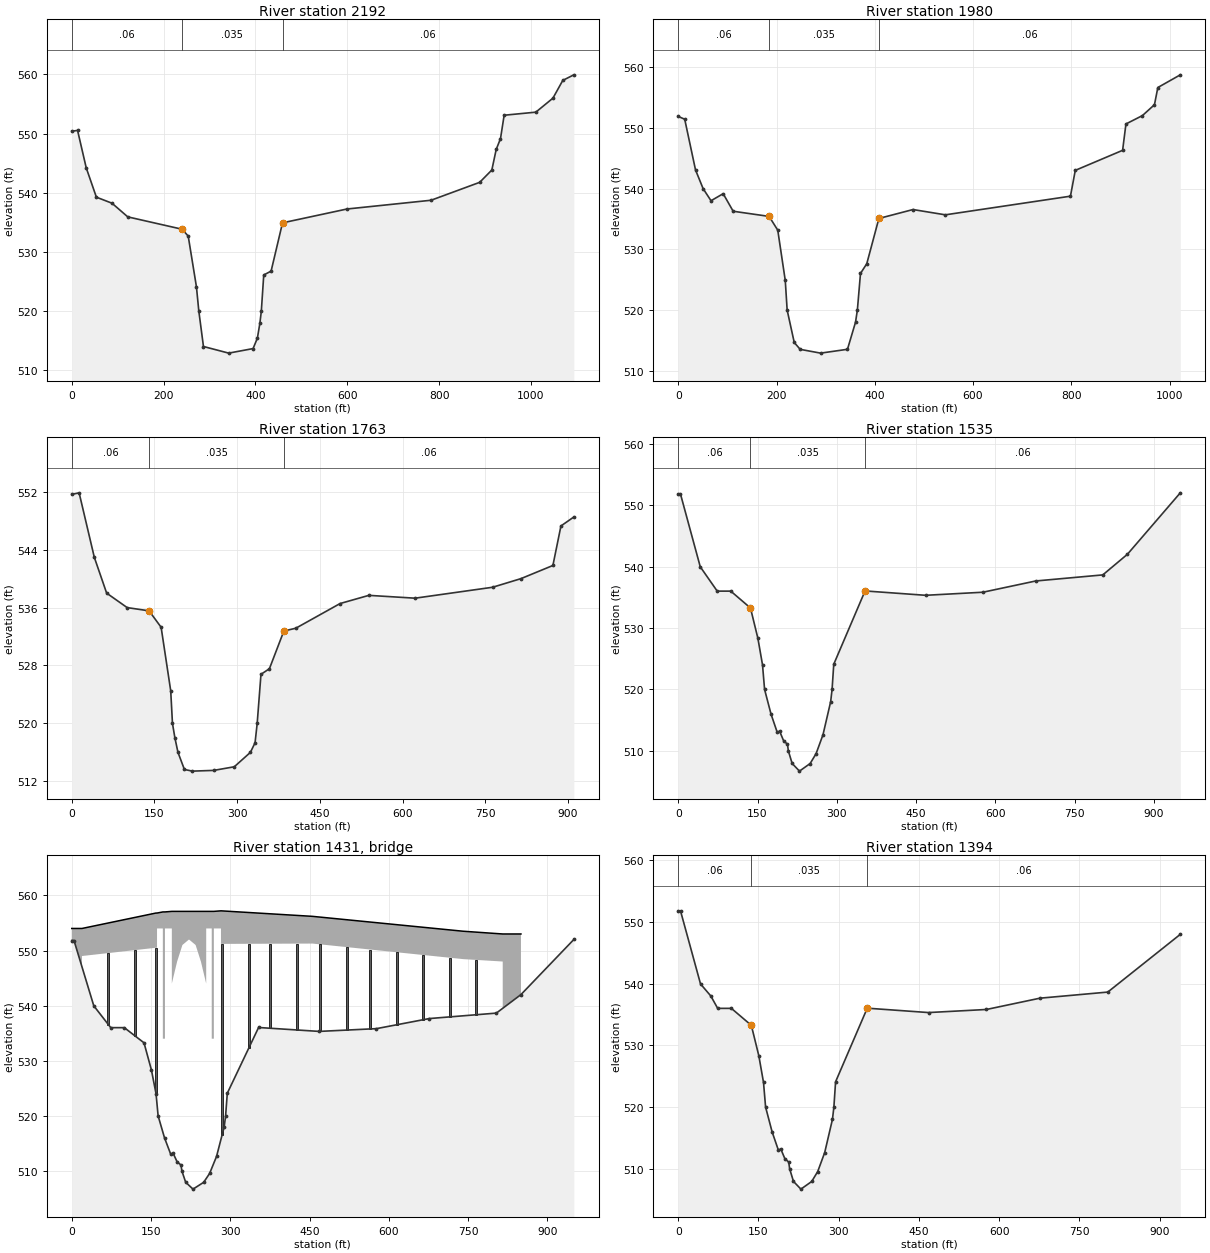
Type RM Length L Ch R = 1 ,2192    ,212,212,205
BEGIN DESCRIPTION:
This cross section corresponds to cross section 2196.683 of the non-georeferenced CDC model which was the source of this model.
Effective flow limit in LOB set at Clear Fork Levee Loop.
END DESCRIPTION:
XS GIS Cut Line= 2
 2323645.7441329 6960300.9694149 2324559.8293677 6959701.0029614
#Sta/Elev= 30
       0  550.41   12.63  550.54   31.48  544.22   53.59  539.26   87.57  538.24
  121.97  535.93  240.34  533.84   253.6  532.68   271.5  524.11  276.69     520
  286.77  514.02  341.81   512.9  394.83  513.67  404.19  515.42  409.76     518
   412.8     520  418.08  526.11   434.1  526.76  458.96  534.92  599.29  537.26
  782.45  538.74  888.39  541.77  914.79  543.85  924.31  547.33  933.66  549.16
  941.61  553.11 1010.61  553.63 1047.88     556 1069.32     559 1093.39  559.94
#Mann= 3 ,-1,0
       0     .06       0  240.34    .035       0  458.96     .06       0
Bank Sta=240.34,458.96
XS Rating Curve= 0 ,0
Exp/Cntr=0.3,0.1

Type RM Length L Ch R = 1 ,1980    ,217,217,205
BEGIN DESCRIPTION:
This cross section corresponds to cross section 1984.189 of the non-georeferenced CDC model which was the source of this model.
Effective flow limit in LOB set at Clear Fork Levee Loop.
END DESCRIPTION:
XS GIS Cut Line= 2
 2323814.9536134 6960447.9972534 2324661.7483765 6959876.1764197
#Sta/Elev= 30
       0  551.88   13.18  551.42   35.19  543.07   50.59     540   66.71     538
   91.45  539.16  111.78  536.27  184.95  535.42  202.55  533.15  217.82  524.87
  221.65     520   236.1  514.66  248.17  513.53  289.73  512.91  344.41  513.54
  360.79     518  364.56     520   370.9  526.03   383.7  527.63  408.33  535.08
  477.79  536.55  543.59  535.68  798.19  538.75  808.03     543  904.36   546.3
  911.13  550.64  944.67  552.02  969.18  553.81  976.04  556.64 1021.78  558.73
#Mann= 3 ,-1,0
       0     .06       0  184.95    .035       0  408.33     .06       0
Bank Sta=184.95,408.33
XS Rating Curve= 0 ,0
Exp/Cntr=0.3,0.1

Type RM Length L Ch R = 1 ,1763    ,228,228,192
BEGIN DESCRIPTION:
This cross section corresponds to cross section 1765.998 of the non-georeferenced CDC model which was the source of this model.
Effective flow limit in LOB set at Clear Fork Levee Loop.
END DESCRIPTION:
XS GIS Cut Line= 2
 2323986.9398017  6960603.297008 2324725.4478866 6960070.4596274
#Sta/Elev= 30
       0  551.64   13.33  551.86   40.92  542.94   63.25     538  100.45     536
  140.22  535.55  162.08  533.28  179.47   524.5  182.63     520  187.04     518
   192.6     516  204.28  513.63   218.7   513.4  257.34   513.5  294.74     514
  323.98  515.99  332.45  517.32  336.31     520  343.18  526.78  358.46  527.55
  384.68  532.76   406.4  533.15  486.67  536.56  538.86  537.69  622.75   537.3
  763.29  538.81  814.65     540  872.67  541.82  887.26  547.28  910.66  548.52
#Mann= 3 ,-1,0
       0     .06       0  140.22    .035       0  384.68     .06       0
#Block Obstruct= 2 , 0
       0                     909       0     570
Bank Sta=140.22,384.68
XS Rating Curve= 0 ,0
Exp/Cntr=0.5,0.3

Type RM Length L Ch R = 1 ,1535    ,141,141,141
BEGIN DESCRIPTION:
This cross section corresponds to cross section 1537.796 of the non-georeferenced CDC model which was the source of this model.
Upstream of Henderson Street.
Copy of cross-section 1396.969.
Effective flow limit in LOB set at Clear Fork Levee Loop.
END DESCRIPTION:
XS GIS Cut Line= 5
 2324178.5161762 6960780.9688422 2324794.8782862 6960204.5688195
 2324799.2459906  6960200.4842972324854.75545908 6960148.5738076
2324872.284764916960132.18102147
#Sta/Elev= 30
       0  551.81    4.26   551.8   41.67  539.96   73.76     536   99.39     536
  136.68  533.25  150.66  528.33  159.45     524  163.35     520  175.48     516
  187.01  513.08  191.91  513.18  199.36  511.64  206.64  511.08  208.31     510
  215.49  507.95  229.37   506.7   249.6  507.94  260.82  509.55  273.89  512.63
  288.35     518  291.06     520  294.23   524.1  353.44  536.03  468.02  535.32
  576.35  535.82  676.29  537.65  803.23  538.64   849.8     542  949.86     552
#Mann= 3 ,-1,0
       0     .06       0  136.68    .035       0  353.44     .06       0
#XS Ineff= 2 , 0
       0                  849.86       0
Permanent Ineff=
       F       F
Bank Sta=136.68,353.44
XS Rating Curve= 0 ,0
Exp/Cntr=0.5,0.3

Type RM Length L Ch R = 3 ,1431    ,,,
BEGIN DESCRIPTION:
Henderson Street
Bridge data from bridge plans, 1975 USACE survey.
END DESCRIPTION:
Node Name=Henderson Street
Bridge Culvert--1,0,-1,-1, 0
Deck Dist Width WeirC Skew NumUp NumDn MinLoCord MaxHiCord MaxSubmerge Is_Ogee
38.27,73,2.6,0, 30, 30, , , 0.95, 0, 0,0,,
       0    19.3    19.3   159.3   161.3   161.3   172.3   172.3   176.3   176.3
   189.3   189.3   199.3   209.3   221.8   234.3   244.3   254.3   254.3   264.8
   264.8   268.8   268.8   282.3   282.3   455.3   740.3   815.3   815.3   849.8
     554     554     554   556.8   556.8   556.8     557     557     557     557
   557.1   557.1   557.1   557.1   557.1   557.1   557.1   557.1   557.1   557.1
   557.1   557.1   557.1   557.2   557.2   556.2   553.5     553     553     553
     545     545     549   550.5   550.5     554     554     534     534     554
     554     544     548     551     552     551     548     544     554     554
     534     534     554     554   551.2  551.26  548.44     548     535     535
       0    19.3    19.3   159.3   161.3   161.3   172.3   172.3   176.3   176.3
   189.3   189.3   199.3   209.3   221.8   234.3   244.3   254.3   254.3   264.8
   264.8   268.8   268.8   282.3   282.3   455.3   740.3   815.3   815.3   849.8
     554     554     554   556.8   556.8   556.8     557     557     557     557
   557.1   557.1   557.1   557.1   557.1   557.1   557.1   557.1   557.1   557.1
   557.1   557.1   557.1   557.2   557.2   556.2   553.5     553     553     553
     545     545     549   550.5   550.5     554     554     534     534     554
     554     544     548     551     552     551     548     544     554     554
     534     534     554     554   551.2  551.26  548.44     548     535     535
Pier Skew, UpSta & Num, DnSta & Num=  ,69.3, 2 ,69.3, 2 , 0 , 0 , 0 ,,
       4       4
     500     553
       4       4
     500     553
Pier Skew, UpSta & Num, DnSta & Num=  ,119.3, 2 ,119.3, 2 , 0 , 0 , 0 ,,
       4       4
     500     553
       4       4
     500     553
Pier Skew, UpSta & Num, DnSta & Num=  ,159.3, 2 ,159.3, 2 , 0 , 0 , 0 ,,
       4       4
     500     553
       4       4
     500     553
Pier Skew, UpSta & Num, DnSta & Num=  ,284.3, 2 ,284.3, 2 , 0 , 0 , 0 ,,
       4       4
     500     554
       4       4
     500     554
Pier Skew, UpSta & Num, DnSta & Num=  ,335.3, 2 ,335.3, 2 , 0 , 0 , 0 ,,
       4       4
     500     553
       4       4
     500     553
Pier Skew, UpSta & Num, DnSta & Num=  ,375.3, 2 ,375.3, 2 , 0 , 0 , 0 ,,
       4       4
     500     553
       4       4
     500     553
Pier Skew, UpSta & Num, DnSta & Num=  ,425.3, 2 ,425.3, 2 , 0 , 0 , 0 ,,
       4       4
     500     553
       4       4
     500     553
Pier Skew, UpSta & Num, DnSta & Num=  ,470, 2 ,470, 2 , 0 , 0 , 0 ,,
       4       4
     500     553
       4       4
     500     553
Pier Skew, UpSta & Num, DnSta & Num=  ,520, 2 ,520, 2 , 0 , 0 , 0 ,,
       4       4
     500     553
       4       4
     500     553
Pier Skew, UpSta & Num, DnSta & Num=  ,565, 2 ,565, 2 , 0 , 0 , 0 ,,
       4       4
     500     553
       4       4
     500     553
Pier Skew, UpSta & Num, DnSta & Num=  ,615, 2 ,615, 2 , 0 , 0 , 0 ,,
       4       4
     500     553
       4       4
     500     553
Pier Skew, UpSta & Num, DnSta & Num=  ,665, 2 ,665, 2 , 0 , 0 , 0 ,,
       4       4
     500     553
       4       4
     500     553
Pier Skew, UpSta & Num, DnSta & Num=  ,715, 2 ,715, 2 , 0 , 0 , 0 ,,
       4       4
     500     553
       4       4
     500     553
Pier Skew, UpSta & Num, DnSta & Num=  ,765, 2 ,765, 2 , 0 , 0 , 0 ,,
       4       4
     500     553
       4       4
     500     553
BR Coef=-1 , 0 , 0 ,, 0 ,,,0.8,-1,,0,
WSPro=,,,, 1 ,,,, 0 ,,,, 0 ,,,,-1 ,-1 ,-1 , 0 , 0 , 0 , 0 , 0
BC Design=,, 0 ,, 0 ,,,,,,
BC Use User HTab Curves=0
BC User HTab FreeFlow(D)= 0

Type RM Length L Ch R = 1 ,1394    ,130,130,125
BEGIN DESCRIPTION:
This cross section corresponds to cross section 1396.939 of the non-georeferenced CDC model which was the source of this model.
Downstream of Henderson Street.
Effective flow limit in LOB set at Clear Fork Levee Loop.
---------------------------------------------------------------------
RADIO SHACK RIVERFRONT CAMPUS CDC FW080602-01 IN ROB.
---------------------------------------------------------------------
END DESCRIPTION:
XS GIS Cut Line= 3
  2324279.296189 6960879.3880246 2324900.1270368 6960299.0133131
2324965.142219146960238.23481308
#Sta/Elev= 30
       0  551.81    4.26   551.8   41.67  539.96   60.98     538   73.76     536
   99.39     536  136.68  533.25  150.66  528.33  159.45     524  163.35     520
  175.48     516  187.01  513.08  191.91  513.18  199.36  511.64  206.64  511.08
  208.31     510  215.49  507.95  229.37   506.7   249.6  507.94  260.82  509.55
  273.89  512.63  288.35     518  291.06     520  294.23   524.1  353.44  536.03
  468.02  535.32  576.35  535.82  676.29  537.65  803.23  538.64  938.86     548
#Mann= 3 ,-1,0
       0     .06       0  136.68    .035       0  353.44     .06       0
#XS Ineff= 2 , 0
       0                  849.86       0
Permanent Ineff=
       F       F
Bank Sta=136.68,353.44
XS Rating Curve= 0 ,0
Exp/Cntr=0.5,0.3

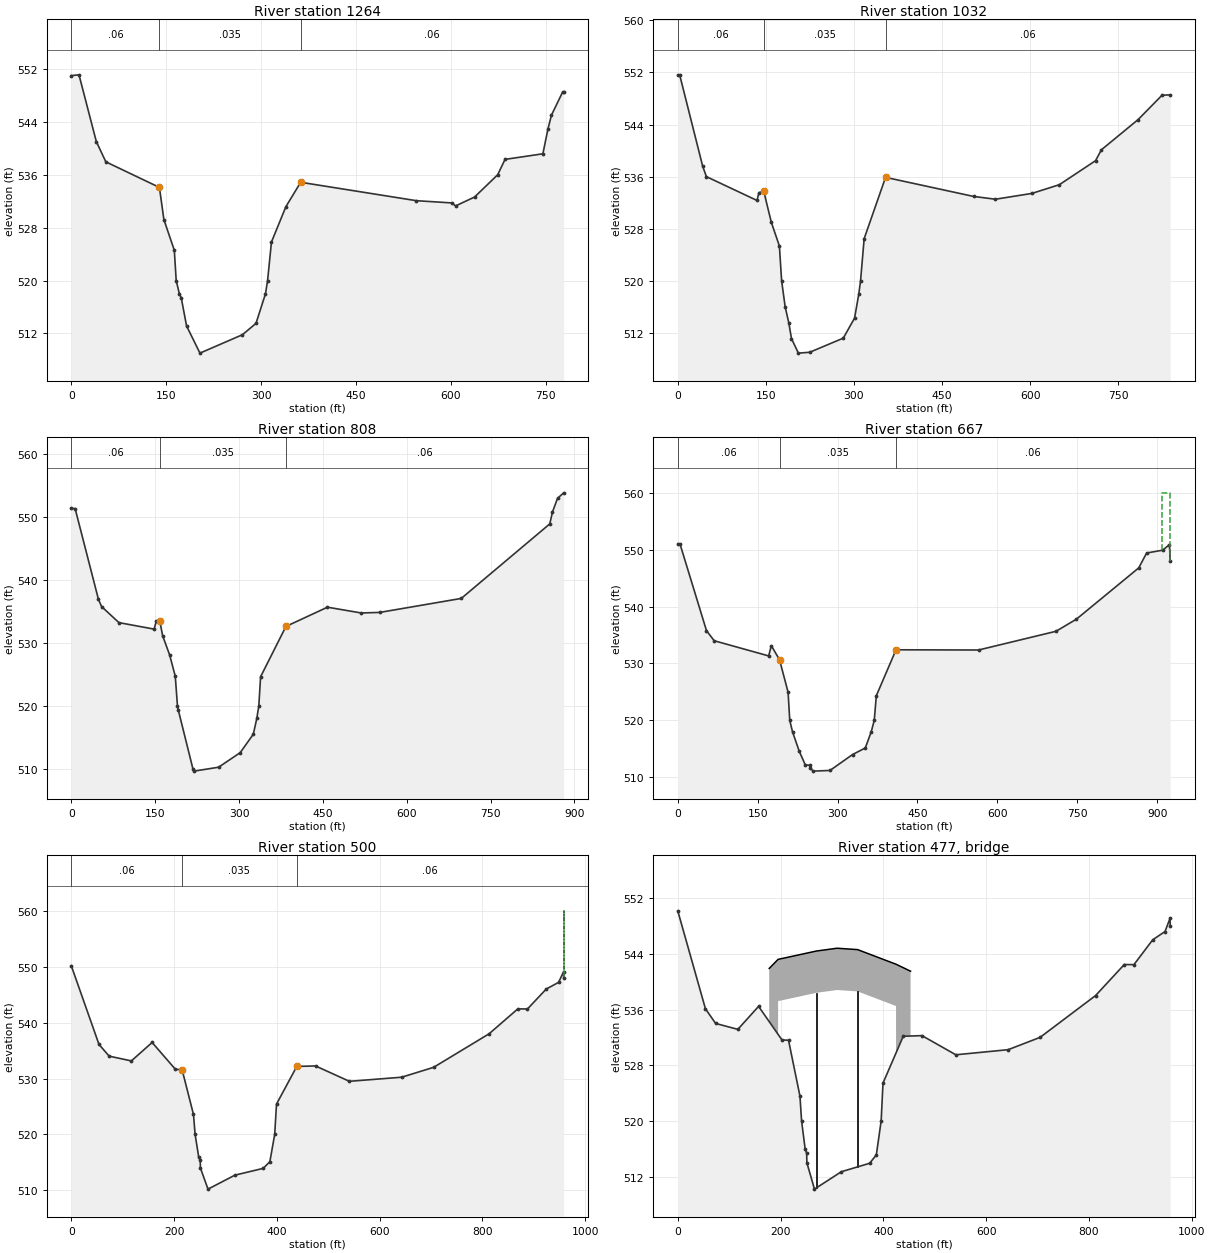
Type RM Length L Ch R = 1 ,1264    ,232,232,229
BEGIN DESCRIPTION:
This cross section corresponds to cross section 1266.415 of the non-georeferenced CDC model which was the source of this model.
Effective flow limit in LOB set at Clear Fork Levee Loop.
---------------------------------------------------------------------
RADIO SHACK RIVERFRONT CAMPUS CDC FW080602-01 IN ROB.
---------------------------------------------------------------------
END DESCRIPTION:
XS GIS Cut Line= 2
 2324372.0990816 6960976.3744523  2324931.520986 6960434.5919475
#Sta/Elev= 30
       0  551.07   12.19  551.19    39.6  541.07   54.62     538  139.37  534.12
  146.48  529.23  162.94  524.59  165.92     520   170.9     518  173.86   517.4
  182.32  513.12  203.47     509  270.63  511.79  292.11  513.51  307.11     518
  310.44     520  316.56  525.84  339.44  531.21  362.78   534.9  545.75  532.11
  601.72  531.77  607.76  531.32  637.73  532.66  674.32  536.04  685.95  538.37
  745.82  539.22  753.81  542.97  759.39  545.08   777.1  548.59  778.77  548.57
#Mann= 3 ,-1,0
       0     .06       0  139.37    .035       0  362.78     .06       0
Bank Sta=139.37,362.78
XS Rating Curve= 0 ,0
Exp/Cntr=0.3,0.1

Type RM Length L Ch R = 1 ,1032    ,224,224,203
BEGIN DESCRIPTION:
This cross section corresponds to cross section 1034.324 of the non-georeferenced CDC model which was the source of this model.
Effective flow limit in LOB set at Clear Fork Levee Loop.
---------------------------------------------------------------------
RADIO SHACK RIVERFRONT CAMPUS CDC FW080602-01 IN ROB.
---------------------------------------------------------------------
END DESCRIPTION:
XS GIS Cut Line= 2
 2324539.6081056 6961140.5371409 2325135.3547255 6960550.2813216
#Sta/Elev= 30
       0  551.63    3.28  551.62   42.43   537.6   48.76     536  134.95  532.34
  138.13  533.51  146.34   533.8  159.31     529  173.11  525.34  176.89     520
  182.94     516  189.18  513.52  193.68  511.13  205.44   508.9  224.68  509.03
  281.88   511.2  301.15  514.28  308.36     518  311.31     520  317.47  526.48
  353.93  535.89  503.72  532.96  541.04  532.53  603.04  533.42  649.87  534.76
  711.56  538.45  721.49  540.12  784.06  544.76  824.65  548.49  838.64  548.56
#Mann= 3 ,-1,0
       0     .06       0  146.34    .035       0  353.93     .06       0
Bank Sta=146.34,353.93
XS Rating Curve= 0 ,0
Exp/Cntr=0.3,0.1

Type RM Length L Ch R = 1 ,808     ,141,141,127
BEGIN DESCRIPTION:
This cross section corresponds to cross section 811.3182 of the non-georeferenced CDC model which was the source of this model.
Effective flow limit in LOB set at Clear Fork Levee Loop.
---------------------------------------------------------------------
RADIO SHACK RIVERFRONT CAMPUS CDC FW080602-01 IN ROB.
---------------------------------------------------------------------
END DESCRIPTION:
XS GIS Cut Line= 3
 2324708.5334204 6961305.5650308 2324967.3296142 6961018.5481571
 2325234.5169906 6960602.6170588
#Sta/Elev= 30
       0  551.36    6.88   551.3   48.65  536.88   54.18  535.76   85.22  533.21
  148.12  532.18  152.11  533.46   158.5  533.39  163.37  531.13     176  528.06
  185.98  524.71  189.91     520  191.24   519.4  217.56     510  219.67  509.64
  263.46  510.26  302.11  512.57   325.6   515.5  331.82     518  335.43     520
  338.64  524.62  383.92   532.6   458.2  535.66  518.62  534.74  551.74  534.83
  697.57  537.05  855.87  548.88  860.73  550.77  869.73  552.94  880.82  553.81
#Mann= 3 ,-1,0
       0     .06       0   158.5    .035       0  383.92     .06       0
Bank Sta=158.5,383.92
XS Rating Curve= 0 ,0
Exp/Cntr=0.3,0.1

Type RM Length L Ch R = 1 ,667     ,167,167,145
BEGIN DESCRIPTION:
This cross section corresponds to cross section 670.0113 of the non-georeferenced CDC model which was the source of this model.
Effective flow limit in LOB set at Clear Fork Levee Loop.
---------------------------------------------------------------------
RADIO SHACK RIVERFRONT CAMPUS CDC FW080602-01 IN ROB.
---------------------------------------------------------------------
END DESCRIPTION:
XS GIS Cut Line= 3
 2324812.9117841 6961409.2452961 2325080.2644485 6961098.4289031
2325305.944858186960636.19193027
#Sta/Elev= 30
       0  551.04    4.21  551.01   53.95  535.77   68.41     534  170.67  531.33
  175.59  533.14  191.06  530.65  207.12  524.95  210.24     520   215.4     518
  227.91  514.61   239.3   512.2  247.39   512.1  248.72  511.63  254.38  511.08
   285.8   511.2  328.18     514  352.05  515.15   363.2     518  368.86     520
  372.75  524.34  409.73  532.41  564.54  532.37  709.99  535.66  748.31  537.79
  865.38  546.81  880.12  549.42  910.36  549.92  922.98   550.9  924.37     548
#Mann= 3 ,-1,0
       0     .06       0  191.06    .035       0  409.73     .06       0
#XS Ineff= 2 , 0
       0                  908.43       0     560
Permanent Ineff=
       F       F
Bank Sta=191.06,409.73
XS Rating Curve= 0 ,0
Exp/Cntr=0.5,0.3

Type RM Length L Ch R = 1 ,500     ,28,28,25
BEGIN DESCRIPTION:
This cross section corresponds to cross section 501.6482 of the non-georeferenced CDC model which was the source of this model.
Effective flow limit in LOB set at Clear Fork Levee Loop.
---------------------------------------------------------------------
RADIO SHACK RIVERFRONT CAMPUS CDC FW080602-01 IN ROB.
---------------------------------------------------------------------
END DESCRIPTION:
XS GIS Cut Line= 5
 2324917.8435708 6961507.0659417 2325008.3015784 6961446.4914756
 2325047.8769567 6961405.3006831 2325235.2542397  6961161.387275
2325349.081088016960690.29224345
#Sta/Elev= 30
       0  550.17   53.89   536.1   73.71     534  116.92  533.15   157.3  536.45
  202.78  531.63  215.56  531.59  237.77  523.57  240.95     520  247.85     516
  250.89  515.35  251.25     514  266.02  510.21  318.37  512.71  373.33  513.92
   386.4  515.12   395.8     520  399.36  525.43  438.79  532.16  475.23  532.25
  541.11   529.5  642.81  530.23  705.03     532  812.99     538   868.9  542.46
  887.64  542.44  924.24  546.01  948.19   547.2  957.94   549.1  958.22     548
#Mann= 3 ,-1,0
       0     .06       0  215.56    .035       0  438.79     .06       0
#XS Ineff= 2 , 0
       0                  957.94       0     560
Permanent Ineff=
       F       F
Bank Sta=215.56,438.79
XS Rating Curve= 0 ,0
Exp/Cntr=0.5,0.3

Type RM Length L Ch R = 3 ,477     ,,,
BEGIN DESCRIPTION:
Pedestrian Bridge
Bridge data from TRWD May 2007 survey data, bridge plans.  Minimum low chord elev. 537.0.  Bridge width 10 feet.
END DESCRIPTION:
Node Name=ped. bridge
Bridge Culvert--1,0,-1,-1, 0
Deck Dist Width WeirC Skew NumUp NumDn MinLoCord MaxHiCord MaxSubmerge Is_Ogee
13.7,10,2.6,0, 9, 9, , , 0.95, 0, 0,0,,
     178  195.25  195.25     270     310     350   424.8   424.8     453
   541.9   543.2   543.2   544.4   544.8   544.6   542.5   542.5   541.5
     450     450   537.2   538.4   538.8   538.6   536.5     450     450
     174  206.25  206.25     281     321     361   435.8   435.8   456.7
   541.9   543.2   543.2   544.4   544.8   544.6   542.5   542.2   541.5
     450     450   537.2   538.4   538.8   538.6   536.5     450     450
Pier Skew, UpSta & Num, DnSta & Num=  ,270, 2 ,281, 2 , 0 , 0 , 0 ,,
     2.5     2.5
     500     540
     2.5     2.5
     500     540
Pier Skew, UpSta & Num, DnSta & Num=  ,350, 2 ,361, 2 , 0 , 0 , 0 ,,
     2.5     2.5
     500     540
     2.5     2.5
     500     540
BR Coef=-1 , 0 , 0 ,, 0 ,,,0.8,-1,,0,
WSPro=,,,, 1 ,,,, 0 ,,,, 0 ,,,,-1 ,-1 ,-1 , 0 , 0 , 0 , 0 , 0
BC Design=,, 0 ,, 0 ,,,,,,
BC Use User HTab Curves=0
BC User HTab FreeFlow(D)= 0

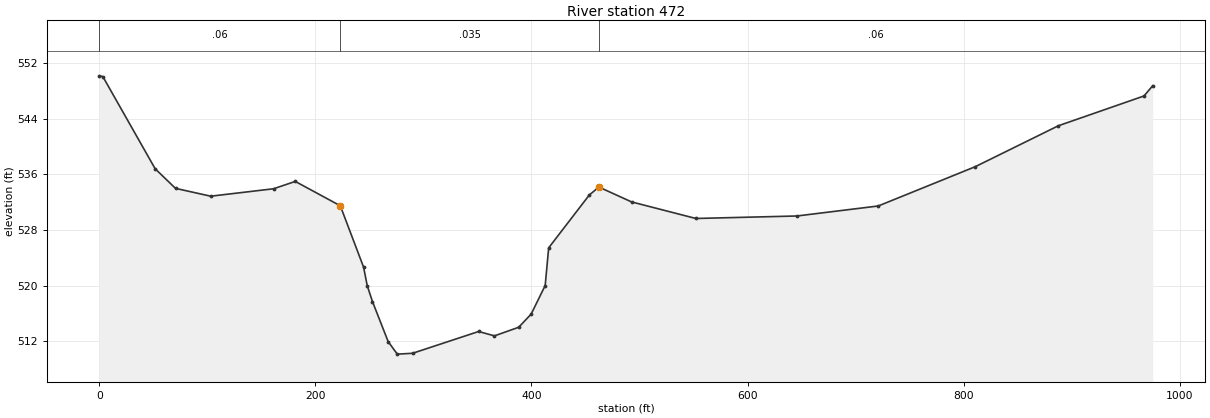
Type RM Length L Ch R = 1 ,472     ,472,472,472
BEGIN DESCRIPTION:
This cross section corresponds to cross section 473.3100 of the non-georeferenced CDC model which was the source of this model.
Cross-section located 473.31 feet upstream of the West Fork/Clear Fork confluence.
Effective flow limit in LOB set at Clear Fork Levee Loop.
---------------------------------------------------------------------
RADIO SHACK RIVERFRONT CAMPUS CDC FW080602-01 IN ROB.
---------------------------------------------------------------------
END DESCRIPTION:
XS GIS Cut Line= 5
 2324929.0239065 6961521.7620492 2325020.9806544 6961468.4689383
 2325069.5193062 6961426.8827511 2325259.4840261  6961172.694526
 2325373.1319969 6960698.5736453
#Sta/Elev= 30
       0  550.21    3.25   550.1   51.68  536.82    70.5     534  103.08  532.87
  161.27  533.94  181.36     535  223.05  531.49  244.62  522.64  247.95     520
  252.82  517.69  267.37  511.92  275.79  510.12  289.92  510.24   351.1  513.38
  365.74  512.75  388.18  513.99  399.69  515.88  412.69     520  415.92  525.43
  453.52  533.04  462.38  534.19  492.61  532.05  552.17  529.66  645.76  530.02
  720.99  531.46  810.78  537.12  887.77  543.02  967.01  547.31  975.08  548.79
#Mann= 3 ,-1,0
       0     .06       0  223.05    .035       0  462.38     .06       0
Bank Sta=223.05,462.38
XS Rating Curve= 0 ,0
Exp/Cntr=0.5,0.3

River Reach=West Fork       ,wf4

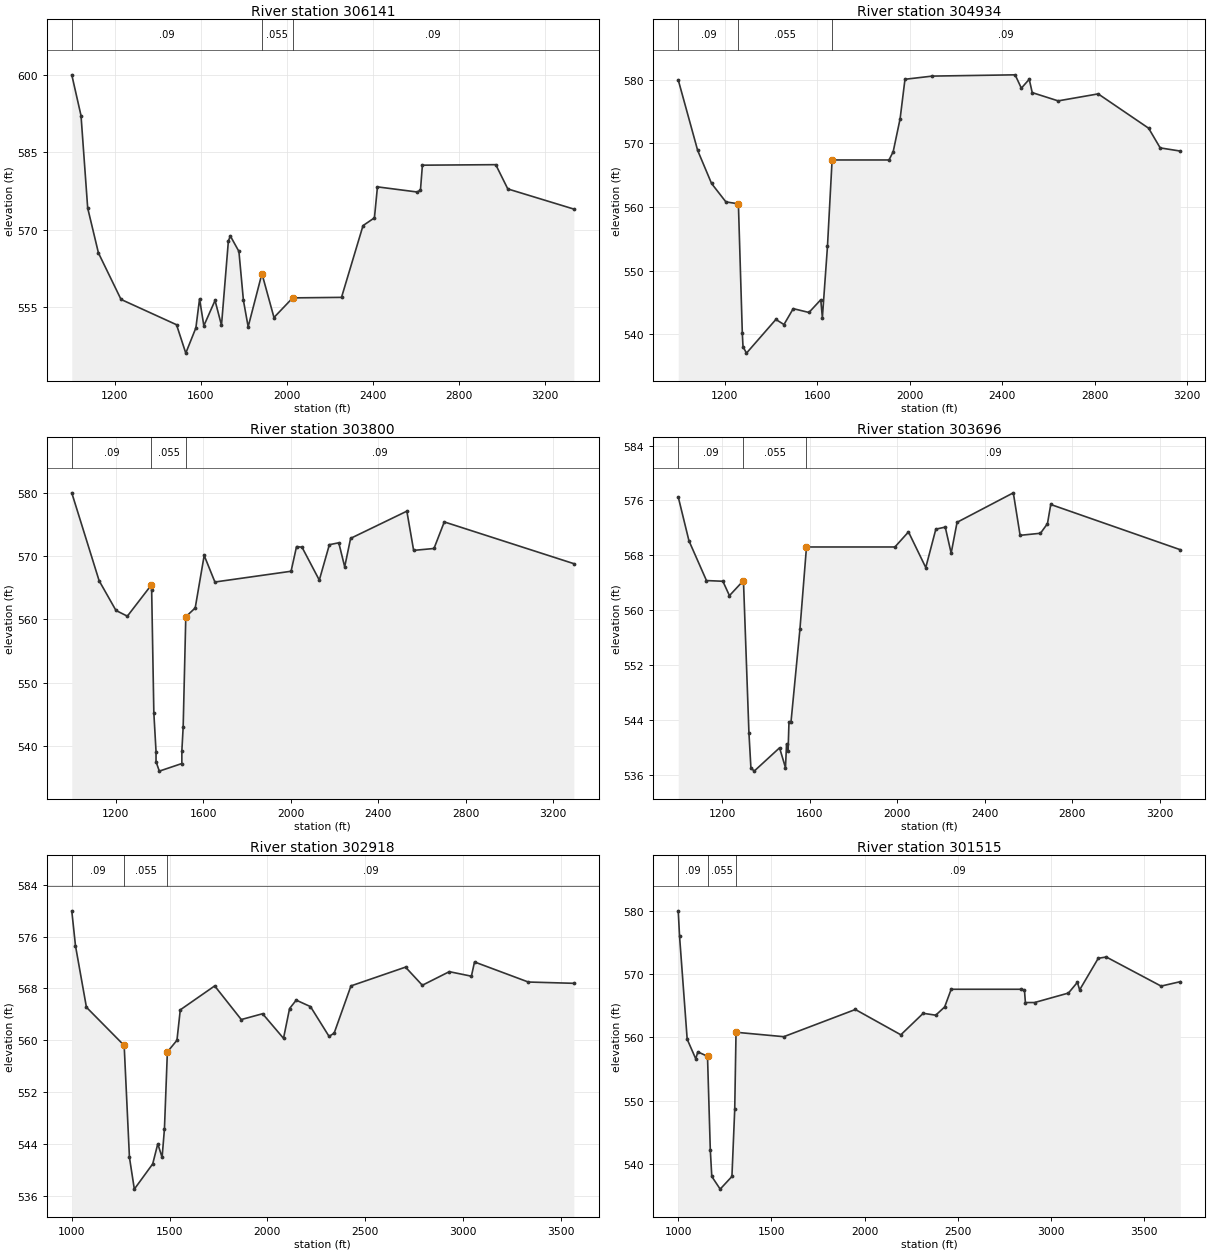
Type RM Length L Ch R = 1 ,306141  ,1207,1207,805
BEGIN DESCRIPTION:
This cross section corresponds to cross section 305599.5 of the non-georeferenced CDC model which was the source of this model.
424 feet downstream of Lake Worth Spillway.  Fish
hatchery ponds removed from conveyance in ROB.
Lake Worth: spillway crest elev. 594.3, top of dam elev. 606.3,
sta 3060+24 river mile 57.96
Channel data from 1975 USACE field survey.
END DESCRIPTION:
XS GIS Cut Line= 5
      2302262.09      6973483.24     2302130.541     6972749.547
      2302051.83     6972311.915     2302108.502     6971971.885
2301990.387650576971181.42817069
#Sta/Elev= 30
    1000     600    1043   592.1    1074   574.2    1124   565.5    1229   556.5
    1487   551.6    1530   546.1    1577     551    1594   556.6    1614   551.4
    1666   556.3    1696   551.5    1728   567.8    1737   568.8    1777   565.8
    1798   556.3    1820   551.2    1884   561.5    1940     553    2027   556.8
    2254   556.9    2354   570.8    2407   572.3    2421   578.3    2607   577.3
    2621   577.7    2630   582.5    2971   582.6    3027   577.9    3334     574
#Mann= 3 ,0,0
    1000     .09       0    1884    .055       0    2027     .09       0
Bank Sta=1884,2027
XS Rating Curve= 0 ,0
Exp/Cntr=0.3,0.1

Type RM Length L Ch R = 1 ,304934  ,1134,1134,742
BEGIN DESCRIPTION:
This cross section corresponds to cross section 304609.5 of the non-georeferenced CDC model which was the source of this model.
Fish hatchery ponds removed from conveyance removed in
ROB.
Channel data from 1975 USACE field survey.
END DESCRIPTION:
XS GIS Cut Line= 3
      2303319.57     6973163.447      2303157.07     6972644.864
     2302670.734     6971092.828
#Sta/Elev= 30
    1000     580    1084   568.9    1144   563.7    1206   560.8    1260   560.5
    1277   540.1    1280     538    1295     537    1422   542.3    1457   541.5
    1497     544    1565   543.4    1616   545.4    1623   542.6    1645   553.8
    1665   567.4    1911   567.4    1929   568.7    1959   573.9    1980   580.1
    2098   580.6    2456   580.8    2483   578.7    2517   580.1    2530     578
    2642   576.7    2815   577.8    3033   572.4    3083   569.3    3170   568.8
#Mann= 3 ,0,0
    1000     .09       0    1260    .055       0    1665     .09       0
#XS Ineff= 2 , 0
       0                    2702       0
Permanent Ineff=
       F       F
Bank Sta=1260,1665
XS Rating Curve= 0 ,0
Exp/Cntr=0.3,0.1

Type RM Length L Ch R = 1 ,303800  ,105,105,105
BEGIN DESCRIPTION:
This cross section corresponds to cross section 303612.5 of the non-georeferenced CDC model which was the source of this model.
Channel data from 1975 USACE field survey.
END DESCRIPTION:
XS GIS Cut Line= 6
     2304346.193     6972656.786      2304329.86     6972634.336
     2304087.261     6972300.856     2304086.173      6972299.36
     2303930.184     6972084.937     2302682.613     6971104.311
#Sta/Elev= 30
    1000     580    1125   566.1    1202   561.4    1254   560.5    1363   565.4
    1365   564.7    1375   545.2    1385   539.1    1385   537.5    1400     536
    1503   537.2    1503   539.2    1509     543    1521   560.4    1564   561.8
    1605   570.1    1654   565.9    2002   567.6    2027   571.5    2052   571.4
    2131   566.2    2177   571.8    2220   572.1    2247   568.3    2274   572.8
    2531   577.1    2562   570.9    2655   571.2    2702   575.4    3294   568.8
#Mann= 3 ,0,0
    1000     .09       0    1363    .055       0    1521     .09       0
#XS Ineff= 2 , 0
       0                    2198       0
Permanent Ineff=
       F       F
Bank Sta=1363,1521
XS Rating Curve= 0 ,0
Exp/Cntr=0.3,0.1

Type RM Length L Ch R = 1 ,303696  ,778,778,646
BEGIN DESCRIPTION:
This cross section corresponds to cross section 303510.5 of the non-georeferenced CDC model which was the source of this model.
Fish hatchery pond in ROB removed from conveyance.
Channel data from 1975 USACE field survey.
END DESCRIPTION:
XS GIS Cut Line= 6
     2304419.002     6972585.952     2304001.906     6972012.607
     2303878.534     6971927.404     2303877.646     6971926.792
     2303865.897     6971918.677     2302697.705     6971111.909
#Sta/Elev= 30
    1000   576.5    1049   570.1    1129   564.3    1204   564.2    1234   562.1
    1298   564.3    1323   542.1    1332     537    1347   536.5    1463   539.9
    1490     537    1495   540.5    1502   539.5    1506   543.7    1515   543.6
    1556   557.2    1586   569.2    1990   569.2    2052   571.4    2131   566.2
    2177   571.8    2220   572.1    2247   568.3    2274   572.8    2531   577.1
    2562   570.9    2655   571.2    2687   572.6    2702   575.4    3294   568.8
#Mann= 3 ,0,0
    1000     .09       0    1298    .055       0    1586     .09       0
#XS Ineff= 2 , 0
       0                    2198       0
Permanent Ineff=
       F       F
Bank Sta=1298,1586
XS Rating Curve= 0 ,0
Exp/Cntr=0.3,0.1

Type RM Length L Ch R = 1 ,302918  ,1403,1403,710
BEGIN DESCRIPTION:
This cross section corresponds to cross section 302774.5 of the non-georeferenced CDC model which was the source of this model.
Channel data from 1975 USACE field survey.
END DESCRIPTION:
XS GIS Cut Line= 4
     2305024.641     6971993.963      2304735.08     6971782.824
     2304271.835     6971445.042     2302673.085     6971094.992
#Sta/Elev= 30
    1000     580    1019   574.6    1075   565.1    1268   559.2    1295   541.9
    1320     537    1414   540.9    1440     544    1462   541.9    1474   546.3
    1489   558.2    1538     560    1555   564.7    1731   568.4    1867   563.2
    1976   564.1    2083   560.3    2114   564.9    2148   566.2    2221   565.2
    2316   560.6    2342   561.1    2428   568.4    2707   571.3    2793   568.5
    2931   570.6    3044   569.9    3060   572.1    3335     569    3568   568.8
#Mann= 3 ,0,0
    1000     .09       0    1268    .055       0    1489     .09       0
#XS Ineff= 2 , 0
       0                    3060       0
Permanent Ineff=
       F       F
Bank Sta=1268,1489
XS Rating Curve= 0 ,0
Exp/Cntr=0.3,0.1

Type RM Length L Ch R = 1 ,301515  ,865,865,911
BEGIN DESCRIPTION:
This cross section corresponds to cross section 301394.5 of the non-georeferenced CDC model which was the source of this model.
Camp Carter area in ROB - conveyance removed from ponds
in ROB.
Channel data from 1975 USACE field survey.
END DESCRIPTION:
XS GIS Cut Line= 3
     2305295.294     6970463.488     2305065.749     6970518.726
     2302676.613      6971093.64
#Sta/Elev= 30
    1000     580    1007     576    1048   559.7    1094   556.6    1105   557.7
    1157     557    1172   542.2    1180     538    1225     536    1288     538
    1303   548.6    1310   560.8    1566   560.1    1950   564.4    2194   560.4
    2314   563.8    2381   563.5    2429   564.8    2464   567.6    2838   567.6
    2857   567.5    2862   565.5    2911   565.5    3093     567    3141   568.7
    3153   567.5    3253   572.5    3296   572.7    3590   568.1    3693   568.8
#Mann= 3 ,0,0
    1000     .09       0    1157    .055       0    1310     .09       0
#XS Ineff= 2 , 0
       0                    3296       0
Permanent Ineff=
       F       F
Bank Sta=1157,1310
XS Rating Curve= 0 ,0
Exp/Cntr=0.3,0.1

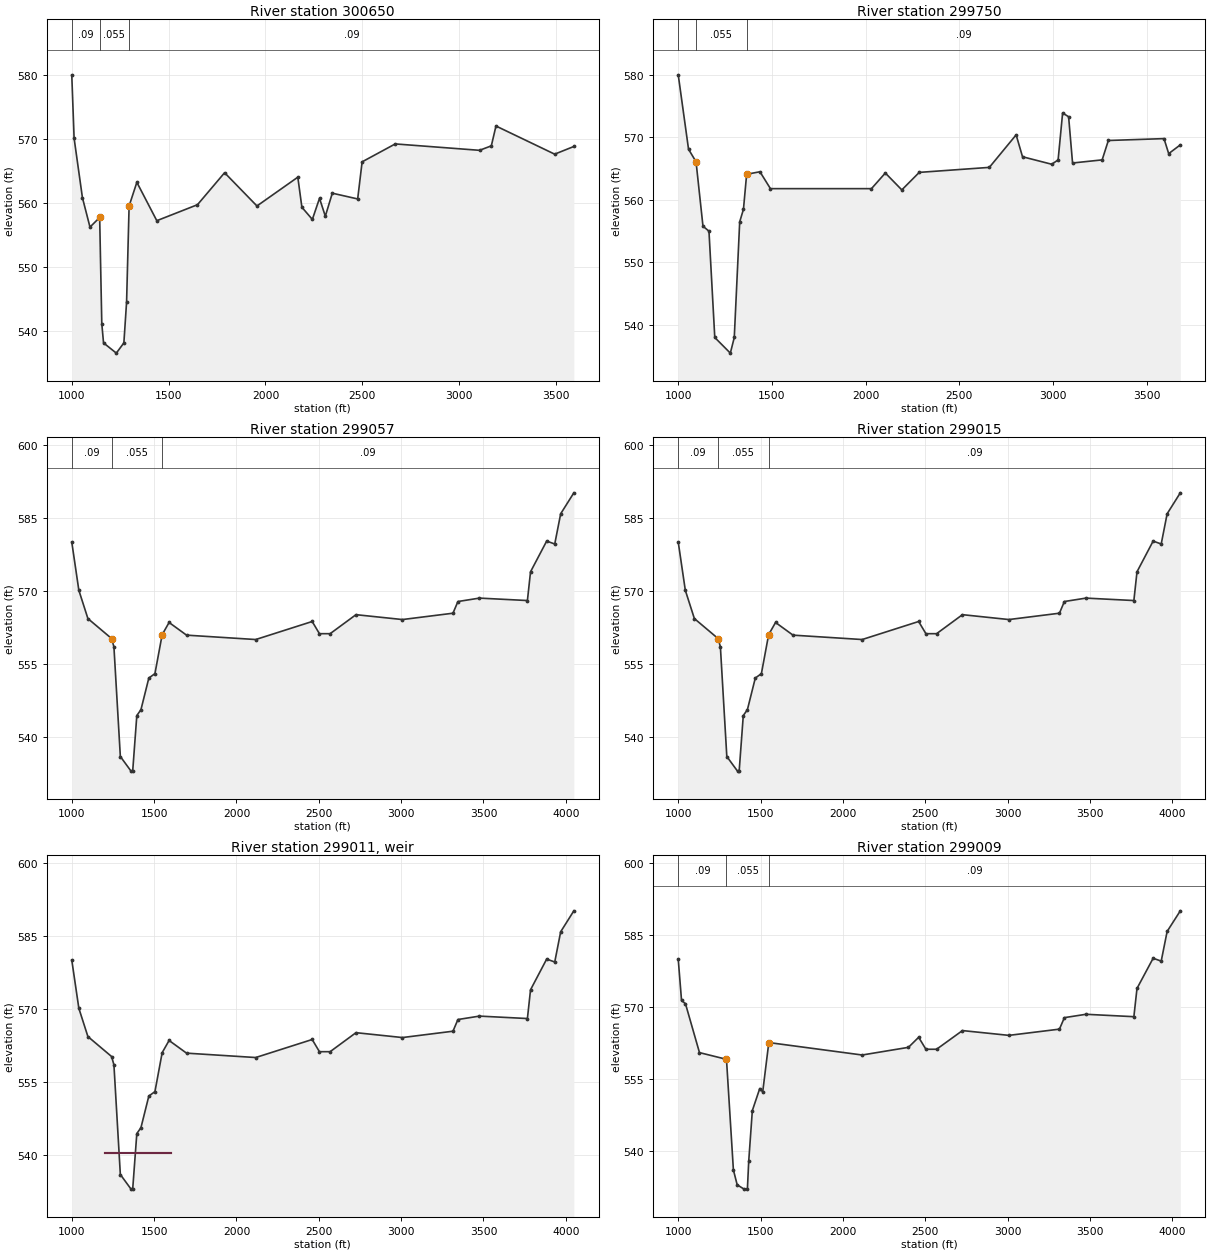
Type RM Length L Ch R = 1 ,300650  ,900,900,841
BEGIN DESCRIPTION:
This cross section corresponds to cross section 300530.5 of the non-georeferenced CDC model which was the source of this model.
Camp Carter area in ROB - conveyance removed from ponds
in ROB.
Channel data from 1975 USACE field survey.
END DESCRIPTION:
XS GIS Cut Line= 4
     2304822.302     6969645.464     2304656.012     6969776.577
     2304070.644     6970238.117     2302676.012     6971091.389
#Sta/Elev= 30
    1000     580    1012   570.1    1055   560.8    1094   556.2    1144   557.7
    1155   541.1    1164   538.1    1230   536.5    1269   538.1    1283   544.5
    1296   559.5    1336   563.2    1439   557.2    1649   559.7    1789   564.7
    1956   559.5    2167     564    2188   559.3    2242   557.4    2279   560.7
    2309   557.9    2345   561.5    2476   560.6    2499   566.4    2670   569.2
    3105   568.2    3166   568.9    3190     572    3493   567.6    3592   568.8
#Mann= 3 ,0,0
    1000     .09       0    1144    .055       0    1296     .09       0
#XS Ineff= 2 , 0
       0                    3190       0
Permanent Ineff=
       F       F
Bank Sta=1144,1296
XS Rating Curve= 0 ,0
Exp/Cntr=0.3,0.1

Type RM Length L Ch R = 1 ,299750  ,693,693,965
BEGIN DESCRIPTION:
This cross section corresponds to cross section 299631.5 of the non-georeferenced CDC model which was the source of this model.
Camp Carter area in ROB - conveyance removed from ponds
in ROB.
Channel data from 1975 USACE field survey.
END DESCRIPTION:
XS GIS Cut Line= 4
     2304217.732     6968943.697     2304051.233     6969114.188
     2303212.619      6969972.91     2302676.012     6971091.389
#Sta/Elev= 30
    1000     580    1055   568.1    1095   566.1    1132   555.8    1164     555
    1195     538    1278   535.5    1299     538    1328   556.5    1348   558.5
    1365   564.1    1436   564.5    1492   561.8    2031   561.8    2105   564.3
    2193   561.6    2286   564.4    2660   565.2    2803   570.4    2837   566.9
    2993   565.7    3027   566.4    3051   573.9    3083   573.3    3104   565.9
    3262   566.4    3295   569.5    3592   569.8    3617   567.4    3679   568.8
#Mann= 3 ,0,0
    1000     .09       0    1095    .055       0    1365     .09       0
#XS Ineff= 2 , 0
       0                    3346       0
Permanent Ineff=
       F       F
Bank Sta=1095,1365
XS Rating Curve= 0 ,0
Exp/Cntr=0.3,0.1

Type RM Length L Ch R = 1 ,299057  ,41,41,41
BEGIN DESCRIPTION:
This cross section corresponds to cross section 298943.5 of the non-georeferenced CDC model which was the source of this model.
Camp Carter area in ROB - conveyance removed from ponds
in ROB.
Channel data from 1975 USACE field survey.
END DESCRIPTION:
XS GIS Cut Line= 6
     2303567.857      6968435.92     2303448.517     6968911.441
      2303376.55     6969030.402     2303364.375     6969050.529
      2302868.87     6969869.589     2301541.644     6970424.909
#Sta/Elev= 30
    1000     580    1043   570.1    1098   564.3    1242   560.2    1256   558.5
    1295     536    1360     533    1370     533    1395   544.4    1420   545.6
    1468   552.1    1505     553    1549     561    1591   563.5    1697   560.9
    2117     560    2460   563.7    2504   561.2    2569   561.2    2726   565.1
    3008   564.1    3315   565.4    3345   567.8    3476   568.5    3767     568
    3786   573.9    3884   580.2    3933   579.6    3969   585.8    4049   590.1
#Mann= 3 ,0,0
    1000     .09       0    1242    .055       0    1549     .09       0
Bank Sta=1242,1549
XS Rating Curve= 0 ,0
Exp/Cntr=0.3,0.1

Type RM Length L Ch R = 1 ,299015  ,7,7,7
BEGIN DESCRIPTION:
This cross section corresponds to cross section 298899.5 of the non-georeferenced CDC model which was the source of this model.
One-foot upstream of channel dam.
END DESCRIPTION:
XS GIS Cut Line= 6
     2303541.772     6968369.241     2303517.616      6968466.28
     2303446.112     6968753.514     2303390.849     6968975.509
      2302860.31     6969853.644      2301570.19     6970395.445
#Sta/Elev= 30
    1000     580    1043   570.1    1098   564.3    1242   560.2    1256   558.5
    1295     536    1360     533    1370     533    1395   544.4    1420   545.6
    1468   552.1    1505     553    1549     561    1591   563.5    1697   560.9
    2117     560    2460   563.7    2504   561.2    2569   561.2    2726   565.1
    3008   564.1    3315   565.4    3345   567.8    3476   568.5    3767     568
    3786   573.9    3884   580.2    3933   579.6    3969   585.8    4049   590.1
#Mann= 3 ,0,0
    1000     .09       0    1242    .055       0    1549     .09       0
Bank Sta=1242,1549
XS Rating Curve= 0 ,0
Exp/Cntr=0.3,0.1

Type RM Length L Ch R = 5 ,299011  ,,,
BEGIN DESCRIPTION:
channel dam
crest elevation 540.5
END DESCRIPTION:
Node Name=channel dam
IW Pilot Flow=0
#Inline Weir SE= 2
    1200   540.5    1600   540.5
IW Dist,WD,Coef,Skew,MaxSub,Min_El,Is_Ogee,SpillHt,DesHd
2,5,3,0,0.95,, 0 ,,,2,2,
Inline Weir Flap Gates= 0
IW Outlet Rating Curve= 0 ,False,,

Type RM Length L Ch R = 1 ,299009  ,49,49,49
BEGIN DESCRIPTION:
This cross section corresponds to cross section 298892.5 of the non-georeferenced CDC model which was the source of this model.
Duplication of cross-section 298842.58.  One-foot downstream of channel dam.
END DESCRIPTION:
XS GIS Cut Line= 5
     2303541.083     6968343.313     2303439.143     6968752.815
     2303384.093     6968973.953     2302853.554     6969852.087
     2301586.591     6970384.164
#Sta/Elev= 30
    1000     580    1020   571.4    1044   570.7    1129   560.5    1293   559.1
    1335     536    1358   532.9    1400     532    1420     532    1428   537.8
    1450   548.4    1495     553    1513   552.3    1550   562.6    2117     560
    2398   561.6    2460   563.7    2504   561.2    2569   561.2    2726   565.1
    3008   564.1    3315   565.4    3345   567.8    3476   568.5    3767     568
    3786   573.9    3884   580.2    3933   579.6    3969   585.8    4049   590.1
#Mann= 3 ,0,0
    1000     .09       0    1293    .055       0    1550     .09       0
Bank Sta=1293,1550
XS Rating Curve= 0 ,0
Exp/Cntr=0.3,0.1

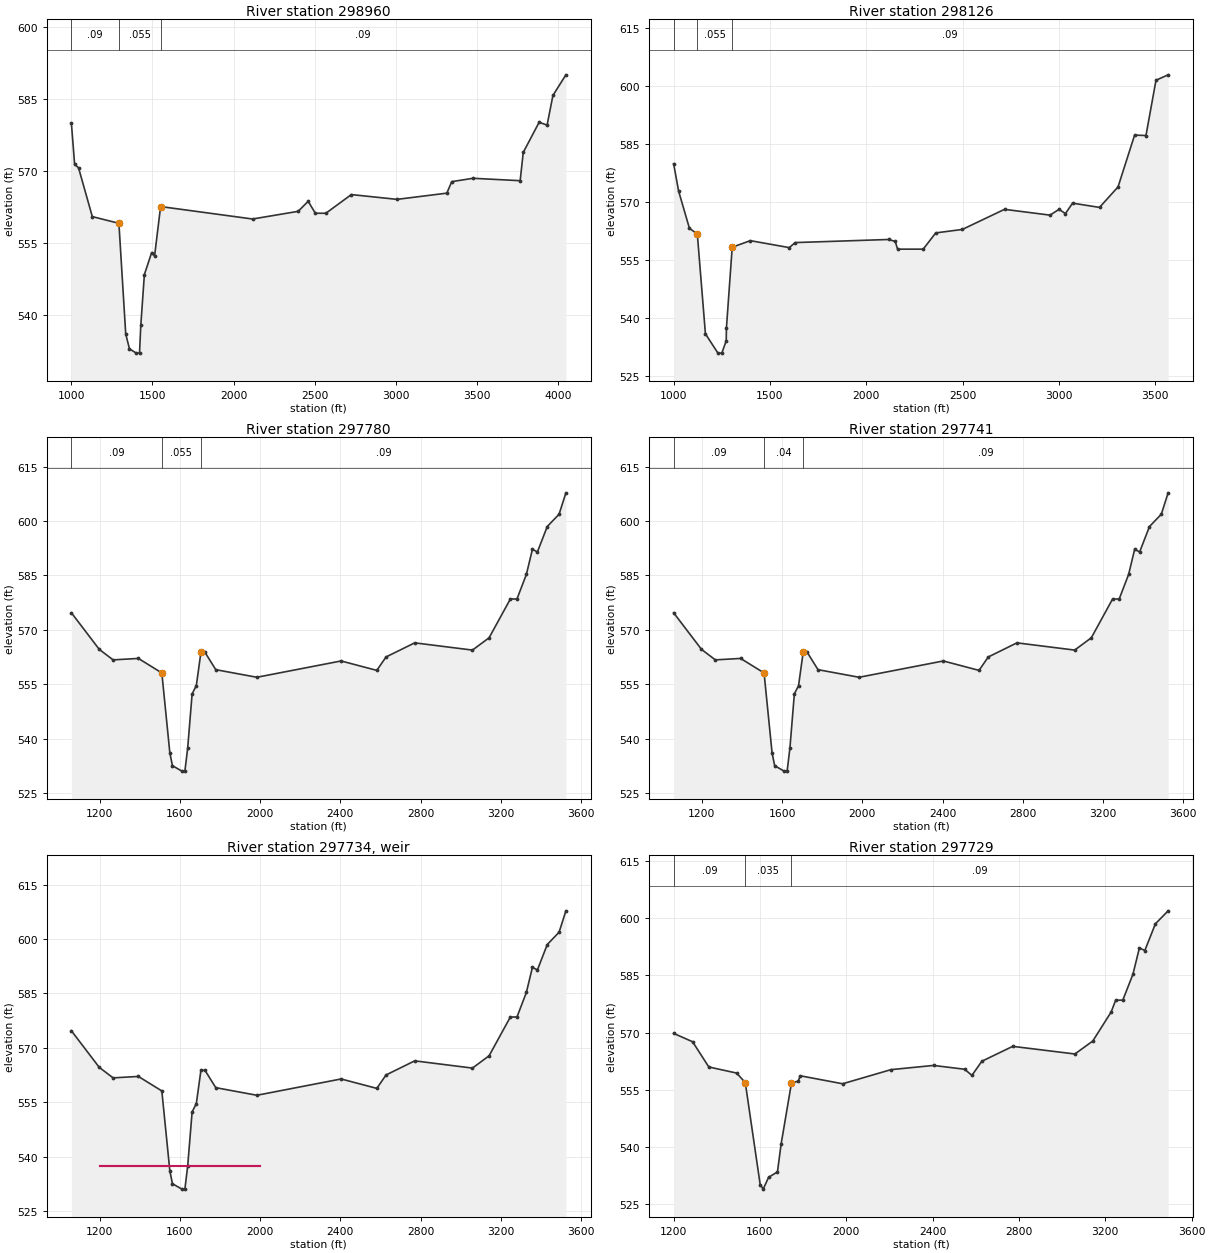
Type RM Length L Ch R = 1 ,298960  ,834,834,783
BEGIN DESCRIPTION:
This cross section corresponds to cross section 298842.5 of the non-georeferenced CDC model which was the source of this model.
51 feet downstream of channel dam.  Camp Carter area in
ROB - conveyance removed from ponds in ROB.
Channel data from 1975 USACE field survey.
END DESCRIPTION:
XS GIS Cut Line= 6
     2303492.279     6968336.068     2303492.279     6968336.069
     2303390.608     6968745.637     2303311.771     6969063.219
     2302838.729     6969842.041     2301553.591     6970370.509
#Sta/Elev= 30
    1000     580    1020   571.4    1044   570.7    1129   560.5    1293   559.1
    1335     536    1358   532.9    1400     532    1420     532    1428   537.8
    1450   548.4    1495     553    1513   552.3    1550   562.6    2117     560
    2398   561.6    2460   563.7    2504   561.2    2569   561.2    2726   565.1
    3008   564.1    3315   565.4    3345   567.8    3476   568.5    3767     568
    3786   573.9    3884   580.2    3933   579.6    3969   585.8    4049   590.1
#Mann= 3 ,0,0
    1000     .09       0    1293    .055       0    1550     .09       0
Bank Sta=1293,1550
XS Rating Curve= 0 ,0
Exp/Cntr=0.3,0.1

Type RM Length L Ch R = 1 ,298126  ,345,345,345
BEGIN DESCRIPTION:
This cross section corresponds to cross section 297998.5 of the non-georeferenced CDC model which was the source of this model.
Camp Carter area in ROB.  Conveyance removed below
elev. 559.2 in pond in ROB.
Channel data from 1975 USACE field survey.
END DESCRIPTION:
XS GIS Cut Line= 4
     2302680.992     6968219.227     2302663.012      6968426.67
     2302585.166     6969324.825      2301357.51     6970107.859
#Sta/Elev= 30
    1000     580    1026   572.9    1082   563.3    1123   561.8    1165     536
    1230     531    1250     531    1273   534.2    1274   537.5    1304   558.4
    1398   560.1    1600   558.3    1631   559.6    2115   560.4    2150   559.9
    2162   557.9    2295   557.9    2360   562.1    2498     563    2717   568.2
    2953   566.7    3000   568.2    3033   567.1    3070   569.8    3210   568.7
    3306     574    3392   587.4    3451   587.3    3503   601.6    3566     603
#Mann= 3 ,0,0
    1000     .09       0    1123    .055       0    1304     .09       0
Bank Sta=1123,1304
XS Rating Curve= 0 ,0
Exp/Cntr=0.3,0.1

Type RM Length L Ch R = 1 ,297780  ,40,40,40
BEGIN DESCRIPTION:
This cross section corresponds to cross section 297653.5 of the non-georeferenced CDC model which was the source of this model.
41 feet upstream of channel dam.  Effective flow limit
set at sta 1059 in LOB at Anahuac Street.
Channel data from 1975 USACE field survey.
END DESCRIPTION:
XS GIS Cut Line= 6
     2302435.067     6967870.107     2302329.395     6968301.809
     2302319.294     6968405.873     2302282.154     6968788.533
      2302170.46      6968904.18     2301217.949     6969892.715
#Sta/Elev= 30
    1059   574.7    1198   564.6    1267   561.7    1393   562.1    1510   558.1
    1550     536    1563   532.5    1610     531    1625     531    1639   537.4
    1661   552.3    1682   554.6    1705   563.8    1725   563.8    1779     559
    1984   556.9    2404   561.4    2582   558.8    2628   562.5    2771   566.4
    3059   564.4    3142   567.8    3248   578.5    3281   578.5    3328   585.3
    3358   592.2    3383   591.5    3432   598.5    3491   601.9    3525   607.8
#Mann= 3 ,0,0
    1059     .09       0    1510    .055       0    1705     .09       0
Bank Sta=1510,1705
XS Rating Curve= 0 ,0
Exp/Cntr=0.3,0.1

Type RM Length L Ch R = 1 ,297741  ,12,12,12
BEGIN DESCRIPTION:
This cross section corresponds to cross section 297613.5 of the non-georeferenced CDC model which was the source of this model.
One-foot upstream of channel dam.
END DESCRIPTION:
XS GIS Cut Line= 6
     2302390.048     6967859.061     2302365.237     6967967.576
     2302290.968     6968292.407     2302280.749     6968397.699
     2302238.872     6968830.834     2301202.719     6969889.758
#Sta/Elev= 30
    1059   574.7    1198   564.6    1267   561.7    1393   562.1    1510   558.1
    1550     536    1563   532.5    1610     531    1625     531    1639   537.4
    1661   552.3    1682   554.6    1705   563.8    1725   563.8    1779     559
    1984   556.9    2404   561.4    2582   558.8    2628   562.5    2771   566.4
    3059   564.4    3142   567.8    3248   578.5    3281   578.5    3328   585.3
    3358   592.2    3383   591.5    3432   598.5    3491   601.9    3525   607.8
#Mann= 3 ,0,0
    1059     .09       0    1510     .04       0    1705     .09       0
Bank Sta=1510,1705
XS Rating Curve= 0 ,0
Exp/Cntr=0.3,0.1

Type RM Length L Ch R = 5 ,297734  ,,,
BEGIN DESCRIPTION:
channel dam
crest elevation 537.4
END DESCRIPTION:
Node Name=channel dam
IW Pilot Flow=0
#Inline Weir SE= 2
    1200   537.4    2000   537.4
IW Dist,WD,Coef,Skew,MaxSub,Min_El,Is_Ogee,SpillHt,DesHd
1,10,3,0,0.95,, 0 ,,,2,2,
Inline Weir Flap Gates= 0
IW Outlet Rating Curve= 0 ,False,,

Type RM Length L Ch R = 1 ,297729  ,51,51,51
BEGIN DESCRIPTION:
This cross section corresponds to cross section 297601.5 of the non-georeferenced CDC model which was the source of this model.
One-foot downstream of channel dam.
**********************************************
Fort Worth Floodway limit.
END DESCRIPTION:
XS GIS Cut Line= 6
     2302353.868     6967963.117     2302279.514     6968288.317
     2302269.331     6968393.232     2302269.295     6968393.608
     2302227.418     6968826.743     2301236.769     6969839.163
#Sta/Elev= 30
    1200   569.8    1288   567.6    1363     561    1492   559.4    1532   556.9
    1601   530.2    1615     529    1640   532.1    1681   533.5    1698   540.8
    1746   556.8    1778   557.3    1786   558.7    1983   556.6    2207   560.3
    2404   561.4    2548   560.4    2582   558.8    2628   562.5    2771   566.4
    3059   564.4    3142   567.8    3227   575.4    3248   578.5    3281   578.5
    3328   585.3    3358   592.2    3383   591.5    3432   598.5    3491   601.9
#Mann= 3 ,0,0
    1200     .09       0    1532    .035       0    1746     .09       0
Bank Sta=1532,1746
XS Rating Curve= 0 ,0
Exp/Cntr=0.3,0.1