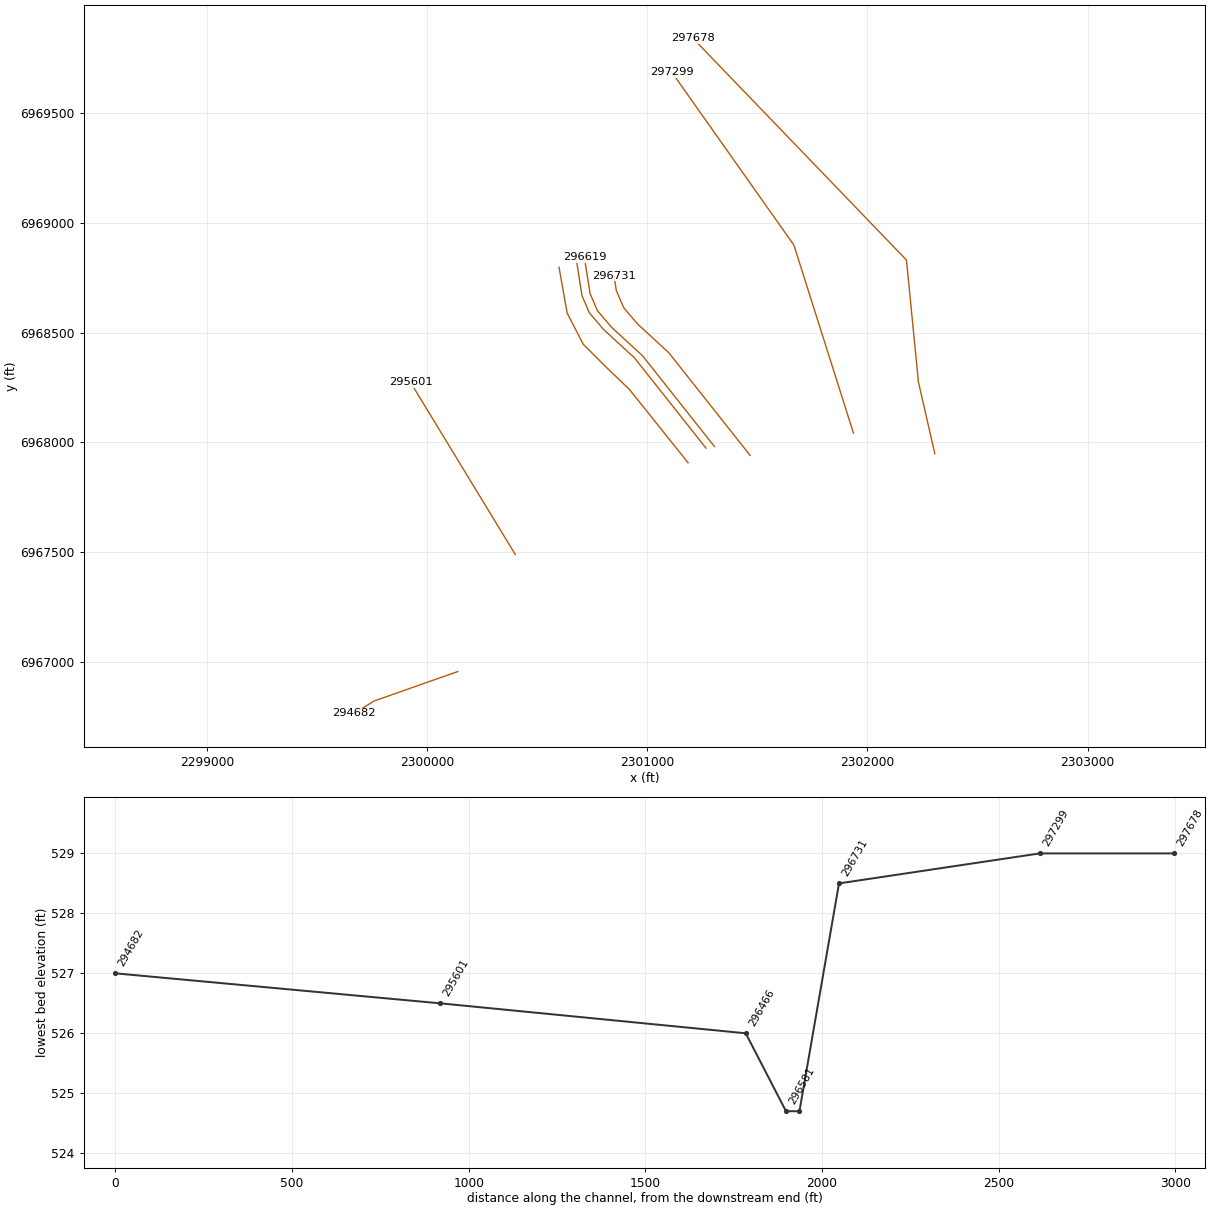
HEC-RAS study CDC_Consolidated_Model.prj: Upper Trinity CDC Consolidated Model

--- CDC_Consolidated_Model.g03 (geometry) --- (continued)

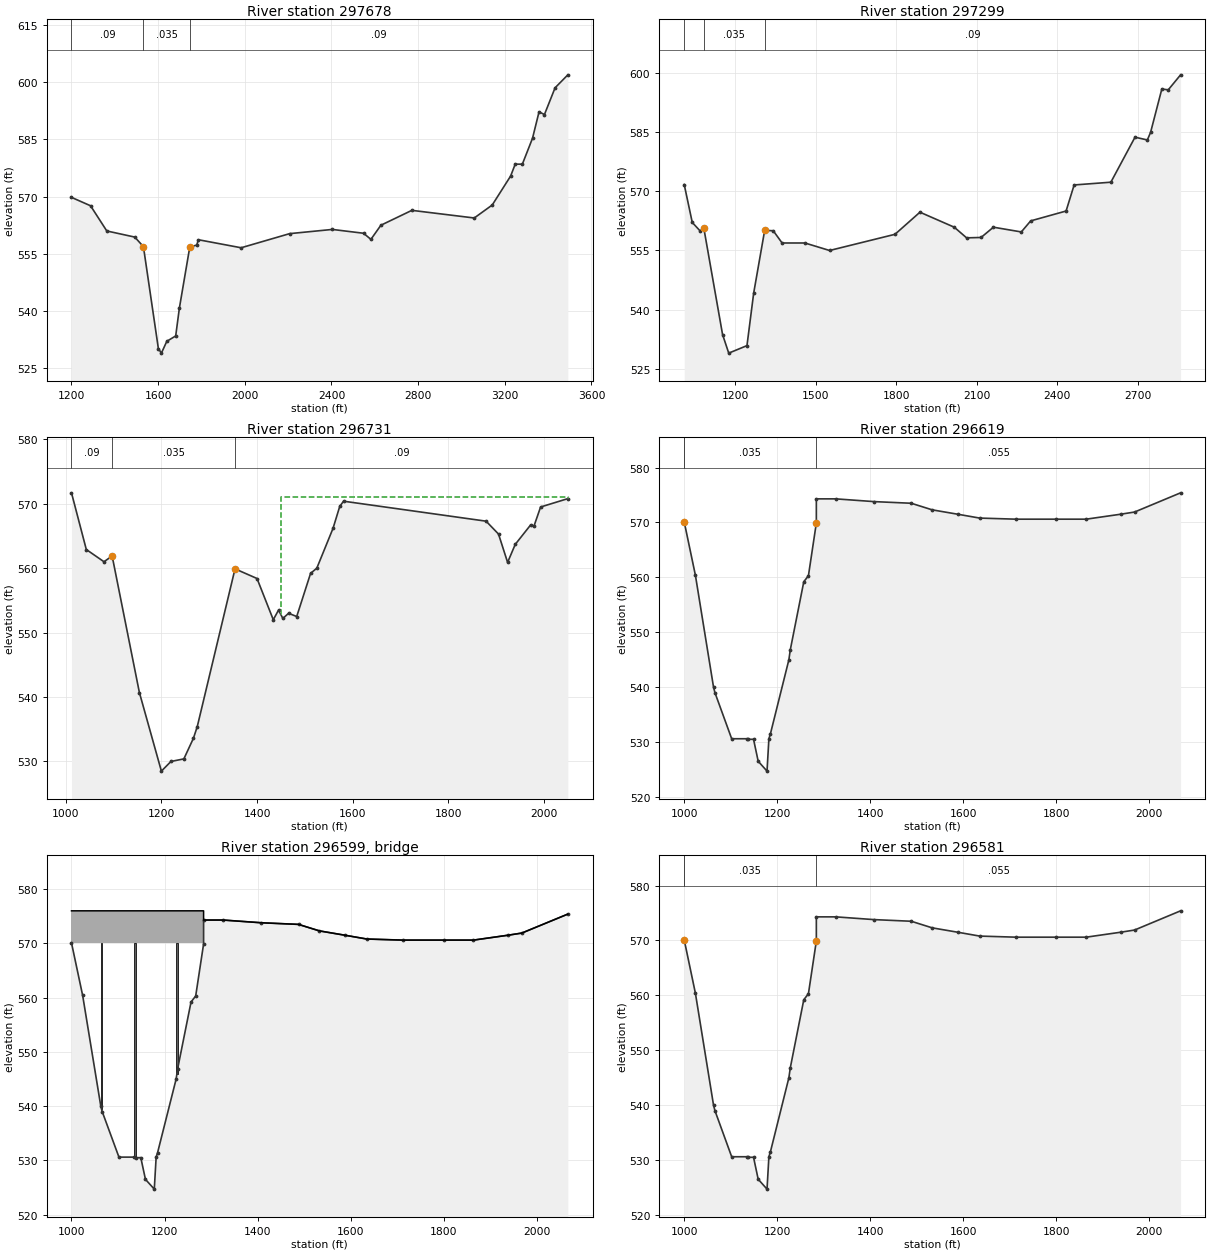
Type RM Length L Ch R = 1 ,297678  ,379,379,421
BEGIN DESCRIPTION:
This cross section corresponds to cross section 297551.5 of the non-georeferenced CDC model which was the source of this model.
51 feet downstream of channel dam.  Effective flow
limit set at sta 1200 in LOB at Anahuac Street.
Channel data from 1975 USACE field survey.
END DESCRIPTION:
XS GIS Cut Line= 5
     2302305.986     6967948.672      2302231.34     6968275.151
     2302221.284      6968378.76     2302177.049     6968829.464
     2301207.155     6969837.865
#Sta/Elev= 30
    1200   569.8    1288   567.6    1363     561    1492   559.4    1532   556.9
    1601   530.2    1615     529    1640   532.1    1681   533.5    1698   540.8
    1746   556.8    1778   557.3    1786   558.7    1983   556.6    2207   560.3
    2404   561.4    2548   560.4    2582   558.8    2628   562.5    2771   566.4
    3059   564.4    3142   567.8    3227   575.4    3248   578.5    3281   578.5
    3328   585.3    3358   592.2    3383   591.5    3432   598.5    3491   601.9
#Mann= 3 ,0,0
    1200     .09       0    1532    .035       0    1746     .09       0
Bank Sta=1532,1746
XS Rating Curve= 0 ,0
Exp/Cntr=0.3,0.1

Type RM Length L Ch R = 1 ,297299  ,568,568,655
BEGIN DESCRIPTION:
This cross section corresponds to cross section 297175.5 of the non-georeferenced CDC model which was the source of this model.
Cross-section WF363.  Effective flow limit set at Carswell Levee in LOB.
Channel data from 1975 USACE field survey.
END DESCRIPTION:
XS GIS Cut Line= 4
     2301936.412     6968042.098      2301876.71     6968230.633
     2301665.451     6968897.763     2301110.855     6969684.026
#Sta/Elev= 30
    1009   571.7    1039   562.1    1069   559.9    1082   560.7    1152   533.7
    1175     529    1243   530.9    1268   544.2    1309   560.1    1341     560
    1374   556.9    1459   556.9    1551     555    1795   559.1    1888   564.7
    2016   560.9    2062   558.2    2116   558.3    2162   560.9    2266   559.7
    2301   562.5    2433     565    2463   571.6    2600   572.3    2690   583.7
    2736     583    2748   584.9    2790   595.9    2814   595.7    2860   599.5
#Mann= 3 ,0,0
    1009     .09       0    1082    .035       0    1309     .09       0
Bank Sta=1082,1309
XS Rating Curve= 0 ,0
Exp/Cntr=0.3,0.1

Type RM Length L Ch R = 1 ,296731  ,112,112,112
BEGIN DESCRIPTION:
This cross section corresponds to cross section 296618.5 of the non-georeferenced CDC model which was the source of this model.
120 feet upstream of Meandering Road.  Effective flow
limit set at Carswell Levee in LOB.  Ineffective flow at sta 1450 due to roadway embankment.
Channel data from 1975 USACE field survey.
END DESCRIPTION:
XS GIS Cut Line= 6
     2301466.989     6967940.811     2301097.386     6968407.791
     2300955.614     6968538.369      2300892.19     6968612.986
     2300858.612     6968691.333     2300848.185     6968758.063
#Sta/Elev= 30
    1012   571.7    1043   562.9    1080     561    1097   561.9    1154   540.7
    1200   528.5    1220     530    1247   530.4    1267   533.6    1275   535.4
    1354   559.9    1400   558.4    1434     552    1445   553.5    1454   552.2
    1466     553    1483   552.5    1512   559.2    1525     560    1559   566.2
    1573   569.6    1581   570.4    1879   567.3    1905   565.3    1924   560.9
    1940   563.7    1972   566.7    1979   566.5    1993   569.5    2050   570.8
#Mann= 3 ,0,0
    1012     .09       0    1097    .035       0    1354     .09       0
#XS Ineff= 2 , 0
       0                    1450       0     571
Permanent Ineff=
       F       F
Bank Sta=1097,1354
XS Rating Curve= 0 ,0
Exp/Cntr=0.5,0.3

Type RM Length L Ch R = 1 ,296619  ,38,38,38
BEGIN DESCRIPTION:
This cross section corresponds to cross section 296499.5 of the non-georeferenced CDC model which was the source of this model.
One-foot upstream of Meandering Road.  Duplication of previous bridge cross-section without bridge piers.  Effective flow limit set at Carswell Levee in LOB.
END DESCRIPTION:
XS GIS Cut Line= 6
     2301304.799      6967981.27     2300978.253      6968393.85
     2300836.481     6968524.428     2300773.057     6968599.045
      2300739.48     6968677.392     2300713.865     6968841.321
#Sta/Elev= 30
    1000   570.1    1024   560.4    1063     540    1066     539    1102   530.6
    1135   530.6    1138   530.5    1149   530.5    1159   526.5    1178   524.7
    1182   530.6    1185   531.4    1225     545    1228   546.8    1257   559.2
    1267   560.3    1284   569.9    1284   574.3    1326   574.3    1408   573.8
    1488   573.5    1533   572.3    1588   571.5    1635   570.8    1713   570.6
    1800   570.6    1864   570.6    1938   571.5    1968   571.9    2067   575.4
#Mann= 3 ,0,0
    1000    .055       0    1000    .035       0    1284    .055       0
Bank Sta=1000,1284
XS Rating Curve= 0 ,0
Exp/Cntr=0.5,0.3

Type RM Length L Ch R = 3 ,296599  ,,,
BEGIN DESCRIPTION:
Meandering Road
Downstream face of bridge.  Bridge data from 1975 USACE field survey, bridge plans.  Minimum low chord elev. 570.1, bridge length 284 feet, bridge width 37 feet, three 3-foot diameter piers across bridge length.  Top of roadway points in ROB from cross-section WF361.  Effective flow limit set at WFL1 Levee in LOB.  Design levee elev. 572.0.
Channel data from 1975 USACE field survey.
END DESCRIPTION:
Node Name=Meandering Road
Bridge Culvert--1,0,-1,-1, 0
Deck Dist Width WeirC Skew NumUp NumDn MinLoCord MaxHiCord MaxSubmerge Is_Ogee
0.5,37,2.6,0, 16, 16, , , 0.95, 0, ,,,
    1000    1284    1284    1284    1326    1408    1488    1533    1588    1635
    1713    1800    1864    1938    1968    2067
     576     576     576   574.3   574.3   573.8   573.5   572.3   571.5   570.8
   570.6   570.6   570.6   571.5   571.9   575.4
   570.1   570.1   570.1   574.3   574.3   573.8   573.5   572.3   571.5   570.8
   570.6   570.6   570.6   571.5   571.9   575.4
    1000    1284    1284    1284    1326    1408    1488    1533    1588    1635
    1713    1800    1864    1938    1968    2067
     576     576     576   574.3   574.3   573.8   573.5   572.3   571.5   570.8
   570.6   570.6   570.6   571.5   571.9   575.4
   570.1   570.1   570.1   574.3   574.3   573.8   573.5   572.3   571.5   570.8
   570.6   570.6   570.6   571.5   571.9   575.4
Pier Skew, UpSta & Num, DnSta & Num=  ,1064.5, 2 ,1064.5, 2 , 0 , 0 , 0 ,,
       3       3
     500     571
       3       3
     500     571
Pier Skew, UpSta & Num, DnSta & Num=  ,1136.5, 2 ,1136.5, 2 , 0 , 0 , 0 ,,
       3       3
     500     571
       3       3
     500     571
Pier Skew, UpSta & Num, DnSta & Num=  ,1226.5, 2 ,1226.5, 2 , 0 , 0 , 0 ,,
       3       3
     500     571
       3       3
     500     571
BR Coef= 1 , 0 , 0 ,1.05, 0 ,,,0.8,-1,0.5,1,
WSPro=,,,, 1 ,,,, 0 ,,,, 0 ,,,,-1 ,-1 ,-1 , 0 , 0 , 0 , 0 , 0
BC Design=,, 0 ,, 0 ,,,,,,
BC HTab HWMax=575.4
BC Use User HTab Curves=0
BC User HTab FreeFlow(D)= 0

Type RM Length L Ch R = 1 ,296581  ,114,114,114
BEGIN DESCRIPTION:
This cross section corresponds to cross section 296460.5 of the non-georeferenced CDC model which was the source of this model.
One-foot downstream of Meandering Road. Duplication of following bridge cross-section without bridge piers.  Effective flow limit set at Carswell Levee in LOB.
END DESCRIPTION:
XS GIS Cut Line= 6
     2301266.115     6967974.204     2300941.499     6968384.344
     2300799.727     6968514.922     2300736.303     6968589.539
     2300702.726     6968667.886     2300676.631     6968834.889
#Sta/Elev= 30
    1000   570.1    1024   560.4    1063     540    1066     539    1102   530.6
    1135   530.6    1138   530.5    1149   530.5    1159   526.5    1178   524.7
    1182   530.6    1185   531.4    1225     545    1228   546.8    1257   559.2
    1267   560.3    1284   569.9    1284   574.3    1326   574.3    1408   573.8
    1488   573.5    1533   572.3    1588   571.5    1635   570.8    1713   570.6
    1800   570.6    1864   570.6    1938   571.5    1968   571.9    2067   575.4
#Mann= 3 ,0,0
    1000    .055       0    1000    .035       0    1284    .055       0
Bank Sta=1000,1284
XS Rating Curve= 0 ,0
Exp/Cntr=0.5,0.3

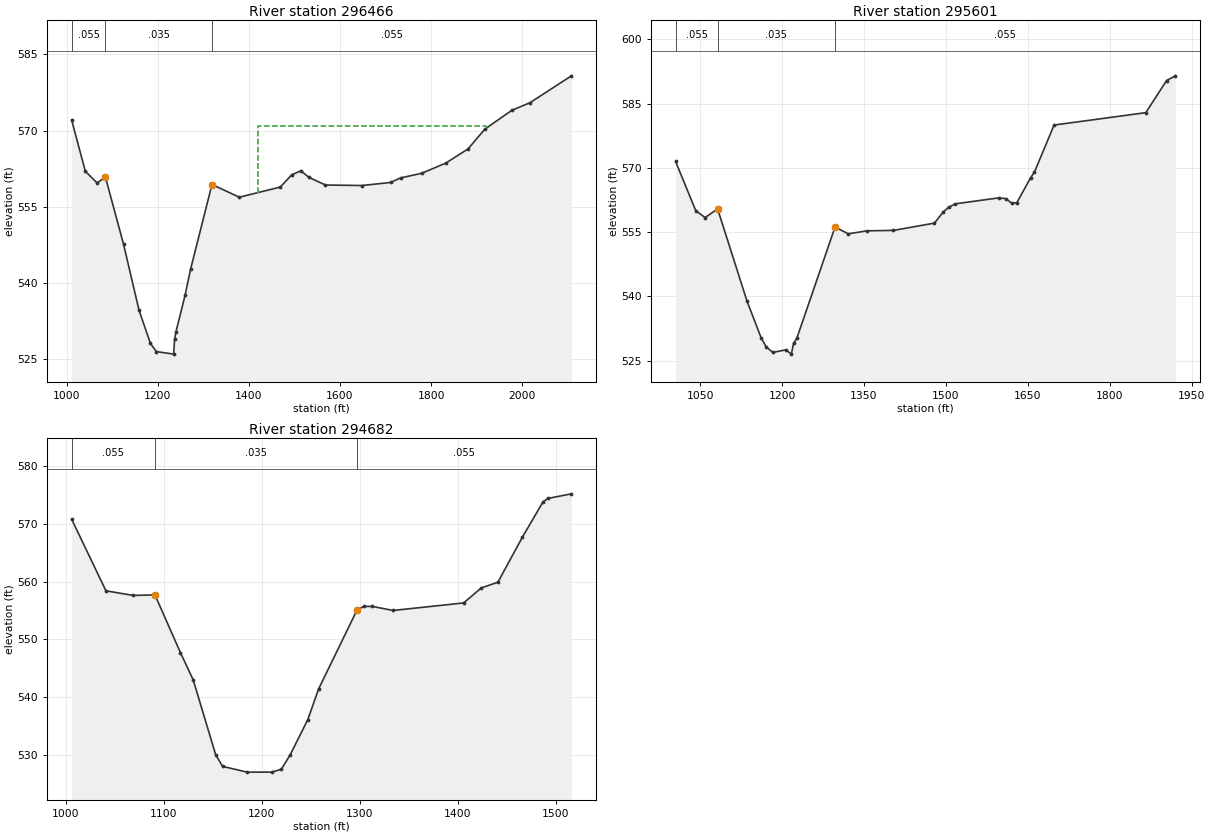
Type RM Length L Ch R = 1 ,296466  ,865,865,852
BEGIN DESCRIPTION:
This cross section corresponds to cross section 296345.5 of the non-georeferenced CDC model which was the source of this model.
116 feet downstream of Meandering Road.  Effective flow
limit set at Carswell Levee in LOB.  Ineffective flow at sta 1420 due to roadway embankment.
Channel data from 1975 USACE field survey.
END DESCRIPTION:
XS GIS Cut Line= 6
     2301184.889     6967907.494     2300918.498     6968240.931
     2300811.273     6968343.867     2300708.336     6968446.804
     2300635.423     6968588.341     2300598.521     6968796.471
#Sta/Elev= 30
    1011   572.1    1041     562    1067   559.7    1085   560.9    1125   547.6
    1159   534.6    1184   528.1    1197   526.5    1235     526    1237     529
    1240   530.4    1260   537.6    1272   542.7    1319   559.4    1379   556.9
    1469   558.9    1494   561.3    1514   562.1    1532   560.8    1568   559.3
    1648   559.2    1711   559.8    1733   560.7    1779   561.6    1832   563.6
    1881   566.4    1918   570.3    1977     574    2017   575.5    2108   580.8
#Mann= 3 ,0,0
    1011    .055       0    1085    .035       0    1319    .055       0
#XS Ineff= 1 ,-1
    1420    1920     571
Permanent Ineff=
       F
Bank Sta=1085,1319
XS Rating Curve= 0 ,0
Exp/Cntr=0.3,0.1

Type RM Length L Ch R = 1 ,295601  ,919,919,1313
BEGIN DESCRIPTION:
This cross section corresponds to cross section 295478.5 of the non-georeferenced CDC model which was the source of this model.
Effective flow limit set at Carswell Levee in LOB, at sta
1920 in ROB.
Channel data from 1975 USACE field survey.
END DESCRIPTION:
XS GIS Cut Line= 3
     2300399.909     6967490.113     2300303.815     6967648.198
     2299924.114     6968272.849
#Sta/Elev= 30
    1005   571.5    1042     560    1059   558.4    1082   560.4    1136   538.8
    1162   530.2    1171   528.2    1183   526.9    1207   527.5    1217   526.5
    1221     529    1227   530.2    1297   556.2    1321   554.6    1356   555.3
    1404   555.4    1479   557.1    1495   559.7    1505   560.8    1517   561.6
    1597     563    1610   562.8    1621   561.7    1630   561.9    1655   567.7
    1662     569    1698     580    1866   582.9    1904   590.4    1920   591.5
#Mann= 3 ,0,0
    1005    .055       0    1082    .035       0    1297    .055       0
Bank Sta=1082,1297
XS Rating Curve= 0 ,0
Exp/Cntr=0.3,0.1

Type RM Length L Ch R = 1 ,294682  ,982,982,1013
BEGIN DESCRIPTION:
This cross section corresponds to cross section 294548.5 of the non-georeferenced CDC model which was the source of this model.
Effective flow limit set at Carswell Levee in LOB.
Channel data from 1975 USACE field survey.
END DESCRIPTION:
XS GIS Cut Line= 4
2300138.573786646966957.96129063      2299957.83     6966894.331
     2299757.997     6966823.9812299667.497280816966767.78419799
#Sta/Elev= 25
    1006   570.8    1041   558.4    1069   557.6    1091   557.7    1117   547.7
    1130     543    1153     530    1160     528    1185     527    1210     527
    1220   527.5    1229     530    1247   536.1    1258   541.4    1297     555
    1304   555.7    1313   555.7    1334     555    1406   556.3    1424   558.9
    1441   559.9    1466   567.7    1487   573.8    1492   574.4    1516   575.2
#Mann= 3 ,0,0
    1006    .055       0    1091    .035       0    1297    .055       0
Bank Sta=1091,1297
XS Rating Curve= 0 ,0
Exp/Cntr=0.3,0.1