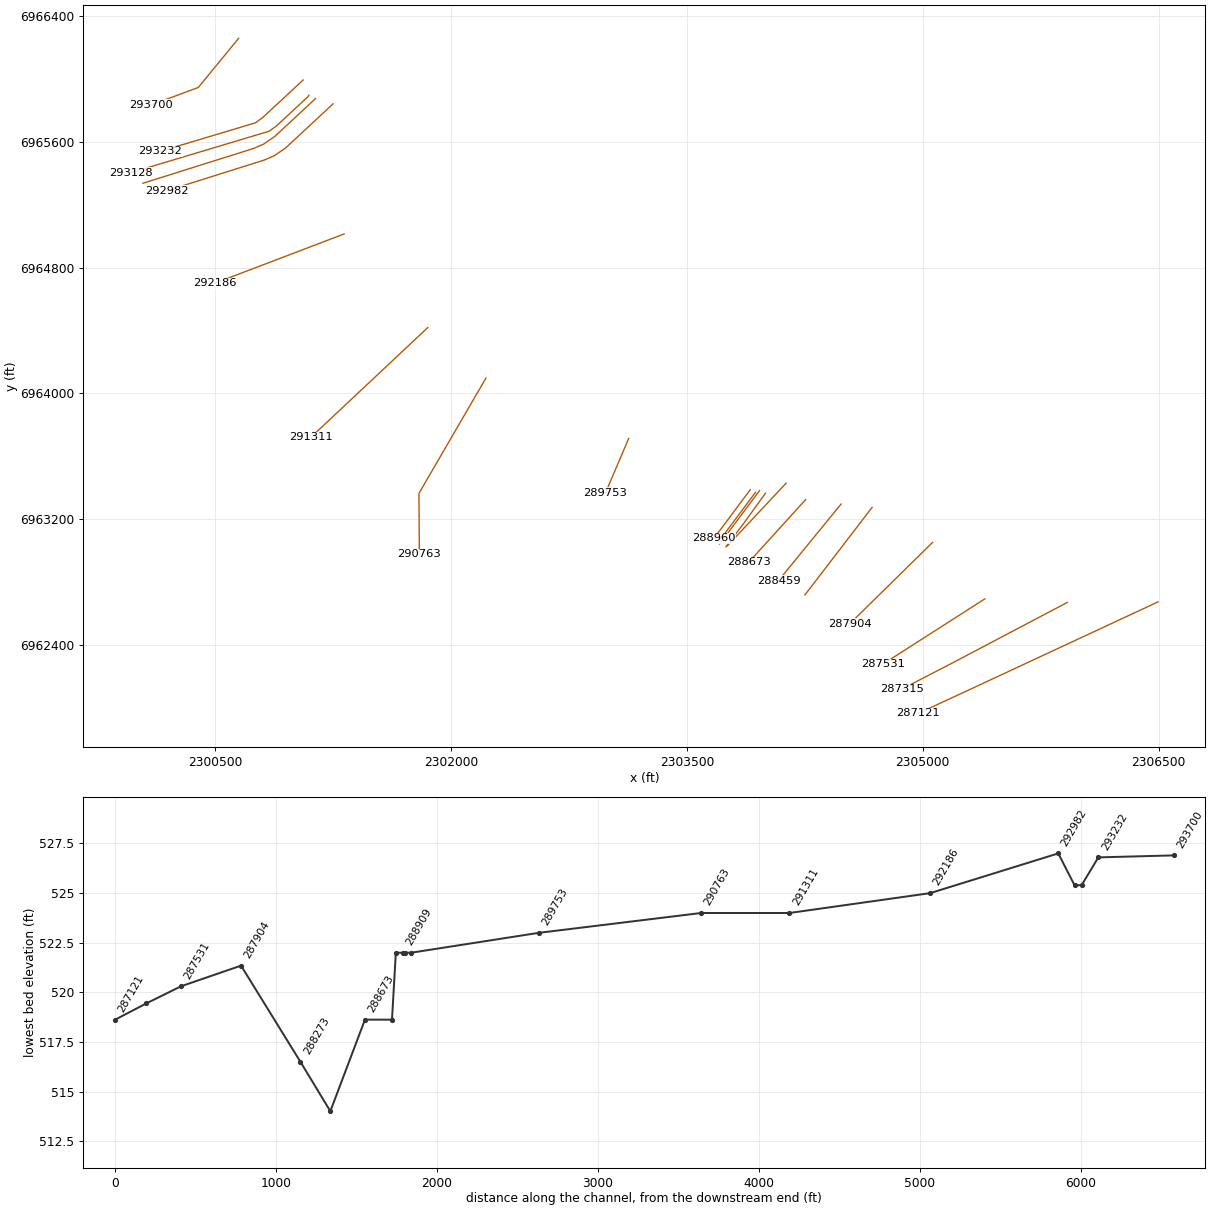
HEC-RAS study CDC_Consolidated_Model.prj: Upper Trinity CDC Consolidated Model

--- CDC_Consolidated_Model.g03 (geometry) --- (continued)

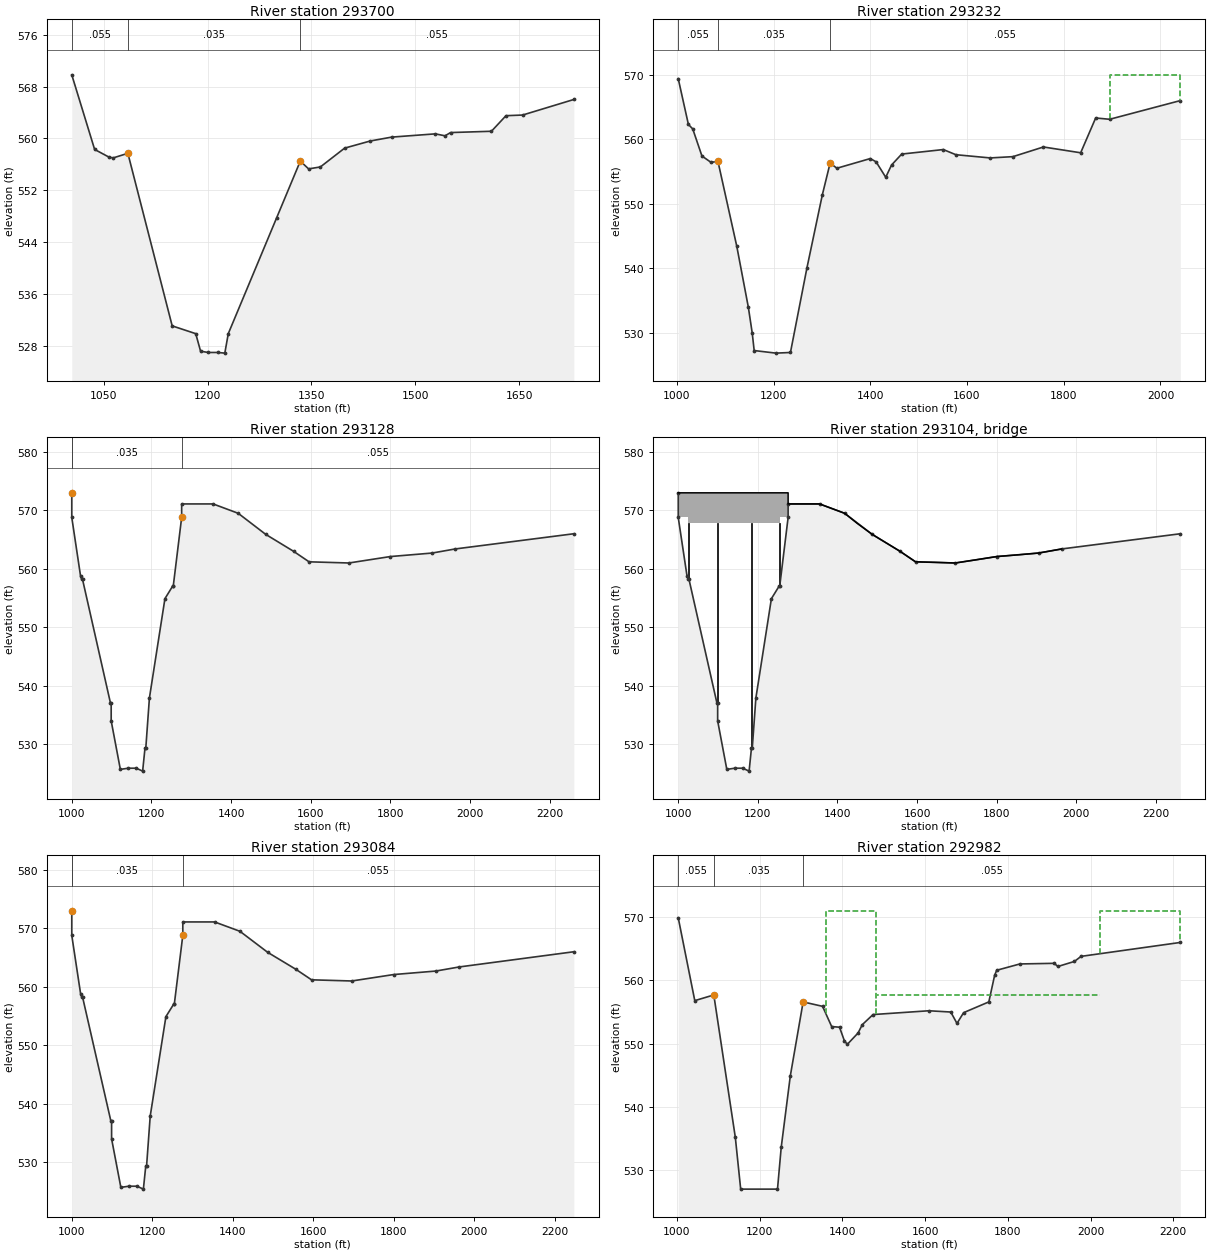
Type RM Length L Ch R = 1 ,293700  ,468,468,468
BEGIN DESCRIPTION:
This cross section corresponds to cross section 293564.5 of the non-georeferenced CDC model which was the source of this model.
Effective flow limit set at Carswell Levee in LOB.
Channel data from 1975 USACE field survey.
END DESCRIPTION:
XS GIS Cut Line= 5
2300649.329720086966259.80393081     2300513.385     6966093.981
     2300392.876     6965946.987     2300159.852     6965860.339
2300092.474830846965835.28537053
#Sta/Elev= 26
    1004   569.8    1037   558.3    1058   557.1    1064     557    1085   557.7
    1149   531.1    1183   529.9    1190   527.2    1201     527    1215     527
    1225   526.9    1230   529.9    1300   547.8    1334   556.5    1346   555.3
    1363   555.6    1398   558.5    1435   559.6    1466   560.2    1529   560.7
    1543   560.4    1551   560.9    1610   561.1    1631   563.5    1655   563.6
    1729     566
#Mann= 3 ,0,0
    1004    .055       0    1085    .035       0    1334    .055       0
#XS Ineff= 2 , 0
       0                    1655       0
Permanent Ineff=
       F       F
Bank Sta=1085,1334
XS Rating Curve= 0 ,0
Exp/Cntr=0.3,0.1

Type RM Length L Ch R = 1 ,293232  ,104,104,104
BEGIN DESCRIPTION:
This cross section corresponds to cross section 293097.5 of the non-georeferenced CDC model which was the source of this model.
103 feet upstream of Carswell Access Road.  Effective
flow limit set at Carswell Levee in LOB.
Channel data from 1975 USACE field survey.
END DESCRIPTION:
XS GIS Cut Line= 6
     2301059.263     6965994.327     2300907.618     6965853.233
      2300803.52     6965756.377      2300756.62     6965721.984
     2300290.017     6965581.8772300150.184767526965539.88954043
#Sta/Elev= 30
    1003   569.4    1024   562.3    1033   561.6    1052   557.4    1071   556.4
    1085   556.6    1124   543.4    1148   533.9    1156   529.9    1160   527.2
    1205   526.8    1235   526.9    1269     540    1301   551.4    1317   556.3
    1331   555.5    1400     557    1412   556.5    1432   554.1    1444     556
    1465   557.7    1551   558.4    1577   557.6    1648   557.1    1695   557.3
    1758   558.8    1835   557.9    1866   563.3    1895   563.1    2041     566
#Mann= 3 ,0,0
    1003    .055       0    1085    .035       0    1317    .055       0
#XS Ineff= 2 ,-1
    1895    2041     570    1551    1895   558.4
Permanent Ineff=
       F       F
Bank Sta=1085,1317
XS Rating Curve= 0 ,0
Exp/Cntr=0.5,0.3

Type RM Length L Ch R = 1 ,293128  ,44,44,44
BEGIN DESCRIPTION:
This cross section corresponds to cross section 292995.5 of the non-georeferenced CDC model which was the source of this model.
One-foot upstream of Carswell Access Road.  Duplication of previous bridge cross-section without bridge piers.  Effective flow limit set at Carswell Levee in LOB.
END DESCRIPTION:
XS GIS Cut Line= 6
      2301096.12      6965897.99     2301088.485      6965886.76
     2300891.095     6965703.103     2300844.195      6965668.71
     2300610.893     6965598.6572299963.399976236965404.23368051
#Sta/Elev= 30
    1000     573    1000   568.8    1022   558.8    1025   558.2    1027   558.2
    1097   537.1    1099   537.1    1099     534    1122   525.7    1142   525.9
    1162   525.9    1178   525.4    1184   529.4    1186   529.4    1195   537.9
    1234   554.9    1253     557    1255   557.1    1276   568.8    1276   571.1
    1355   571.1    1418   569.5    1487   565.9    1557     563    1596   561.2
    1696     561    1800   562.1    1905   562.7    1963   563.4    2261     566
#Mann= 3 ,0,0
    1000    .055       0    1000    .035       0    1276    .055       0
#XS Ineff= 2 , 0
       0                    1963       0
Permanent Ineff=
       F       F
Bank Sta=1000,1276
XS Rating Curve= 0 ,0
Exp/Cntr=0.5,0.3

Type RM Length L Ch R = 3 ,293104  ,,,
BEGIN DESCRIPTION:
Carswell Access Road
Bridge data from 1975 USACE field survey, bridge
plans.  Minimum low chord elev. 567.9, bridge length 276 feet, bridge width 40 feet.  Four 2-foot diameter bridge piers across bridge length.  Effective flow limit set at WFL1 Levee in LOB.  Top of roadway points in ROB from cross-section WF355.  Design levee elev. 569.5.
END DESCRIPTION:
Node Name=Carswell Access
Bridge Culvert--1,0,-1,-1, 0
Deck Dist Width WeirC Skew NumUp NumDn MinLoCord MaxHiCord MaxSubmerge Is_Ogee
1,40,2.6,0, 21, 21, , , 0.95, 0, ,,,
    1000    1025    1025    1255    1255    1276    1276    1323    1355    1418
    1449    1487    1557    1596    1650    1696    1744    1800    1855    1905
    1963
     573     573     573     573     573     573   571.1   571.1   571.1   569.5
   567.8   565.9     563   561.2   561.1     561   561.5   562.1   562.4   562.7
   563.4
   568.8   568.8   567.8   567.8   568.8   568.8   571.1   571.1   571.1   569.5
   567.8   565.9     563   561.2   561.1     561   561.5   562.1   562.4   562.7
   563.4
    1000    1025    1025    1255    1255    1276    1276    1323    1355    1418
    1449    1487    1557    1596    1650    1696    1744    1800    1855    1905
    1963
     573     573     573     573     573     573   571.1   571.1   571.1   569.5
   567.8   565.9     563   561.2   561.1     561   561.5   562.1   562.4   562.7
   563.4
   568.8   568.8   567.8   567.8   568.8   568.8   571.1   571.1   571.1   569.5
   567.8   565.9     563   561.2   561.1     561   561.5   562.1   562.4   562.7
   563.4
Pier Skew, UpSta & Num, DnSta & Num=  ,1026, 2 ,1026, 2 , 0 , 0 , 0 ,,
       2       2
     500     568
       2       2
     500     568
Pier Skew, UpSta & Num, DnSta & Num=  ,1098, 2 ,1098, 2 , 0 , 0 , 0 ,,
       2       2
     500     568
       2       2
     500     568
Pier Skew, UpSta & Num, DnSta & Num=  ,1185, 2 ,1185, 2 , 0 , 0 , 0 ,,
       2       2
     500     568
       2       2
     500     568
Pier Skew, UpSta & Num, DnSta & Num=  ,1254, 2 ,1254, 2 , 0 , 0 , 0 ,,
       2       2
     500     568
       2       2
     500     568
BR Coef= 1 , 0 , 0 ,1.05, 0 ,,,0.8,-1,0.5,1,
WSPro=,,,, 1 ,,,, 0 ,,,, 0 ,,,,-1 ,-1 ,-1 , 0 , 0 , 0 , 0 , 0
BC Design=,, 0 ,, 0 ,,,,,,
BC HTab HWMax=573
BC Use User HTab Curves=0
BC User HTab FreeFlow(D)= 0

Type RM Length L Ch R = 1 ,293084  ,101,101,101
BEGIN DESCRIPTION:
This cross section corresponds to cross section 292953.5 of the non-georeferenced CDC model which was the source of this model.
One-foot downstream of Carswell Access Road.  Duplication of following bridge cross-section without bridge piers.  Effective flow limit set at Carswell Levee in LOB.
END DESCRIPTION:
XS GIS Cut Line= 6
      2301137.66      6965876.71     2301122.092     6965861.152
     2300880.208     6965636.231     2300808.294     6965586.204
     2300742.633     6965558.0642300039.977345866965336.86115396
#Sta/Elev= 30
    1000     573    1000   568.8    1022   558.8    1025   558.2    1027   558.2
    1097   537.1    1099   537.1    1099     534    1122   525.7    1142   525.9
    1162   525.9    1178   525.4    1184   529.4    1186   529.4    1195   537.9
    1234   554.9    1253     557    1255   557.1    1276   568.8    1276   571.1
    1355   571.1    1418   569.5    1487   565.9    1557     563    1596   561.2
    1696     561    1800   562.1    1905   562.7    1963   563.4    2248     566
#Mann= 3 ,0,0
    1000    .055       0    1000    .035       0    1276    .055       0
#XS Ineff= 2 , 0
       0                    1963       0
Permanent Ineff=
       F       F
Bank Sta=1000,1276
XS Rating Curve= 0 ,0
Exp/Cntr=0.5,0.3

Type RM Length L Ch R = 1 ,292982  ,796,796,731
BEGIN DESCRIPTION:
This cross section corresponds to cross section 292852.5 of the non-georeferenced CDC model which was the source of this model.
102 feet downstream of Carswell Access Road.  Effective
flow limit set at Carswell Levee in LOB.  Ineffective flow from sta 1360 - 1480 elev. set at 571.0 due to road embankment.
Channel data from 1975 USACE field survey.
END DESCRIPTION:
XS GIS Cut Line= 6
     2301249.989     6965842.581     2301103.334     6965706.212
     2300948.808     6965562.522     2300876.894     6965512.495
     2300811.233     6965484.3552300194.428022576965290.17824788
#Sta/Elev= 30
    1003   569.9    1043   556.8    1089   557.7    1141   535.2    1154     527
    1243     527    1252   533.6    1274   544.9    1305   556.6    1352   555.9
    1374   552.7    1393   552.6    1405   550.4    1412   549.9    1438   551.7
    1448     553    1474   554.6    1609   555.2    1662     555    1677   553.2
    1693   554.9    1754   556.6    1768   560.8    1773   561.6    1829   562.6
    1912   562.7    1921   562.2    1961     563    1977   563.8    2217     566
#Mann= 3 ,0,0
    1003    .055       0    1089    .035       0    1305    .055       0
#XS Ineff= 3 ,-1
    1360    1480     571    2023    2217     571    1480    2023  557.69
Permanent Ineff=
       F       F       F
Bank Sta=1089,1305
XS Rating Curve= 0 ,0
Exp/Cntr=0.3,0.1

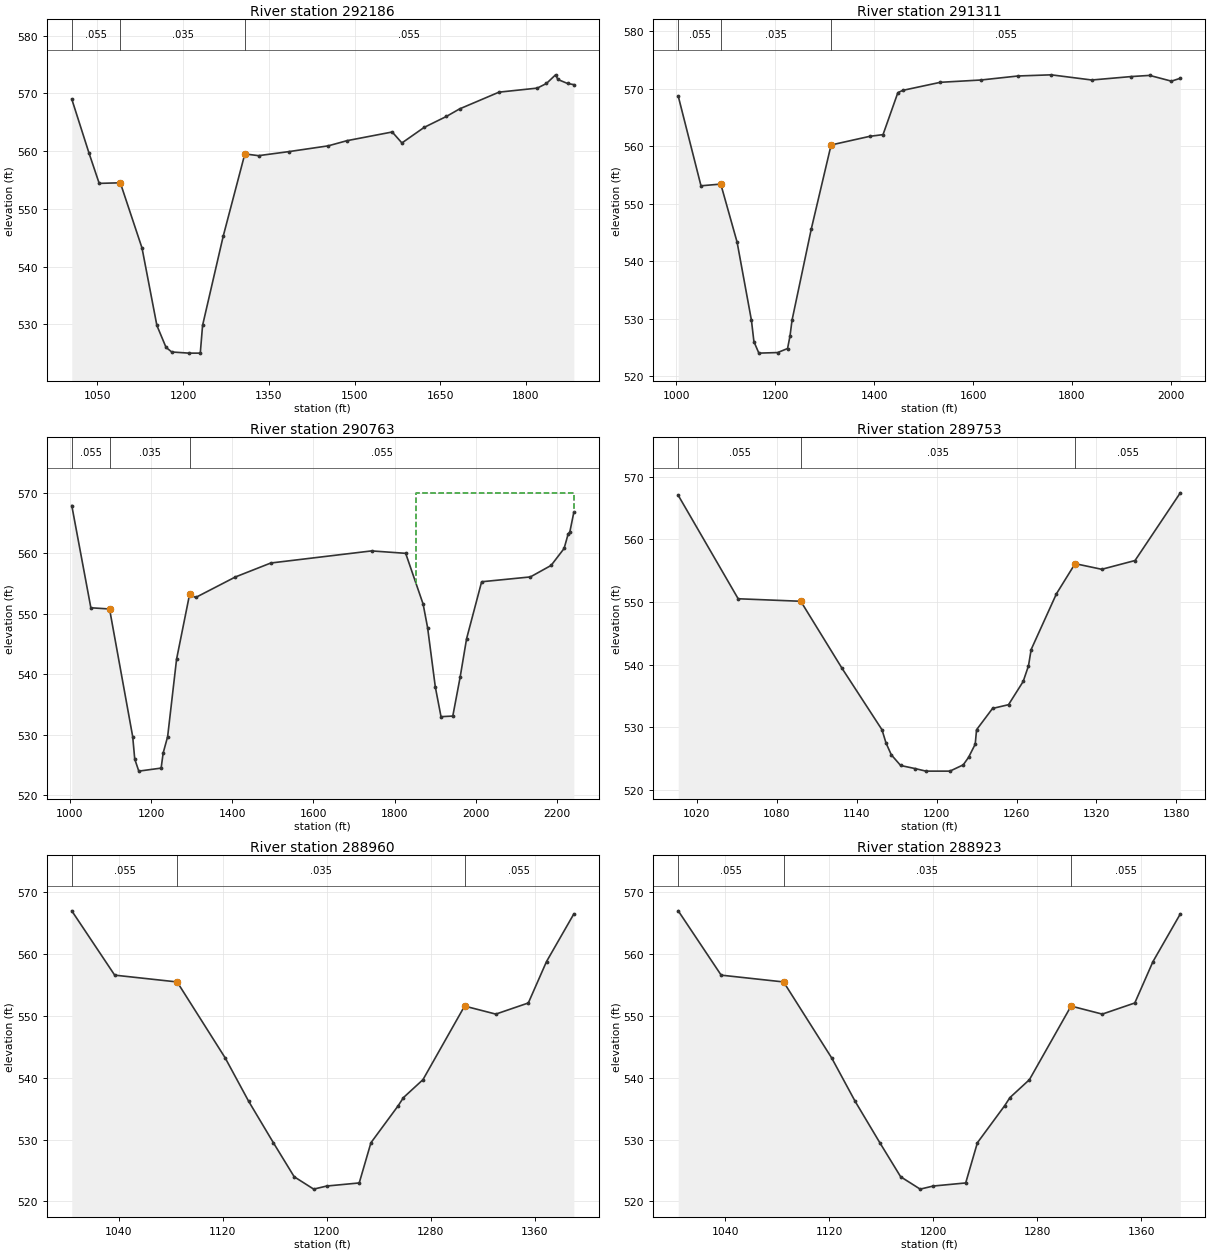
Type RM Length L Ch R = 1 ,292186  ,875,875,949
BEGIN DESCRIPTION:
This cross section corresponds to cross section 292064.5 of the non-georeferenced CDC model which was the source of this model.
Effective flow limit set at Carswell Levee in LOB.
Channel data from 1975 USACE field survey.
END DESCRIPTION:
XS GIS Cut Line= 3
  2301320.2450296965014.29684106     2301140.896     6964945.868
2300498.989974756964700.95814911
#Sta/Elev= 29
    1005     569    1035   559.7    1053   554.4    1090   554.5    1128   543.2
    1154   529.8    1170     526    1180   525.2    1210     525    1230     525
    1234   529.8    1270   545.2    1308   559.5    1332   559.2    1385   559.9
    1454   560.9    1487   561.8    1566   563.3    1583   561.4    1622   564.1
    1661     566    1684   567.3    1753   570.2    1820   570.9    1836   571.7
    1852   573.2    1856   572.4    1873   571.7    1884   571.5
#Mann= 3 ,0,0
    1005    .055       0    1090    .035       0    1308    .055       0
Bank Sta=1090,1308
XS Rating Curve= 0 ,0
Exp/Cntr=0.3,0.1

Type RM Length L Ch R = 1 ,291311  ,548,548,621
BEGIN DESCRIPTION:
This cross section corresponds to cross section 291187.5 of the non-georeferenced CDC model which was the source of this model.
Effective flow limit set at Carswell Levee in LOB.
Channel data from 1975 USACE field survey.
END DESCRIPTION:
XS GIS Cut Line= 3
       2301852.2     6964418.148     2301710.609     6964285.086
      2301109.47     6963720.161
#Sta/Elev= 26
    1004   568.7    1050   553.1    1090   553.4    1123   543.3    1152   529.7
    1157     526    1167     524    1205   524.1    1225   524.8    1230     527
    1234   529.7    1273   545.6    1313   560.2    1391   561.7    1418     562
    1448   569.3    1458   569.7    1534   571.1    1616   571.5    1691   572.2
    1758   572.4    1840   571.5    1920   572.1    1957   572.3    2001   571.3
    2019   571.8
#Mann= 3 ,0,0
    1004    .055       0    1090    .035       0    1313    .055       0
Bank Sta=1090,1313
XS Rating Curve= 0 ,0
Exp/Cntr=0.3,0.1

Type RM Length L Ch R = 1 ,290763  ,1010,1010,1040
BEGIN DESCRIPTION:
This cross section corresponds to cross section 290635.5 of the non-georeferenced CDC model which was the source of this model.
Approx. 750 feet upstream of left bank of Farmers
Branch.  Farmers Branch removed from conveyance in ROB.  Effective flow limit set at Carswell Levee in LOB, at sta 1853 in ROB.
Channel data from 1975 USACE field survey.
END DESCRIPTION:
XS GIS Cut Line= 4
2302221.692046326964095.97491718     2302120.595     6963921.728
     2301795.799     6963361.922 2301798.75178716962974.59017749
#Sta/Elev= 30
    1005   567.9    1052     551    1098   550.8    1155   529.7    1160     526
    1170     524    1225   524.5    1230     527    1241   529.7    1263   542.5
    1295   553.2    1310   552.7    1408   556.1    1495   558.4    1743   560.4
    1827     560    1870   551.6    1881   547.7    1900   537.9    1914     533
    1943   533.1    1961   539.5    1977   545.9    2014   555.3    2134   556.1
    2185     558    2217   560.8    2227   563.2    2231   563.5    2241   566.8
#Mann= 3 ,0,0
    1005    .055       0    1098    .035       0    1295    .055       0
#XS Ineff= 2 , 0
       0                    1853       0     570
Permanent Ineff=
       F       F
#Block Obstruct= 2 , 0
                            1825           555.3
Bank Sta=1098,1295
XS Rating Curve= 0 ,0
Exp/Cntr=0.3,0.1

Type RM Length L Ch R = 1 ,289753  ,792,792,753
BEGIN DESCRIPTION:
This cross section corresponds to cross section 289624.5 of the non-georeferenced CDC model which was the source of this model.
Approx. 100 feet downstream of right bank of Farmers
Branch.  Effective flow limit set at Carswell Levee in LOB, at White Settlement Levee in ROB.
Channel data from 1975 USACE field survey.
END DESCRIPTION:
XS GIS Cut Line= 3
      2303129.77     6963712.175     2303053.468     6963532.723
     2302982.252     6963365.235
#Sta/Elev= 25
    1006     567    1051   550.5    1098   550.1    1129   539.4    1159   529.6
    1162   527.5    1166   525.6    1173   523.9    1184   523.4    1192     523
    1210     523    1220     524    1224   525.2    1229   527.3    1230   529.6
    1242     533    1254   533.6    1265   537.3    1269   539.8    1271   542.4
    1290   551.3    1304   556.1    1324   555.2    1349   556.6    1383   567.4
#Mann= 3 ,0,0
    1006    .055       0    1098    .035       0    1304    .055       0
Bank Sta=1098,1304
XS Rating Curve= 0 ,0
Exp/Cntr=0.3,0.1

Type RM Length L Ch R = 1 ,288960  ,37,37,37
BEGIN DESCRIPTION:
This cross section corresponds to cross section 288832.5 of the non-georeferenced CDC model which was the source of this model.
38 feet upstream of channel dam.  Effective flow limit
set at Carswell Levee in LOB, at White Settlement Levee in ROB.
Channel data from 1975 USACE field survey.
END DESCRIPTION:
XS GIS Cut Line= 3
2303903.506203756963386.48546854     2303782.296     6963224.028
2303672.678785896963077.10753919
#Sta/Elev= 19
    1004     567    1037   556.6    1085   555.5    1122   543.2    1140   536.2
    1159   529.5    1175     524    1190     522    1200   522.5    1225     523
    1234   529.5    1255   535.5    1259   536.8    1274   539.7    1306   551.6
    1330   550.3    1355   552.1    1369   558.8    1390   566.5
#Mann= 3 ,0,0
    1004    .055       0    1085    .035       0    1306    .055       0
Bank Sta=1085,1306
XS Rating Curve= 0 ,0
Exp/Cntr=0.3,0.1

Type RM Length L Ch R = 1 ,288923  ,14,14,14
BEGIN DESCRIPTION:
This cross section corresponds to cross section 288795.5 of the non-georeferenced CDC model which was the source of this model.
One-foot upstream of channel dam.
END DESCRIPTION:
XS GIS Cut Line= 3
2303936.111200056963368.76347129     2303813.836     6963204.879
2303705.283781646963059.38554236
#Sta/Elev= 19
    1004     567    1037   556.6    1085   555.5    1122   543.2    1140   536.2
    1159   529.5    1175     524    1190     522    1200   522.5    1225     523
    1234   529.5    1255   535.5    1259   536.8    1274   539.7    1306   551.6
    1330   550.3    1355   552.1    1369   558.8    1390   566.5
#Mann= 3 ,0,0
    1004    .055       0    1085    .035       0    1306    .055       0
Bank Sta=1085,1306
XS Rating Curve= 0 ,0
Exp/Cntr=0.3,0.1

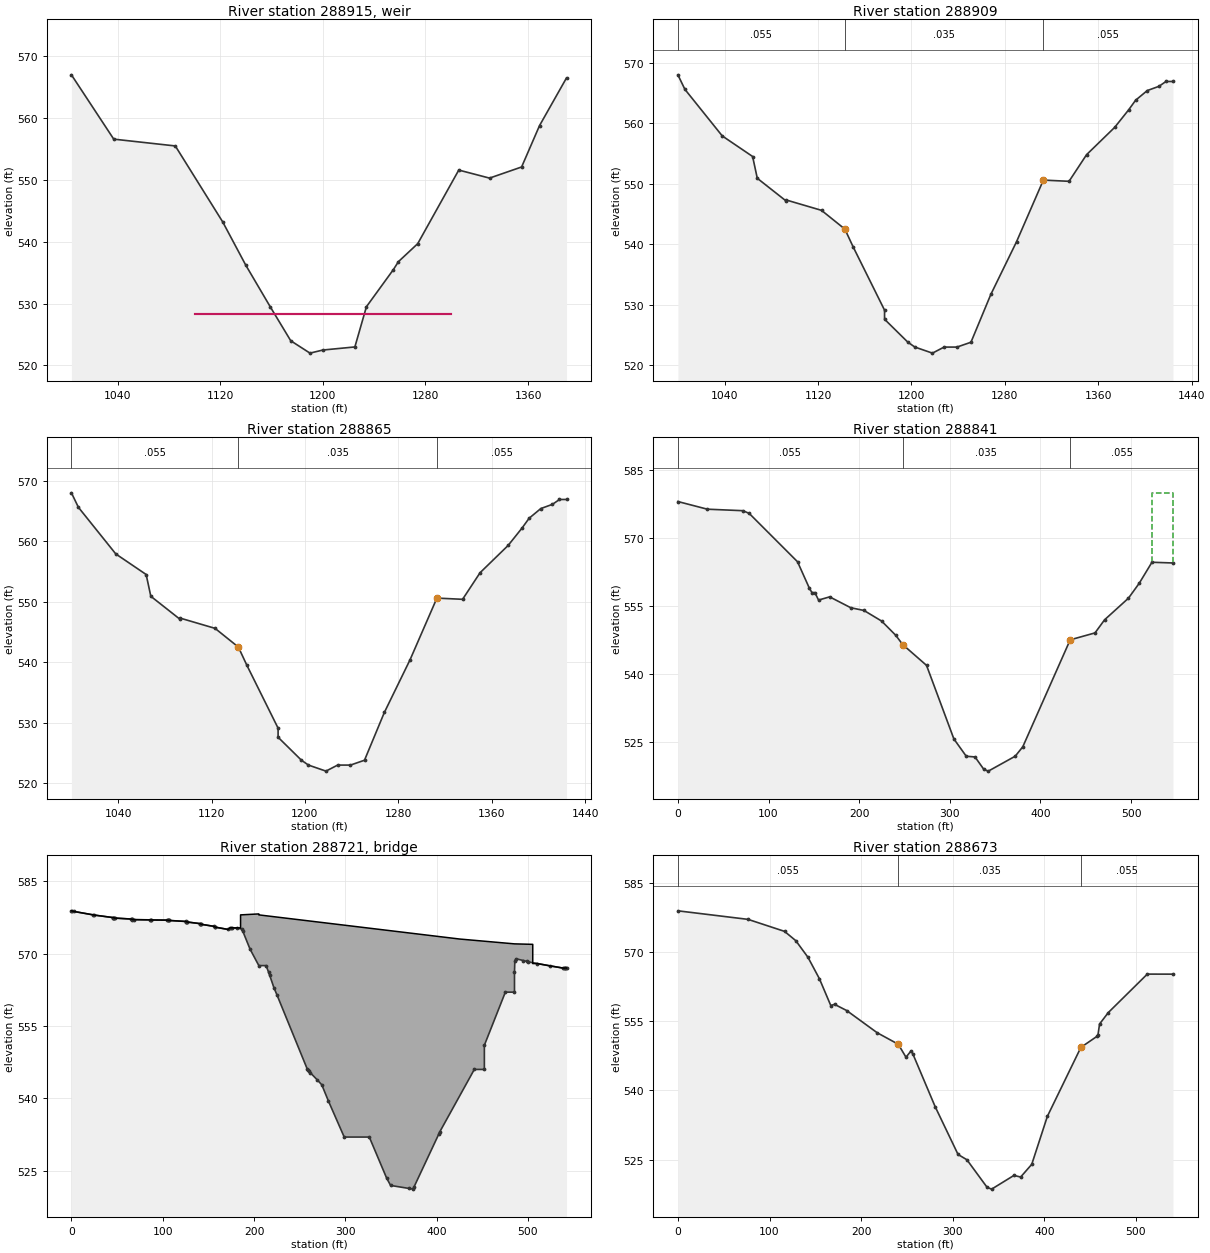
Type RM Length L Ch R = 5 ,288915  ,,,
BEGIN DESCRIPTION:
channel dam
crest elevation 528.4.
END DESCRIPTION:
Node Name=channel dam
IW Pilot Flow=0
#Inline Weir SE= 2
    1100   528.4    1300   528.4
IW Dist,WD,Coef,Skew,MaxSub,Min_El,Is_Ogee,SpillHt,DesHd
1,12,3,0,0.95,, 0 ,,,2,2,
Inline Weir Flap Gates= 0
IW Outlet Rating Curve= 0 ,False,,

Type RM Length L Ch R = 1 ,288909  ,44,44,44
BEGIN DESCRIPTION:
This cross section corresponds to cross section 288781.5 of the non-georeferenced CDC model which was the source of this model.
One-foot downstream of channel dam.
END DESCRIPTION:
XS GIS Cut Line= 4
    2303961.9045    6963380.0574    2303888.1855    6963281.2518
    2303825.5608     6963197.316    2303708.3531    6963040.2225
#Sta/Elev= 30
    1000     568    1006   565.6    1038   557.9    1064   554.5    1068   550.9
    1093   547.1    1093   547.3    1123   545.6    1143   542.5    1150   539.6
    1177   529.1    1177   527.6    1197   523.8    1203     523    1218     522
    1228     523    1239     523    1251   523.8    1268   531.7    1290   540.4
    1313   550.6    1335   550.4    1350   554.8    1374   559.3    1386   562.2
    1392   563.8    1402   565.4    1412   566.1    1418   566.9    1424   566.9
#Mann= 3 ,0,0
    1000    .055       0    1143    .035       0    1313    .055       0
Bank Sta=1143,1313
XS Rating Curve= 0 ,0
Exp/Cntr=0.3,0.1

Type RM Length L Ch R = 1 ,288865  ,24,24,13
BEGIN DESCRIPTION:
This cross section corresponds to cross section 288732.5 of the non-georeferenced CDC model which was the source of this model.
67 feet upstream of S.H. 183 - River Oaks Boulevard,
Effective flow limit set at Carswell Levee in LOB, at White Settlement Levee in ROB.
Channel data from 1975 USACE field survey.
END DESCRIPTION:
XS GIS Cut Line= 3
2304000.167249486963363.850671552303861.014088566963171.40481069
2303748.507277596963022.62935672
#Sta/Elev= 30
    1000     568    1006   565.6    1038   557.9    1064   554.5    1068   550.9
    1093   547.1    1093   547.3    1123   545.6    1143   542.5    1150   539.6
    1177   529.1    1177   527.6    1197   523.8    1203     523    1218     522
    1228     523    1239     523    1251   523.8    1268   531.7    1290   540.4
    1313   550.6    1335   550.4    1350   554.8    1374   559.3    1386   562.2
    1392   563.8    1402   565.4    1412   566.1    1418   566.9    1424   566.9
#Mann= 3 ,0,0
    1000    .055       0    1143    .035       0    1313    .055       0
Bank Sta=1143,1313
XS Rating Curve= 0 ,0
Exp/Cntr=0.5,0.3

Type RM Length L Ch R = 1 ,288841  ,168,168,173
BEGIN DESCRIPTION:
This cross section corresponds to cross section 288719.8 of the non-georeferenced CDC model which was the source of this model.
Upstream of SH 183/River Oaks Boulevard.
Effective flow limit set at White Settlement Levee in ROB.
Upstream end of mapping for the Central City project.  The CDC Model (with modifications) is used upstream of this point. NOTE: All river stationing  of the CDC Model from this point upstream reduced 646.42 feet.
END DESCRIPTION:
XS GIS Cut Line= 3
2304130.985338816963427.23497933 2303788.4266977 6963061.5343656
2303757.616630396963028.64288617
#Sta/Elev= 30
       0  578.08   32.51  576.39   71.78  576.06   78.68  575.46  131.98   564.8
  145.11  558.94  147.89     558  151.11     558  155.18  556.35  167.43  557.06
  190.72  554.66  205.26  554.06  224.76  551.72  240.35  548.58  247.99  546.54
   274.3  541.95  304.46  525.73  318.12  521.91  327.77  521.76  337.57     519
  342.46  518.63  372.12  521.92  380.49     524  432.76  547.58  460.14  549.11
  470.71     552  497.01  556.76  508.97  560.07  522.97  564.69  546.15  564.53
#Mann= 3 ,-1,0
       0    .055       0  247.99    .035       0  432.76    .055       0
#XS Ineff= 2 , 0
       0                  522.97       0     580
Permanent Ineff=
       F       T
Bank Sta=247.99,432.76
XS Rating Curve= 0 ,0
Exp/Cntr=0.5,0.3

Type RM Length L Ch R = 3 ,288721  ,,,
BEGIN DESCRIPTION:
SH 183/River Oaks Boulevard
Double bridges - bridge width set at 95 feet.
Data from bridge plans.
Note:  Internal bridge cross-sections modified to represent geometry under bridge.
END DESCRIPTION:
Node Name=SH 183/River Oak
Bridge Culvert--1,0,-1,-1, 0
Deck Dist Width WeirC Skew NumUp NumDn MinLoCord MaxHiCord MaxSubmerge Is_Ogee
39.1,95,2.6,0, 55, 55, , , 0.95, 0, 0,0,,
       0      .3    2.46    23.9   24.28   45.64   46.04   46.42    46.8   47.26
   65.53   65.98   66.43   66.88   68.21    86.2   86.62   87.03  105.14  105.55
  105.94  106.37  106.78  124.99  125.41  125.82  126.22  126.62  140.84  141.26
  141.68  142.21  156.35   156.9  157.48  171.47  173.78  185.24  185.24  205.24
  205.24  425.24  425.24  485.24  485.24  505.24  505.24  510.24  524.63  538.67
  539.46  540.22  540.97  541.69   542.2
  578.84  578.84  578.72     578  577.98  577.44  577.42   577.4  577.38  577.34
  577.14  577.11  577.08  577.04  577.02  576.97  576.96  576.95  576.91   576.9
  576.88  576.87  576.85  576.64  576.62  576.59  576.57  576.53  576.19  576.16
  576.12  576.05  575.62  575.54  575.46  574.99  575.32  575.31     578   578.2
     578     573     573     572     572   571.9  567.92  567.92  567.43  566.98
  566.99     567     567     567  566.99
                                                                     450     450
     570  566.09   566.5  566.09     450     450
       0      .3    2.46    23.9   24.28   45.64   46.04   46.42    46.8   47.26
   65.53   65.98   66.43   66.88   68.21    86.2   86.62   87.03  105.14  105.55
  105.94  106.37  106.78  124.99  125.41  125.82  126.22  126.62  140.84  141.26
  141.68  142.21  156.35   156.9  157.48  171.47  173.78  185.24  185.24  205.24
  205.24  425.24  425.24  485.24  485.24  505.24  505.24  510.24  524.63  538.67
  539.46  540.22  540.97  541.69   542.2
  578.84  578.84  578.72     578  577.98  577.44  577.42   577.4  577.38  577.34
  577.14  577.11  577.08  577.04  577.02  576.97  576.96  576.95  576.91   576.9
  576.88  576.87  576.85  576.64  576.62  576.59  576.57  576.53  576.19  576.16
  576.12  576.05  575.62  575.54  575.46  574.99  575.32  575.31     578   578.2
     578     573     573     572     572   571.9  567.92  567.92  567.43  566.98
  566.99     567     567     567  566.99
                                                                     450     450
     570  566.09   566.5  566.09     450     450
Pier Skew, UpSta & Num, DnSta & Num=  ,315.24, 2 ,315.24, 2 , 0 , 0 , 0 ,,
     3.5     3.5
     450     575
     3.5     3.5
     450     575
Pier Skew, UpSta & Num, DnSta & Num=  ,425.24, 2 ,425.24, 2 , 0 , 0 , 0 ,,
     3.5     3.5
     450     575
     3.5     3.5
     450     575
BR Coef=-1 , 0 , 0 ,, 0 ,,,0.8,-1,,0,
WSPro=,,,, 1 ,,,, 0 ,,,, 0 ,,,,-1 ,-1 ,-1 , 0 , 0 , 0 , 0 , 0
BR U #Sta/Elev= 84
       0  578.84      .3  578.84    2.46  578.72    23.9     578   24.28  577.98
   45.64  577.44   46.04  577.42   46.42   577.4    46.8  577.38   47.26  577.34
   65.53  577.14   65.98  577.11   66.43  577.08   66.88  577.04   68.21  577.02
    86.2  576.97   86.62  576.96   87.03  576.95  105.14  576.91  105.55   576.9
  105.94  576.88  106.37  576.87  106.78  576.85  124.99  576.64  125.41  576.62
  125.82  576.59  126.22  576.57  126.62  576.53  140.84  576.19  141.26  576.16
  141.68  576.12  142.21  576.05  156.35  575.62   156.9  575.54  157.48  575.46
  171.47  574.99  173.78  575.32  174.62  575.31  176.33  575.31  181.59  575.24
  186.66  575.09   187.7  574.61  195.64   570.9  205.24   567.5  213.24   567.5
  215.93  566.12     217  565.56  221.78  562.91  224.97  561.49  258.27  546.08
  258.75  545.89  259.91  545.64  261.48  545.34  269.02  543.88  274.18  542.82
   281.5  539.44  298.75     532  326.23     532  345.35  523.44  349.59  521.98
  369.69  521.36   374.1  521.22  375.29   521.7  402.36  532.62  403.13  532.98
  441.24     546  452.24     546  452.24     551  475.24     562  485.24     562
  485.24  566.09  485.62  568.45  486.86  568.91  494.96  568.55  498.49  568.36
  500.27  568.27  510.34  567.92  524.63  567.43  538.67  566.98  539.46  566.99
  540.22     567  540.97     567  541.69     567   542.2  566.99
BR U #Mann= 3
       0    .055  258.75    .035  441.24    .055
BR U Banks=258.75,441.24
BR D #Sta/Elev= 84
       0  578.84      .3  578.84    2.46  578.72    23.9     578   24.28  577.98
   45.64  577.44   46.04  577.42   46.42   577.4    46.8  577.38   47.26  577.34
   65.53  577.14   65.98  577.11   66.43  577.08   66.88  577.04   68.21  577.02
    86.2  576.97   86.62  576.96   87.03  576.95  105.14  576.91  105.55   576.9
  105.94  576.88  106.37  576.87  106.78  576.85  124.99  576.64  125.41  576.62
  125.82  576.59  126.22  576.57  126.62  576.53  140.84  576.19  141.26  576.16
  141.68  576.12  142.21  576.05  156.35  575.62   156.9  575.54  157.48  575.46
  171.47  574.99  173.78  575.32  174.62  575.31  176.33  575.31  181.59  575.24
  186.66  575.09   187.7  574.61  195.64   570.9  205.24   567.5  213.24   567.5
  215.93  566.12     217  565.56  221.78  562.91  224.97  561.49  258.27  546.08
  258.75  545.89  259.91  545.64  261.48  545.34  269.02  543.88  274.18  542.82
   281.5  539.44  298.75     532  326.23     532  345.35  523.44  349.59  521.98
  369.69  521.36   374.1  521.22  375.29   521.7  402.36  532.62  403.13  532.98
  441.24     546  452.24     546  452.24     551  475.24     562  485.24     562
  485.24  566.09  485.62  568.45  486.86  568.91  494.96  568.55  498.49  568.36
  500.27  568.27  510.34  567.92  524.63  567.43  538.67  566.98  539.46  566.99
  540.22     567  540.97     567  541.69     567   542.2  566.99
BR D #Mann= 3
       0    .055  258.75    .035  441.24    .055
BR D Banks=258.75,441.24
BC Design=,, 0 ,, 0 ,,,,,,
BC Use User HTab Curves=0
BC User HTab FreeFlow(D)= 0

Type RM Length L Ch R = 1 ,288673  ,215,215,234
BEGIN DESCRIPTION:
This cross section corresponds to cross section 288551.7 of the non-georeferenced CDC model which was the source of this model.
Downstream of SH 183/River Oaks Boulevard.
Effective flow limit set at White Settlement Levee in ROB.
END DESCRIPTION:
XS GIS Cut Line= 2
 2304255.2214118 6963322.8946522 2303892.0812083 6962922.7360424
#Sta/Elev= 30
       0  578.93   76.57  577.08  116.39  574.48  128.71  572.46  141.95  568.87
  154.44  564.23  166.88  558.41  170.98  558.67   184.2  557.33  217.56  552.51
  240.55  550.02  248.96  547.21  254.54  548.59  256.31     548  280.73  536.53
   305.8  526.14  315.47  524.99  337.57     519  342.46  518.63  366.79   521.6
  374.11  521.25  386.23     524  403.26  534.39  439.85  549.34  457.63  551.76
  458.48     552  460.26  554.41  469.72  556.87  512.36  565.22  540.37  565.21
#Mann= 3 ,-1,0
       0    .055       0  240.55    .035       0  439.85    .055       0
Bank Sta=240.55,439.85
XS Rating Curve= 0 ,0
Exp/Cntr=0.5,0.3

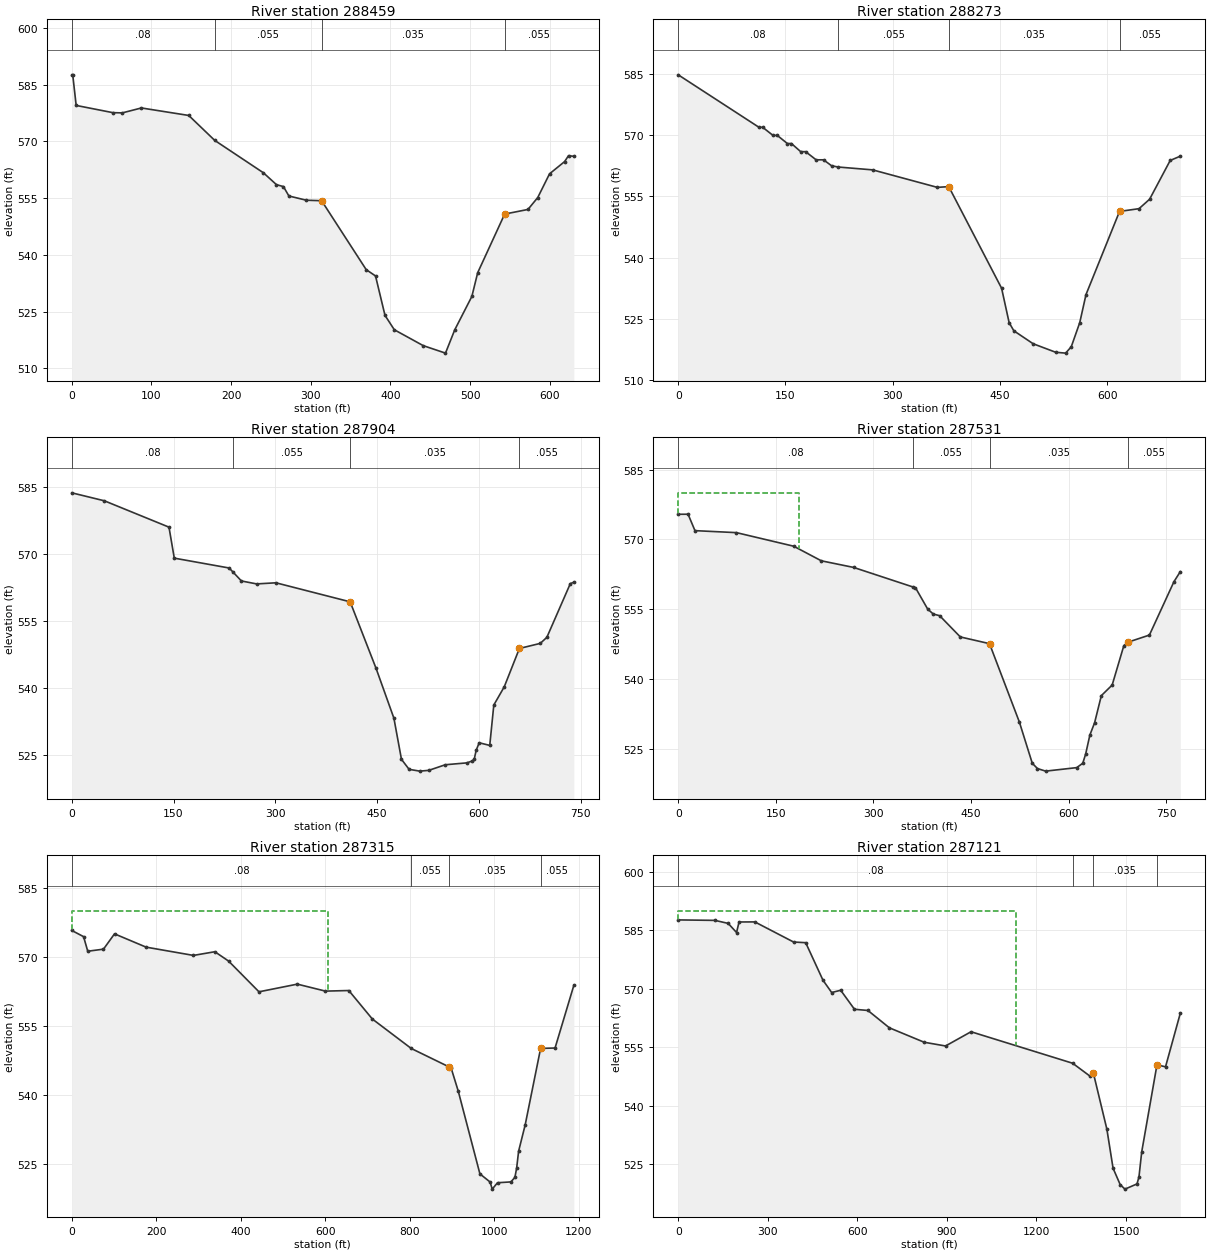
Type RM Length L Ch R = 1 ,288459  ,186,186,194
BEGIN DESCRIPTION:
This cross section corresponds to cross section 288337.2 of the non-georeferenced CDC model which was the source of this model.
Effective flow limit set at White Settlement Levee in ROB.
END DESCRIPTION:
XS GIS Cut Line= 2
 2304480.6710547 6963294.6922511 2304082.2109568 6962806.3833127
#Sta/Elev= 30
       0  587.59    1.24  587.53    5.53   579.5   51.57  577.59   63.41  577.53
   87.42  578.83  146.84  576.85  179.43  570.26  240.58  561.69  256.92  558.56
  265.73  558.04  272.54  555.56  294.49  554.44  313.62  554.31   369.6  536.09
   381.3  534.42  393.19     524  404.88   520.2  441.19     516  469.13  514.02
  480.77  520.19  502.23  529.01  509.55  535.28  543.41  550.78  572.66     552
  584.97  555.16  599.74  561.42  618.68  564.66  623.56  566.22  630.25  566.04
#Mann= 4 ,-1,0
       0     .08       0  179.43    .055       0  313.62    .035       0
  543.41    .055       0
Bank Sta=313.62,543.41
XS Rating Curve= 0 ,0
Exp/Cntr=0.3,0.1

Type RM Length L Ch R = 1 ,288273  ,369,369,324
BEGIN DESCRIPTION:
This cross section corresponds to cross section 288151.3 of the non-georeferenced CDC model which was the source of this model.
Effective flow limit set at White Settlement Levee in ROB.
END DESCRIPTION:
XS GIS Cut Line= 2
 2304677.7014128 6963273.1524449 2304250.5066218 6962715.8575046
#Sta/Elev= 30
       0  584.88  112.85     572  118.05     572  132.49     570   138.5     570
  152.66     568  158.34     568   171.3     566  178.19     566  192.84     564
  203.22     564  214.47  562.54  223.65  562.23   271.9  561.53  362.42  557.23
  378.33  557.42  452.25  532.45  462.78     524  469.35     522  496.42  518.81
  527.94  516.72  541.81  516.51   549.7  518.08  561.54     524   570.3   530.9
  617.19  551.32  644.45     552  659.26  554.32  688.03  563.84  702.19   564.9
#Mann= 4 ,-1,0
       0     .08       0  223.65    .055       0  378.33    .035       0
  617.19    .055       0
Bank Sta=378.33,617.19
XS Rating Curve= 0 ,0
Exp/Cntr=0.3,0.1

Type RM Length L Ch R = 1 ,287904  ,373,373,311
BEGIN DESCRIPTION:
This cross section corresponds to cross section 287782.6 of the non-georeferenced CDC model which was the source of this model.
Effective flow limit set at White Settlement Levee in ROB.
END DESCRIPTION:
XS GIS Cut Line= 2
  2305062.221709 6963050.3020359 2304534.9645789 6962531.2405951
#Sta/Elev= 30
       0  583.77   48.07  581.98  143.26  576.07  151.07  569.12   231.9  566.91
  237.43  566.03  250.01     564  272.41  563.34  300.85  563.59  410.26  559.32
  448.48  544.38  474.71  533.22  485.85     524  497.11  521.75  512.75  521.35
  526.02  521.52  550.46  522.78   582.2   523.2  590.36  523.64  593.05     524
  595.93  526.02  600.39  527.71  615.95  527.12  621.94  536.18  637.36  540.27
  659.64  548.86  690.39     550  700.13  551.36  734.66   563.4  739.88  563.72
#Mann= 4 ,-1,0
       0     .08       0  237.43    .055       0  410.26    .035       0
  659.64    .055       0
Bank Sta=410.26,659.64
XS Rating Curve= 0 ,0
Exp/Cntr=0.3,0.1

Type RM Length L Ch R = 1 ,287531  ,215,215,190
BEGIN DESCRIPTION:
This cross section corresponds to cross section 287409.2 of the non-georeferenced CDC model which was the source of this model.
Effective flow limit set at White Settlement Levee in ROB.
END DESCRIPTION:
XS GIS Cut Line= 2
 2305394.7127312 6962690.6743632 2304745.2068237 6962274.4474319
#Sta/Elev= 30
       0   575.4    15.1  575.41   25.71  571.89    89.5  571.46  177.41  568.55
  219.83  565.42  269.49     564  359.95  559.84  364.55  559.64  383.25  555.07
  391.88     554  401.64  553.65  433.41  549.09  478.27  547.65   524.2  530.82
  543.97     522  551.96  520.86  564.52  520.31  612.24  521.06  621.57     522
  626.04     524  632.46  528.05  639.73  530.68  650.09   536.5  666.74  538.78
   684.7  547.24  691.71     548  723.94  549.49  761.69  560.95  771.43   563.1
#Mann= 4 ,-1,0
       0     .08       0  359.95    .055       0  478.27    .035       0
  691.71    .055       0
#XS Ineff= 2 , 0
       0  185.61     580               0
Permanent Ineff=
       F       F
Bank Sta=478.27,691.71
XS Rating Curve= 0 ,0
Exp/Cntr=0.3,0.1

Type RM Length L Ch R = 1 ,287315  ,194,194,182
BEGIN DESCRIPTION:
This cross section corresponds to cross section 287193.9 of the non-georeferenced CDC model which was the source of this model.
Ineffective flow set in LOB.
Effective flow limit set at White Settlement Levee in ROB.
END DESCRIPTION:
XS GIS Cut Line= 3
 2305918.9109324 6962667.9171303 2305205.1786675 6962291.4529037
 2304866.7926345  6962115.888588
#Sta/Elev= 30
       0  575.73   27.95  574.38   37.81  571.21   75.02  571.66  101.17  574.99
  175.86   572.1  287.96   570.3  338.59   571.1  371.22  569.06  443.02  562.38
  533.78  564.05  600.38  562.53  655.62  562.66  711.29  556.46  803.43  550.05
  893.81     546  897.93  545.74  914.64  540.76  965.87  522.77  990.04  520.99
     995  519.45 1007.49  520.84 1039.12  521.02 1048.64     522 1052.76     524
 1057.43   527.7 1072.96  533.42 1109.51  550.07 1143.67  550.15 1188.15  563.79
#Mann= 4 ,-1,0
       0     .08       0  803.43    .055       0  893.81    .035       0
 1109.51    .055       0
#XS Ineff= 1 ,-1
       0  607.31     580
Permanent Ineff=
       F
Bank Sta=893.81,1109.51
XS Rating Curve= 0 ,0
Exp/Cntr=0.3,0.1

Type RM Length L Ch R = 1 ,287121  ,178,178,144
BEGIN DESCRIPTION:
This cross section corresponds to cross section 286999.9 of the non-georeferenced CDC model which was the source of this model.
Ineffective flow set in LOB.
Effective flow limit set at White Settlement Levee in ROB.
END DESCRIPTION:
XS GIS Cut Line= 3
 2306496.1650076  6962671.593912 2305303.4767684 6962115.7078732
 2304971.6146181 6961961.5793942
#Sta/Elev= 30
       0  587.67  122.89  587.55  167.27  586.78  195.35  584.44  203.75  587.14
  256.51  587.16  386.36     582  426.93  581.83  484.83  572.21  513.91  569.05
  544.19  569.63  590.39  564.75  635.36  564.45   707.2     560  823.72   556.3
  895.35  555.34  980.79  558.99  1321.2  550.91 1379.68  547.58 1390.83  548.31
 1435.81     534  1456.5     524 1480.29   519.8 1496.27  518.63 1536.78  519.97
 1543.34  521.79 1552.46  528.17 1603.57   550.5 1632.27     550 1681.78  563.74
#Mann= 4 ,-1,0
       0     .08       0  1321.2    .055       0 1390.83    .035       0
 1603.57    .055       0
#XS Ineff= 1 ,-1
       0 1132.35     590
Permanent Ineff=
       F
Bank Sta=1390.83,1603.57
XS Rating Curve= 0 ,0
Exp/Cntr=0.3,0.1