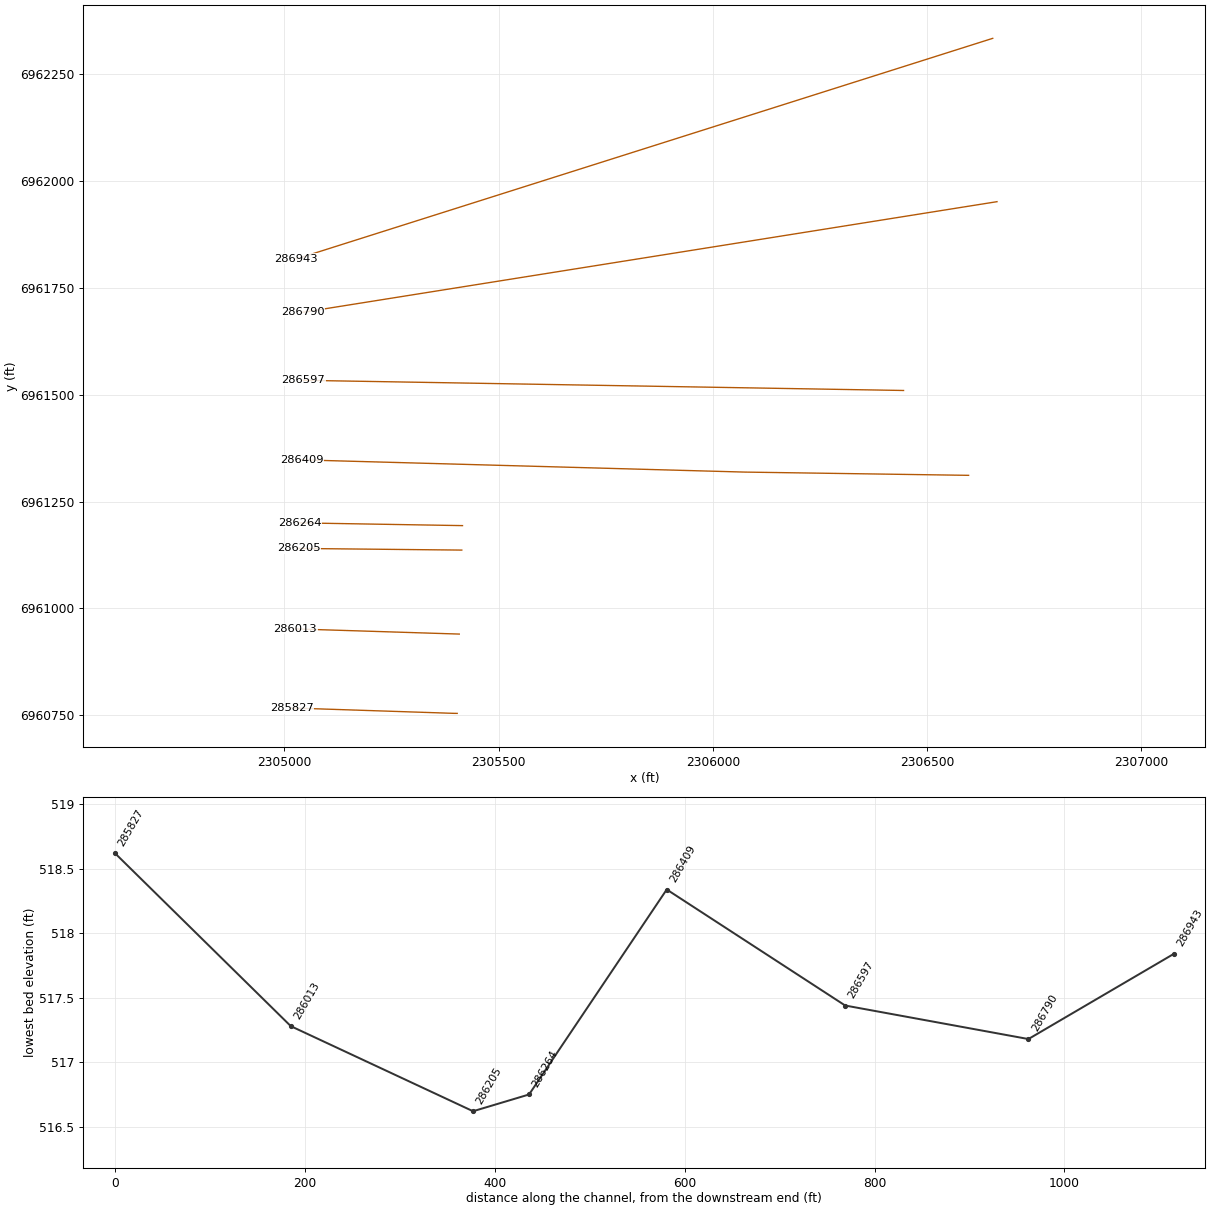
HEC-RAS study CDC_Consolidated_Model.prj: Upper Trinity CDC Consolidated Model

--- CDC_Consolidated_Model.g03 (geometry) --- (continued)

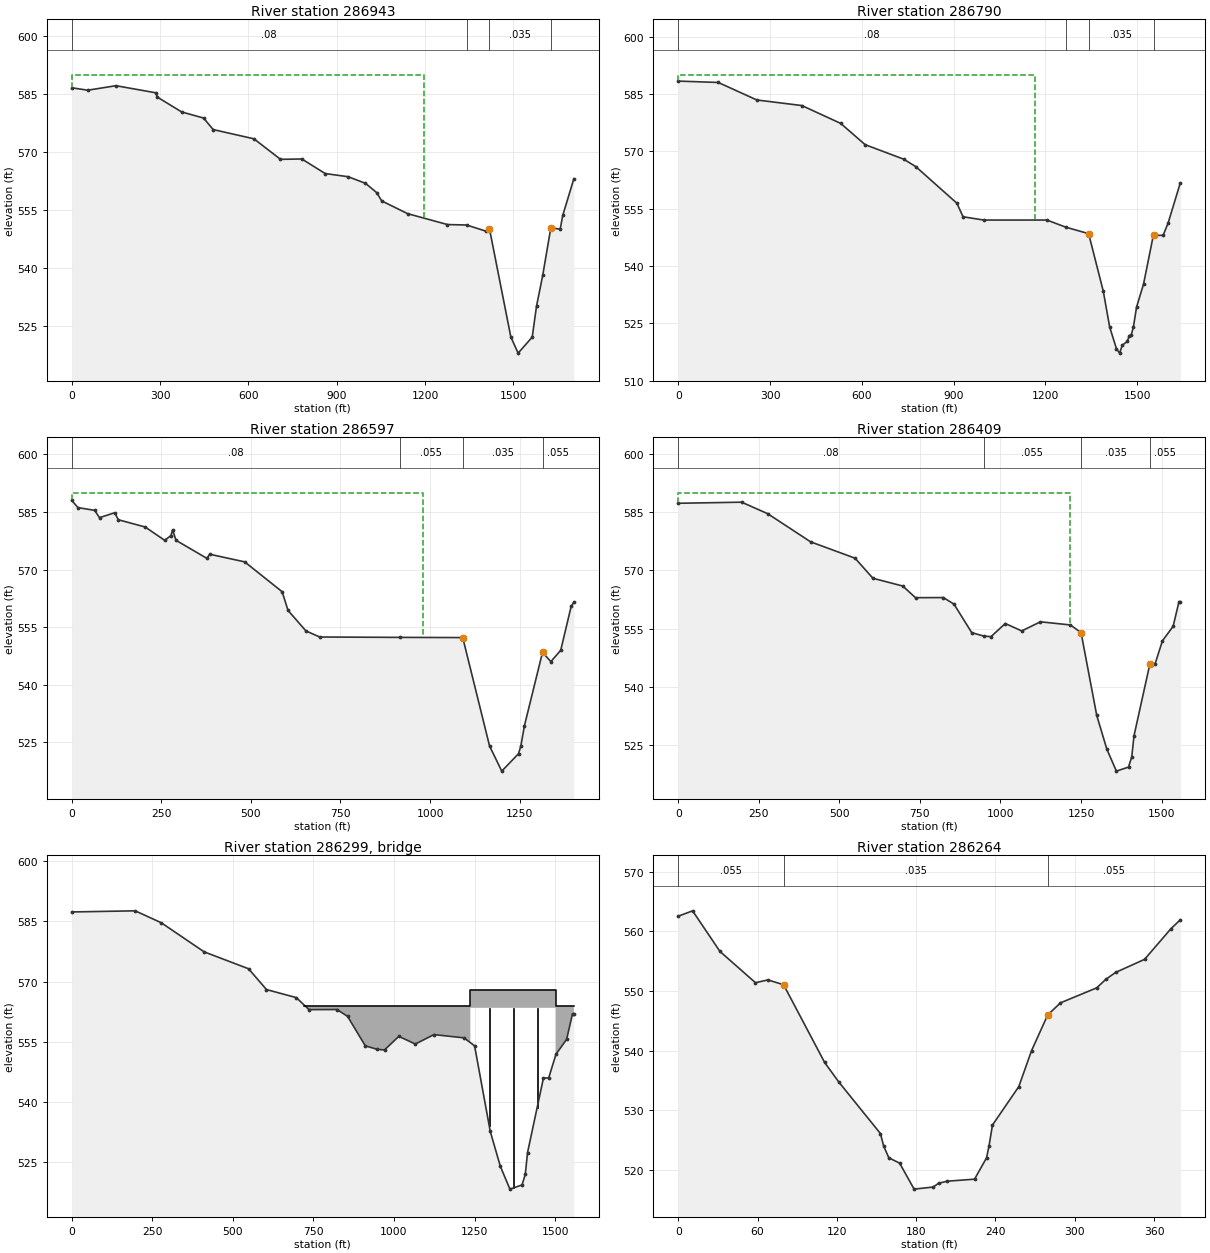
Type RM Length L Ch R = 1 ,286943  ,153,153,114
BEGIN DESCRIPTION:
This cross section corresponds to cross section 286821.8 of the non-georeferenced CDC model which was the source of this model.
Ineffective flow set in LOB.
Effective flow limit set at White Settlement Levee in ROB.
END DESCRIPTION:
XS GIS Cut Line= 2
 2306653.7555883 6962332.6461593 2305027.8433725 6961817.1129355
#Sta/Elev= 30
       0  586.64   54.37  586.01  150.13  587.18  285.54  585.34  291.06  584.21
  373.24  580.38  448.01  578.79  480.15  575.81  618.85  573.41   709.1  568.09
  781.59  568.18  861.03   564.4  939.03  563.58  997.75  561.87 1036.35  559.43
  1052.8  557.31 1141.11     554 1276.22  551.18 1341.35  551.06 1408.44  549.43
 1418.93  550.12 1491.71     522 1516.41  517.84 1564.32     522 1578.84     530
 1599.96     538 1627.39  550.29  1659.3     550 1667.96  553.53 1705.69  563.05
#Mann= 4 ,-1,0
       0     .08       0 1341.35    .055       0 1418.93    .035       0
 1627.39    .055       0
#XS Ineff= 1 ,-1
       0  1195.3     590
Permanent Ineff=
       F
Bank Sta=1418.93,1627.39
XS Rating Curve= 0 ,0
Exp/Cntr=0.3,0.1

Type RM Length L Ch R = 1 ,286790  ,193,193,147
BEGIN DESCRIPTION:
This cross section corresponds to cross section 286668.6 of the non-georeferenced CDC model which was the source of this model.
Ineffective flow set in LOB.
Effective flow limit set at White Settlement Levee in ROB.
END DESCRIPTION:
XS GIS Cut Line= 2
 2306663.6720871 6961950.8596609 2305043.1377575  6961692.325724
#Sta/Elev= 30
       0  588.36  130.96     588  256.86  583.42  404.02  581.96  531.03  577.29
  610.98  571.72  736.66  567.94   776.1     566  910.74  556.41  930.89  552.86
  998.66     552 1205.03     552 1267.04  550.13 1341.41  548.44 1389.28  533.37
 1410.18     524  1432.3  518.34 1442.67  517.18 1451.28  519.24 1467.66  520.24
 1474.31  521.74 1481.03  522.05 1487.66     524 1498.04  529.22 1520.94  535.28
 1552.58  547.88 1554.28     548 1584.86     548 1601.17  551.22 1641.03  561.72
#Mann= 4 ,-1,0
       0     .08       0 1267.04    .055       0 1341.41    .035       0
 1554.28    .055       0
#XS Ineff= 1 ,-1
       0 1164.76     590
Permanent Ineff=
       F
Bank Sta=1341.41,1554.28
XS Rating Curve= 0 ,0
Exp/Cntr=0.3,0.1

Type RM Length L Ch R = 1 ,286597  ,188,188,185
BEGIN DESCRIPTION:
This cross section corresponds to cross section 286475.7 of the non-georeferenced CDC model which was the source of this model.
Ineffective flow set in LOB.
Effective flow limit set at White Settlement Levee in ROB.
END DESCRIPTION:
XS GIS Cut Line= 2
 2306445.5084663   6961509.57417 2305044.2967177 6961533.3233898
#Sta/Elev= 30
       0     588   17.29  586.15   63.72  585.43   77.45  583.53  119.63   584.8
  130.08  582.98   204.9  581.09  259.28  577.62  276.79  578.85  281.43  580.33
  290.99  577.62  377.08  572.92  384.98  573.99  482.62     572  587.19  564.22
   603.6  559.35  653.53     554  692.08  552.41  915.68  552.31 1091.26  552.26
 1166.11     524 1200.22  517.44 1247.12     522 1253.52     524 1263.37  529.23
 1313.93   548.4 1337.29     546 1364.69  548.93 1393.89  560.38 1401.41  561.46
#Mann= 4 ,-1,0
       0     .08       0  915.68    .055       0 1091.26    .035       0
 1313.93    .055       0
#XS Ineff= 1 ,-1
       0  980.49     590
Permanent Ineff=
       F
Bank Sta=1091.26,1313.93
XS Rating Curve= 0 ,0
Exp/Cntr=0.5,0.3

Type RM Length L Ch R = 1 ,286409  ,145,145,148
BEGIN DESCRIPTION:
This cross section corresponds to cross section 286287.5 of the non-georeferenced CDC model which was the source of this model.
Upstream of White Settlement Road.
Ineffective flow set in LOB.
Effective flow limit set at White Settlement Levee in ROB.
END DESCRIPTION:
XS GIS Cut Line= 3
 2306597.3789175 6961311.2435467 2306074.0756047 6961318.8419955
 2305039.7221956 6961347.3910476
#Sta/Elev= 30
       0  587.31  196.81  587.59  277.82  584.62  410.83  577.38   548.7  573.17
  604.23     568  696.66     566  736.34     563   822.8  563.03  855.78  561.34
   910.8     554  947.48  553.13  970.51  552.96 1014.88  556.35 1066.11  554.44
 1123.96  556.79 1217.08  555.98 1250.11     554 1298.72  532.69 1330.08     524
 1359.69  518.34 1397.33  519.38 1407.38     522 1414.45  527.45 1463.83     546
 1479.99     546 1502.66   551.9 1535.77  555.62 1554.08     562  1558.1   561.8
#Mann= 4 ,-1,0
       0     .08       0  947.48    .055       0 1250.11    .035       0
 1463.83    .055       0
#XS Ineff= 1 ,-1
       0 1216.62     590
Permanent Ineff=
       F
Bank Sta=1250.11,1463.83
XS Rating Curve= 0 ,0
Exp/Cntr=0.5,0.3

Type RM Length L Ch R = 3 ,286299  ,,,
BEGIN DESCRIPTION:
White Settlement Road - upper crossing
Double bridges - total bridge width set at 70 feet.
Bridge data from USACE 1975 survey.
Note:  Internal bridge cross-sections modified to represent geometry under bridge.
END DESCRIPTION:
Node Name=White Settlement
Bridge Culvert--1,0,-1,-1, 0
Deck Dist Width WeirC Skew NumUp NumDn MinLoCord MaxHiCord MaxSubmerge Is_Ogee
38.3,70,2.6,0, 6, 6, , , 0.95, 0, 0,0,,
  721.88 1236.88 1236.88 1501.88 1501.88  1558.1
     564     564     568     568     564     564
     460     450  563.46  563.46     450     450
       0   52.22   52.22  317.22  317.22     400
     564     564     568     568     564     564
     460     450  563.46  563.46
Pier Skew, UpSta & Num, DnSta & Num=  ,1295.38, 2 ,110.72, 2 , 0 , 0 , 0 ,,
       3       3
     500     567
       3       3
     500     567
Pier Skew, UpSta & Num, DnSta & Num=  ,1369.88, 2 ,185.22, 2 , 0 , 0 , 0 ,,
       3       3
     500     567
       3       3
     500     567
Pier Skew, UpSta & Num, DnSta & Num=  ,1443.88, 2 ,259.22, 2 , 0 , 0 , 0 ,,
       3       3
     500     567
       3       3
     500     567
BR Coef=-1 , 0 , 0 ,, 0 ,,,0.8,-1,,0,
WSPro=,,,, 1 ,,,, 0 ,,,, 0 ,,,,-1 ,-1 ,-1 , 0 , 0 , 0 , 0 , 0
BR U #Sta/Elev= 468
       0  587.31   36.76  587.37   65.73  587.67  101.41  587.97  126.29  587.34
  157.96  586.84  177.77  587.39  183.22  587.46  186.92  587.49   191.3  587.54
  196.44  587.59  196.81  587.59  200.85  587.33  201.08  587.31  204.33   587.1
  205.83  587.01  208.35  586.85   210.1  586.75   212.4   586.6  216.37  586.36
  219.11  586.21  219.41   586.2   221.7  586.07  224.55  585.92  226.59   585.8
  227.55  585.75   229.2  585.65  230.69  585.57  232.21  585.48  234.37  585.37
  239.36  585.62  239.57  585.62  244.07  585.81  277.82  584.62  290.33     584
  311.15  582.71  322.27     582  330.26     582  339.79  581.57  344.14  581.32
  347.13  581.22  357.76  580.56  359.02  580.48  366.76     580  372.33  579.63
  378.32  579.27  379.11  579.22  395.91     578  410.83  577.38  423.47  577.02
  450.74  576.38  460.62     576  462.06  575.94  462.32  575.92  477.65  575.26
  480.58  575.05  483.27  574.85  488.24  574.63  491.04   574.4  494.84  574.11
  495.28  574.09  496.32     574  499.07  573.92   501.8  573.83  503.59  573.79
  511.83  573.57  516.93  573.46  521.96  573.37  524.59   573.3  524.73  573.29
  532.07  573.25  540.79  573.28  541.91  573.27  544.41  573.29  548.55  573.17
   548.7  573.17  549.81  573.08  555.73   572.8  557.47  572.61  558.36  572.53
  561.72  572.25  563.51  572.06  566.08  571.74  567.67  571.52  569.74  571.27
  570.66  571.15   573.2  570.84  574.93  570.61  577.95  570.19  579.58     570
  583.99  569.52  588.26  569.06  589.44  568.93  590.35  568.81  593.18  568.54
  593.87   568.5  604.23     568  611.61     568  614.25  567.93  615.86  567.91
  616.94  567.92  617.76  567.95  619.63  567.98  620.97  567.98   622.6  567.95
  624.33  567.93   626.9  567.89  628.74  567.84  630.65  567.82  632.55  567.76
  633.26  567.75  635.54  567.68  637.54   567.6  638.69  567.59  642.38  567.45
  642.99  567.42  644.19  567.39   645.6  567.37  648.08  567.28  660.16     566
  696.66     566  697.86  565.88  707.73  564.84  715.14     564  716.27   563.9
  716.76  563.89  722.95  563.49  724.77  563.47  729.66   563.2  732.76  563.17
  736.34     563  760.71  562.81  762.76  562.89  768.61  562.83  770.21  562.93
  772.65  563.07  775.48  563.22  780.39  563.14  781.89  563.25  786.18  563.17
  787.05  563.21  788.87  563.21  791.49  563.16   794.7  563.13  796.35  563.06
  797.02  563.02  798.08     563  798.85  562.95  799.75  562.93  800.47  562.89
  801.16  562.87  802.22   562.8  802.82  562.78     804  562.72  805.48  562.61
  807.78  562.45  809.68   562.3  811.22  562.19  813.58  562.62  813.83  562.57
  814.31   562.6  815.98  562.79  816.63  562.83  817.11  562.88  820.01  562.97
  821.32  563.03   822.8  563.03  827.74  562.44  831.38     562  833.43  561.82
  834.62  561.78  836.84  561.63   837.3  561.63  838.72  561.55   839.3  561.55
  842.84  561.49  849.31  561.57  851.68  561.58  852.97  561.56  855.52  561.35
  855.78  561.34  862.52  560.26  864.21     560  865.49  559.77  867.38  559.42
  868.26  559.27  872.81  558.67  873.31  558.59  874.79  558.46  876.31  558.36
  877.39   558.3  879.98     558  881.48   557.8   886.1  557.13  894.13     556
  899.89  555.37   910.8     554  919.02  553.58  924.57  553.34  927.29  553.32
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BR U #Mann= 3
       0    .055 1251.69    .035 1465.07    .055
BR U Banks=1251.69,1465.07
BR D #Sta/Elev= 305
       0  562.54    3.67  562.86    5.45  563.02   10.86  563.44   14.67  562.18
    15.2     562   18.25     561   21.29     560   22.88  559.47   24.99  558.78
   27.34     558    28.6  557.59    30.1  557.11   31.59  556.62   34.03  556.18
   35.03     556   36.12  555.78   36.33  555.74   36.66  555.67   38.55  555.28
   39.49  555.09    40.9   554.8   41.66  554.66   42.97  554.41   43.47  554.32
    44.8  554.07   44.84  554.06   45.21     554    46.4  553.78    46.6  553.73
   47.84  553.51   48.26  553.42   48.61  553.35   49.74  553.13   50.22  553.03
   51.09  552.85   51.82  552.69   52.29   552.6   53.59  552.34   53.81   552.3
   55.32     552   55.95  551.87   57.13  551.65   58.45  551.38   60.61  551.53
   61.81  551.59    63.1  551.68   64.16  551.64   64.53  551.67   67.88  551.85
   74.49   551.4    76.9  551.25   79.71  551.04   81.03  550.49   82.19     550
   84.48  549.04   85.32  548.69   86.96     548   87.47  547.78   91.69     546
   94.26  544.92   96.45     544   99.47  542.71  101.14     542  102.35  541.49
  105.87     540  108.83   538.8  110.77     538  114.02  536.95  117.15     536
  120.59  534.99  121.45  534.73  122.52  534.44  124.11     534  130.08  532.38
  131.46     532  135.83   530.8   138.7     530  140.51   529.5  145.96     528
  150.25  526.82  152.96  526.08  153.03  526.03  153.05     526  154.67  524.61
  155.39     524  156.11  523.64  159.32     522  164.44  521.45  167.46  521.12
  168.22  520.73   169.9     520  171.99  519.23  175.19     518  178.17  516.86
  178.46  516.75  185.95  516.95   192.9   517.1  194.11  517.45  196.48  517.62
  196.93  517.73  198.48  517.73  198.53  517.73  198.58  517.74  198.73  517.75
  200.07  517.83  201.03  517.96  201.13  517.96   201.9  517.99  202.85     518
  203.33  517.98   203.5  518.08  210.17  518.32  210.43   518.3  210.62  518.33
  210.77  518.34  211.54  518.35  214.59  518.36  224.17  518.42  225.47  518.93
  228.18     520   231.4  521.27  233.26     522  234.07  522.87  235.13     524
  236.32  525.61   236.6     526  237.41  527.06  237.62  527.33  237.74   527.5
  238.07   527.6   239.3     528  242.09  528.92  245.39     530  248.88  531.13
   251.6     532  256.02  533.42  257.65  533.95  257.71  533.99  258.18   534.3
  260.84     536  263.15  537.45  264.03     538  266.96  539.76  267.34     540
  267.59  540.13  267.89  540.28  269.62  541.14  271.36     542  271.95  542.29
  273.75  543.17     275  543.78  275.17  543.87  275.46     544  277.54  544.99
  279.51  545.97  279.64  545.99  279.68     546  281.06   546.3  281.68  546.43
  284.12  546.94  285.09  547.14  286.58  547.45  288.99  547.96  289.18     548
  289.19     548  289.24     548  290.79  548.17   290.9  548.18  294.09  548.52
  294.42  548.56  296.67   548.8  297.74  548.91  298.71  549.02  299.29  549.06
  300.33  549.17   301.1  549.23  306.65  549.69  307.05  549.73  307.24  549.75
  308.38  549.84  308.53  549.85  308.67  549.87  310.31     550  310.33     550
  310.52     550  310.53     550  310.54     550  310.63     550  311.15  550.05
  311.73  550.11  315.28   550.4  315.63  550.43  315.79  550.45  315.88  550.46
  315.95  550.46     316  550.47  316.04  550.47  316.08  550.48  316.11  550.48
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BR D #Mann= 3
       0    .055   79.71    .035  279.51    .055
BR D Banks=67.88,279.51
BC Design=,, 0 ,, 0 ,,,,,,
BC Use User HTab Curves=0
BC User HTab FreeFlow(D)= 0

Type RM Length L Ch R = 1 ,286264  ,59,59,60
BEGIN DESCRIPTION:
This cross section corresponds to cross section 286142.2 of the non-georeferenced CDC model which was the source of this model.
Downstream of White Settlement Road.
Effective flow limit set at Sump 6W Levee in LOB.
Effective flow limit set at White Settlement Levee in ROB.
END DESCRIPTION:
XS GIS Cut Line= 2
 2305415.6669644  6961193.717467 2305035.8728663 6961200.1241573
#Sta/Elev= 30
       0  562.54   10.86  563.44   31.59  556.62   58.45  551.38   67.88  551.85
   79.71  551.04  110.77     538  121.45  534.73  152.96  526.08  155.39     524
  159.32     522  167.46  521.12  178.46  516.75   192.9   517.1  196.93  517.73
   203.5  518.08  224.17  518.42  233.26     522  235.13     524  237.74   527.5
  257.65  533.95  267.34     540  279.51  545.97  289.18     548  316.62  550.52
  323.45  551.94  330.94  553.11  352.81   555.3  372.87  560.47  379.85  561.93
#Mann= 3 ,-1,0
       0    .055       0   79.71    .035       0  279.51    .055       0
Bank Sta=79.71,279.51
XS Rating Curve= 0 ,0
Exp/Cntr=0.5,0.3

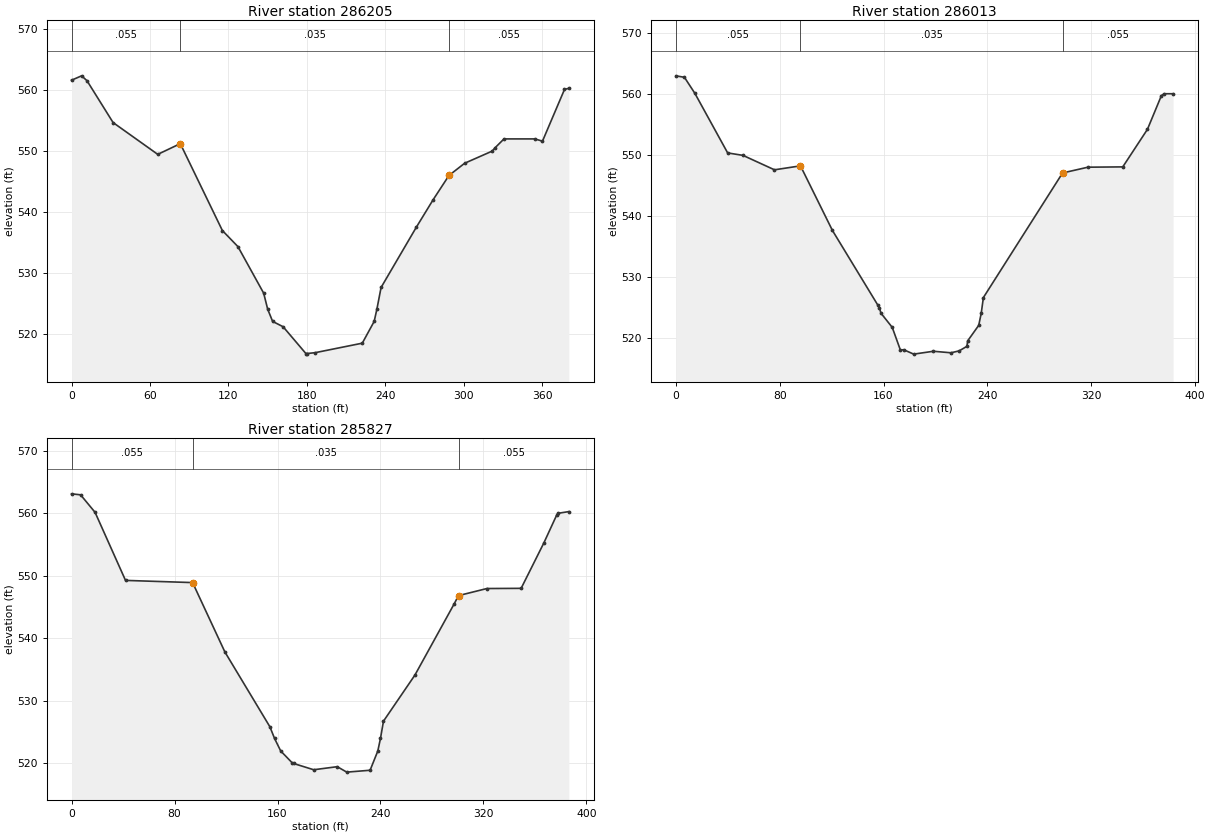
Type RM Length L Ch R = 1 ,286205  ,192,192,187
BEGIN DESCRIPTION:
This cross section corresponds to cross section 286083.7 of the non-georeferenced CDC model which was the source of this model.
Effective flow limit set at Sump 6W Levee in LOB.
Effective flow limit set at White Settlement Levee in ROB.
END DESCRIPTION:
XS GIS Cut Line= 2
 2305413.9656005 6961136.5255053 2305033.4524026 6961140.3688713
#Sta/Elev= 30
       0  561.65    7.71  562.37   11.82  561.57   31.79  554.69   65.98  549.46
   83.24  551.22  115.42  536.94  127.34  534.29  147.03  526.64  150.11     524
  153.88     522  161.92  521.12  179.72  516.62  179.85  516.71  186.47  516.86
  222.49  518.42  231.59     522  233.66     524  236.88  527.58  263.89   537.5
   276.7     542  288.83  545.99  300.83     548  321.96     550  324.14  550.55
  330.93     552   354.5     552  360.38  551.63  377.22  560.13  380.53  560.32
#Mann= 3 ,-1,0
       0    .055       0   83.24    .035       0  288.83    .055       0
Bank Sta=83.24,288.83
XS Rating Curve= 0 ,0
Exp/Cntr=0.3,0.1

Type RM Length L Ch R = 1 ,286013  ,185,185,185
BEGIN DESCRIPTION:
This cross section corresponds to cross section 285891.3 of the non-georeferenced CDC model which was the source of this model.
Effective flow limit set at Sump 6W Levee in LOB.
Effective flow limit set at White Settlement Levee in ROB.
END DESCRIPTION:
XS GIS Cut Line= 2
 2305408.1258154 6960940.2263032 2305025.2447867  6960952.304509
#Sta/Elev= 30
       0  562.94    6.62   562.7   14.66  560.07   39.92  550.29   51.72  549.89
   75.99  547.52   96.02  548.17   120.6  537.58  155.66   525.3  156.84  524.87
     158     524   166.7  521.67  172.98  517.95  175.56     518  183.23  517.28
  198.39  517.75  211.94   517.5  218.21  517.81  224.24  518.56  224.82  519.46
  233.32     522  235.27     524  236.91  526.56   297.9     547  317.45  547.95
  344.29     548  363.28  554.16     374  559.67  376.06     560  383.07     560
#Mann= 3 ,-1,0
       0    .055       0   96.02    .035       0   297.9    .055       0
Bank Sta=96.02,297.9
XS Rating Curve= 0 ,0
Exp/Cntr=0.3,0.1

Type RM Length L Ch R = 1 ,285827  ,187,187,290
BEGIN DESCRIPTION:
This cross section corresponds to cross section 285705.9 of the non-georeferenced CDC model which was the source of this model.
Effective flow limit set at Sump 6W Levee in LOB.
Effective flow limit set at White Settlement Levee in ROB.
END DESCRIPTION:
XS GIS Cut Line= 3
 2305403.2588309 6960754.8727929 2305395.6264171 6960754.9330744
 2305017.1778277 6960767.4644932
#Sta/Elev= 27
       0  563.11    7.04  562.95   18.29  560.15   41.94  549.27   94.05  548.92
  119.13  537.83  154.06  525.88  157.72     524  162.49     522  171.59  520.07
  172.53     520  188.12     519  206.41  519.49  213.79  518.62  231.93  518.92
  237.92     522  239.98     524  242.33  526.77  266.73  534.13  297.11  545.47
  300.61  546.84  322.67  547.97  349.25     548  366.81  555.22  376.95  559.75
   378.1     560  386.29  560.27
#Mann= 3 ,-1,0
       0    .055       0   94.05    .035       0  300.61    .055       0
Bank Sta=94.05,300.61
XS Rating Curve= 0 ,0
Exp/Cntr=0.3,0.1