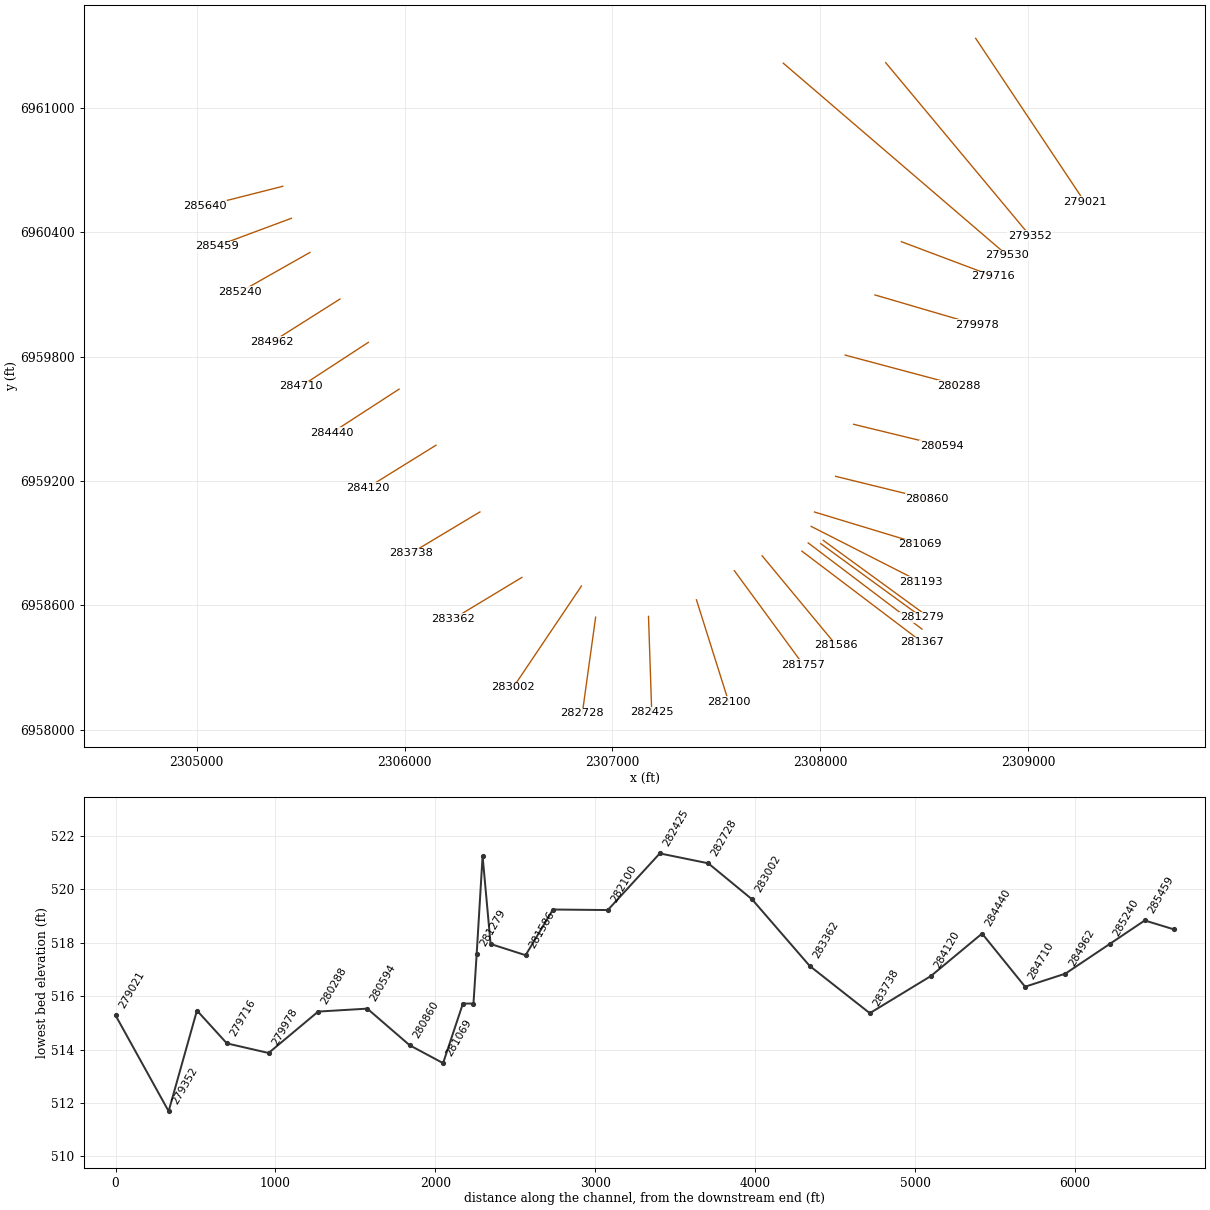
HEC-RAS study CDC_Consolidated_Model.prj: Upper Trinity CDC Consolidated Model

--- CDC_Consolidated_Model.g03 (geometry) --- (continued)

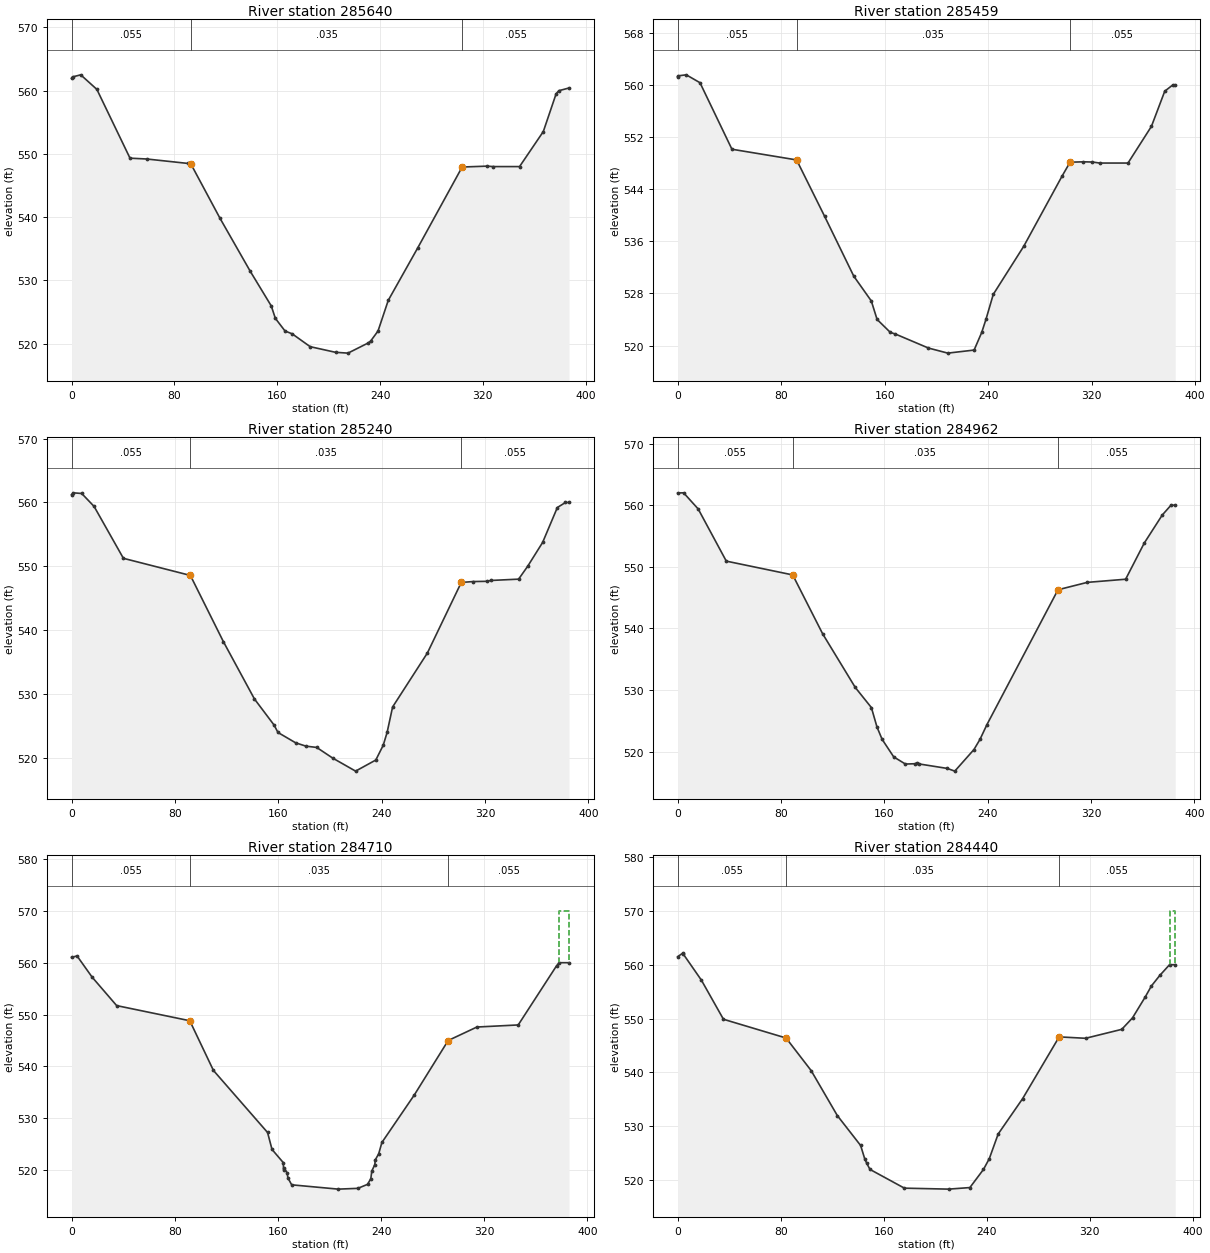
Type RM Length L Ch R = 1 ,285640  ,181,181,215
BEGIN DESCRIPTION:
This cross section corresponds to cross section 285518.5 of the non-georeferenced CDC model which was the source of this model.
Effective flow limit set at Sump 6W Levee in LOB.
Effective flow limit set at White Settlement Levee in ROB.
END DESCRIPTION:
XS GIS Cut Line= 2
  2305413.428123 6960622.8788975 2305038.3259986 6960527.5138473
#Sta/Elev= 30
       0  561.98     .79  562.18    7.15  562.51    19.7  560.21   45.48  549.33
   58.45   549.2   90.53   548.5   92.96  548.37  115.51  539.82  139.04  531.44
  155.39  525.96  158.55     524  166.08     522  171.67  521.55  185.66  519.52
  205.35  518.63  215.06   518.5  230.72   520.1   232.7  520.41  238.44     522
   246.4  526.85   269.4  535.17  303.87  547.93  323.34  548.07  327.94     548
  348.54     548  367.02  553.54  376.98  559.51   379.1     560  387.04  560.43
#Mann= 3 ,-1,0
       0    .055       0   92.96    .035       0  303.87    .055       0
Bank Sta=92.96,303.87
XS Rating Curve= 0 ,0
Exp/Cntr=0.3,0.1

Type RM Length L Ch R = 1 ,285459  ,219,219,271
BEGIN DESCRIPTION:
This cross section corresponds to cross section 285337.4 of the non-georeferenced CDC model which was the source of this model.
Effective flow limit set at Sump 6W Levee in LOB.
Effective flow limit set at White Settlement Levee in ROB.
END DESCRIPTION:
XS GIS Cut Line= 2
 2305455.2715112 6960468.5733336 2305094.9699822 6960333.9967979
#Sta/Elev= 30
       0  561.25     .51  561.39    6.64  561.54   17.24  560.33   41.95  550.12
   91.94  548.48  113.61  539.82  136.14  530.64  149.68  526.84  154.16     524
  164.46     522  168.21  521.77  193.86  519.61  208.82  518.83  229.17   519.3
  235.03     522  238.31     524  243.98  527.85  267.54  535.23  297.17     546
  302.97     548  303.04  548.13  313.61  548.19   320.6  548.16  326.25     548
  348.13     548  366.25  553.63  376.55  559.03  382.84     560  384.61     560
#Mann= 3 ,-1,0
       0    .055       0   91.94    .035       0  303.04    .055       0
Bank Sta=91.94,303.04
XS Rating Curve= 0 ,0
Exp/Cntr=0.3,0.1

Type RM Length L Ch R = 1 ,285240  ,277,277,292
BEGIN DESCRIPTION:
This cross section corresponds to cross section 285118.3 of the non-georeferenced CDC model which was the source of this model.
Effective flow limit set at Sump 6W Levee in LOB.
Effective flow limit set at White Settlement Levee in ROB.
END DESCRIPTION:
XS GIS Cut Line= 3
 2305544.5801518 6960303.6826002 2305542.4985608 6960302.5144358
 2305209.6689251 6960113.5773532
#Sta/Elev= 30
       0  561.23    1.26  561.51    7.86  561.41   17.46  559.38   40.14  551.26
   91.99  548.58   117.5  538.23  141.56  529.25  156.82  525.15  159.79     524
  173.49  522.38  181.43  521.86  189.76  521.66  202.08     520  219.87  517.95
  235.52  519.69  241.26     522  244.26     524  248.52  527.99  275.45  536.44
  301.67  547.48  310.54  547.62  321.57  547.66   324.3  547.79  346.06     548
  353.03     550  364.63  553.74  376.04  559.21  382.33     560   385.1     560
#Mann= 3 ,-1,0
       0    .055       0   91.99    .035       0  301.67    .055       0
Bank Sta=91.99,301.67
XS Rating Curve= 0 ,0
Exp/Cntr=0.3,0.1

Type RM Length L Ch R = 1 ,284962  ,252,252,257
BEGIN DESCRIPTION:
This cross section corresponds to cross section 284840.9 of the non-georeferenced CDC model which was the source of this model.
Effective flow limit set at Sump 6W Levee in LOB.
Effective flow limit set at White Settlement Levee in ROB.
END DESCRIPTION:
XS GIS Cut Line= 2
 2305688.8433388 6960078.4510077 2305363.5097382 6959872.1706178
#Sta/Elev= 27
       0  562.01    4.59  562.03   15.88  559.41   37.64  550.94   89.07   548.7
  112.27  539.13  137.53  530.42  149.99  527.16  154.33     524   158.3     522
  167.28  519.15  176.33  517.99  183.61  518.04  185.65  518.16  187.13     518
   208.7  517.28  214.57  516.84  229.43  520.35  234.09     522  239.48   524.4
  294.48  546.29  317.15  547.49  346.85     548  361.26  553.87   375.2  558.42
  381.89     560  385.22  560.03
#Mann= 3 ,-1,0
       0    .055       0   89.07    .035       0  294.48    .055       0
Bank Sta=89.07,294.48
XS Rating Curve= 0 ,0
Exp/Cntr=0.3,0.1

Type RM Length L Ch R = 1 ,284710  ,269,269,269
BEGIN DESCRIPTION:
This cross section corresponds to cross section 284588.4 of the non-georeferenced CDC model which was the source of this model.
Effective flow limit set at Sump 6W Levee in LOB.
Effective flow limit set at White Settlement Levee in ROB.
END DESCRIPTION:
XS GIS Cut Line= 2
 2305825.6482153 6959869.5698282 2305502.8236208 6959658.2754447
#Sta/Elev= 30
       0  561.02    4.25  561.31   15.95  557.22   34.98  551.73    91.7  548.81
  110.04  539.23  152.02  527.27  155.48     524  164.14  521.48  164.56     520
  164.61  520.47  167.13  519.53  167.84  518.49  170.72  517.18  206.83  516.35
  222.05   516.5  229.55  517.27  232.09  518.36  232.87  519.84  235.17  521.06
  235.58     522  238.21  523.16  240.68  525.34  265.85  534.51  292.09     545
  314.37   547.6  346.41     548  376.16  559.41  378.26     560  385.83     560
#Mann= 3 ,-1,0
       0    .055       0    91.7    .035       0  292.09    .055       0
#XS Ineff= 2 , 0
       0                  378.26       0     570
Permanent Ineff=
       F       T
Bank Sta=91.7,292.09
XS Rating Curve= 0 ,0
Exp/Cntr=0.3,0.1

Type RM Length L Ch R = 1 ,284440  ,320,320,314
BEGIN DESCRIPTION:
This cross section corresponds to cross section 284318.9 of the non-georeferenced CDC model which was the source of this model.
Upstream of Sump 6W outfall (left bank).
Upstream of Sump 5W outfall (right bank).
Effective flow limit set at Sump 6W Levee in LOB.
Effective flow limit set at White Settlement Levee in ROB.
END DESCRIPTION:
XS GIS Cut Line= 2
 2305973.5737942 6959643.7091044 2305649.5895914 6959432.9387161
#Sta/Elev= 28
       0  561.49    3.88  562.13     4.1  562.06   18.43  557.13   35.56  549.87
   84.21  546.39  103.68  540.35  124.01     532  142.14  526.44  145.28     524
  146.82  523.16   149.4     522  176.13  518.52  210.56  518.34  227.01  518.63
  237.58     522   242.1     524     249  528.58     268  535.14  296.37   546.6
  316.88  546.34  345.01     548  353.35  550.13  363.22     554  368.03  556.05
  374.52     558  382.14     560  386.51     560
#Mann= 3 ,-1,0
       0    .055       0   84.21    .035       0  296.37    .055       0
#XS Ineff= 2 , 0
       0                  382.14       0     570
Permanent Ineff=
       F       T
Bank Sta=84.21,296.37
XS Rating Curve= 0 ,0
Exp/Cntr=0.3,0.1

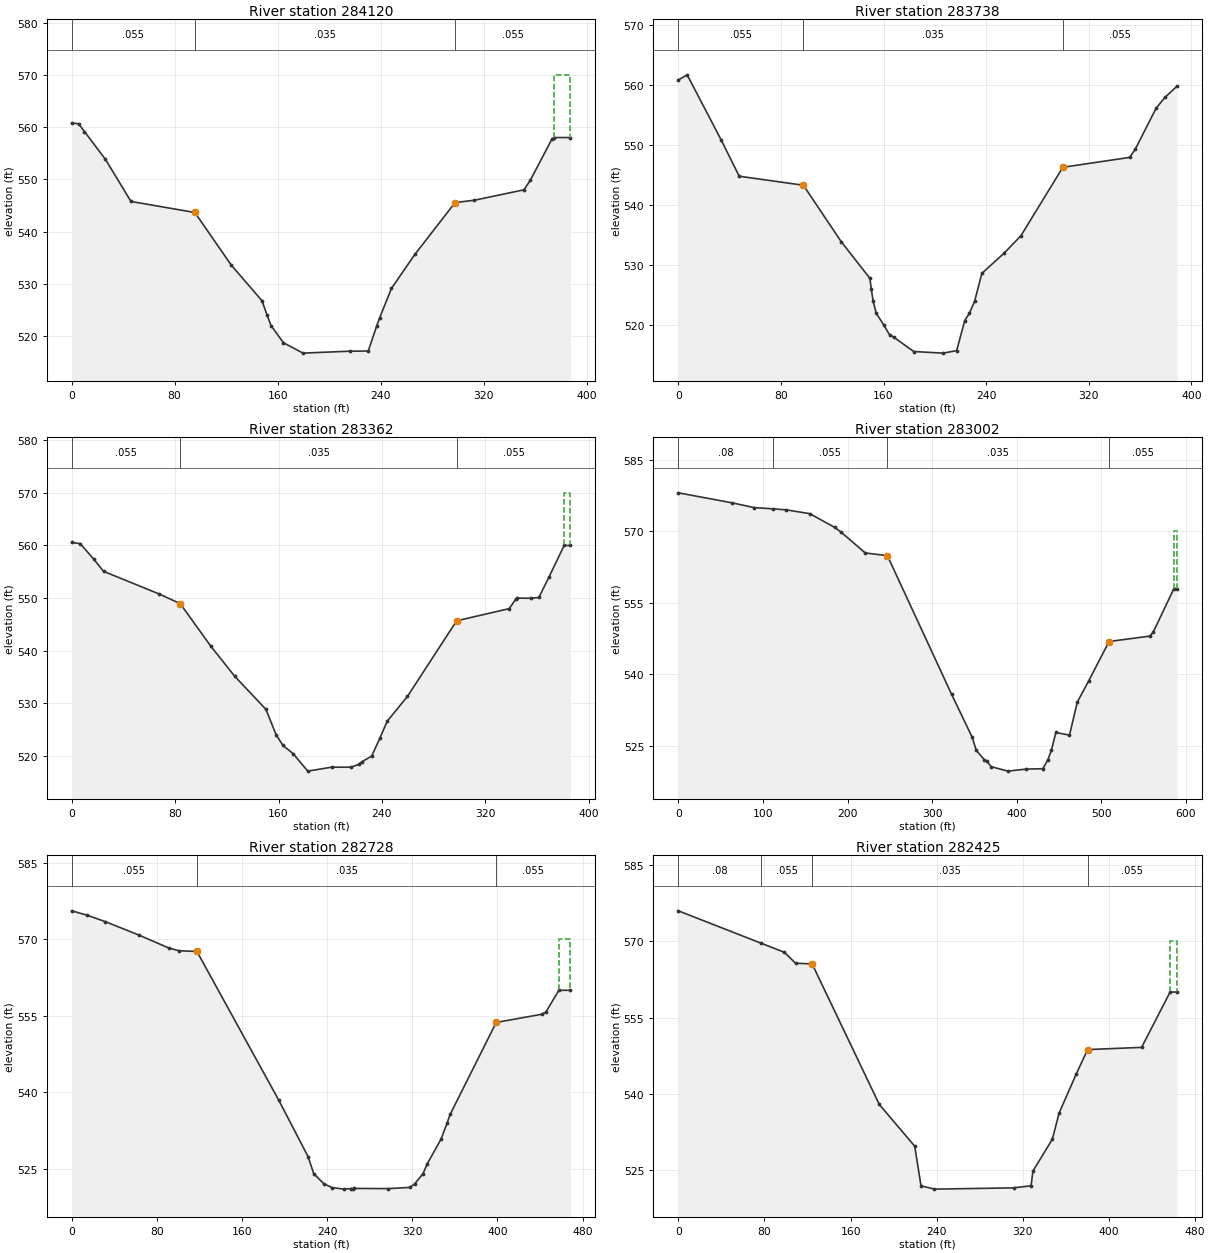
Type RM Length L Ch R = 1 ,284120  ,382,382,378
BEGIN DESCRIPTION:
This cross section corresponds to cross section 283999 of the non-georeferenced CDC model which was the source of this model.
Downstream of Sump 6W outfall (left bank).
Downstream of Sump 5W outfall (right bank).
Effective flow limit set at Sump 6W Levee in LOB.
Effective flow limit set at White Settlement Levee in ROB.
END DESCRIPTION:
XS GIS Cut Line= 2
  2306150.970667 6959372.9098947 2305822.0181031 6959168.2011014
#Sta/Elev= 25
       0  560.78    5.38  560.64    9.98  559.15   26.32  553.81   46.11  545.77
   95.71  543.66  123.96  533.61  147.95  526.75  151.82     524  154.97     522
  164.46  518.75  179.71  516.75  215.91  517.12  230.38  517.15  237.02     522
  239.33  523.55  248.39  529.12   266.7  535.67  297.86  545.56   312.7     546
  351.38     548  356.24  549.81   373.2  557.77  374.95     558  387.45     558
#Mann= 3 ,-1,0
       0    .055       0   95.71    .035       0  297.86    .055       0
#XS Ineff= 2 , 0
       0                  374.95       0     570
Permanent Ineff=
       F       T
Bank Sta=95.71,297.86
XS Rating Curve= 0 ,0
Exp/Cntr=0.3,0.1

Type RM Length L Ch R = 1 ,283738  ,376,376,377
BEGIN DESCRIPTION:
This cross section corresponds to cross section 283616.7 of the non-georeferenced CDC model which was the source of this model.
Effective flow limit set at Sump 6W Levee in LOB.
Effective flow limit set at White Settlement Levee in ROB.
END DESCRIPTION:
XS GIS Cut Line= 2
 2306362.4578217 6959050.8802381 2306029.0793004 6958850.3943897
#Sta/Elev= 28
       0  560.91    6.87  561.77   33.28  550.96   47.47  544.86   97.51  543.36
  127.12  533.91  149.34  527.85  150.51     526  151.91     524  154.35     522
  160.35     520  164.89  518.35  168.12     518  183.55  515.63  206.37  515.36
  217.03  515.78  223.35  520.79  226.94     522  231.02     524  236.69  528.66
   253.9     532  267.11  534.92  299.85  546.35  351.96     548  356.45  549.42
  372.65  556.22  379.46     558  389.02  559.91
#Mann= 3 ,-1,0
       0    .055       0   97.51    .035       0  299.85    .055       0
Bank Sta=97.51,299.85
XS Rating Curve= 0 ,0
Exp/Cntr=0.3,0.1

Type RM Length L Ch R = 1 ,283362  ,360,360,516
BEGIN DESCRIPTION:
This cross section corresponds to cross section 283241 of the non-georeferenced CDC model which was the source of this model.
Effective flow limit set at Sump 6W Levee in LOB.
Effective flow limit set at White Settlement Levee in ROB.
END DESCRIPTION:
XS GIS Cut Line= 2
 2306564.5685478 6958734.7641302 2306234.6390349 6958534.9105244
#Sta/Elev= 30
       0  560.58    6.64  560.35   17.16  557.39   24.67  555.09   67.87  550.77
   84.01  548.94  107.66  540.86   126.1  535.16  150.26  528.87   158.2     524
   163.5     522  171.22  520.46  182.66  517.13  201.04  517.88  216.05  517.88
  222.24  518.43  224.25  518.86  232.05     520   238.3  523.35  244.05  526.62
  259.66  531.31  297.73  545.69  338.38     548  343.45   549.8  344.32     550
   355.5  549.97   361.3  550.12  369.15     554  380.85     560  385.74     560
#Mann= 3 ,-1,0
       0    .055       0   84.01    .035       0  297.73    .055       0
#XS Ineff= 2 , 0
       0                  380.85       0     570
Permanent Ineff=
       F       T
Bank Sta=84.01,297.73
XS Rating Curve= 0 ,0
Exp/Cntr=0.3,0.1

Type RM Length L Ch R = 1 ,283002  ,274,274,476
BEGIN DESCRIPTION:
This cross section corresponds to cross section 282880.9 of the non-georeferenced CDC model which was the source of this model.
Effective flow limit set at White Settlement Levee in ROB.
END DESCRIPTION:
XS GIS Cut Line= 2
 2306851.0607782 6958693.2397802 2306522.5198136 6958203.5215514
#Sta/Elev= 30
       0  578.11   63.73     576   89.78     575  112.22  574.74   127.8  574.53
  155.41  573.73  184.84  570.84  191.93  569.92     221  565.47  247.11  564.91
  323.01  535.77  347.37  526.74  352.14     524  361.74     522  364.71  521.71
  369.91  520.55  389.62  519.62  411.17  520.05  430.93  520.13  436.82     522
     441     524  446.27  527.75  462.37  527.18  471.65  534.14  485.26  538.65
  509.18  546.86  557.39     548  561.31  548.82  585.91     558  589.71     558
#Mann= 4 ,-1,0
       0     .08       0  112.22    .055       0  247.11    .035       0
  509.18    .055       0
#XS Ineff= 2 , 0
       0                  585.91       0     570
Permanent Ineff=
       F       T
Bank Sta=247.11,509.18
XS Rating Curve= 0 ,0
Exp/Cntr=0.3,0.1

Type RM Length L Ch R = 1 ,282728  ,303,303,363
BEGIN DESCRIPTION:
This cross section corresponds to cross section 282606.7 of the non-georeferenced CDC model which was the source of this model.
Effective flow limit set at White Settlement Levee in ROB.
END DESCRIPTION:
XS GIS Cut Line= 2
 2306919.4247788 6958542.6715388 2306855.2633699 6958078.4167278
#Sta/Elev= 29
       0   575.6   14.29  574.76   31.78  573.47   62.91  570.87   91.38   568.3
  100.83  567.77  117.75  567.62  194.41  538.51  222.22  527.33   227.5     524
  237.13     522  244.86  521.26  256.07  520.97  262.96  521.09  264.22  521.04
  265.15  521.11  297.37  521.07  317.76   521.3  322.31     522  330.16     524
  334.27     526  346.96  530.73  352.75  533.91   355.6  535.62  398.92  553.69
  441.79   555.3  445.44  555.69  457.83     560  468.67     560
#Mann= 3 ,-1,0
       0    .055       0  117.75    .035       0  398.92    .055       0
#XS Ineff= 2 , 0
       0                  457.82       0     570
Permanent Ineff=
       F       T
Bank Sta=117.75,398.92
XS Rating Curve= 0 ,0
Exp/Cntr=0.3,0.1

Type RM Length L Ch R = 1 ,282425  ,325,325,408
BEGIN DESCRIPTION:
This cross section corresponds to cross section 282303.7 of the non-georeferenced CDC model which was the source of this model.
Effective flow limit set at White Settlement Levee in ROB.
END DESCRIPTION:
XS GIS Cut Line= 2
 2307173.8283321 6958546.6056511 2307189.3897706  6958083.490225
#Sta/Elev= 19
       0  575.94   76.83  569.59   98.51   567.8   108.9  565.66  124.29  565.52
  186.67  537.95  219.55  529.77  225.42     522  237.78  521.34  311.34  521.59
  327.66     522  329.34  524.87  347.41  531.13  353.71  536.28  369.77     544
  380.16  548.72  430.32  549.15  456.79     560  463.38     560
#Mann= 4 ,-1,0
       0     .08       0   76.83    .055       0  124.29    .035       0
  380.16    .055       0
#XS Ineff= 2 , 0
       0                  456.79       0     570
Permanent Ineff=
       F       T
Bank Sta=124.29,380.16
XS Rating Curve= 0 ,0
Exp/Cntr=0.3,0.1

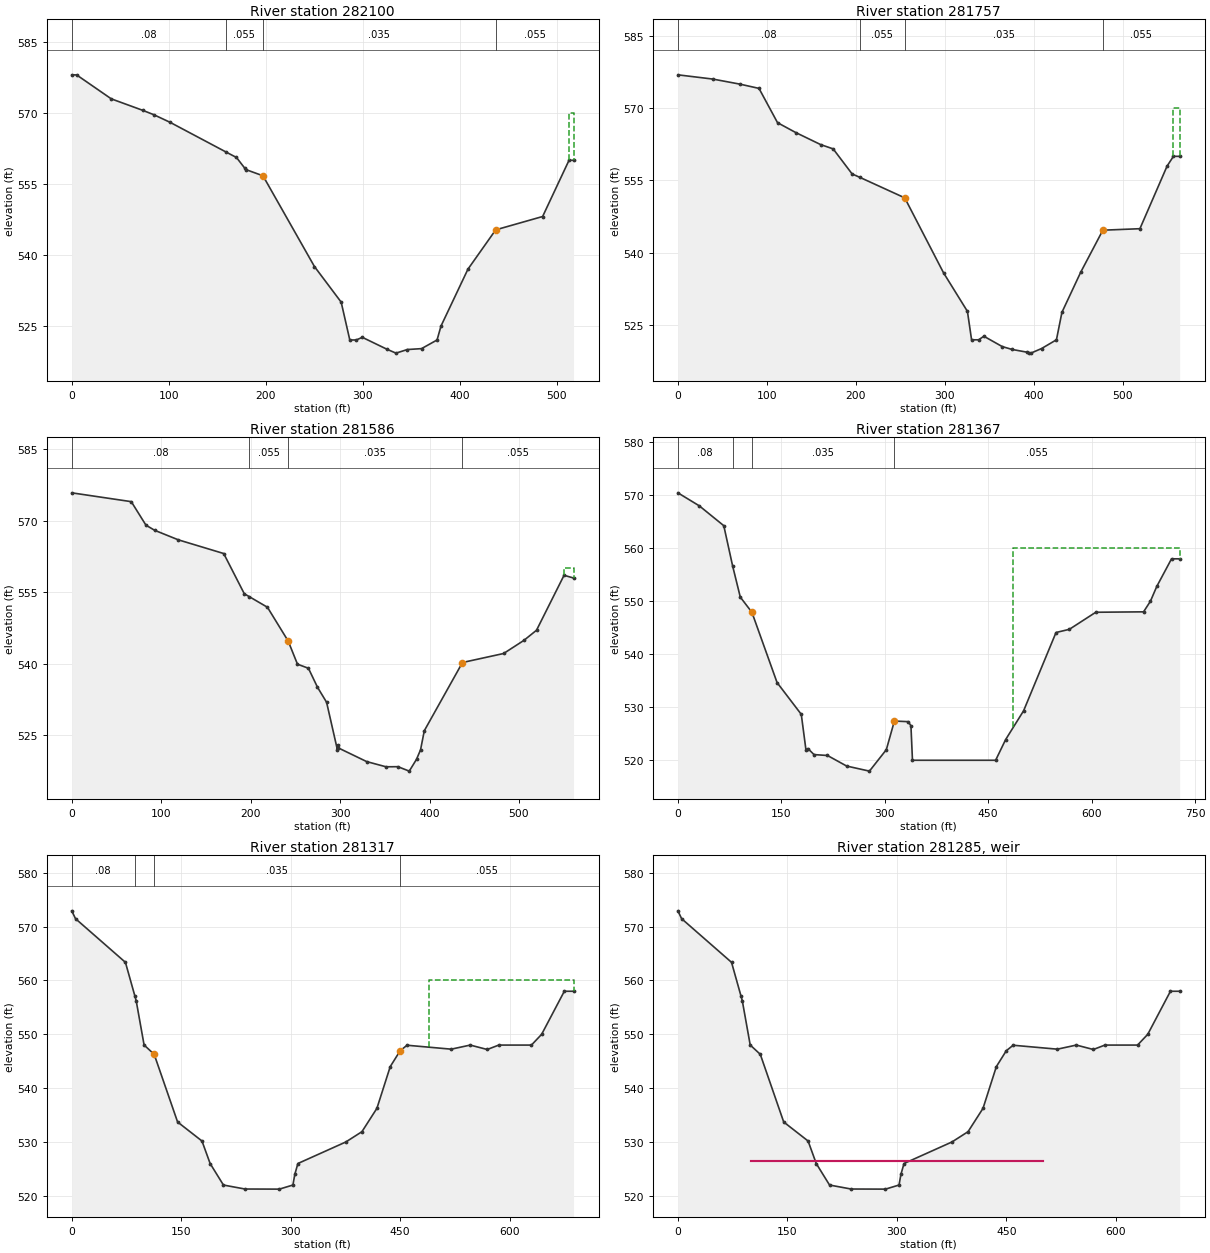
Type RM Length L Ch R = 1 ,282100  ,343,343,439
BEGIN DESCRIPTION:
This cross section corresponds to cross section 281978.7 of the non-georeferenced CDC model which was the source of this model.
Effective flow limit set at White Settlement Levee in ROB.
END DESCRIPTION:
XS GIS Cut Line= 2
 2307404.6274707  6958626.598404 2307559.8065327 6958133.0780339
#Sta/Elev= 27
       0  578.07    5.04  578.05   40.75  572.99   73.34  570.55   84.68  569.63
  101.26  568.04  158.77  561.78  169.84  560.59  178.57  558.28  179.99     558
  197.16  556.72  250.23  537.53   277.8     530  286.68     522  293.29     522
  299.61  522.56     325  520.04  334.28  519.22  346.02  519.98  360.63  520.17
  376.65     522   380.7  524.94  408.48  536.97  437.13  545.29   485.5  548.11
  512.71     560  517.34     560
#Mann= 4 ,-1,0
       0     .08       0  158.77    .055       0  197.16    .035       0
  437.13    .055       0
#XS Ineff= 2 , 0
       0                  512.71       0     570
Permanent Ineff=
       F       T
Bank Sta=197.16,437.13
XS Rating Curve= 0 ,0
Exp/Cntr=0.3,0.1

Type RM Length L Ch R = 1 ,281757  ,171,171,187
BEGIN DESCRIPTION:
This cross section corresponds to cross section 281636.1 of the non-georeferenced CDC model which was the source of this model.
Effective flow limit set at White Settlement Levee in ROB.
END DESCRIPTION:
XS GIS Cut Line= 2
 2307587.0099465  6958767.245739 2307919.8193587   6958312.00839
#Sta/Elev= 30
       0  576.88   39.31     576   69.83  574.95   91.18  574.07     112  566.97
  132.45  564.93  160.49  562.43  174.55  561.54  195.84  556.35  204.36  555.66
  254.98   551.4  298.59  535.87  325.44  527.89   330.1     522  338.08     522
  343.89  522.74  364.53   520.6  375.68     520   392.9  519.42  394.18  519.24
  397.13  519.27  408.75  520.19  425.47     522  431.65  527.69  452.76     536
  477.63   544.7  519.29  545.01  549.88     558  556.98     560  563.92     560
#Mann= 4 ,-1,0
       0     .08       0  204.36    .055       0  254.98    .035       0
  477.63    .055       0
#XS Ineff= 2 , 0
       0                  556.98       0     570
Permanent Ineff=
       F       T
Bank Sta=254.98,477.63
XS Rating Curve= 0 ,0
Exp/Cntr=0.3,0.1

Type RM Length L Ch R = 1 ,281586  ,219,219,290
BEGIN DESCRIPTION:
This cross section corresponds to cross section 281464.6 of the non-georeferenced CDC model which was the source of this model.
Effective flow limit set at White Settlement Levee in ROB.
END DESCRIPTION:
XS GIS Cut Line= 2
 2307720.6320901 6958839.1961639 2308077.8895985 6958406.6984172
#Sta/Elev= 30
       0  575.85   66.55     574   82.97  569.07   92.67     568  119.13     566
  169.89  563.13  192.87  554.71  198.58  554.08  218.78  551.87     242  544.78
  252.35  539.94  264.59  539.09  274.73  535.11  284.91  531.96     297     522
  297.23  523.03  297.64  522.43   329.7  519.53  351.31  518.44  364.69  518.46
  377.32  517.53  385.44     520  389.96     522  394.16     526  436.82  540.29
  482.84  542.18  505.44  544.92   519.6  547.05  550.39  558.57  560.97     558
#Mann= 4 ,-1,0
       0     .08       0  198.58    .055       0     242    .035       0
  436.82    .055       0
#XS Ineff= 2 , 0
       0                  550.39       0     560
Permanent Ineff=
       F       T
Bank Sta=242,436.82
XS Rating Curve= 0 ,0
Exp/Cntr=0.3,0.1

Type RM Length L Ch R = 1 ,281367  ,50,50,50
BEGIN DESCRIPTION:
This cross section corresponds to cross section 281245.5 of the non-georeferenced CDC model which was the source of this model.
Ineffective flow in ROB.
White Settlement Levee in ROB.
END DESCRIPTION:
XS GIS Cut Line= 2
 2307912.1709994 6958861.5224814 2308491.4697189 6958421.3166125
#Sta/Elev= 30
       0  570.45   31.14  567.99   66.59  564.25   79.38  556.67   90.52  550.78
  107.34  547.92  143.83  534.66  178.96  528.66  185.69     522  188.58  522.21
   197.4  521.07  216.96   520.9  244.73  518.91  277.79  517.95  302.31     522
  313.96   527.4  334.05  527.28  337.97   526.5  340.19     520  460.78     520
  475.32  523.91  501.36  529.34  548.34   544.1  567.66   544.7  605.99  547.92
   675.3     548  685.24     550  694.48   552.8  715.85     558  727.58     558
#Mann= 4 ,-1,0
       0     .08       0   79.38    .055       0  107.34    .035       0
  313.96    .055       0
#XS Ineff= 1 ,-1
  486.62  727.58     560
Permanent Ineff=
       F
Bank Sta=107.34,313.96
XS Rating Curve= 0 ,0
Exp/Cntr=0.5,0.3

Type RM Length L Ch R = 1 ,281317  ,37,37,42
BEGIN DESCRIPTION:
This cross section corresponds to cross section 281195.4 of the non-georeferenced CDC model which was the source of this model.
Upstream of Tucker Dam.
Dowsntream of Sump 7W and Sump 8W outfall channel.
Ineffective flow in ROB.
White Settlement Levee in ROB.
END DESCRIPTION:
XS GIS Cut Line= 2
 2307942.4224525 6958901.3326335 2308489.7185742 6958485.4453527
#Sta/Elev= 30
       0  572.94    5.15  571.48   73.53  563.37   86.34  557.18   88.25  556.25
   99.11  548.01  112.92  546.28     145  533.71  178.39  530.18  189.56     526
  207.79     522  237.29  521.26  284.38  521.24  302.97     522  305.61     524
  309.82     526  375.48     530  397.53  531.91  418.05  536.25  436.31     544
  449.92  546.95   459.3  547.97  519.91  547.24  545.88     548  569.21  547.18
  585.01     548  629.75     548  643.72     550  674.81     558  687.38     558
#Mann= 4 ,-1,0
       0     .08       0   86.34    .055       0  112.92    .035       0
  449.92    .055       0
#XS Ineff= 1 ,-1
  489.22  687.38     560
Permanent Ineff=
       F
Bank Sta=112.92,449.92
XS Rating Curve= 0 ,0
Exp/Cntr=0.5,0.3

Type RM Length L Ch R = 5 ,281285  ,,,
BEGIN DESCRIPTION:
Tucker Dam
Constructed by TRWD.  Top of dam road surface elevation suveyed by TRWD May 2007.
END DESCRIPTION:
Node Name=Tucker Dam
IW Pilot Flow=0
#Inline Weir SE= 2
     100   526.5     500   526.5
IW Dist,WD,Coef,Skew,MaxSub,Min_El,Is_Ogee,SpillHt,DesHd
8,11.4,3,0,0.95,, 0 ,,,2,2,
Inline Weir Flap Gates= 0
IW Outlet Rating Curve= 0 ,False,,

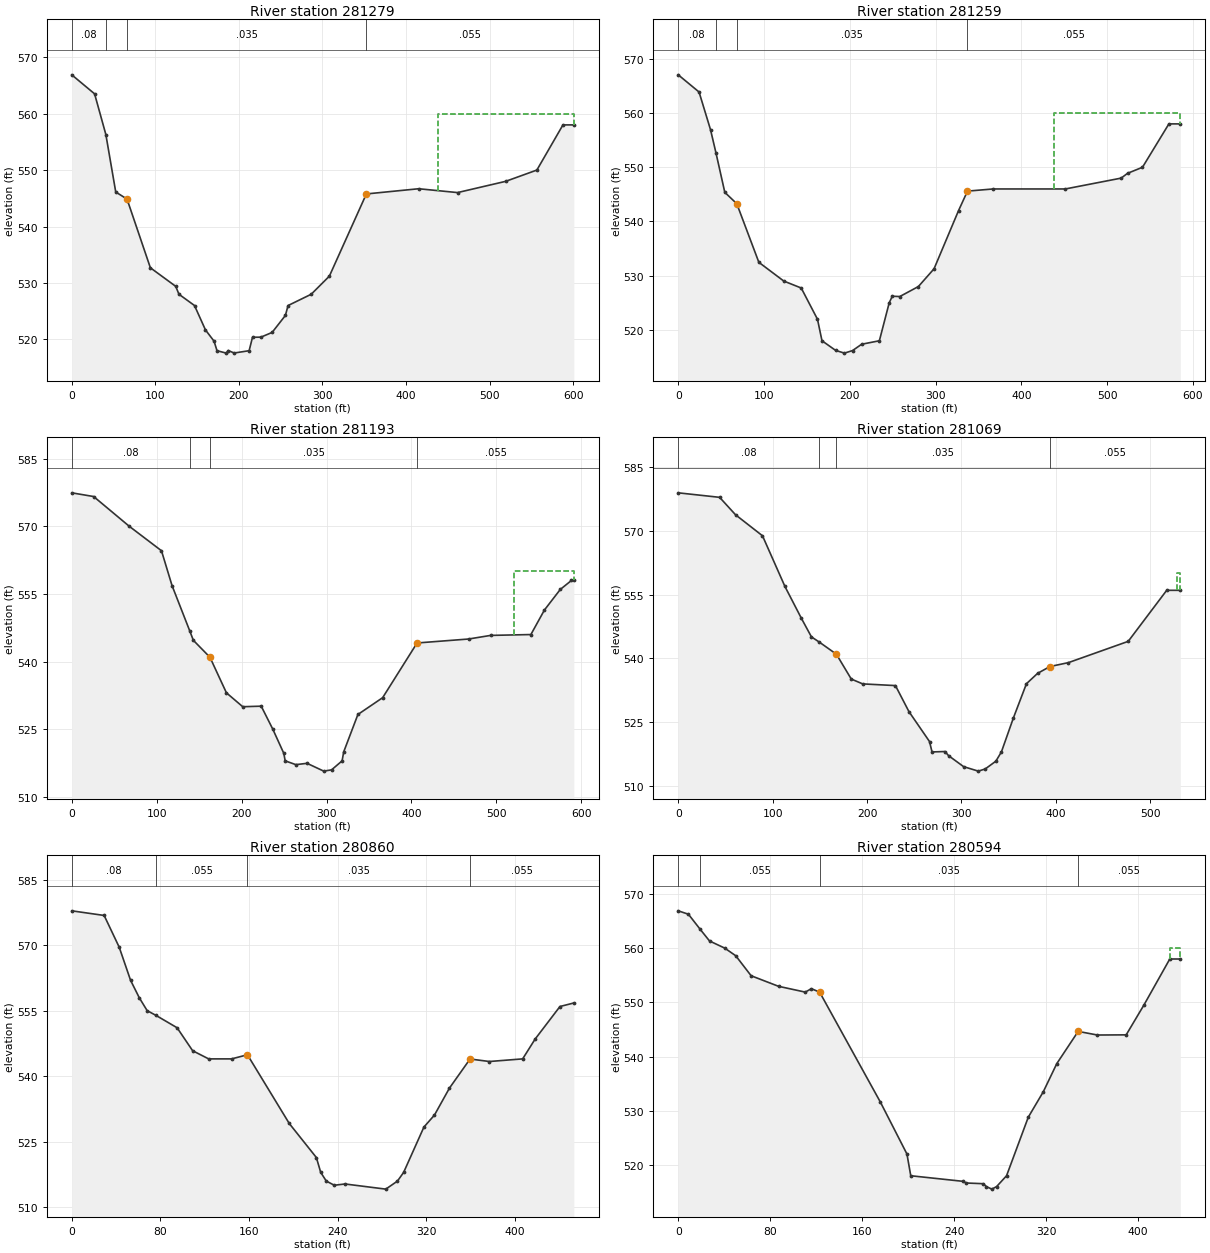
Type RM Length L Ch R = 1 ,281279  ,20,20,20
BEGIN DESCRIPTION:
This cross section corresponds to cross section 281157.9 of the non-georeferenced CDC model which was the source of this model.
Downstream of Tucker Dam.
Ineffective flow in ROB.
White Settlement Levee in ROB.
END DESCRIPTION:
XS GIS Cut Line= 2
 2308002.8986532 6958897.6706305 2308488.1401067 6958543.2515374
#Sta/Elev= 30
       0  566.87   27.32   563.5    40.8  556.29   52.63  546.11   66.14  544.86
   94.07  532.69  124.42   529.4  128.28     528   146.9     526     160  521.68
  170.28  519.69  173.82     518  185.01  517.57  187.22  518.03  194.35  517.59
  212.27     518   216.3  520.38  226.38   520.4   239.8  521.24  255.69  524.25
  258.86     526  286.57     528  308.31  531.21  352.56  545.77  415.19  546.69
  461.69  546.01  519.27     548  556.64     550  587.86     558  600.89     558
#Mann= 4 ,-1,0
       0     .08       0    40.8    .055       0   66.14    .035       0
  352.56    .055       0
#XS Ineff= 1 ,-1
  438.68  600.89     560
Permanent Ineff=
       F
Bank Sta=66.14,352.56
XS Rating Curve= 0 ,0
Exp/Cntr=0.5,0.3

Type RM Length L Ch R = 1 ,281259  ,66,66,120
BEGIN DESCRIPTION:
This cross section corresponds to cross section 281137.8 of the non-georeferenced CDC model which was the source of this model.
Ineffective flow in ROB.
White Settlement Levee in ROB.
END DESCRIPTION:
XS GIS Cut Line= 2
 2308014.6950269 6958913.8212719 2308487.4500458 6958568.5223138
#Sta/Elev= 30
       0  567.05   24.28  563.88   37.66  556.92   43.97  552.67    54.3  545.38
   68.29  543.27      94  532.47  123.09  529.01  143.41  527.73  162.36  521.97
  167.62     518  183.55  516.22   193.8  515.72  203.23  516.19  213.88  517.36
  234.52     518     246     525  249.58  526.21  258.36  526.16  280.01     528
   298.3  531.28  326.83     542  337.26   545.6  367.26     546  451.35     546
  516.47     548  523.86  548.88  541.32     550  572.12     558  585.43     558
#Mann= 4 ,-1,0
       0     .08       0   43.97    .055       0   68.29    .035       0
  337.26    .055       0
#XS Ineff= 1 ,-1
  438.16  585.43     560
Permanent Ineff=
       F
Bank Sta=68.29,337.26
XS Rating Curve= 0 ,0
Exp/Cntr=0.3,0.1

Type RM Length L Ch R = 1 ,281193  ,124,124,164
BEGIN DESCRIPTION:
This cross section corresponds to cross section 281071.7 of the non-georeferenced CDC model which was the source of this model.
Ineffective flow in ROB.
White Settlement Levee in ROB.
END DESCRIPTION:
XS GIS Cut Line= 2
 2307956.8233752 6958980.9902732 2308483.5235821 6958712.3127124
#Sta/Elev= 30
       0  577.42   25.74   576.6   67.73     570  105.64  564.58  118.09  556.85
  138.77  546.89   143.2  544.72  162.71  540.97  182.13  533.08  201.33     530
  223.11  530.12  236.85  524.98  249.75  519.64   251.3     518  263.86  517.16
  277.12  517.45  296.72  515.72  305.95     516  318.36     518  320.24  519.99
  336.97  528.28  366.09     532  406.63  544.13  467.28  545.01  493.24  545.81
  540.68     546  556.63  551.44   575.3     556  588.49     558  591.27     558
#Mann= 4 ,-1,0
       0     .08       0  138.77    .055       0  162.71    .035       0
  406.63    .055       0
#XS Ineff= 1 ,-1
  520.44  591.27     560
Permanent Ineff=
       F
Bank Sta=162.71,406.63
XS Rating Curve= 0 ,0
Exp/Cntr=0.3,0.1

Type RM Length L Ch R = 1 ,281069  ,209,209,223
BEGIN DESCRIPTION:
This cross section corresponds to cross section 280947.3 of the non-georeferenced CDC model which was the source of this model.
Ineffective flow in ROB.
White Settlement Levee in ROB.
END DESCRIPTION:
XS GIS Cut Line= 2
 2307972.8526758 6959050.4508783 2308481.5887408 6958895.6736928
#Sta/Elev= 30
       0  578.92   43.83  577.86   60.69  573.76   89.24  568.82  113.02   556.9
  130.52  549.38  141.08  545.05  149.26  543.85  167.51  540.98  183.26  535.14
  195.37     534  230.06   533.6  244.33  527.49  266.13  520.45   268.8     518
  282.52   518.1  286.35  517.12  302.28  514.54  317.79  513.49  325.14     514
  336.42  515.83  342.27     518  354.99     526  368.79  534.04  380.57  536.47
  393.67  538.08  413.25     539  476.58     544  517.35     556  531.76     556
#Mann= 4 ,-1,0
       0     .08       0  149.26    .055       0  167.51    .035       0
  393.67    .055       0
#XS Ineff= 1 ,-1
  527.77  531.76     560
Permanent Ineff=
       F
Bank Sta=167.51,393.67
XS Rating Curve= 0 ,0
Exp/Cntr=0.3,0.1

Type RM Length L Ch R = 1 ,280860  ,265,265,266
BEGIN DESCRIPTION:
This cross section corresponds to cross section 280738.3 of the non-georeferenced CDC model which was the source of this model.
Effective flow limit set at White Settlement Levee in ROB.
END DESCRIPTION:
XS GIS Cut Line= 2
 2308074.3721415 6959222.7666054 2308514.2928077 6959114.3990333
#Sta/Elev= 30
       0  577.92   29.22  576.86   42.79   569.6   53.07     562   60.93     558
   68.04  555.05   75.89  553.98   95.05  551.13  109.07  545.87  123.52     544
  144.21     544  158.53  544.94  196.26   529.2  220.72   521.4  224.64     518
  229.69     516  236.92  515.05  246.57  515.34  283.38  514.16  293.89     516
  299.48     518  317.78  528.38   327.3  531.13  340.78  537.29   359.4  543.97
  376.87   543.4  406.88     544   418.1  548.53  440.54     556  453.07  556.81
#Mann= 4 ,-1,0
       0     .08       0   75.89    .055       0  158.53    .035       0
   359.4    .055       0
Bank Sta=158.53,359.4
XS Rating Curve= 0 ,0
Exp/Cntr=0.3,0.1

Type RM Length L Ch R = 1 ,280594  ,307,307,300
BEGIN DESCRIPTION:
This cross section corresponds to cross section 280473 of the non-georeferenced CDC model which was the source of this model.
Effective flow limit set at White Settlement Levee in ROB.
END DESCRIPTION:
XS GIS Cut Line= 2
 2308161.1978331 6959473.8934386  2308585.569506 6959370.3881841
#Sta/Elev= 30
       0  566.89    8.87  566.26   19.13  563.47   27.21  561.33   40.53     560
   50.03   558.6   63.41  554.91   87.26  552.96  110.49  551.89  115.85  552.52
  123.03  551.88  175.93  531.57  198.98  522.01   202.3     518  247.67  516.97
  250.68  516.66  265.42  516.53  268.07     516  272.85  515.53  276.98     516
  285.64     518  304.55  528.81  317.61   533.5  329.34  538.69  347.94  544.64
  364.66  543.97  389.72     544  405.22  549.53  427.66     558  436.81     558
#Mann= 4 ,-1,0
       0     .08       0   19.13    .055       0  123.03    .035       0
  347.94    .055       0
#XS Ineff= 2 , 0
       0                  427.66       0     560
Permanent Ineff=
       F       T
Bank Sta=123.03,347.94
XS Rating Curve= 0 ,0
Exp/Cntr=0.3,0.1

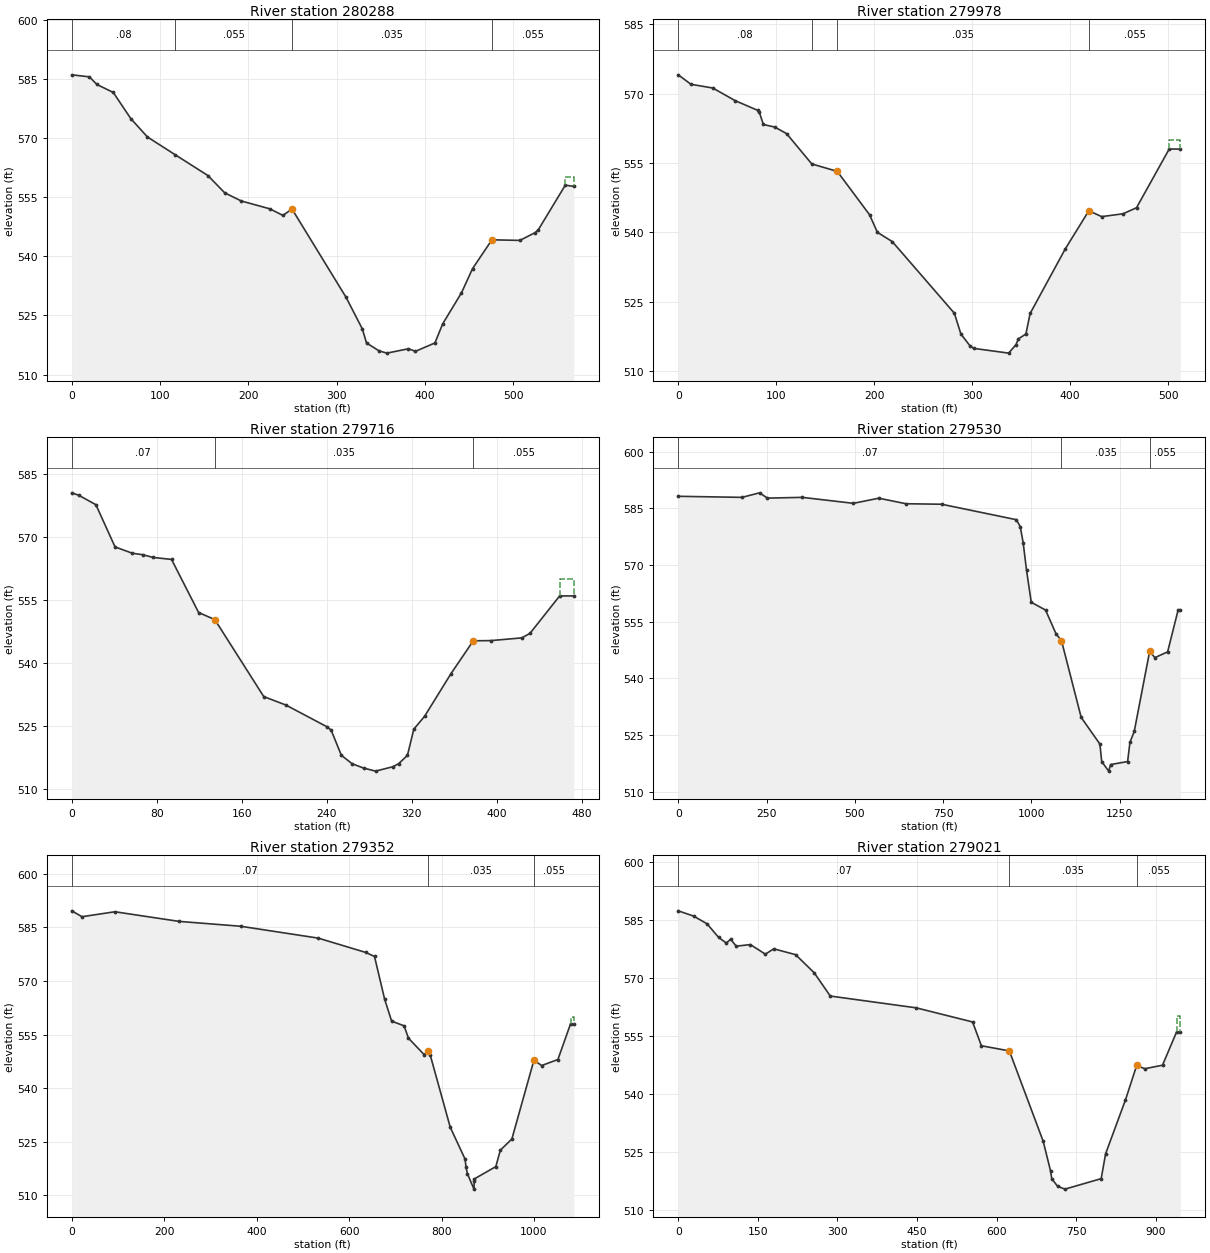
Type RM Length L Ch R = 1 ,280288  ,310,310,301
BEGIN DESCRIPTION:
This cross section corresponds to cross section 280166.3 of the non-georeferenced CDC model which was the source of this model.
Effective flow limit set at White Settlement Levee in ROB.
END DESCRIPTION:
XS GIS Cut Line= 2
 2308120.4006204 6959808.1059186 2308669.6157675 6959660.9947231
#Sta/Elev= 30
       0  585.98   19.98  585.47   28.48  583.53   47.01  581.51   66.84  574.88
   85.71  570.22   116.9  565.75   154.2  560.44  173.23  556.06  191.89     554
  224.37     552  239.13  550.33  249.39  551.96  310.63  529.57  329.09  521.54
  333.77     518  347.95     516  356.86  515.42  381.33  516.53  389.24  515.88
  411.26     518  420.07  522.85  441.31   530.7  453.86  536.84   475.8  544.15
  507.44     544  524.96     546  528.43  546.73  558.89     558  568.58   557.7
#Mann= 4 ,-1,0
       0     .08       0   116.9    .055       0  249.39    .035       0
   475.8    .055       0
#XS Ineff= 2 , 0
       0                  558.89       0     560
Permanent Ineff=
       F       T
Bank Sta=249.39,475.8
XS Rating Curve= 0 ,0
Exp/Cntr=0.3,0.1

Type RM Length L Ch R = 1 ,279978  ,261,261,242
BEGIN DESCRIPTION:
This cross section corresponds to cross section 279856.3 of the non-georeferenced CDC model which was the source of this model.
Effective flow limit set at White Settlement Levee in ROB.
END DESCRIPTION:
XS GIS Cut Line= 2
 2308263.6514673 6960098.4885734 2308755.3941169 6959953.9852975
#Sta/Elev= 30
       0  574.05   13.04     572   35.27   571.2   58.07  568.47   81.12  566.37
   82.56   566.1   86.92  563.31   98.53  562.75  110.61  561.34  136.33  554.78
  162.34  553.17  195.31  543.79  203.27     540  218.54  537.98  281.89   522.5
  288.56     518     298   515.4  301.55   514.9  337.29  513.87  344.81  515.71
  347.23  516.95  354.89     518  359.24  522.45  395.03  536.38  419.17  544.66
  432.25  543.39  454.04     544  467.83  545.31  501.17     558  512.54     558
#Mann= 4 ,-1,0
       0     .08       0  136.33    .055       0  162.34    .035       0
  419.17    .055       0
#XS Ineff= 2 , 0
       0                  501.17       0     560
Permanent Ineff=
       F       T
Bank Sta=162.34,419.17
XS Rating Curve= 0 ,0
Exp/Cntr=0.3,0.1

Type RM Length L Ch R = 1 ,279716  ,187,187,112
BEGIN DESCRIPTION:
This cross section corresponds to cross section 279595 of the non-georeferenced CDC model which was the source of this model.
Effective flow limit set at White Settlement Levee in ROB.
END DESCRIPTION:
XS GIS Cut Line= 2
 2308390.9522222 6960355.5088616 2308833.1243047 6960188.7014363
#Sta/Elev= 30
       0  580.58    6.58     580    22.7  577.75   40.76  567.68   56.98  566.18
   67.17  565.81   76.44  565.18   93.92   564.7  119.41  552.04  134.63  550.36
  180.71     532  201.43     530  240.17  524.81  244.11  524.02  253.77     518
  263.84     516  274.69  514.96  285.98  514.23  302.11  515.27  307.67     516
  315.97     518  321.94  524.23  332.09   527.3  356.99  537.49  377.93   545.3
   394.6  545.35  423.62     546  431.32  547.08  459.22     556  472.59     556
#Mann= 3 ,-1,0
       0     .07       0  134.63    .035       0  377.93    .055       0
#XS Ineff= 2 , 0
       0                  459.22       0     560
Permanent Ineff=
       F       T
Bank Sta=134.63,377.93
XS Rating Curve= 0 ,0
Exp/Cntr=0.3,0.1

Type RM Length L Ch R = 1 ,279530  ,177,177,135
BEGIN DESCRIPTION:
This cross section corresponds to cross section 279408.3 of the non-georeferenced CDC model which was the source of this model.
Effective flow limit set at White Settlement Levee in ROB.
END DESCRIPTION:
XS GIS Cut Line= 2
  2307822.636919  6961217.162946 2308900.0188632 6960289.7962092
#Sta/Elev= 30
       0  588.22  180.48  587.94  230.32  589.14  252.47  587.74  351.04  587.94
  495.84  586.36  567.95  587.72  644.88  586.25  745.79  586.12  957.13  582.03
  968.31  580.21  976.69  575.87  986.23  568.58  999.46  560.17 1040.03   558.1
  1069.4  551.86 1085.08     550 1140.89  529.68 1193.93  522.61 1198.98     518
 1218.69  515.46  1224.2   517.2  1272.4     518 1278.85  523.06 1291.12  525.98
 1334.69  547.17  1349.5   545.5 1385.65  547.04 1415.02     558 1421.53     558
#Mann= 3 ,-1,0
       0     .07       0 1085.08    .035       0 1334.69    .055       0
Bank Sta=1085.08,1334.69
XS Rating Curve= 0 ,0
Exp/Cntr=0.3,0.1

Type RM Length L Ch R = 1 ,279352  ,332,332,302
BEGIN DESCRIPTION:
This cross section corresponds to cross section 279230.9 of the non-georeferenced CDC model which was the source of this model.
Effective flow limit set at White Settlement Levee in ROB.
END DESCRIPTION:
XS GIS Cut Line= 2
 2308315.4489492 6961219.6497841 2309009.7432223  6960384.142956
#Sta/Elev= 30
       0  589.65    22.1     588   93.29  589.39  231.64   586.7  365.28  585.33
  533.35     582  635.96     578  655.02  576.86   676.9  564.91  692.05  558.76
  719.12  557.43  728.38     554  762.38  549.37  770.08   550.3  775.68  549.21
  818.87  529.04   851.2  520.03   852.8     518  856.08     516  870.26  511.69
   870.8     514  871.16  514.56  917.49     518  927.39  522.62   952.2  525.72
   999.9  547.77 1016.85  546.32 1051.87     548 1079.22     558 1086.33     558
#Mann= 3 ,-1,0
       0     .07       0  770.08    .035       0   999.9    .055       0
#XS Ineff= 2 , 0
       0                 1079.22       0     560
Permanent Ineff=
       F       T
Bank Sta=770.08,999.9
XS Rating Curve= 0 ,0
Exp/Cntr=0.3,0.1

Type RM Length L Ch R = 1 ,279021  ,268,268,257
BEGIN DESCRIPTION:
This cross section corresponds to cross section 278899.3 of the non-georeferenced CDC model which was the source of this model.
Effective flow limit set at White Settlement Levee in ROB.
END DESCRIPTION:
XS GIS Cut Line= 2
 2308748.3409239 6961337.2925376 2309271.8808253 6960549.2199786
#Sta/Elev= 30
       0  587.35   28.77     586   54.21     584   76.21  580.45   90.83     579
   98.58     580  109.27   578.2  136.04  578.61   164.1  576.13  180.01  577.51
  221.16     576  256.37  571.28  286.53  565.28  448.35  562.23   554.7  558.57
  571.27  552.41  623.98  551.07  687.73  527.67   701.5  520.05  703.84     518
  714.92     516  728.88  515.28  797.02     518  805.38  524.46  842.81   538.4
  863.88   547.3  879.26  546.46  912.56  547.37  939.16     556  946.12     556
#Mann= 3 ,-1,0
       0     .07       0  623.98    .035       0  863.88    .055       0
#XS Ineff= 2 , 0
       0                  939.16       0     560
Permanent Ineff=
       F       T
Bank Sta=623.98,863.88
XS Rating Curve= 0 ,0
Exp/Cntr=0.3,0.1