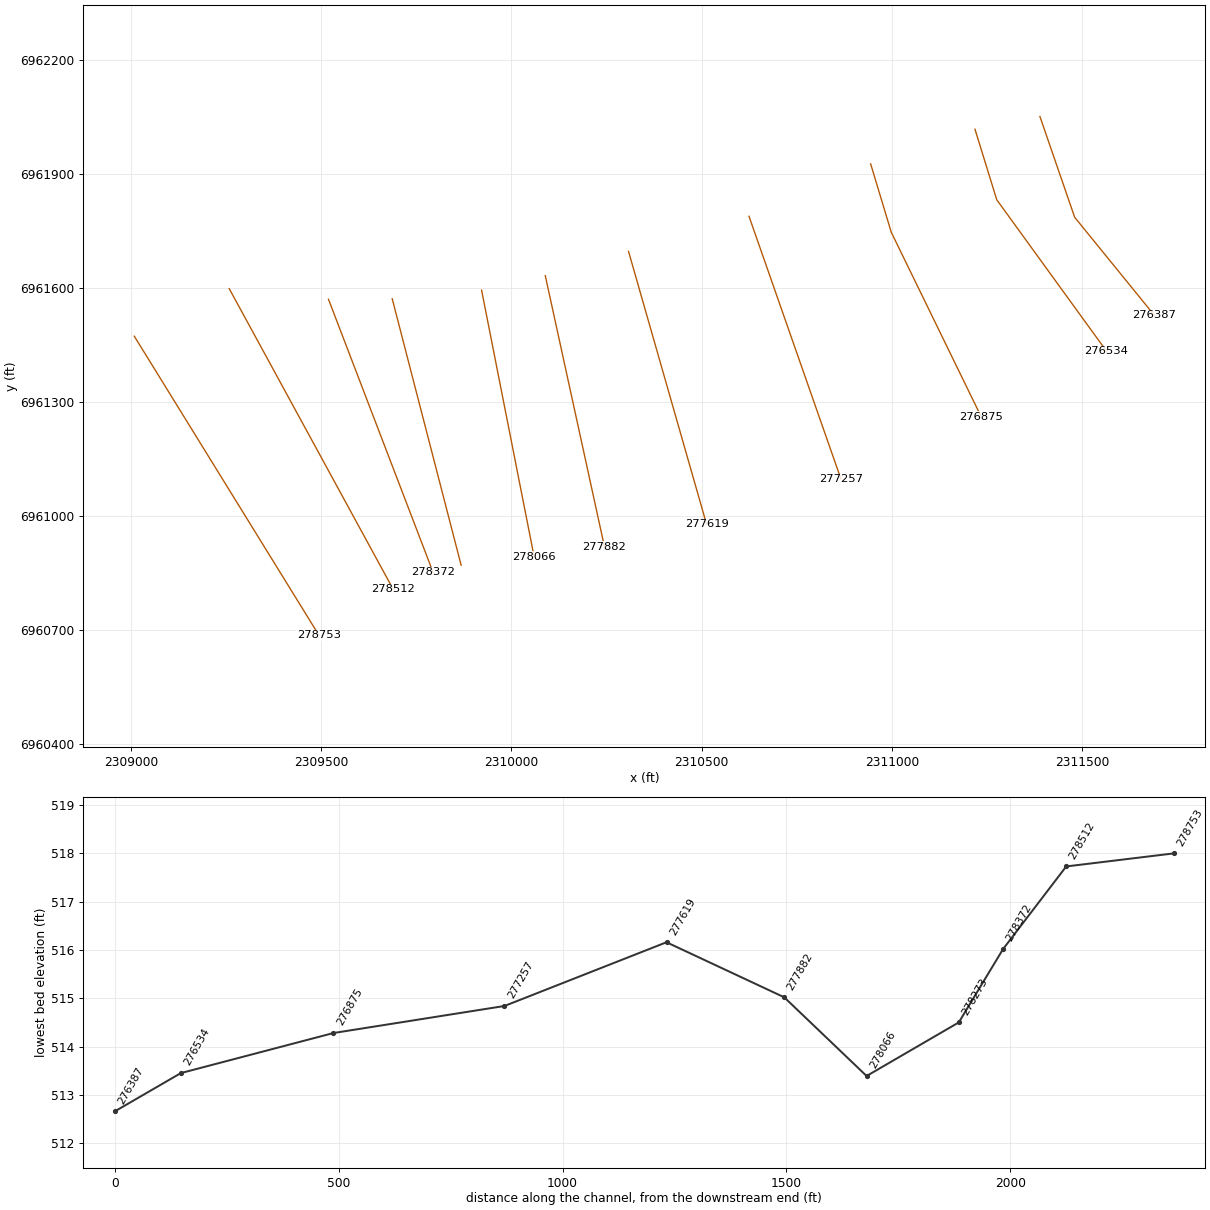
HEC-RAS study CDC_Consolidated_Model.prj: Upper Trinity CDC Consolidated Model

--- CDC_Consolidated_Model.g03 (geometry) --- (continued)

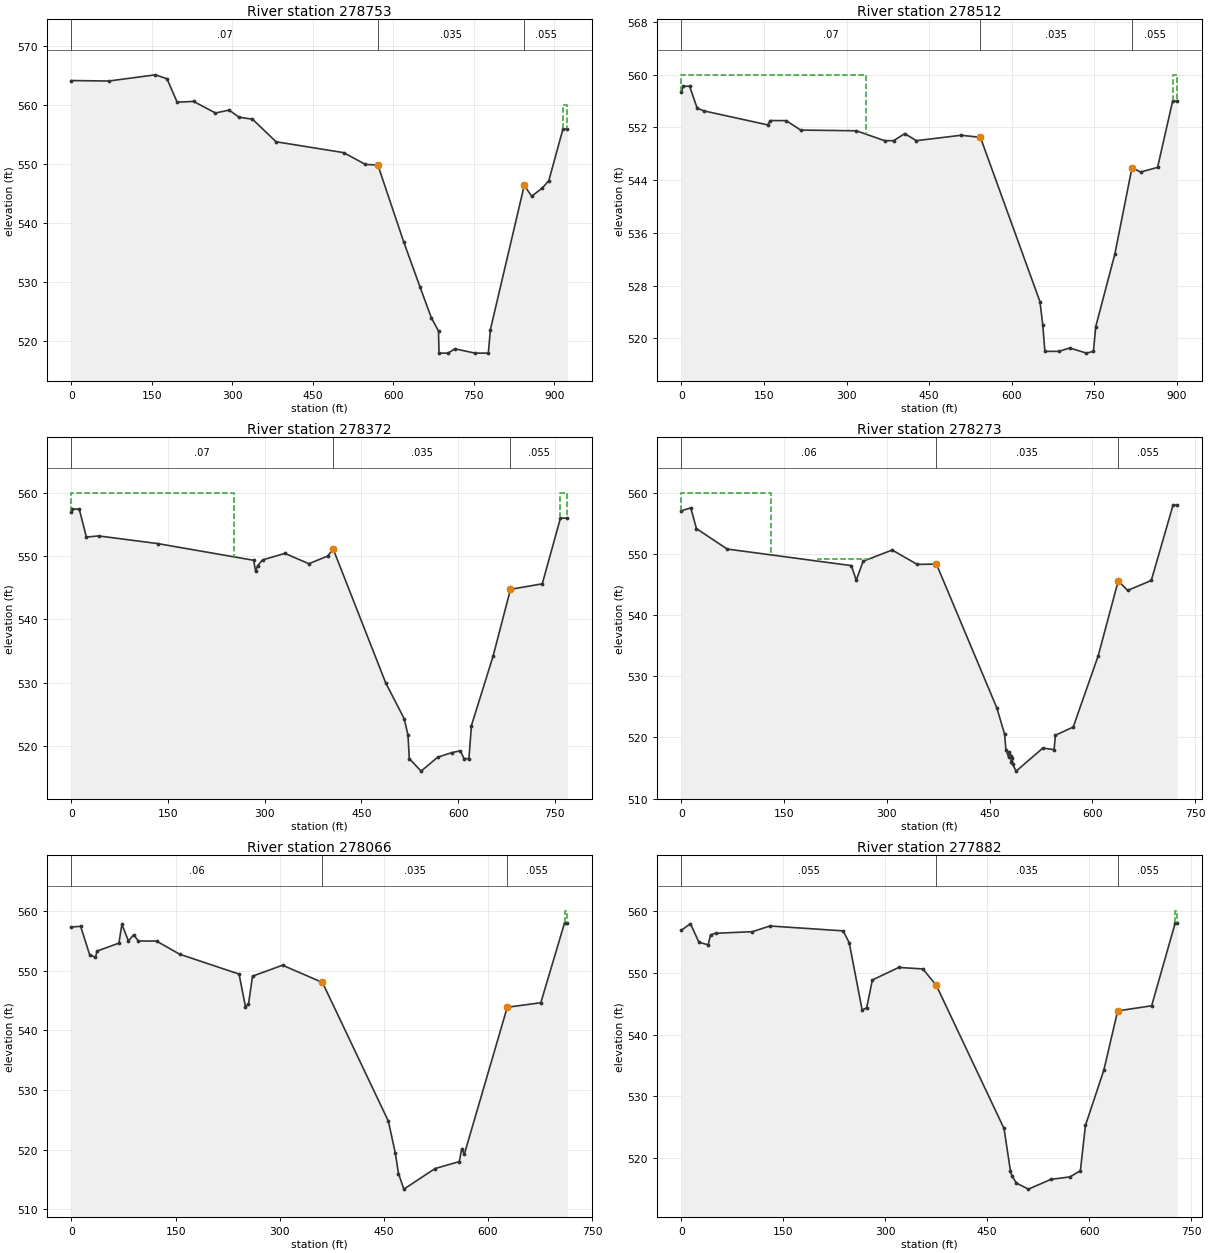
Type RM Length L Ch R = 1 ,278753  ,240,240,223
BEGIN DESCRIPTION:
This cross section corresponds to cross section 278631.3 of the non-georeferenced CDC model which was the source of this model.
Effective flow limit set at White Settlement Levee in ROB.
END DESCRIPTION:
XS GIS Cut Line= 2
 2309008.6337837 6961473.5931238 2309493.9108876 6960686.9744505
#Sta/Elev= 30
       0  564.22   69.51  564.14  156.34  565.19  178.04  564.52     197  560.55
   227.5  560.68  268.42  558.72   293.7  559.21  312.35     558  337.35  557.67
  381.31  553.84  507.12     552  547.88     550  571.08  549.88  618.99  536.92
   649.7  529.19  670.64     524  684.02  521.75     685     518  701.93     518
   714.6  518.73  752.05     518  776.87     518  780.75     522  843.87  546.45
  857.69   544.6  877.55     546  889.59  547.25  915.96     556  924.26     556
#Mann= 3 ,-1,0
       0     .07       0  571.08    .035       0  843.87    .055       0
#XS Ineff= 2 , 0
       0                  915.96       0     560
Permanent Ineff=
       F       T
Bank Sta=571.08,843.87
XS Rating Curve= 0 ,0
Exp/Cntr=0.3,0.1

Type RM Length L Ch R = 1 ,278512  ,141,141,103
BEGIN DESCRIPTION:
This cross section corresponds to cross section 278390.9 of the non-georeferenced CDC model which was the source of this model.
Effective flow limit set at Brookside Levee in LOB.
Effective flow limit set at White Settlement Levee in ROB.
END DESCRIPTION:
XS GIS Cut Line= 2
  2309258.144036 6961598.7313939 2309689.1438203 6960807.6631691
#Sta/Elev= 30
       0  557.39    3.33  558.26   15.01  558.27   28.74  554.93   40.59  554.53
  156.64   552.4  161.72  553.06  190.53  553.04  216.56  551.61  317.87   551.5
  369.08     550  385.62     550  405.69  551.07  426.88     550  508.11  550.82
  543.16  550.51  651.37  525.55  656.49  522.01  660.33     518  685.98     518
  705.44  518.51   735.9  517.73  748.47     518  752.71  521.76  787.36  532.76
  818.49  545.88  834.28  545.24  865.02  545.94  892.31     556  900.86     556
#Mann= 3 ,-1,0
       0     .07       0  543.16    .035       0  818.49    .055       0
#XS Ineff= 2 ,-1
       0  335.04     560  892.31  900.86     560
Permanent Ineff=
       F       T
Bank Sta=543.16,818.49
XS Rating Curve= 0 ,0
Exp/Cntr=0.3,0.1

Type RM Length L Ch R = 1 ,278372  ,99,99,68
BEGIN DESCRIPTION:
This cross section corresponds to cross section 278250.3 of the non-georeferenced CDC model which was the source of this model.
Effective flow limit set at Brookside Levee in LOB.
Effective flow limit set atWhite Settlement Levee in ROB.
END DESCRIPTION:
XS GIS Cut Line= 2
 2309519.0454148 6961570.8132881 2309794.1082756 6960851.9975438
#Sta/Elev= 30
       0  557.03      .8  557.41   12.02  557.45   23.12  553.01   42.08  553.19
  133.79  551.98  282.76  549.34  285.84  547.59  288.74  548.47   296.6   549.4
  331.24  550.43  368.36   548.8  397.52     550  406.12  551.13  487.53     530
  516.31  524.31  522.24  521.74  524.25     518   542.6  516.02  568.37  518.22
  590.15  518.94  603.56  519.24  609.13     518  616.83     518  620.72  523.23
  654.29  534.18  681.29  544.75  730.62  545.62  758.85     556  769.65     556
#Mann= 3 ,-1,0
       0     .07       0  406.12    .035       0  681.29    .055       0
#XS Ineff= 2 ,-1
       0  252.42     560  758.85  769.65     560
Permanent Ineff=
       F       T
Bank Sta=406.12,681.29
XS Rating Curve= 0 ,0
Exp/Cntr=0.3,0.1

Type RM Length L Ch R = 1 ,278273  ,206,206,188
BEGIN DESCRIPTION:
This cross section corresponds to cross section 278151.2 of the non-georeferenced CDC model which was the source of this model.
Effective flow limit set at Brookside Levee in LOB.
Effective flow limit set at White Settlement Levee in ROB.
White Settlement Road in LOB - drainage ditch to the west non-effective up to elevation 549.14.
END DESCRIPTION:
XS GIS Cut Line= 2
 2309686.5618282 6961572.2049477 2309867.7214325 6960871.1959653
#Sta/Elev= 30
       0  557.07   13.77  557.54      22  554.15    66.9  550.81  248.12   548.1
  255.36  545.71  265.35  548.82  307.77  550.65  344.34   548.3  372.37  548.35
  460.69   524.8  471.88  520.55  473.86     518  477.78  516.79  478.49  517.67
  481.46  517.01  481.59     516  483.15  516.57  483.78  515.59  488.71   514.5
  527.87  518.28  544.11     518  546.12  520.37  572.07  521.71  608.51  533.34
  637.81  545.62  651.55  544.04  686.05  545.67  717.82     558  724.04     558
#Mann= 3 ,-1,0
       0     .06       0  372.37    .035       0  637.81    .055       0
#XS Ineff= 2 ,-1
       0   130.2     560     200     280  549.14
Permanent Ineff=
       F       F
Bank Sta=372.37,637.81
XS Rating Curve= 0 ,0
Exp/Cntr=0.3,0.1

Type RM Length L Ch R = 1 ,278066  ,184,184,191
BEGIN DESCRIPTION:
This cross section corresponds to cross section 277944.9 of the non-georeferenced CDC model which was the source of this model.
Effective flow limit set at Brookside Levee in LOB.
Effective flow limit set at White Settlement Levee in ROB.
White Settlement Road in LOB - drainage ditch to the west non-effective up to elevation 550.
END DESCRIPTION:
XS GIS Cut Line= 2
 2309921.4986101 6961594.7631869 2310059.5551376 6960893.7612049
#Sta/Elev= 30
       0   557.3   13.24   557.4   26.13  552.67    34.6  552.22   36.81  553.26
   68.36  554.59   72.63  557.72   82.11  554.96   89.65  555.99   96.45  554.95
  122.61  554.93  155.93  552.73  241.45  549.41  250.64  543.95  255.03  544.36
  260.84  549.06   304.1  550.89  361.58     548  456.56  524.77  466.66  519.36
  471.12     516  478.86  513.39  523.87  516.84  558.67     518  562.14  520.07
  566.02  519.26  627.81  543.85  676.18  544.61   710.4     558  714.47     558
#Mann= 3 ,-1,0
       0     .06       0  361.58    .035       0  627.81    .055       0
#XS Ineff= 2 ,-1
   710.4  714.42     560     200     300     550
Permanent Ineff=
       T       F
Bank Sta=361.58,627.81
XS Rating Curve= 0 ,0
Exp/Cntr=0.3,0.1

Type RM Length L Ch R = 1 ,277882  ,263,263,286
BEGIN DESCRIPTION:
This cross section corresponds to cross section 277760.9 of the non-georeferenced CDC model which was the source of this model.
Effective flow limit set at Brookside Levee in LOB.
Effective flow limit set at White Settlement Levee in ROB.
White Settlement Road in LOB - drainage ditch to the west non-effective up to elevation 550.
END DESCRIPTION:
XS GIS Cut Line= 2
 2310088.9489083 6961632.8330838 2310244.4551757 6960919.9069054
#Sta/Elev= 30
       0  556.86    13.3  557.92   25.89  554.93   39.39   554.5   42.91  556.11
   50.23  556.37  104.47  556.63  130.27  557.55  238.11  556.76  246.98  554.84
     266  543.95   272.7  544.35  280.99  548.82  319.89  550.85  355.22  550.61
  374.88     548  474.72  524.82  484.13     518  486.13  517.21  492.92     516
  510.67  515.02  543.55  516.59   571.8     517  587.08     518  594.51  525.31
  621.64  534.27  641.94  543.83  691.93  544.65  726.53     558  729.69     558
#Mann= 3 ,-1,0
       0    .055       0  374.88    .035       0  641.94    .055       0
#XS Ineff= 2 ,-1
  726.53  729.69     560     250     350     550
Permanent Ineff=
       T       F
Bank Sta=374.88,641.94
XS Rating Curve= 0 ,0
Exp/Cntr=0.3,0.1

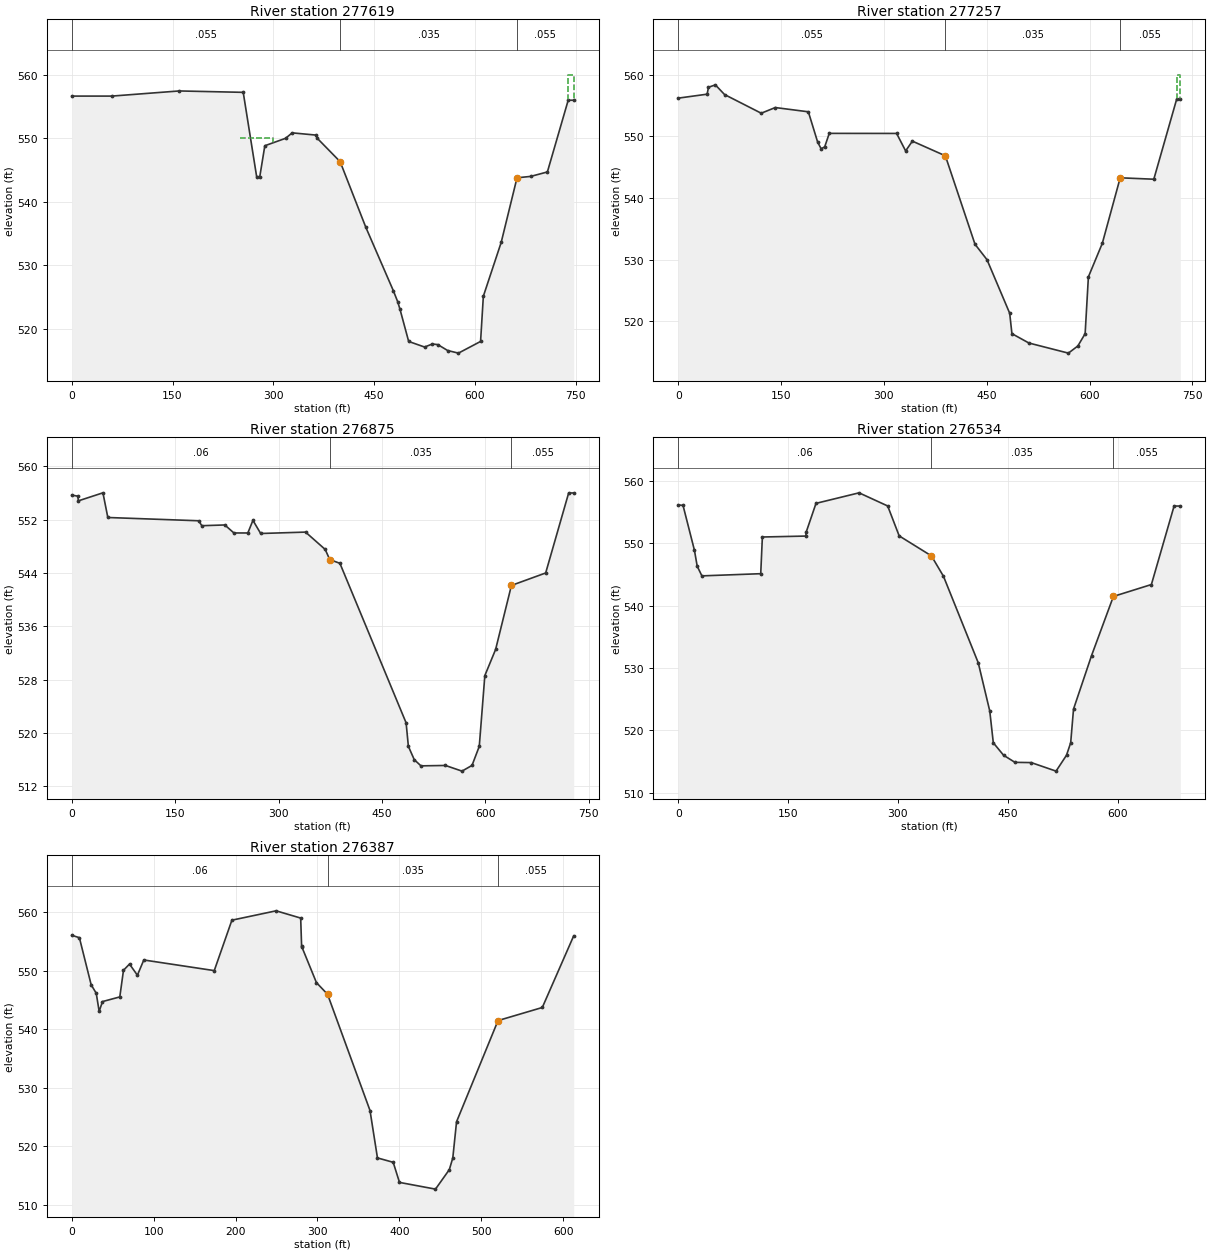
Type RM Length L Ch R = 1 ,277619  ,362,362,369
BEGIN DESCRIPTION:
This cross section corresponds to cross section 277497.7 of the non-georeferenced CDC model which was the source of this model.
Effective flow limit set at Brookside Levee in LOB.
Effective flow limit set at White Settlement Levee in ROB.
White Settlement Road in LOB - drainage ditch to the west non-effective up to elevation 550.
END DESCRIPTION:
XS GIS Cut Line= 2
  2310307.774718 6961696.7235501 2310512.9850792 6960978.4870266
#Sta/Elev= 30
       0  556.65   59.62  556.65  159.96  557.46  255.17  557.24  275.16  543.95
   279.8  543.95  287.32  548.83  318.25     550  327.99  550.86  363.13  550.51
  365.39     550   399.4  546.32  437.47  536.02  478.54     526  484.93  524.29
  488.47  523.07  501.38     518  525.05  517.12   536.7   517.6  544.81   517.5
  559.39  516.57  575.45  516.16  608.39     518  612.51  525.12  639.06   533.6
  662.63  543.78  683.03     544  707.82   544.7   738.8     556  746.98     556
#Mann= 3 ,-1,0
       0    .055       0   399.4    .035       0  662.63    .055       0
#XS Ineff= 2 ,-1
   738.8  746.98     560     250     300     550
Permanent Ineff=
       T       F
Bank Sta=399.4,662.63
XS Rating Curve= 0 ,0
Exp/Cntr=0.3,0.1

Type RM Length L Ch R = 1 ,277257  ,382,382,423
BEGIN DESCRIPTION:
This cross section corresponds to cross section 277135.4 of the non-georeferenced CDC model which was the source of this model.
Effective flow limit set at Brookside Levee in LOB.
Effective flow limit set at White Settlement Levee in ROB.
White Settlement Road in LOB - drainage ditch to the west non-effective up to elevation 550.
END DESCRIPTION:
XS GIS Cut Line= 2
 2310624.4098947 6961789.1712356 2310866.1313902 6961097.6937282
#Sta/Elev= 30
       0  556.22   41.97  556.86   43.93  557.98   53.96  558.37    67.4   556.8
  120.91  553.77  141.43  554.69  189.68     554  203.24  549.09  208.32     548
  213.53  548.31   220.2   550.5  318.48  550.49  331.65  547.65  341.48  549.24
  389.63  546.86  432.87  532.51   450.4     530  483.51  521.31  486.75     518
  511.54  516.48  569.18  514.84  582.98     516  593.61     518  598.35  527.21
  618.65  532.65  644.78  543.29  693.83  543.06  727.06     556  732.51     556
#Mann= 3 ,-1,0
       0    .055       0  389.63    .035       0  644.78    .055       0
#XS Ineff= 2 ,-1
  727.06  732.51     560     150     250     550
Permanent Ineff=
       T       F
Bank Sta=389.63,644.78
XS Rating Curve= 0 ,0
Exp/Cntr=0.3,0.1

Type RM Length L Ch R = 1 ,276875  ,341,341,426
BEGIN DESCRIPTION:
This cross section corresponds to cross section 276753.4 of the non-georeferenced CDC model which was the source of this model.
Upstream of Sump 9W outfall.
Effective flow limit set at Brookside Levee in LOB.
Effective flow limit set at White Settlement Levee in ROB.
END DESCRIPTION:
XS GIS Cut Line= 3
  2310944.246861 6961926.9049655 2310998.3936355 6961747.0903513
 2311234.9573693 6961261.2616395
#Sta/Elev= 30
       0  555.68    8.67  555.52    9.67  554.82   45.22  556.02   52.32  552.32
  184.05  551.83  188.67  551.09  222.03   551.2  235.22     550  255.44     550
  262.82  551.89  274.05  549.92  339.15  550.13  367.64  547.53  374.28     546
  388.98  545.45  485.03  521.52  488.31     518  496.84     516  506.57  515.07
  542.07  515.13  566.12  514.28  580.66  515.14  591.17     518  599.24  528.61
  614.87  532.53   637.8  542.13  687.49     544  720.84     556  728.15     556
#Mann= 3 ,-1,0
       0     .06       0  374.28    .035       0   637.8    .055       0
Bank Sta=374.28,637.8
XS Rating Curve= 0 ,0
Exp/Cntr=0.3,0.1

Type RM Length L Ch R = 1 ,276534  ,147,147,128
BEGIN DESCRIPTION:
This cross section corresponds to cross section 276412.8 of the non-georeferenced CDC model which was the source of this model.
Downstream of Sump 9W outfall.
Effective flow limit set at Brookside Levee in LOB.
Effective flow limit set at White Settlement Levee in ROB.
White Settlement Road in LOB - area to the west non-effective up to elevation 550.
END DESCRIPTION:
XS GIS Cut Line= 3
 2311218.4582621 6962018.1748934 2311275.6406306  6961832.629649
  2311563.972289 6961434.4576059
#Sta/Elev= 30
       0  556.19    6.37  556.09    21.9  548.92   25.73  546.34   32.12  544.79
  112.51  545.14  114.75  551.03  174.11  551.18  174.81  551.88  188.03  556.43
  246.87  558.12  285.96  556.01  301.65  551.21   345.7     548   362.2  544.72
  409.71  530.83   425.4  523.11  430.26     518  444.29     516  459.83  514.86
  482.08  514.82  515.98  513.45  530.26     516  535.97     518  539.86  523.41
   564.5     532  594.32  541.49  646.24   543.4  677.25     556  685.76     556
#Mann= 3 ,-1,0
       0     .06       0   345.7    .035       0  594.32    .055       0
#XS Ineff= 1 ,-1
       0     200     550
Permanent Ineff=
       F
Bank Sta=345.7,594.32
XS Rating Curve= 0 ,0
Exp/Cntr=0.5,0.3

Type RM Length L Ch R = 1 ,276387  ,115,115,229
BEGIN DESCRIPTION:
This cross section corresponds to cross section 276265.7 of the non-georeferenced CDC model which was the source of this model.
Effective flow limit set at Brookside Levee in LOB.
Effective flow limit set at White Settlement Levee in ROB.
White Settlement Road in LOB - area to the west non-effective up to elevation 550.
Reach lengths revised due to copy of cross-section 276307.7
END DESCRIPTION:
XS GIS Cut Line= 3
 2311389.1890398  6962051.578744 2311480.4838581 6961786.5467223
 2311690.0928232 6961528.3498432
#Sta/Elev= 30
       0   556.1    9.32  555.68   23.68  547.63    29.9  546.17   33.46  543.07
    37.5  544.75   58.65  545.55   63.16  550.11   70.51  551.17   80.15  549.26
   87.95  551.87     174  550.05  195.53  558.68  249.52  560.28  279.52  559.04
  280.64  554.25  281.11  554.05  298.74     548  312.32     546  364.17  526.11
  373.26     518  392.48  517.25  400.17  513.81  444.12  512.66  461.03     516
  465.26     518  469.84  524.19  520.47   541.5  574.54  543.74  612.88     556
#Mann= 3 ,-1,0
       0     .06       0  312.32    .035       0  520.47    .055       0
#XS Ineff= 1 ,-1
       0     200     550
Permanent Ineff=
       F
Bank Sta=312.32,520.47
XS Rating Curve= 0 ,0
Exp/Cntr=0.5,0.3