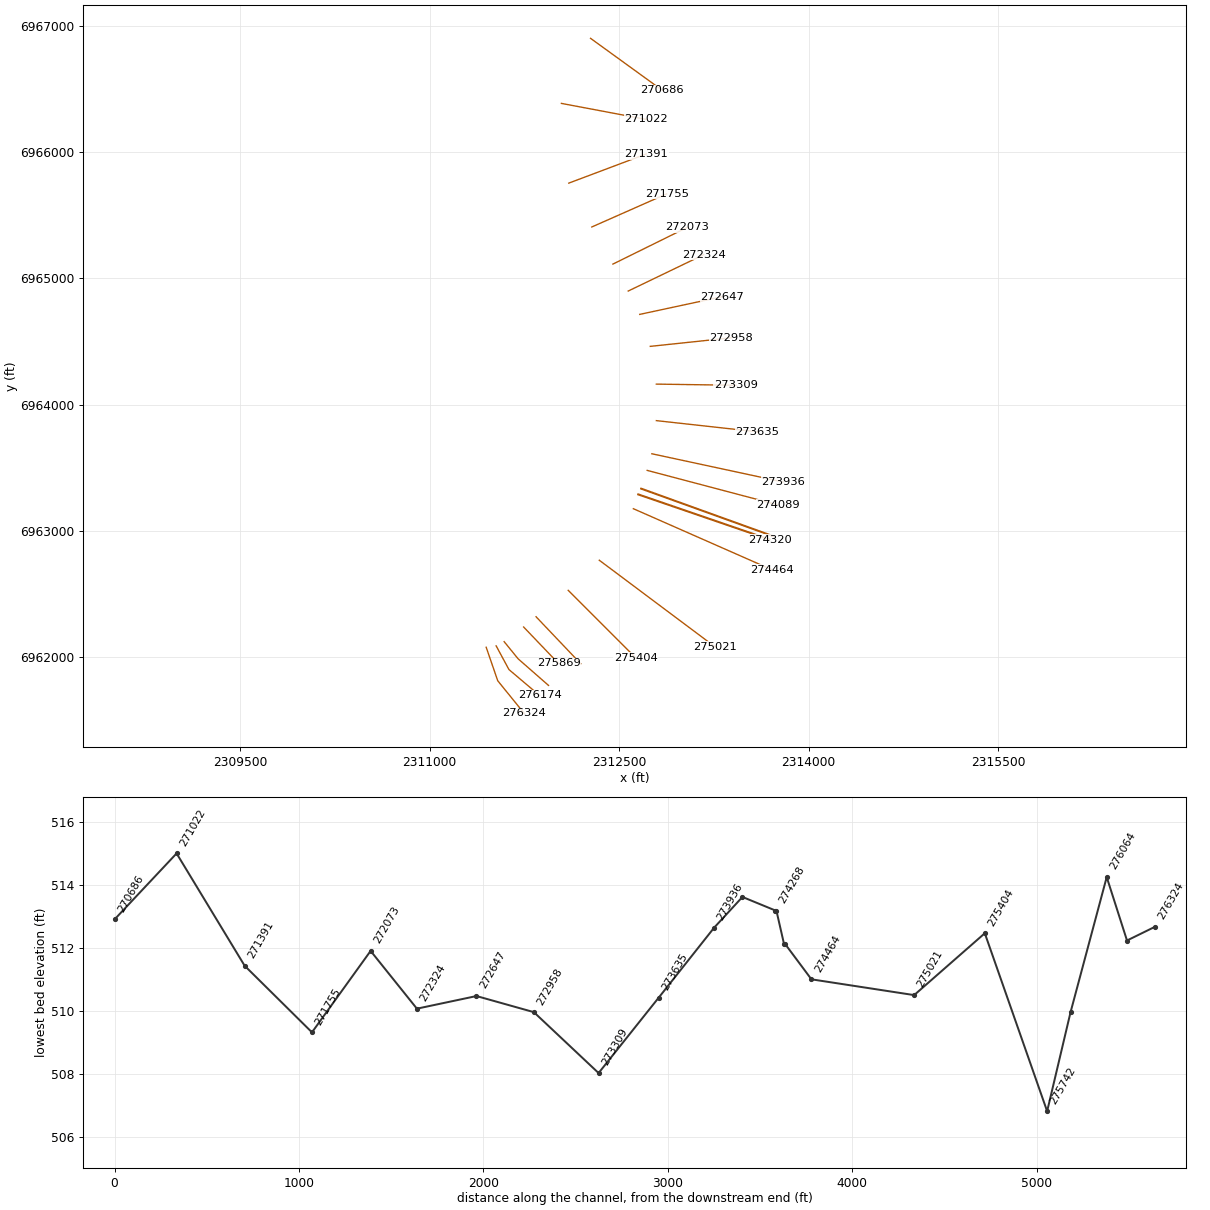
HEC-RAS study CDC_Consolidated_Model.prj: Upper Trinity CDC Consolidated Model

--- CDC_Consolidated_Model.g03 (geometry) --- (continued)

Type RM Length L Ch R = 3 ,276381  ,,,
BEGIN DESCRIPTION:
White Settlement Road - lower crossing
Double bridges - total bridge width set at 114 feet.
Bridge data from USACE 1975 survey.
Bridges represented at this point in the model due to the bridge skew of 43 degrees. Cross-section 276307.7 is a copy of cross-section 276377.7 - bridges skew data was manually generated and entered as resulting bridge length and pier locations.
END DESCRIPTION:
Node Name=White Settlement
Bridge Culvert--1,0,-1,-1, 0
Deck Dist Width WeirC Skew NumUp NumDn MinLoCord MaxHiCord MaxSubmerge Is_Ogee
0.5,114,2.6,0, 3, 3, , , 0.95, 0, 0,0,,
  279.52  614.35  614.35
     564     564     564
  557.17  557.52     500
  279.52  614.35  614.35
     564     564     564
  557.17  557.52     500
Pier Skew, UpSta & Num, DnSta & Num=  ,328, 2 ,328, 2 , 0 , 0 , 0 ,,
       3       3
     500     562
       3       3
     500     562
Pier Skew, UpSta & Num, DnSta & Num=  ,388.45, 2 ,388.45, 2 , 0 , 0 , 0 ,,
       3       3
     500     562
       3       3
     500     562
Pier Skew, UpSta & Num, DnSta & Num=  ,448.18, 2 ,448.18, 2 , 0 , 0 , 0 ,,
       3       3
     500     562
       3       3
     500     562
Pier Skew, UpSta & Num, DnSta & Num=  ,507.9, 2 ,507.9, 2 , 0 , 0 , 0 ,,
       3       3
     500     562
       3       3
     500     562
Pier Skew, UpSta & Num, DnSta & Num=  ,567.63, 2 ,567.63, 2 , 0 , 0 , 0 ,,
       3       3
     500     562
       3       3
     500     562
BR Coef=-1 , 0 , 0 ,, 0 ,,,0.8,-1,,0,
WSPro=,,,, 1 ,,,, 0 ,,,, 0 ,,,,-1 ,-1 ,-1 , 0 , 0 , 0 , 0 , 0
BR U #Sta/Elev= 314
       0   556.1    2.16     556    6.94  555.79    7.96  555.74    8.37  555.72
    9.32  555.68    9.83   555.4   10.29  555.14   12.33     554   13.43  553.38
   15.88     552   16.28  551.78   19.45     550   19.92  549.73   23.02     548
   23.13  547.94   23.68  547.63   26.35  547.02   28.03  546.62    29.9  546.17
   29.93  546.14   30.04     546    32.2  544.19   32.42     544   32.91  543.55
   33.46  543.07   35.69  543.99   35.72     544   35.77  544.02   36.89   544.5
   37.15   544.6    37.5  544.75   41.48  544.89   47.33  545.11   58.65  545.55
   59.01  545.92    59.1     546   60.35  547.22   61.19     548   61.87  548.81
   63.07     550   63.15   550.1   63.16  550.11   63.66  550.19   70.51  551.17
   70.53  551.17   70.55  551.17   70.86  551.14   71.89  550.96   71.95  550.94
   73.14  550.77   73.22  550.76    73.3  550.74   73.45  550.71   73.54  550.69
   74.42  550.58   74.51  550.56   74.61  550.54   74.71  550.52   74.96  550.48
    75.1  550.45   75.25  550.42   75.77  550.34    75.9  550.31   76.05  550.29
   76.57  550.17   76.79  550.12   77.03  550.06   77.28     550   77.31  549.99
    77.6  549.92   77.83  549.88   78.02  549.83   78.19   549.8   78.76  549.64
   78.93   549.6   79.08  549.56   79.22  549.52   79.33  549.49   80.15  549.26
   81.38  549.63   81.87  549.81   82.43     550   82.44     550   84.13  550.57
    85.9  551.15   86.56  551.37   86.89  551.48   87.06  551.53   87.16  551.57
   87.95  551.87   88.66  551.87  110.52  551.17  115.17  550.74  130.75  550.26
  162.81  550.07  173.73  550.05  173.85  550.05     174  550.05  174.01  550.06
  174.71  550.75  175.05  550.88  175.81  551.18  177.96     552  179.92  552.74
  183.27     554  185.63  554.89  188.52     556   191.3  557.07  193.72     558
  194.16  558.17  195.53  558.68  210.73  559.21  216.62  559.43  226.27   559.8
  231.36     560  231.97  560.43  232.03  560.47  232.04  560.48  232.55  560.48
  249.52  560.28  249.65  560.16  249.81     560   262.9  559.58  278.05  559.03
  278.68  559.03  278.95  559.03  279.52  559.04  279.52     557  280.11  556.32
  280.32  555.53  280.41  555.21  280.64  554.25  281.11  554.05   281.2  554.02
  284.59  552.77  284.88  552.65  285.17  552.54  285.55   552.4  285.94  552.25
  286.53  552.02  286.59     552  286.65  551.97  286.75  551.94  288.81  551.24
  289.83   550.9  290.69  550.62  292.63     550  293.46  549.73   295.8  548.97
  297.68  548.35  298.17  548.18  298.74     548  298.85     548  305.47  547.02
  307.91  546.67  312.32     546  314.09  545.33  317.56     544  318.39  543.68
  319.08  543.41  320.69   542.8  322.74     542  325.59  540.89   327.9     540
  329.73  539.29  333.05     538  336.54  536.65  338.24     536  343.11  534.12
  343.43     534   347.4  532.48  348.67     532  351.95  530.75  353.93     530
  357.99  528.45  359.19     528  361.27  527.21  364.17  526.11  364.23  526.07
  364.35     526   366.1  524.87  367.42     524  368.43  523.32  368.72  523.12
   368.9  522.92  369.78     522  371.35  520.21  371.53     520  371.62  519.91
  372.71  518.64  373.23  518.04  373.26     518  387.21  517.49  388.45  517.44
   389.9  517.33  389.99  517.32  390.66  517.51  390.83  517.46  391.58  517.39
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BR U #Mann= 3
       0     .06  312.32    .035  520.47    .055
BR D #Sta/Elev= 314
       0   556.1    2.16     556    6.94  555.79    7.96  555.74    8.37  555.72
    9.32  555.68    9.83   555.4   10.29  555.14   12.33     554   13.43  553.38
   15.88     552   16.28  551.78   19.45     550   19.92  549.73   23.02     548
   23.13  547.94   23.68  547.63   26.35  547.02   28.03  546.62    29.9  546.17
   29.93  546.14   30.04     546    32.2  544.19   32.42     544   32.91  543.55
   33.46  543.07   35.69  543.99   35.72     544   35.77  544.02   36.89   544.5
   37.15   544.6    37.5  544.75   41.48  544.89   47.33  545.11   58.65  545.55
   59.01  545.92    59.1     546   60.35  547.22   61.19     548   61.87  548.81
   63.07     550   63.15   550.1   63.16  550.11   63.66  550.19   70.51  551.17
   70.53  551.17   70.55  551.17   70.86  551.14   71.89  550.96   71.95  550.94
   73.14  550.77   73.22  550.76    73.3  550.74   73.45  550.71   73.54  550.69
   74.42  550.58   74.51  550.56   74.61  550.54   74.71  550.52   74.96  550.48
    75.1  550.45   75.25  550.42   75.77  550.34    75.9  550.31   76.05  550.29
   76.57  550.17   76.79  550.12   77.03  550.06   77.28     550   77.31  549.99
    77.6  549.92   77.83  549.88   78.02  549.83   78.19   549.8   78.76  549.64
   78.93   549.6   79.08  549.56   79.22  549.52   79.33  549.49   80.15  549.26
   81.38  549.63   81.87  549.81   82.43     550   82.44     550   84.13  550.57
    85.9  551.15   86.56  551.37   86.89  551.48   87.06  551.53   87.16  551.57
   87.95  551.87   88.66  551.87  110.52  551.17  115.17  550.74  130.75  550.26
  162.81  550.07  173.73  550.05  173.85  550.05     174  550.05  174.01  550.06
  174.71  550.75  175.05  550.88  175.81  551.18  177.96     552  179.92  552.74
  183.27     554  185.63  554.89  188.52     556   191.3  557.07  193.72     558
  194.16  558.17  195.53  558.68  210.73  559.21  216.62  559.43  226.27   559.8
  231.36     560  231.97  560.43  232.03  560.47  232.04  560.48  232.55  560.48
  249.52  560.28  249.65  560.16  249.81     560   262.9  559.58  278.05  559.03
  278.68  559.03  278.95  559.03  279.52  559.04  279.52     557  280.11  556.32
  280.32  555.53  280.41  555.21  280.64  554.25  281.11  554.05   281.2  554.02
  284.59  552.77  284.88  552.65  285.17  552.54  285.55   552.4  285.94  552.25
  286.53  552.02  286.59     552  286.65  551.97  286.75  551.94  288.81  551.24
  289.83   550.9  290.69  550.62  292.63     550  293.46  549.73   295.8  548.97
  297.68  548.35  298.17  548.18  298.74     548  298.85     548  305.47  547.02
  307.91  546.67  312.32     546  314.09  545.33  317.56     544  318.39  543.68
  319.08  543.41  320.69   542.8  322.74     542  325.59  540.89   327.9     540
  329.73  539.29  333.05     538  336.54  536.65  338.24     536  343.11  534.12
  343.43     534   347.4  532.48  348.67     532  351.95  530.75  353.93     530
  357.99  528.45  359.19     528  361.27  527.21  364.17  526.11  364.23  526.07
  364.35     526   366.1  524.87  367.42     524  368.43  523.32  368.72  523.12
   368.9  522.92  369.78     522  371.35  520.21  371.53     520  371.62  519.91
  372.71  518.64  373.23  518.04  373.26     518  387.21  517.49  388.45  517.44
   389.9  517.33  389.99  517.32  390.66  517.51  390.83  517.46  391.58  517.39
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BR D #Mann= 3
       0     .06  312.32    .035  520.47    .055
BC Design=,, 0 ,, 0 ,,,,,,
BC Use User HTab Curves=0
BC User HTab FreeFlow(D)= 0

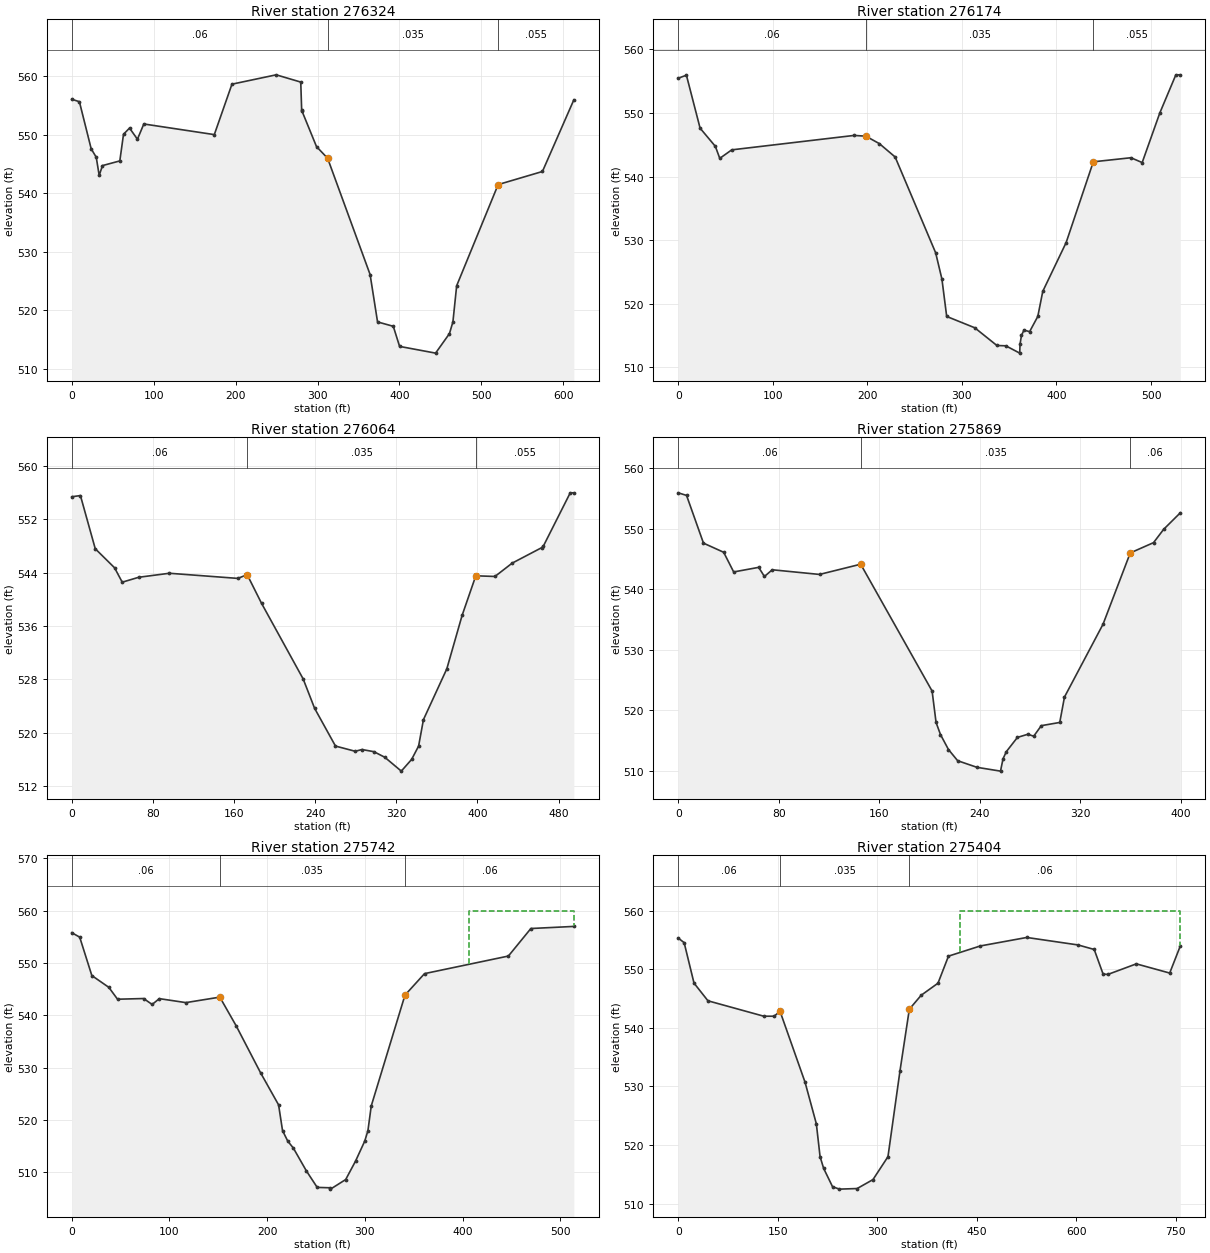
Type RM Length L Ch R = 1 ,276324  ,150,150,150
BEGIN DESCRIPTION:
This cross section corresponds to cross section 276125.9 of the non-georeferenced CDC model which was the source of this model.
Copy of cross-section 276447.63 here for White Settlement bridge model.
Effective flow limit set at Brookside Levee in LOB.
Effective flow limit set at White Settlement Levee in ROB.
White Settlement Road in LOB - area to the west non-effective up to elevation 550.
END DESCRIPTION:
XS GIS Cut Line= 3
      2311447.87      6962079.01     2311539.164     6961813.977
     2311748.774     6961555.781
#Sta/Elev= 30
       0   556.1    9.32  555.68   23.68  547.63    29.9  546.17   33.46  543.07
    37.5  544.75   58.65  545.55   63.16  550.11   70.51  551.17   80.15  549.26
   87.95  551.87     174  550.05  195.53  558.68  249.52  560.28  279.52  559.04
  280.64  554.25  281.11  554.05  298.74     548  312.32     546  364.17  526.11
  373.26     518  392.48  517.25  400.17  513.81  444.12  512.66  461.03     516
  465.26     518  469.84  524.19  520.47   541.5  574.54  543.74  612.88     556
#Mann= 3 ,-1,0
       0     .06       0  312.32    .035       0  520.47    .055       0
#XS Ineff= 1 ,-1
       0     200     550
Permanent Ineff=
       F
Bank Sta=312.32,520.47
XS Rating Curve= 0 ,0
Exp/Cntr=0.5,0.3

Type RM Length L Ch R = 1 ,276174  ,110,110,140
BEGIN DESCRIPTION:
This cross section corresponds to cross section 276052.6 of the non-georeferenced CDC model which was the source of this model.
Upstream of White Settlement Road.
Effective flow limit set at Brookside Levee in LOB.
Effective flow limit set at White Settlement Levee in ROB.
END DESCRIPTION:
XS GIS Cut Line= 3
 2311526.5404684 6962090.4307445 2311627.8579587 6961902.8027424
 2311870.3703732 6961697.5617868
#Sta/Elev= 30
       0  555.47    8.65  555.94   23.12  547.61   39.26  544.75   43.92  542.86
   56.58   544.2     186  546.47  198.41  546.35  212.69  545.18  229.37  543.08
  272.22  528.01  278.85  523.87  283.89     518  313.54  516.22  336.98  513.43
  346.43  513.38  361.12  512.23  361.46  513.66  362.99  515.02   365.6  515.85
  371.58  515.61  380.24     518   385.5  521.95  410.21  529.62  438.93  542.32
  478.74  542.96  490.62   542.2  509.25     550  526.22     556  530.94     556
#Mann= 3 ,-1,0
       0     .06       0  198.41    .035       0  438.93    .055       0
Bank Sta=198.41,438.93
XS Rating Curve= 0 ,0
Exp/Cntr=0.3,0.1

Type RM Length L Ch R = 1 ,276064  ,196,196,179
BEGIN DESCRIPTION:
This cross section corresponds to cross section 275942.7 of the non-georeferenced CDC model which was the source of this model.
Downstream of White Settlement Road.
Effective flow limit set at Brookside Levee in LOB.
Effective flow limit set at White Settlement Levee in ROB.
END DESCRIPTION:
XS GIS Cut Line= 3
 2311589.9160141 6962123.7569422  2311700.159183 6961988.1869936
 2311941.1993032 6961777.1128644
#Sta/Elev= 30
       0  555.41    8.53  555.59   23.16  547.61   42.22  544.75   49.76  542.59
   66.06  543.33   96.25  543.93  163.73  543.16  172.98  543.72  187.15  539.42
   228.2  528.07  239.46  523.67  260.07     518  279.51  517.22   286.2  517.48
  297.93  517.16  308.69  516.32  324.97  514.24  335.17     516  342.03     518
  346.82  521.97  369.86  529.59  384.92   537.6  398.44  543.55  417.33  543.45
  434.31  545.45   463.4  547.77  465.05     548  491.57     556  495.13     556
#Mann= 3 ,-1,0
       0     .06       0  172.98    .035       0  398.44    .055       0
Bank Sta=172.98,398.44
XS Rating Curve= 0 ,0
Exp/Cntr=0.3,0.1

Type RM Length L Ch R = 1 ,275869  ,127,127,125
BEGIN DESCRIPTION:
This cross section corresponds to cross section 275747.2 of the non-georeferenced CDC model which was the source of this model.
Effective flow limit set at Brookside Levee in LOB.
END DESCRIPTION:
XS GIS Cut Line= 2
 2311744.1329059 6962239.6733118 2312020.5248114 6961950.8400856
#Sta/Elev= 30
       0  555.93    6.63   555.5    20.1  547.62   36.18  546.11   44.14  542.86
   64.05  543.62   68.63  542.11   74.86  543.22   112.5  542.45  145.27  544.14
  202.14  523.19  205.29     518  208.81     516  215.19  513.52  222.49  511.68
  237.84  510.59   256.6  509.96  258.62     512  261.25  513.18  270.08  515.53
  278.37  516.05  283.04  515.73  289.09  517.47  303.77     518  307.54   522.2
  338.27  534.24   359.9     546  378.45   547.7   386.5   549.9  399.77  552.63
#Mann= 3 ,-1,0
       0     .06       0  145.27    .035       0   359.9     .06       0
Bank Sta=145.27,359.9
XS Rating Curve= 0 ,0
Exp/Cntr=0.3,0.1

Type RM Length L Ch R = 1 ,275742  ,338,338,346
BEGIN DESCRIPTION:
This cross section corresponds to cross section 275620.4 of the non-georeferenced CDC model which was the source of this model.
Effective flow limit set at Brookside Levee in LOB.
END DESCRIPTION:
XS GIS Cut Line= 2
  2311842.709598 6962320.7626692 2312196.8616376 6961948.4174181
#Sta/Elev= 30
       0  555.82    8.12  554.97   20.54  547.63   37.92  545.38   46.84  543.11
   73.52  543.24   82.26  542.11   89.63  543.22   116.8  542.46  151.53  543.51
  168.34     538  193.21  529.06  211.67  522.92  215.72     518  221.04     516
  226.81  514.66  240.04  510.33   251.2  507.15   263.9  507.08  264.79  506.82
  280.35  508.65  290.45  512.18  299.86     516  303.12     518  306.52  522.72
  341.03  543.89  361.06     548  446.89  551.36  469.89  556.62  513.87  557.02
#Mann= 3 ,-1,0
       0     .06       0  151.53    .035       0  341.03     .06       0
#XS Ineff= 2 , 0
       0                  406.61       0     560
Permanent Ineff=
       F       T
Bank Sta=151.53,341.03
XS Rating Curve= 0 ,0
Exp/Cntr=0.3,0.1

Type RM Length L Ch R = 1 ,275404  ,383,383,428
BEGIN DESCRIPTION:
This cross section corresponds to cross section 275282.5 of the non-georeferenced CDC model which was the source of this model.
Effective flow limit set at Brookside Levee in LOB.
END DESCRIPTION:
XS GIS Cut Line= 3
  2312097.157228 6962530.0716528 2312620.9864805 6962006.2422706
 2312632.3001876 6961994.9285607
#Sta/Elev= 30
       0  555.35    8.92  554.56   23.79  547.65   44.81  544.63   128.9     542
  144.41     542   153.5  542.82  191.16  530.72  208.18  523.62  213.81     518
  219.21     516  232.59  512.87  242.97  512.46  269.68  512.56  293.55  514.09
  316.14     518  334.25  532.66  348.34  543.19  366.22  545.58  391.56  547.64
  407.35  552.26  455.39     554  525.39  555.45   602.7  554.17  627.02   553.4
  640.41   549.2  647.51  549.13   690.5  550.94  740.81  549.37  756.81     554
#Mann= 3 ,-1,0
       0     .06       0   153.5    .035       0  348.34     .06       0
#XS Ineff= 2 , 0
       0                  424.73       0     560
Permanent Ineff=
       F       T
Bank Sta=153.5,348.34
XS Rating Curve= 0 ,0
Exp/Cntr=0.3,0.1

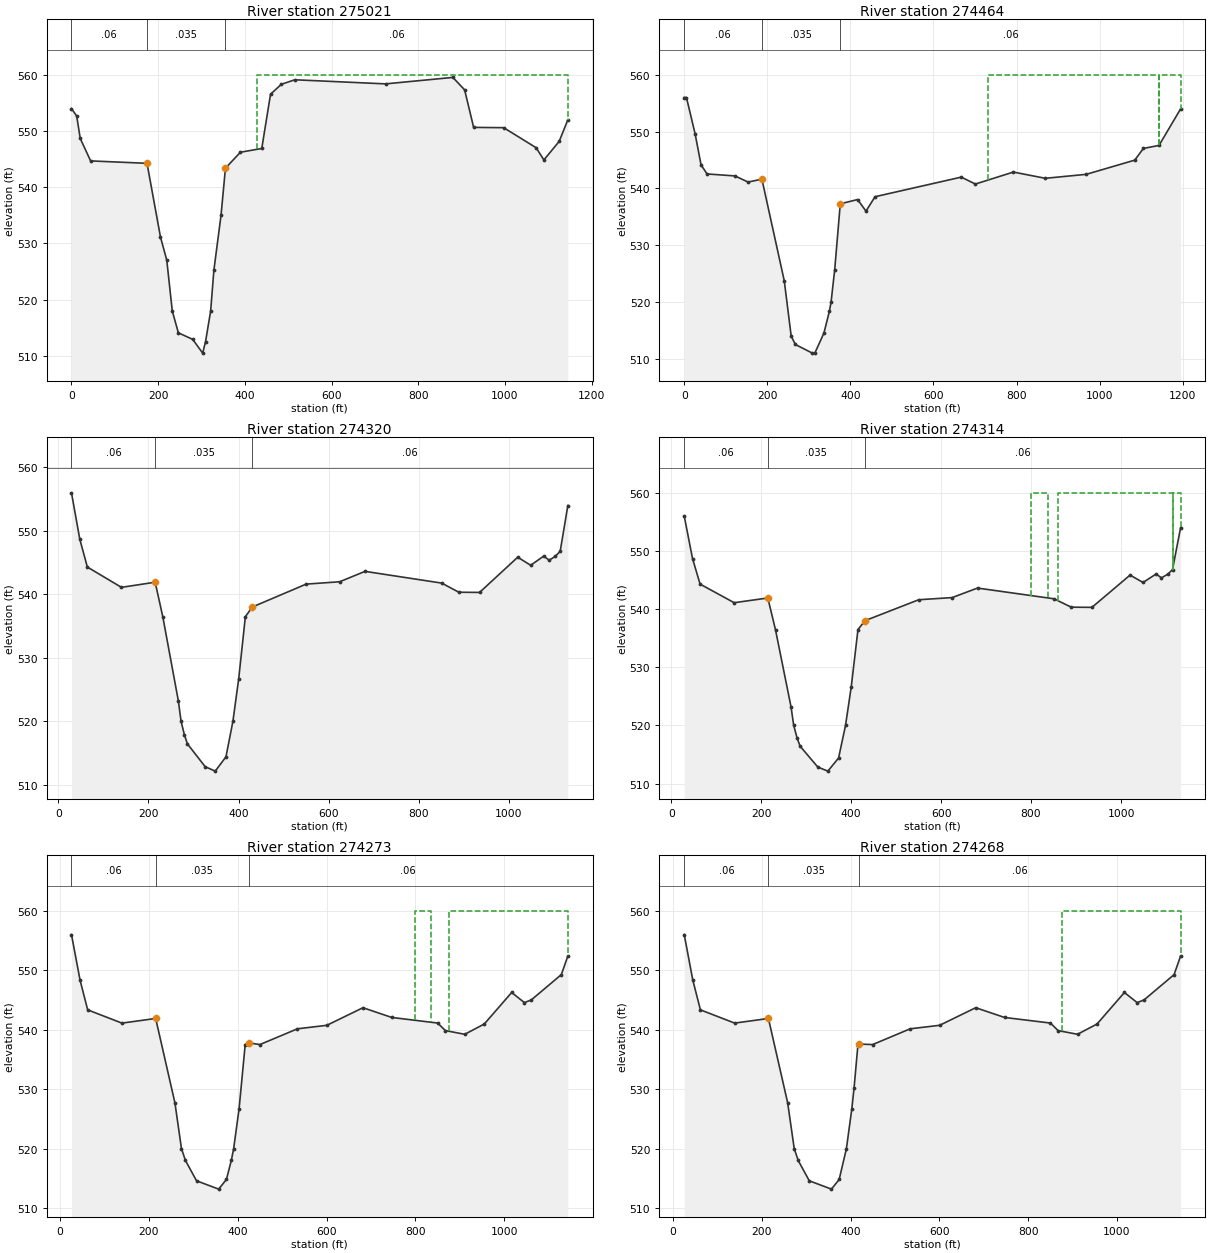
Type RM Length L Ch R = 1 ,275021  ,557,557,629
BEGIN DESCRIPTION:
This cross section corresponds to cross section 274899.6 of the non-georeferenced CDC model which was the source of this model.
Effective flow limit set at Brookside Levee in LOB.
END DESCRIPTION:
XS GIS Cut Line= 3
 2312343.4213547 6962768.2168358 2313244.4864369 6962094.1118043
2313260.500874836962082.13107904
#Sta/Elev= 30
       0     554   12.03  552.67   20.18  548.69   44.14  544.69  174.31  544.26
  205.28  531.17  219.87  527.03  232.57     518  246.61  514.11  279.64  512.95
  302.75   510.5  309.38  512.56  321.13     518  328.56  525.24  345.11  535.04
  355.26  543.39  389.72  546.23  439.07   546.9  459.26  556.55  484.14  558.31
  515.17  559.12  724.79  558.39  879.95  559.54  907.14  557.33  927.94  550.65
  997.27   550.6 1072.19  547.03 1090.02  544.86 1125.32  548.16 1145.32     552
#Mann= 3 ,-1,0
       0     .06       0  174.31    .035       0  355.26     .06       0
#XS Ineff= 2 , 0
       0                  427.12       0     560
Permanent Ineff=
       F       T
Bank Sta=174.31,355.26
XS Rating Curve= 0 ,0
Exp/Cntr=0.3,0.1

Type RM Length L Ch R = 1 ,274464  ,144,144,173
BEGIN DESCRIPTION:
This cross section corresponds to cross section 274342.7 of the non-georeferenced CDC model which was the source of this model.
Upstream of Sump 11W outfall.
Effective flow limit set at Brookside Levee in LOB.
West Side Lions Club fields in ROB.
END DESCRIPTION:
XS GIS Cut Line= 3
 2312612.9218549 6963176.3937905 2313658.9082942 6962715.6367317
    2313706.49596962694.67438988
#Sta/Elev= 30
       0     556    5.39     556    26.3  549.57   40.45  544.15   54.91  542.55
  122.08   542.2  153.72  541.12  186.99  541.63  240.83  523.73  257.46  514.01
  267.56  512.52  308.43     511  314.93  511.09  336.33  514.54  349.47  518.37
  353.55     520  362.26  525.71  375.67  537.29  417.35  538.04  437.53     536
  459.38  538.54  666.98  541.99  700.91  540.77  792.41  542.88   869.4  541.78
   967.8  542.48  1084.6  544.98 1105.39  547.04 1142.97  547.57 1194.97     554
#Mann= 3 ,-1,0
       0     .06       0  186.99    .035       0  375.67     .06       0
#XS Ineff= 2 ,-1
  732.11 1142.97     560 1142.97 1194.97     560
Permanent Ineff=
       F       F
Bank Sta=186.99,375.67
XS Rating Curve= 0 ,0
Exp/Cntr=0.3,0.1

Type RM Length L Ch R = 1 ,274320  ,5,5,5
BEGIN DESCRIPTION:
This cross section corresponds to cross section 274196 of the non-georeferenced CDC model which was the source of this model.
END DESCRIPTION:
XS GIS Cut Line= 3
 2312649.02296136963287.49910456      2313690.34       6962930.2
2313691.786811236962929.70356679
#Sta/Elev= 30
   28.99     556   47.41   548.7   64.23   544.3  139.97   541.1  214.83  541.91
   231.9  536.43  266.36   523.2  272.34     520  279.89  517.82  286.48  516.43
  325.89  512.83  348.27  512.13  372.12  514.39  387.56     520  400.33  526.66
   415.2  536.47  430.58     538  550.21  541.61  624.63  541.98  680.94  543.62
   851.2  541.77  889.36  540.33  935.37   540.3 1020.11  545.85 1048.89  544.58
 1078.12  546.04 1089.78  545.37 1103.87     546 1114.43  546.79 1131.43     554
#Mann= 3 ,0,0
   28.99     .06       0  214.83    .035       0  430.58     .06       0
#XS Ineff= 2 , 0
       0                 1114.43       0
Permanent Ineff=
       F       F
Bank Sta=214.83,430.58
XS Rating Curve= 0 ,0
Exp/Cntr=0.3,0.1

Type RM Length L Ch R = 1 ,274314  ,41,41,38
BEGIN DESCRIPTION:
This cross section corresponds to cross section 274191 of the non-georeferenced CDC model which was the source of this model.
END DESCRIPTION:
XS GIS Cut Line= 3
 2312650.37953686963292.823901712312763.045219496963254.13750544
2313694.008792136962934.46939693
#Sta/Elev= 30
   28.99     556   47.41   548.7   64.23   544.3  139.97   541.1  214.83  541.91
   231.9  536.43  266.36   523.2  272.34     520  279.89  517.82  286.48  516.43
  325.89  512.83  348.27  512.13  372.12  514.39  387.56     520  400.33  526.66
   415.2  536.47  430.58     538  550.21  541.61  624.63  541.98  680.94  543.62
   851.2  541.77  889.36  540.33  935.37   540.3 1020.11  545.85 1048.89  544.58
 1078.12  546.04 1089.78  545.37 1103.87     546 1114.43  546.79 1132.43     554
#Mann= 3 ,0,0
   28.99     .06       0  214.83    .035       0  430.58     .06       0
#XS Ineff= 3 ,-1
     800     838     560     860 1114.43     560 1114.43 1132.43     560
Permanent Ineff=
       F       F       F
Bank Sta=214.83,430.58
XS Rating Curve= 0 ,0
Exp/Cntr=0.3,0.1

Type RM Length L Ch R = 1 ,274273  ,5,5,5
BEGIN DESCRIPTION:
This cross section corresponds to cross section 274149 of the non-georeferenced CDC model which was the source of this model.
Effective flow limit set at Brookside Levee in LOB.
West Side Lions Club fields in ROB.
---------------------------------------------------------------------
CDC FW081296-01 West Side Little League
New Building in ROB.
Cross-section 274149 - 274191
---------------------------------------------------------------------
END DESCRIPTION:
XS GIS Cut Line= 2
2312671.87598318 6963333.53366392313723.36101682 6962954.7513361
#Sta/Elev= 30
   25.61     556   44.92  548.34   62.04  543.34  139.21  541.11  215.18  541.89
  258.56  527.68  273.24     520  282.21     518  307.19  514.58  357.11  513.18
  374.49  514.81  385.49     518   390.8     520  403.04  526.74  416.75  537.49
  424.51  537.79  449.84   537.5  534.31  540.15  600.62  540.74  681.91   543.7
  746.85  542.06  850.18  541.12  867.39  539.85  911.18  539.23  955.08  540.96
 1016.74  546.26 1045.44  544.56 1060.94  545.01 1128.58  549.27 1143.24   552.4
#Mann= 3 ,0,0
   25.61     .06       0  215.18    .035       0  424.51     .06       0
#XS Ineff= 2 ,-1
     876 1143.24     560     798     836     560
Permanent Ineff=
       F       F
Bank Sta=215.18,424.51
XS Rating Curve= 0 ,0
Exp/Cntr=0.3,0.1

Type RM Length L Ch R = 1 ,274268  ,179,179,213
BEGIN DESCRIPTION:
This cross section corresponds to cross section 274144 of the non-georeferenced CDC model which was the source of this model.
END DESCRIPTION:
XS GIS Cut Line= 2
2312673.645762256963338.343022012313725.104237756962959.48697799
#Sta/Elev= 30
   25.61     556   44.92  548.34   62.04  543.34  139.21  541.11  215.18  541.89
  258.56  527.68  273.24     520  282.21     518  307.19  514.58  357.11  513.18
  374.49  514.81   390.8     520  403.04  526.74  407.98  530.17  416.75  537.49
  418.09  537.59  449.84   537.5  534.31  540.15  600.62  540.74  681.91   543.7
  746.85  542.06  850.18  541.12  867.39  539.85  911.18  539.23  955.08  540.96
 1016.74  546.26 1045.44  544.56 1060.94  545.01 1128.58  549.27 1143.24   552.4
#Mann= 3 ,0,0
   25.61     .06       0  215.18    .035       0  418.09     .06       0
#XS Ineff= 1 ,-1
     876 1143.24     560
Permanent Ineff=
       F
Bank Sta=215.18,418.09
XS Rating Curve= 0 ,0
Exp/Cntr=0.3,0.1

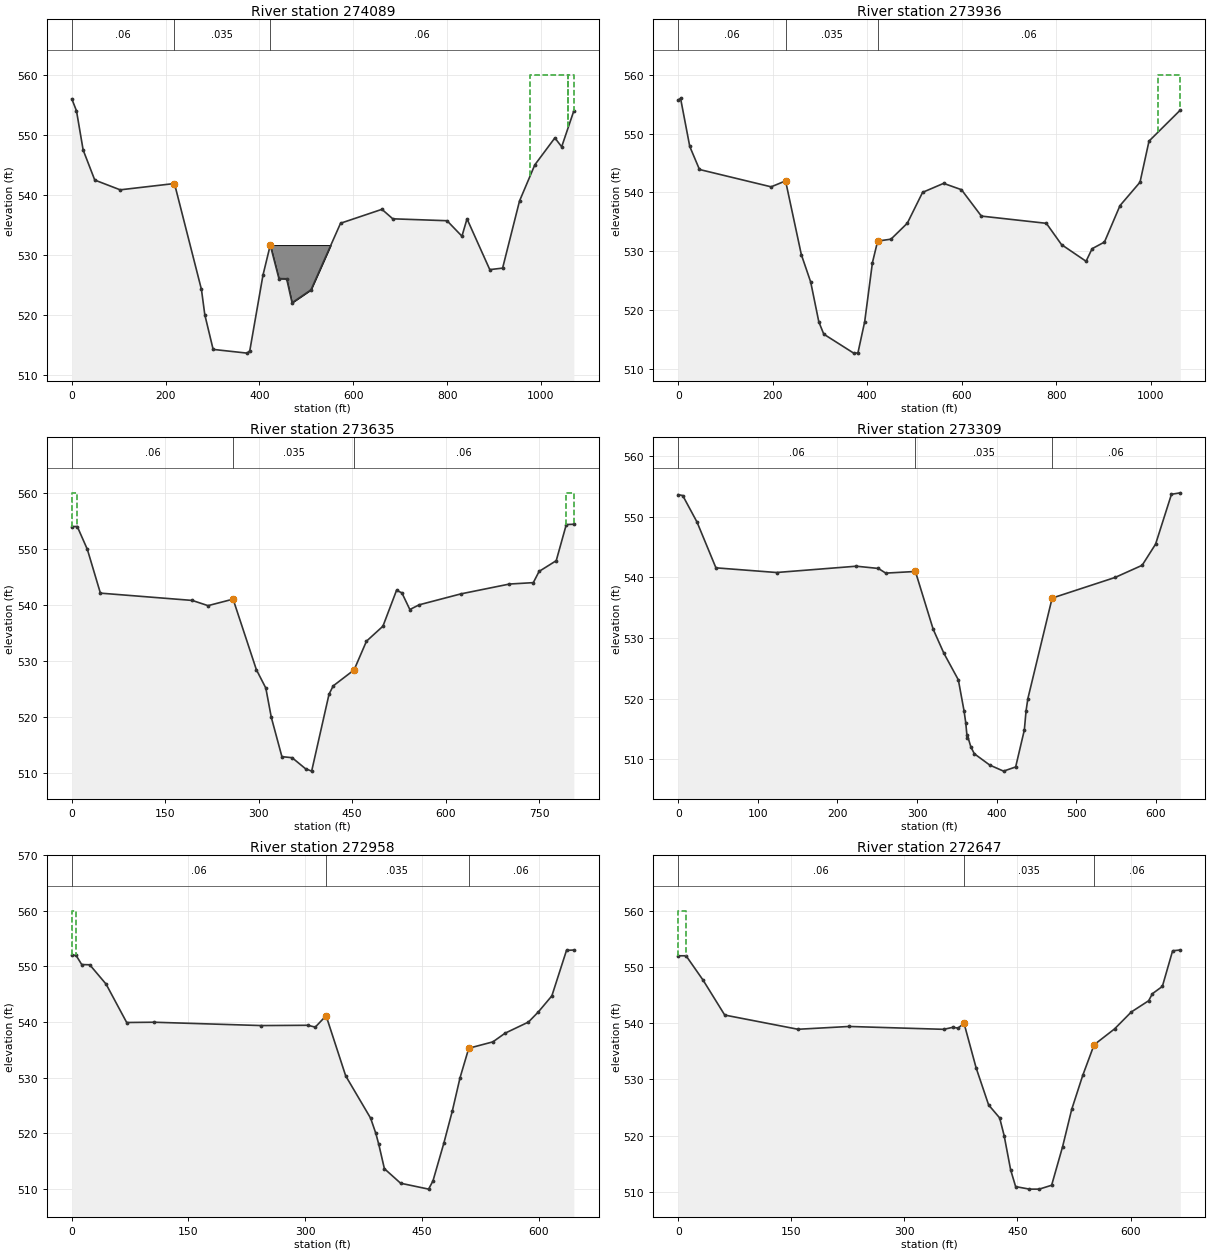
Type RM Length L Ch R = 1 ,274089  ,153,153,170
BEGIN DESCRIPTION:
This cross section corresponds to cross section 273967.4 of the non-georeferenced CDC model which was the source of this model.
Downstream of Sump 11W outfall.
Effective flow limit set at Brookside Levee in LOB.
West Side Lions Club fields in ROB.
END DESCRIPTION:
XS GIS Cut Line= 3
 2312722.6792717  6963479.689258 2313746.4281952  6963209.461102
2313757.45057308 6963206.5516417
#Sta/Elev= 30
       0     556   10.05     554   24.26  547.47   49.01  542.46   103.2  540.83
  218.89  541.88  276.42  524.22  283.59     520  301.34  514.23  373.77  513.61
  379.44     514  407.54   526.6  423.13  531.62  441.53  526.04  458.05     526
  469.53     522  509.93  524.16  572.95  535.26  661.15  537.58  684.25     536
  799.93  535.68  831.67   533.1   842.5  535.99  891.01  527.53  918.36  527.78
  954.41  538.97     987  544.99 1029.79  549.49 1044.25     548 1070.21     554
#Mann= 3 ,-1,0
       0     .06       0  218.89    .035       0  423.13     .06       0
#XS Ineff= 3 ,-1
  977.08 1058.81     560 1058.81 1070.21     560  661.15  977.08  537.58
Permanent Ineff=
       F       F       F
#Block Obstruct= 1 ,-1
  423.13     600  531.62
Bank Sta=218.89,423.13
XS Rating Curve= 0 ,0
Exp/Cntr=0.3,0.1

Type RM Length L Ch R = 1 ,273936  ,301,301,340
BEGIN DESCRIPTION:
This cross section corresponds to cross section 273814.8 of the non-georeferenced CDC model which was the source of this model.
Effective flow limit set at Brookside Levee in LOB.
END DESCRIPTION:
XS GIS Cut Line= 3
 2312759.5296676 6963611.3335208 2313756.4293473 6963396.9535031
2313798.468225786963387.91317969
#Sta/Elev= 30
       0  555.71    4.93     556    24.4  547.81   44.95  543.89  196.64  540.94
  227.19  541.95  260.53  529.41  280.39  524.73   297.6  517.95  308.05  515.87
  371.34  512.64  380.31  512.67  394.67     518  411.04  528.04  422.08  531.71
  450.22  532.03  484.87  534.75  517.21     540  561.71  541.53  599.49  540.45
  641.59  535.96  779.17  534.73  811.23  531.11  863.19  528.27  875.98  530.41
  902.12  531.54  934.98  537.74   977.4  541.73  996.43  548.72 1062.69     554
#Mann= 3 ,-1,0
       0     .06       0  227.19    .035       0  422.08     .06       0
#XS Ineff= 2 ,-1
  561.71 1014.86  541.53 1014.86 1062.69     560
Permanent Ineff=
       F       F
Bank Sta=227.19,422.08
XS Rating Curve= 0 ,0
Exp/Cntr=0.3,0.1

Type RM Length L Ch R = 1 ,273635  ,326,326,360
BEGIN DESCRIPTION:
This cross section corresponds to cross section 273513.4 of the non-georeferenced CDC model which was the source of this model.
Effective flow limit set at Brookside Levee in LOB.
Effective flow limit set at Crestwood Levee in ROB.
END DESCRIPTION:
XS GIS Cut Line= 2
 2312795.0292397 6963873.6016688 2313595.8918446 6963785.2685512
#Sta/Elev= 30
       0     554    8.83     554   25.06  549.91   45.94  542.13  193.33  540.83
  218.68   539.9  258.88  541.06  296.25  528.49   311.4  525.22  320.22     520
  337.21     513  353.62  512.81  375.09  510.85  384.96  510.42  412.84  524.12
  419.49   525.6  453.05  528.45  472.93  533.57  499.35  536.24  521.18  542.63
  529.77  542.18  542.52  539.21  557.55  540.05  624.54     542   702.4  543.75
  740.66     544  749.94     546  777.45  547.91  793.62  554.35  805.72   554.4
#Mann= 3 ,-1,0
       0     .06       0  258.88    .035       0  453.05     .06       0
#XS Ineff= 2 , 0
       0    8.78     560  793.62       0     560
Permanent Ineff=
       T       T
Bank Sta=258.88,453.05
XS Rating Curve= 0 ,0
Exp/Cntr=0.3,0.1

Type RM Length L Ch R = 1 ,273309  ,351,351,394
BEGIN DESCRIPTION:
This cross section corresponds to cross section 273187.6 of the non-georeferenced CDC model which was the source of this model.
Effective flow limit set at Brookside Levee in LOB.
Effective flow limit set at Crestwood Levee in ROB.
END DESCRIPTION:
XS GIS Cut Line= 2
 2312794.8013368 6964162.8114923 2313425.5022731 6964153.5710536
#Sta/Elev= 30
       0  553.66    5.65  553.51   23.58  549.14   47.36  541.58   123.5  540.81
  223.73  541.85   251.4  541.48  260.69  540.71  297.95  540.98  320.31  531.44
  333.83  527.46  351.89   523.1  359.04     518  361.23     516  362.96  513.55
  363.14     514  367.68     512  372.04  510.89  391.49  509.02   408.7  508.03
  423.91  508.72  434.82  514.82     437     518  439.26     520  469.75  536.59
  548.75  539.99  582.82     542  599.73   545.5  619.66  553.72  630.77  553.96
#Mann= 3 ,-1,0
       0     .06       0  297.95    .035       0  469.75     .06       0
Bank Sta=297.95,469.75
XS Rating Curve= 0 ,0
Exp/Cntr=0.3,0.1

Type RM Length L Ch R = 1 ,272958  ,311,311,349
BEGIN DESCRIPTION:
This cross section corresponds to cross section 272836.8 of the non-georeferenced CDC model which was the source of this model.
Effective flow limit set at Brookside Levee in LOB.
Effective flow limit set at Crestwood Levee in ROB.
END DESCRIPTION:
XS GIS Cut Line= 3
  2312746.973488 6964461.7276719 2313345.9583256 6964524.9117429
 2313388.7781442 6964529.7590225
#Sta/Elev= 30
       0     552    5.49     552   12.79  550.34   23.11   550.3   44.13  546.82
   70.59  539.92  105.53  539.97  243.55  539.37   303.5  539.42  313.02  539.09
  326.93  541.14  352.16  530.31  384.15  522.72  390.82     520  394.66     518
  401.88  513.63  422.73  511.02   458.7  509.96  464.28  511.43  478.18  518.17
  489.17     524  499.13     530  510.32  535.29  541.34  536.44  557.05     538
  587.03     540  599.88  541.84  617.14  544.71  635.99   552.9   645.4  552.95
#Mann= 3 ,-1,0
       0     .06       0  326.93    .035       0  510.32     .06       0
#XS Ineff= 2 , 0
       0    5.49     560               0
Permanent Ineff=
       T       F
Bank Sta=326.93,510.32
XS Rating Curve= 0 ,0
Exp/Cntr=0.3,0.1

Type RM Length L Ch R = 1 ,272647  ,323,323,426
BEGIN DESCRIPTION:
This cross section corresponds to cross section 272525.4 of the non-georeferenced CDC model which was the source of this model.
Effective flow limit set at Brookside Levee in LOB.
Effective flow limit set at Crestwood Levee in ROB.
END DESCRIPTION:
XS GIS Cut Line= 2
 2312663.6264918 6964714.8646658 2313314.7695926 6964854.6983952
#Sta/Elev= 30
       0     552   10.38     552   32.99  547.66   61.67  541.45   158.9  538.92
  226.68  539.42  352.25  538.91  364.27  539.27  371.23  539.13  379.08     540
  395.12  532.06  411.73  525.45  426.33  523.15   432.3     520  440.92   513.9
  447.55  510.92  465.81  510.47  478.85  510.47  495.29  511.16   509.8     518
   521.9  524.65  536.53   530.7  551.62  536.16  578.73  538.98  601.01     542
  624.02     544  628.96  545.25  642.17  546.55   655.8  552.89  665.99  553.03
#Mann= 3 ,-1,0
       0     .06       0  379.08    .035       0  551.62     .06       0
#XS Ineff= 2 , 0
       0   10.34     560               0
Permanent Ineff=
       T       F
Bank Sta=379.08,551.62
XS Rating Curve= 0 ,0
Exp/Cntr=0.3,0.1

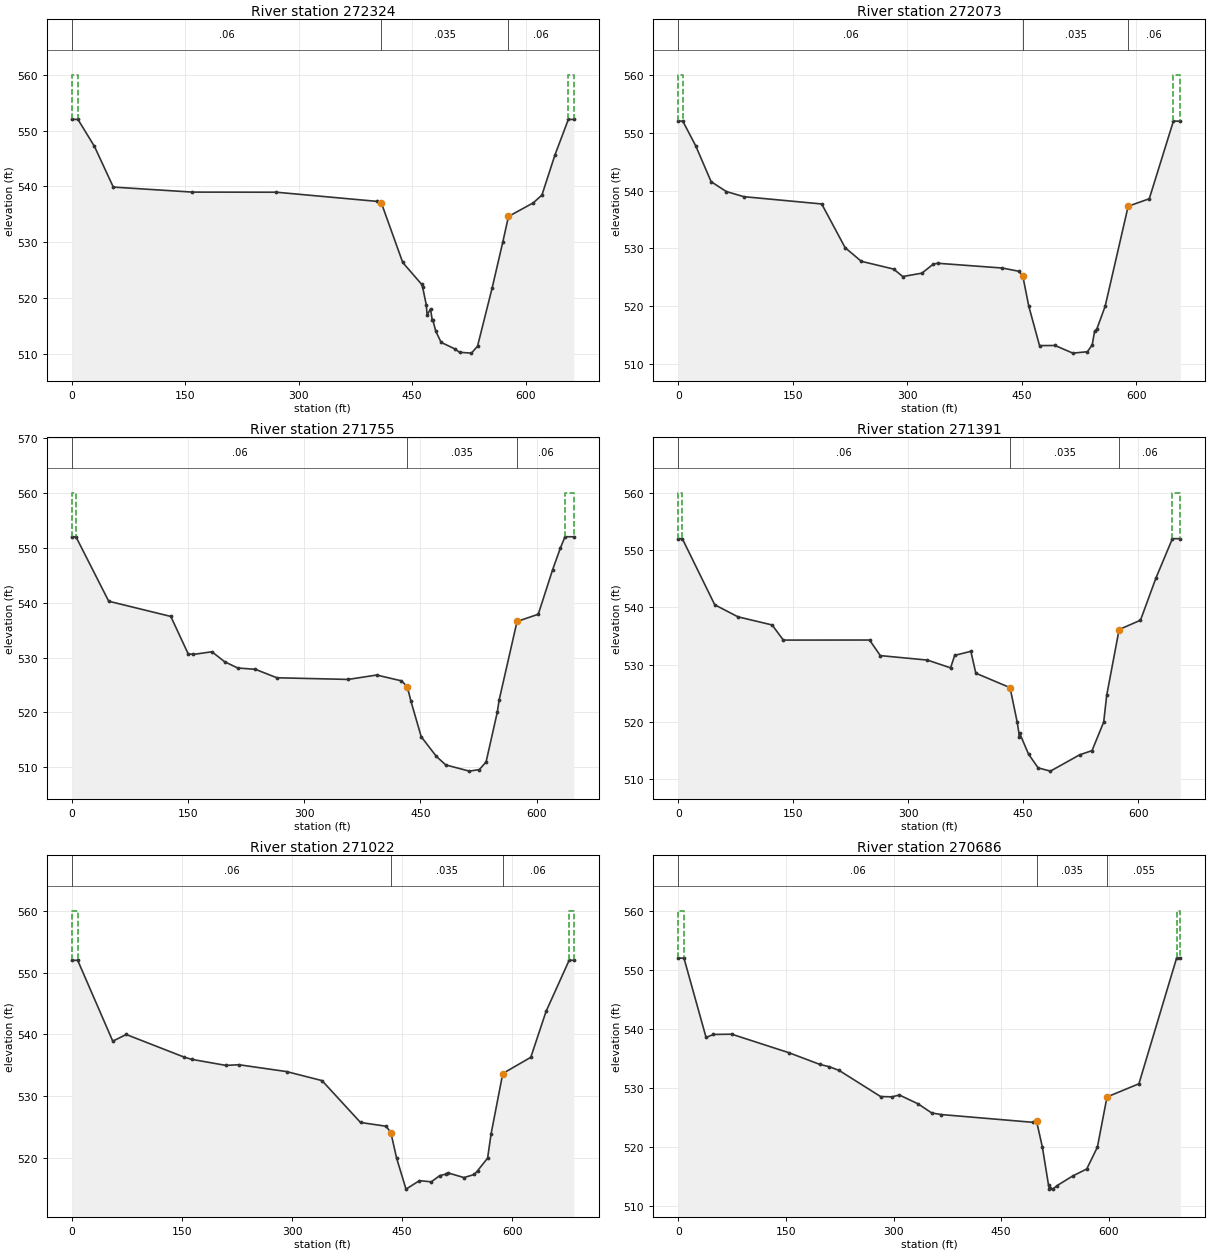
Type RM Length L Ch R = 1 ,272324  ,251,251,254
BEGIN DESCRIPTION:
This cross section corresponds to cross section 272202.9 of the non-georeferenced CDC model which was the source of this model.
Downstream of Sump 11W outfall.
Effective flow limit set at Brookside Levee in LOB.
Effective flow limit set at Crestwood Levee in ROB.
END DESCRIPTION:
XS GIS Cut Line= 2
  2312572.260632 6964899.6856249 2313170.0731568 6965187.7224873
#Sta/Elev= 30
       0     552    8.17     552   29.98  547.16   54.89  539.86  159.24  538.96
   270.3  538.94  403.91  537.29  409.12  537.04  437.43  526.33  462.38  522.42
  463.58     522  468.63  518.68  469.63   516.9  474.14     518   476.5  515.95
  477.22     516  481.12     514  488.15     512  505.85  510.86   512.6  510.22
  528.25  510.07  536.27  511.31  555.54  521.73  569.69     530  577.17  534.59
  609.94  537.03  621.43  538.44  638.72  545.67  656.31     552  663.58     552
#Mann= 3 ,-1,0
       0     .06       0  409.12    .035       0  577.17     .06       0
#XS Ineff= 2 , 0
       0    8.17     560  656.31       0     560
Permanent Ineff=
       T       T
Bank Sta=409.12,577.17
XS Rating Curve= 0 ,0
Exp/Cntr=0.3,0.1

Type RM Length L Ch R = 1 ,272073  ,318,318,303
BEGIN DESCRIPTION:
This cross section corresponds to cross section 271952 of the non-georeferenced CDC model which was the source of this model.
Effective flow limit set at Brookside Levee in LOB.
Effective flow limit set at Crestwood Levee in ROB.
END DESCRIPTION:
XS GIS Cut Line= 2
 2312450.9816734 6965112.9823908 2313040.8440425 6965404.1803365
#Sta/Elev= 30
       0     552    5.96     552   22.97  547.71    43.1  541.53   62.97  539.83
   85.99  538.94  187.99  537.68  218.65  530.13  239.87  527.77  282.14  526.43
  294.19  525.14  319.25  525.72  334.31   527.3  340.17  527.43  424.45  526.61
  446.27  526.05  451.46  525.22  459.32     520  473.38   513.2  493.78  513.22
  516.95   511.9  536.09  512.14  542.36  513.32  545.58  515.72  548.28     516
  559.36     520  589.52  537.29  617.16  538.58  648.78     552  657.83     552
#Mann= 3 ,-1,0
       0     .06       0  451.46    .035       0  589.52     .06       0
#XS Ineff= 2 , 0
       0    5.96     560  648.78       0     560
Permanent Ineff=
       T       T
Bank Sta=451.46,589.52
XS Rating Curve= 0 ,0
Exp/Cntr=0.3,0.1

Type RM Length L Ch R = 1 ,271755  ,365,365,344
BEGIN DESCRIPTION:
This cross section corresponds to cross section 271634 of the non-georeferenced CDC model which was the source of this model.
Effective flow limit set at Brookside Levee in LOB.
Effective flow limit set at Crestwood Levee in ROB.
END DESCRIPTION:
XS GIS Cut Line= 2
   2312283.88736  6965406.855927 2312876.4745819 6965669.0041602
#Sta/Elev= 30
       0     552    5.39     552   47.68  540.26  127.81  537.49  150.19  530.69
  156.74  530.57  180.92  531.06  197.26  529.24  214.19   528.1     237  527.86
  264.71  526.32  356.73  526.02  393.52  526.82  425.53  525.76  433.05  524.68
  437.83  522.01  450.98  515.59  470.57     512  482.66  510.45  513.12  509.32
  526.02   509.6  534.72     511  549.09     520  551.64  522.31  574.67  536.57
  602.07  537.89  620.59     546  630.74     550  636.57     552  647.98     552
#Mann= 3 ,-1,0
       0     .06       0  433.05    .035       0  574.67     .06       0
#XS Ineff= 2 , 0
       0    5.39     560  636.57       0     560
Permanent Ineff=
       T       T
Bank Sta=433.05,574.67
XS Rating Curve= 0 ,0
Exp/Cntr=0.3,0.1

Type RM Length L Ch R = 1 ,271391  ,369,369,221
BEGIN DESCRIPTION:
This cross section corresponds to cross section 271269.5 of the non-georeferenced CDC model which was the source of this model.
Effective flow limit set at Brookside Levee in LOB.
Effective flow limit set at Crestwood Levee in ROB.
Rockwood Park in LOB.
END DESCRIPTION:
XS GIS Cut Line= 2
 2312101.6905253 6965754.0570576 2312714.7858973 6965984.8985877
#Sta/Elev= 30
       0     552    5.32     552   47.65  540.46   77.95  538.36  122.49  536.94
  137.12   534.3  249.64  534.31  263.69  531.59  325.17  530.81  355.38  529.45
  360.68  531.63  381.82  532.34   388.3  528.52  432.93     526  432.93  526.01
  442.26     520  445.25  517.46   445.6     518  457.03  514.41  469.61     512
   485.6  511.43  523.83  514.28  539.92  515.01  555.15     520  559.03  524.63
  575.25  536.14  603.15  537.77  623.34  545.14   644.8     552  655.11     552
#Mann= 3 ,-1,0
       0     .06       0  432.93    .035       0  575.25     .06       0
#XS Ineff= 2 , 0
       0    5.29     560   644.8       0     560
Permanent Ineff=
       T       T
Bank Sta=432.93,575.25
XS Rating Curve= 0 ,0
Exp/Cntr=0.3,0.1

Type RM Length L Ch R = 1 ,271022  ,336,336,213
BEGIN DESCRIPTION:
This cross section corresponds to cross section 270900.4 of the non-georeferenced CDC model which was the source of this model.
Effective flow limit set at Brookside Levee in LOB.
Effective flow limit set at Crestwood Levee in ROB.
Rockwood Park in LOB.
END DESCRIPTION:
XS GIS Cut Line= 2
 2312043.2985083 6966385.4362578   2312715.19633 6966258.6629983
#Sta/Elev= 30
       0     552    8.05     552   55.84  538.92   74.18     540  153.49  536.32
  163.27  535.98  209.99     535  227.61  535.11  292.55     534  340.82  532.54
  393.23  525.77  428.12  525.16  434.56  524.13  442.39     520  455.18  514.99
  473.54  516.36  489.63  516.17  501.04  517.17  509.81  517.43  511.92  517.63
  534.12  516.86  548.19  517.36  552.74  517.98  566.29     520  571.04  523.92
  586.96  533.69  625.13  536.31  645.87  543.72  677.33     552  683.75     552
#Mann= 3 ,-1,0
       0     .06       0  434.56    .035       0  586.96     .06       0
#XS Ineff= 2 , 0
       0    8.05     560  677.33       0     560
Permanent Ineff=
       T       T
Bank Sta=434.56,586.96
XS Rating Curve= 0 ,0
Exp/Cntr=0.3,0.1

Type RM Length L Ch R = 1 ,270686  ,311,311,246
BEGIN DESCRIPTION:
This cross section corresponds to cross section 270564.2 of the non-georeferenced CDC model which was the source of this model.
Effective flow limit set at Brookside Levee in LOB.
Effective flow limit set at Crestwood Levee in ROB.
Rockwood Park in LOB.
END DESCRIPTION:
XS GIS Cut Line= 2
  2312274.094017 6966900.5838098  2312840.779646 6966490.1505126
#Sta/Elev= 30
       0     552    7.98     552   38.79  538.57    49.1  539.08   74.62  539.12
  153.91     536  197.54     534  210.42  533.62  224.24  532.99  281.98  528.57
   298.1  528.52  308.16  528.83  334.51  527.32  353.23  525.79  366.79  525.52
  493.98  524.21  499.34  524.42   507.5     520  516.07  513.57  517.11  512.99
  518.74  513.07   521.9   512.9  528.13  513.51  549.94  515.14  569.32  516.31
  584.13     520  597.55   528.5  642.02  530.73  694.52     552  699.71     552
#Mann= 3 ,-1,0
       0     .06       0  499.34    .035       0  597.55    .055       0
#XS Ineff= 2 , 0
       0    7.93     560  694.52       0     560
Permanent Ineff=
       T       T
Bank Sta=499.34,597.55
XS Rating Curve= 0 ,0
Exp/Cntr=0.3,0.1