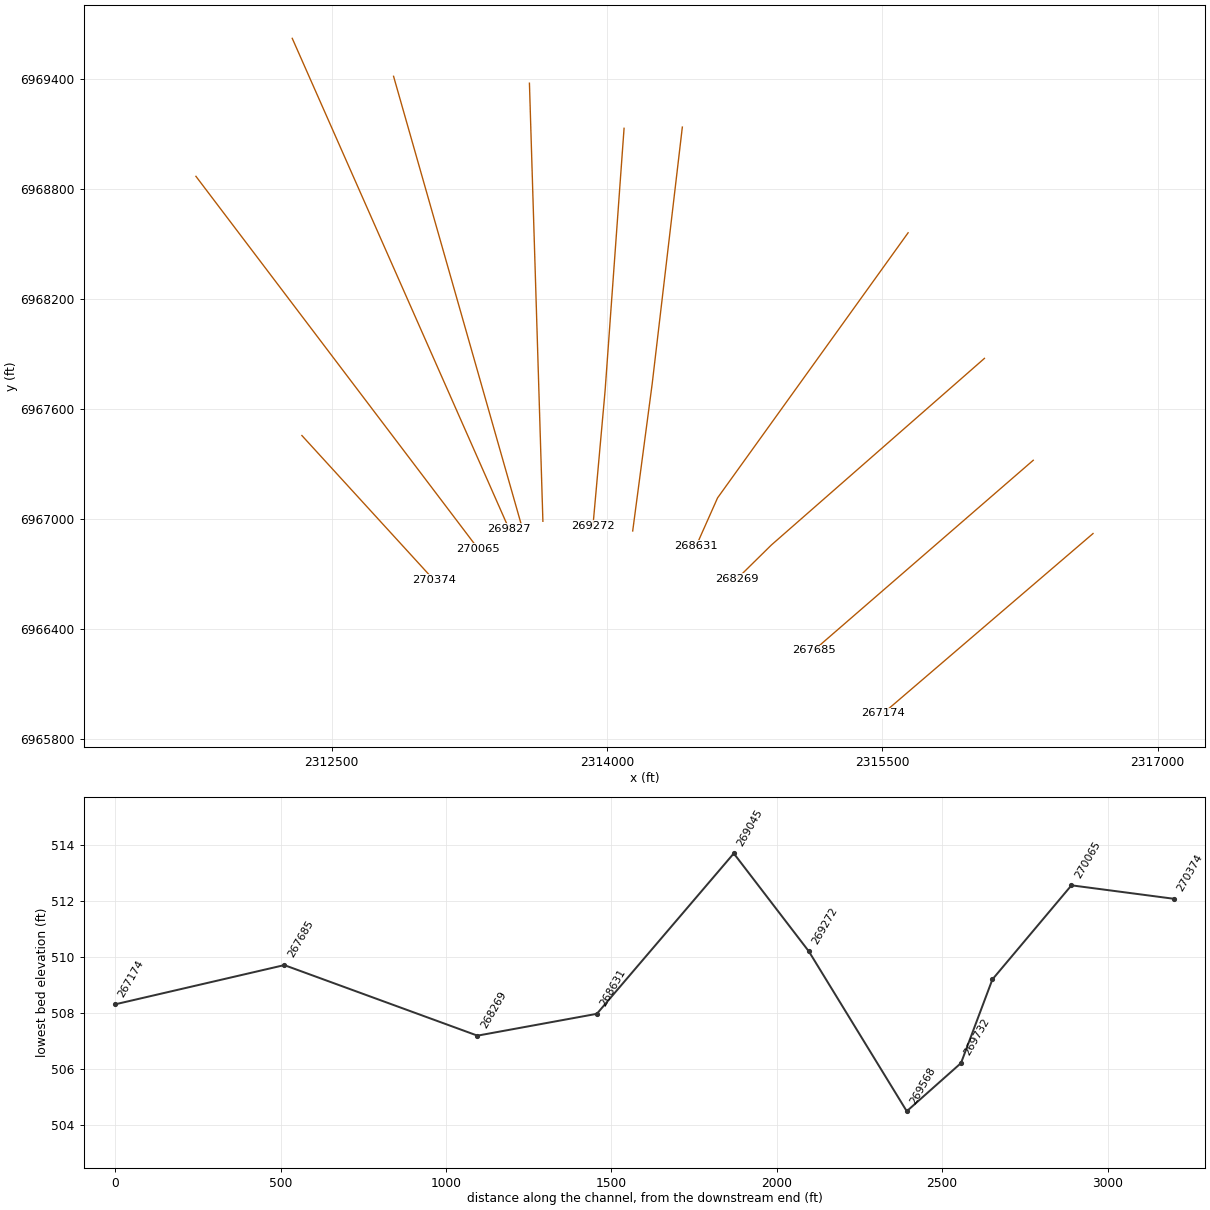
HEC-RAS study CDC_Consolidated_Model.prj: Upper Trinity CDC Consolidated Model

--- CDC_Consolidated_Model.g03 (geometry) --- (continued)

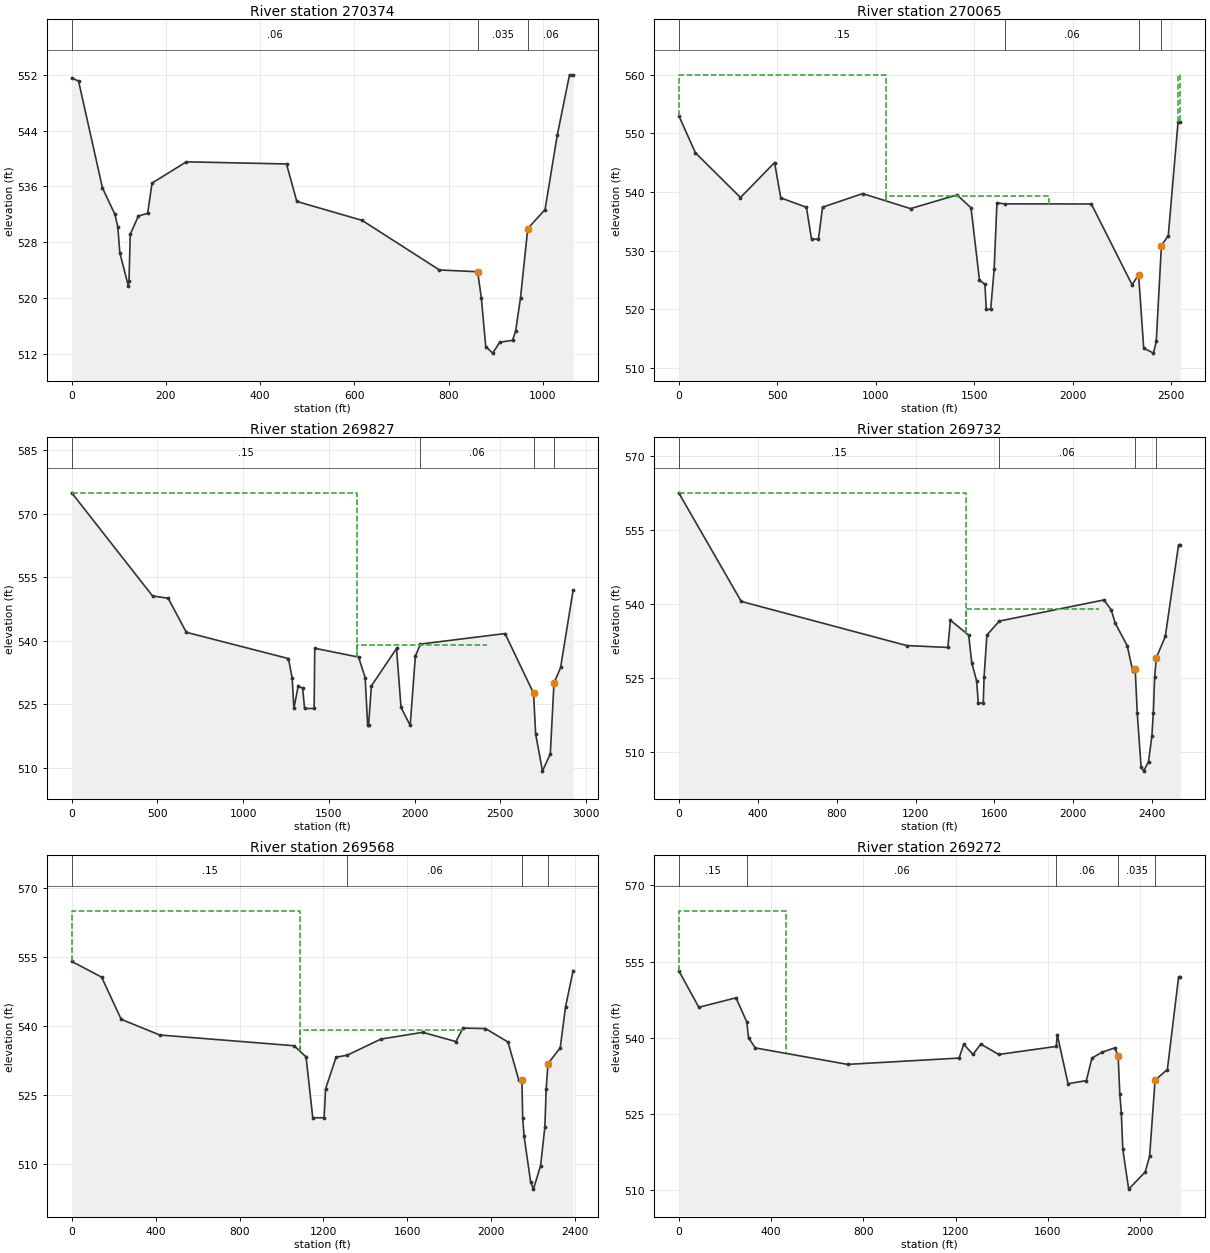
Type RM Length L Ch R = 1 ,270374  ,309,309,271
BEGIN DESCRIPTION:
This cross section corresponds to cross section 270252.7 of the non-georeferenced CDC model which was the source of this model.
Effective flow limit set at Crestwood Levee in ROB.
Rockwood Park in LOB.
Old West Fork river channel in LOB - Sump 12W outfall.
END DESCRIPTION:
XS GIS Cut Line= 2
 2312337.6313505  6967455.732081  2313055.406364 6966669.6056416
#Sta/Elev= 30
       0  551.56   14.54  551.09   65.25  535.77   91.53     532   97.86   530.2
  102.01  526.49  120.07  521.74   121.6   522.4  124.17  529.11  141.56  531.75
  161.11  532.12  170.51  536.47   243.5  539.52  455.96  539.21  477.84  533.83
  616.38  531.12  780.64     524  861.74  523.75  869.59     520  878.93  513.02
  893.69  512.07  908.72  513.64  935.82   513.9  942.46  515.25  952.74     520
  968.14  529.94 1004.85  532.67 1030.92  543.39 1056.77     552 1064.52     552
#Mann= 3 ,-1,0
       0     .06       0  861.74    .035       0  968.14     .06       0
#XS Ineff= 2 , 0
       0   243.5  539.52               0
Permanent Ineff=
       F       F
Bank Sta=861.74,968.14
XS Rating Curve= 0 ,0
Exp/Cntr=0.3,0.1

Type RM Length L Ch R = 1 ,270065  ,239,239,159
BEGIN DESCRIPTION:
This cross section corresponds to cross section 269944.1 of the non-georeferenced CDC model which was the source of this model.
Ineffective flow in LOB.
Effective flow limit set at Crestwood Levee in ROB.
Rockwood Park in LOB.
Old West Fork river channel in LOB - Sump 12W outfall.
END DESCRIPTION:
XS GIS Cut Line= 2
 2311760.2316922 6968869.5783104 2313297.2647568 6966839.1455683
#Sta/Elev= 30
       0     553   83.59  546.71  312.69  539.08  485.72  545.04  517.18  539.03
  647.46  537.41  673.35     532  708.66     532  729.33  537.43  932.96  539.75
 1176.13  537.19 1412.77  539.53 1483.38  537.33 1526.36  525.01 1554.13  524.28
 1560.87     520 1583.28     520 1600.95  526.85 1615.07  538.16 1655.79     538
  2094.6  537.98 2301.71  524.19 2334.51  525.93 2360.52   513.4 2410.21  512.55
 2424.27  514.55 2450.41  530.87 2485.32  532.59 2535.09     552 2546.59     552
#Mann= 4 ,-1,0
       0     .15       0 1655.79     .06       0 2334.51    .035       0
 2450.41     .06       0
#XS Ineff= 3 ,-1
       0 1052.67     560 2535.09 2546.59     560 1052.67 1878.98  539.31
Permanent Ineff=
       F       T       F
Bank Sta=2334.51,2450.41
XS Rating Curve= 0 ,0
Exp/Cntr=0.3,0.1

Type RM Length L Ch R = 1 ,269827  ,95,95,53
BEGIN DESCRIPTION:
This cross section corresponds to cross section 269705.5 of the non-georeferenced CDC model which was the source of this model.
Ineffective flow in LOB.
Effective flow limit set at Crestwood Levee in ROB.
Rockwood Park in LOB.
Old West Fork river channel in LOB - Sump 12W outfall.
END DESCRIPTION:
XS GIS Cut Line= 2
 2312284.9958912 6969622.2601929  2313466.466848 6966945.7924605
#Sta/Elev= 30
       0  574.97  471.53  550.59  562.53  550.06  668.66     542 1264.45  535.79
 1286.11   531.2 1296.24     524 1320.99  529.26 1347.11  528.81 1358.63     524
 1414.43     524 1417.92  538.23 1673.52  536.14 1712.13  531.27 1726.63     520
 1731.91     520 1748.36  529.33 1895.14  538.18 1921.24  524.24 1974.78     520
 2004.99  536.38 2034.78  539.22 2528.23  541.71 2694.67  527.59 2706.79  517.98
 2746.69  509.19 2792.41  513.28 2813.81     530 2852.36  533.69 2925.64     552
#Mann= 4 ,-1,0
       0     .15       0 2034.78     .06       0 2694.67    .035       0
 2813.81     .06       0
#XS Ineff= 2 ,-1
       0 1665.82 574.893 1665.82  2424.3     539
Permanent Ineff=
       F       F
Bank Sta=2694.67,2813.81
XS Rating Curve= 0 ,0
Exp/Cntr=0.3,0.1

Type RM Length L Ch R = 1 ,269732  ,164,164,85
BEGIN DESCRIPTION:
This cross section corresponds to cross section 269610.6 of the non-georeferenced CDC model which was the source of this model.
Ineffective flow in LOB.
Effective flow limit set at Crestwood Levee in ROB.
Rockwood Park in LOB.
Old West Fork river channel in LOB - Sump 12W outfall.
END DESCRIPTION:
XS GIS Cut Line= 2
 2312837.0971602 6969415.2222008   2313533.07037 6966969.8893684
#Sta/Elev= 30
       0   562.5  316.05  540.57  1154.4  531.64 1363.56  531.25 1376.39  536.77
 1469.18  533.73 1485.22  528.05 1509.43   524.5 1517.87     520 1543.31     520
 1547.12   525.2 1561.54  533.76 1624.37  536.59 2154.61  540.87 2192.08  538.86
 2211.87   536.2 2272.95  531.61 2300.67  526.56  2313.6  526.79  2323.9     518
 2343.26  507.12 2356.51   506.2 2381.24  508.15 2398.06  513.31 2405.48     518
 2412.24  525.32 2420.83  529.19 2466.15  533.47 2533.31     552 2542.45     552
#Mann= 4 ,-1,0
       0     .15       0 1624.37     .06       0  2313.6    .035       0
 2420.83     .06       0
#XS Ineff= 2 ,-1
       0  1453.6 562.569  1453.6 2131.91     539
Permanent Ineff=
       F       F
Bank Sta=2313.6,2420.83
XS Rating Curve= 0 ,0
Exp/Cntr=0.3,0.1

Type RM Length L Ch R = 1 ,269568  ,296,296,235
BEGIN DESCRIPTION:
This cross section corresponds to cross section 269446.7 of the non-georeferenced CDC model which was the source of this model.
Ineffective flow in LOB.
Effective flow limit set at Crestwood Levee in ROB.
Rockwood Park in LOB.
Old West Fork river channel in LOB - Sump 12W outfall.
END DESCRIPTION:
XS GIS Cut Line= 2
 2313577.4148564 6969377.5789413 2313650.8252601 6966988.0147794
#Sta/Elev= 30
       0     554  142.43  550.58  235.84  541.41  419.51     538 1060.47  535.66
 1117.23  533.23 1149.19     520  1203.3     520 1210.31   526.3  1260.4  533.17
 1313.92  533.61  1473.9  537.11 1673.82  538.58  1831.4  536.57 1866.04   539.5
  1972.4   539.4  2079.9  536.47 2131.38  528.24 2146.33  528.27 2150.08     520
 2156.69     516 2188.16     506 2201.38  504.48 2235.35  509.58  2255.9     518
 2262.04  526.27 2270.68  531.78 2329.01   535.2 2354.45  544.16 2390.69     552
#Mann= 4 ,-1,0
       0     .15       0 1313.92     .06       0 2146.33    .035       0
 2270.68     .06       0
#XS Ineff= 2 ,-1
       0 1086.44     565 1086.44 1866.04     539
Permanent Ineff=
       F       F
Bank Sta=2146.33,2270.68
XS Rating Curve= 0 ,0
Exp/Cntr=0.3,0.1

Type RM Length L Ch R = 1 ,269272  ,227,227,201
BEGIN DESCRIPTION:
This cross section corresponds to cross section 269150.5 of the non-georeferenced CDC model which was the source of this model.
Downstream of old West Fork channel - Sump 12W outfall.
Ineffective flow in LOB.
Effective flow limit set at Crestwood Levee in ROB.
Rockwood Park in LOB.
END DESCRIPTION:
XS GIS Cut Line= 3
 2314093.0585315 6969131.5963874 2313989.3920079 6967696.5975794
 2313923.5900351 6966963.8842953
#Sta/Elev= 30
       0  553.16    86.3     546  247.57  547.87  294.41   543.1  301.73     540
  331.32     538  731.24  534.76 1215.12     536 1234.76  538.73 1275.18  536.72
 1308.96  538.76 1386.82  536.71 1636.45   538.3  1640.5  540.64  1687.5  530.95
 1766.84  531.57 1790.96     536  1834.1  537.14 1889.47     538 1904.55   536.5
 1911.83  528.99 1918.51  525.13 1924.93     518 1950.39  510.19 2021.96  513.57
 2041.06  516.65 2064.76  531.65 2118.13  533.75 2166.91     552  2174.4     552
#Mann= 5 ,-1,0
       0     .15       0  294.41     .06       0 1636.45     .06       0
 1904.55    .035       0 2064.76     .06       0
#XS Ineff= 2 ,-1
       0  465.04     565  465.04 1904.55   536.5
Permanent Ineff=
       F       F
Bank Sta=1904.55,2064.76
XS Rating Curve= 0 ,0
Exp/Cntr=0.3,0.1

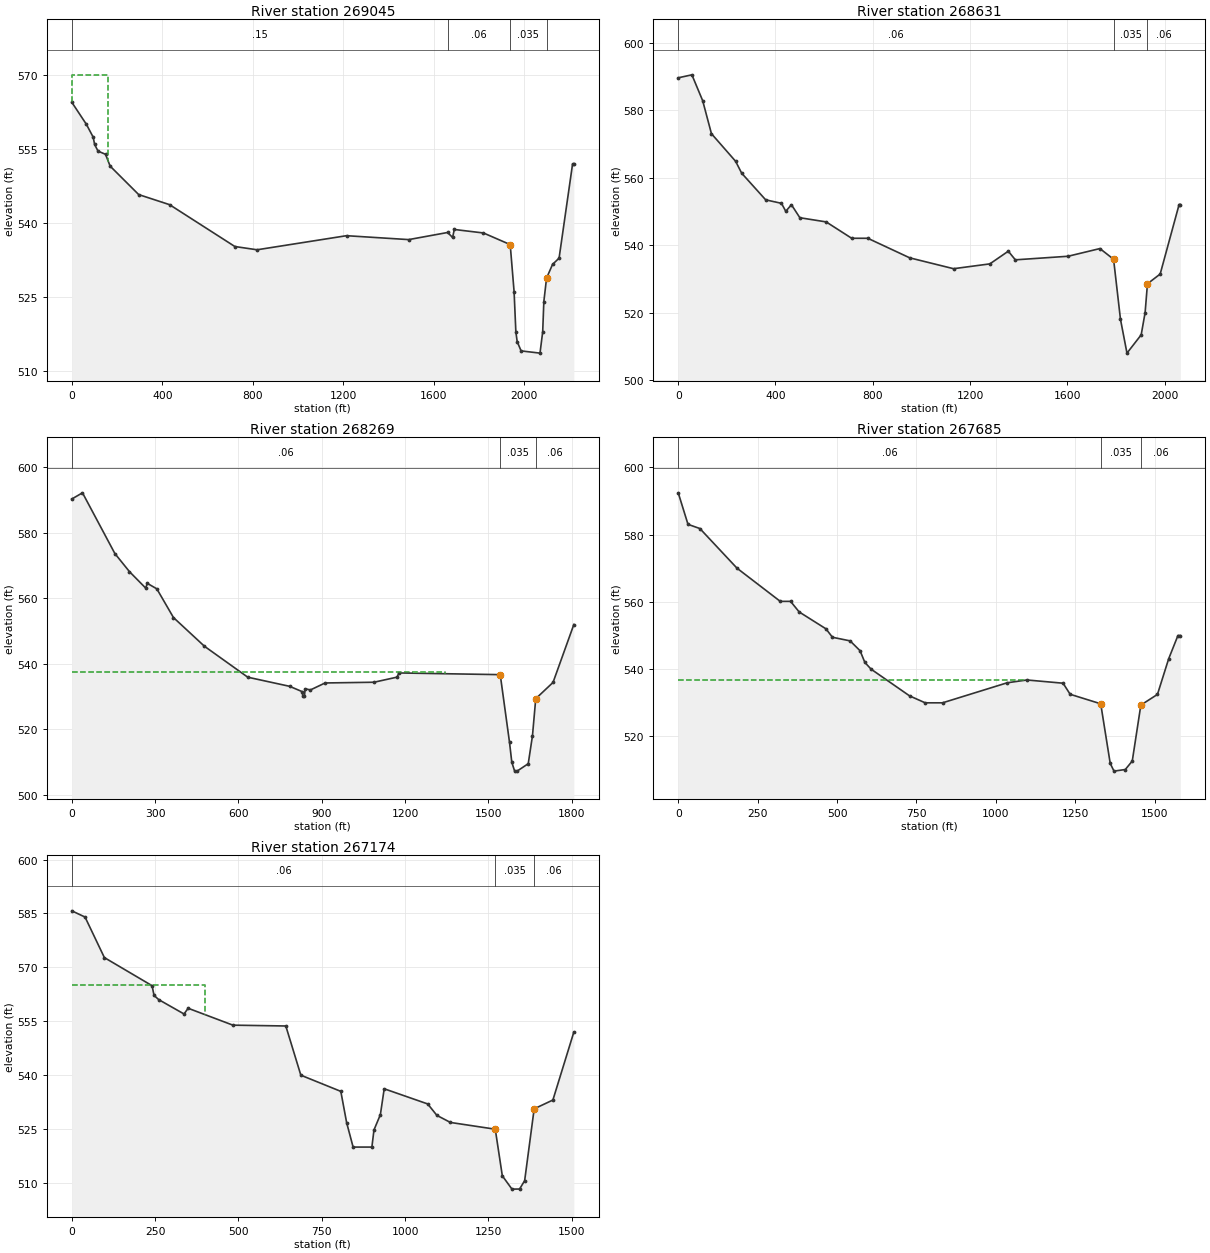
Type RM Length L Ch R = 1 ,269045  ,414,414,239
BEGIN DESCRIPTION:
This cross section corresponds to cross section 268923.7 of the non-georeferenced CDC model which was the source of this model.
Ineffective flow in LOB.
Effective flow limit set at Crestwood Levee in ROB.
Rockwood Park in LOB.
END DESCRIPTION:
XS GIS Cut Line= 3
 2314410.5678546 6969138.1062693 2314246.3454031 6967738.2347142
 2314140.1031099 6966935.2286812
#Sta/Elev= 30
       0  564.46   64.42     560   94.64  557.39  101.04  555.91  116.13  554.56
  149.17  553.92   169.6  551.53  295.82  545.77  432.33  543.73  721.02  535.26
  819.13   534.6 1214.47  537.45 1489.39  536.66  1661.5   538.1 1683.57  537.09
 1690.94  538.71    1820     538 1938.14  535.65 1955.31  526.14 1963.12     518
 1968.98  516.02 1986.31  514.14 2069.86  513.69 2081.77     518 2086.86  524.13
 2098.85  528.87 2125.41  531.65 2154.23  532.91 2213.97     552 2219.47     552
#Mann= 4 ,-1,0
       0     .15       0  1661.5     .06       0 1938.14    .035       0
 2098.85     .06       0
#XS Ineff= 1 ,-1
       0  161.86     570
Permanent Ineff=
       F
Bank Sta=1938.14,2098.85
XS Rating Curve= 0 ,0
Exp/Cntr=0.3,0.1

Type RM Length L Ch R = 1 ,268631  ,361,361,232
BEGIN DESCRIPTION:
This cross section corresponds to cross section 268509.5 of the non-georeferenced CDC model which was the source of this model.
Effective flow limit set at Crestwood Levee in ROB.
Rockwood Park in LOB.
END DESCRIPTION:
XS GIS Cut Line= 3
 2315640.7218795 6968561.5741459 2314602.5787744 6967115.7154663
  2314486.829767 6966855.3252486
#Sta/Elev= 30
       0  589.56   56.17  590.44  100.56  582.77  136.55     573  235.92  564.82
  261.03  561.28  359.62  553.39  424.53  552.36  442.25     550  465.57  551.94
  500.19  548.09  608.41  546.85  713.32     542  779.62     542  952.07   536.2
  1132.3  532.98  1281.6  534.41  1357.5  538.17 1386.43  535.61 1603.37  536.67
 1734.32  538.95 1790.47  535.78 1818.79     518 1845.56  507.96    1904  513.38
  1920.2     520 1929.78  528.51 1982.13   531.4 2059.95     552 2064.92     552
#Mann= 3 ,-1,0
       0     .06       0 1790.47    .035       0 1929.78     .06       0
Bank Sta=1790.47,1929.78
XS Rating Curve= 0 ,0
Exp/Cntr=0.3,0.1

Type RM Length L Ch R = 1 ,268269  ,584,584,574
BEGIN DESCRIPTION:
This cross section corresponds to cross section 268148 of the non-georeferenced CDC model which was the source of this model.
Rockwood Park in LOB.
Effective flow limit set at Crestwood Levee in ROB.
END DESCRIPTION:
XS GIS Cut Line= 3
  2316056.660756  6967876.541183  2314895.577905 6966858.5131669
 2314707.7108512 6966673.3810775
#Sta/Elev= 30
       0  590.36   38.62  592.25  155.21  573.69  207.86  568.15  266.09  563.14
  272.09  564.58  306.28   562.9  366.18  554.13  477.78  545.35  633.82  535.89
  784.69   533.1  829.63  531.48  832.23     530  837.53     530  840.59  532.35
  859.42     532  912.25  534.13 1088.17  534.35 1171.26  535.91  1178.2  537.19
 1542.89  536.67 1576.27     516 1584.52  509.91 1594.66   507.2 1603.55  507.18
 1643.72  509.45 1658.96     518 1670.75  529.32 1733.05   534.3 1807.94     552
#Mann= 3 ,-1,0
       0     .06       0 1542.89    .035       0 1670.75     .06       0
#XS Ineff= 2 , 0
       0 1345.36  537.41               0
Permanent Ineff=
       F       F
Bank Sta=1542.89,1670.75
XS Rating Curve= 0 ,0
Exp/Cntr=0.3,0.1

Type RM Length L Ch R = 1 ,267685  ,511,511,510
BEGIN DESCRIPTION:
This cross section corresponds to cross section 267563.7 of the non-georeferenced CDC model which was the source of this model.
Rockwood Park in LOB.
Effective flow limit set at Crestwood Levee in ROB.
END DESCRIPTION:
XS GIS Cut Line= 2
 2316322.6662265 6967320.8747503 2315128.6425903 6966285.2088901
#Sta/Elev= 30
       0  592.41   30.73  583.04   68.13   581.8  185.17     570  321.27  560.15
  353.71  560.15  380.68  557.01  464.89     552  485.56  549.48  541.11  548.41
  572.37  545.49  587.54     542  607.19     540  728.55  532.05  777.47     530
  832.04     530 1035.46  535.95 1097.77  536.79 1211.53  535.83 1233.78  532.54
 1330.04  529.71 1359.94     512 1371.83   509.7 1407.44  510.18 1429.34   512.7
 1456.36  529.33 1508.63   532.5 1543.81  543.05 1573.14     550  1580.6     550
#Mann= 3 ,-1,0
       0     .06       0 1330.04    .035       0 1456.36     .06       0
#XS Ineff= 2 , 0
       0 1091.35  536.77               0
Permanent Ineff=
       F       F
Bank Sta=1330.04,1456.36
XS Rating Curve= 0 ,0
Exp/Cntr=0.3,0.1

Type RM Length L Ch R = 1 ,267174  ,211,211,176
BEGIN DESCRIPTION:
This cross section corresponds to cross section 267052.2 of the non-georeferenced CDC model which was the source of this model.
Downstream of Sump 13W outfall.
Ineffective flow in LOB to model all flows: Set at sta 399.88 to represent ineffective flow for the more frequent flood flows (up to 50-year).  For 100-year and rarer events the entire floodplain is effective since flow overtops low point in University Drive roadway in LOB.
Rockwood Park in LOB.
Effective flow limit set at Crestwood Levee in ROB.
END DESCRIPTION:
XS GIS Cut Line= 2
 2316648.3405147 6966921.1841322 2315504.8576535 6965940.2267663
#Sta/Elev= 30
       0  585.73   39.81     584   97.85  572.72  240.91   564.9  246.94  562.19
  261.01  561.02  336.85  557.03   349.2  558.62  483.52  553.92  642.28  553.69
   687.4     540  807.34   535.5  824.78   526.8  844.22     520  900.56     520
  906.85  524.77  926.04  529.02  937.53  536.22 1068.08     532 1095.61  528.82
 1136.33  526.85 1270.79  524.97 1291.97     512 1320.94   508.3 1343.82  508.33
 1358.99  510.66 1387.51  530.63 1387.51  530.64 1443.73  533.09 1506.59     552
#Mann= 3 ,-1,0
       0     .06       0 1270.79    .035       0 1387.51     .06       0
#XS Ineff= 2 ,-1
       0  399.88     565  399.88  937.42  535.75
Permanent Ineff=
       F       F
Bank Sta=1270.79,1387.51
XS Rating Curve= 0 ,0
Exp/Cntr=0.3,0.1