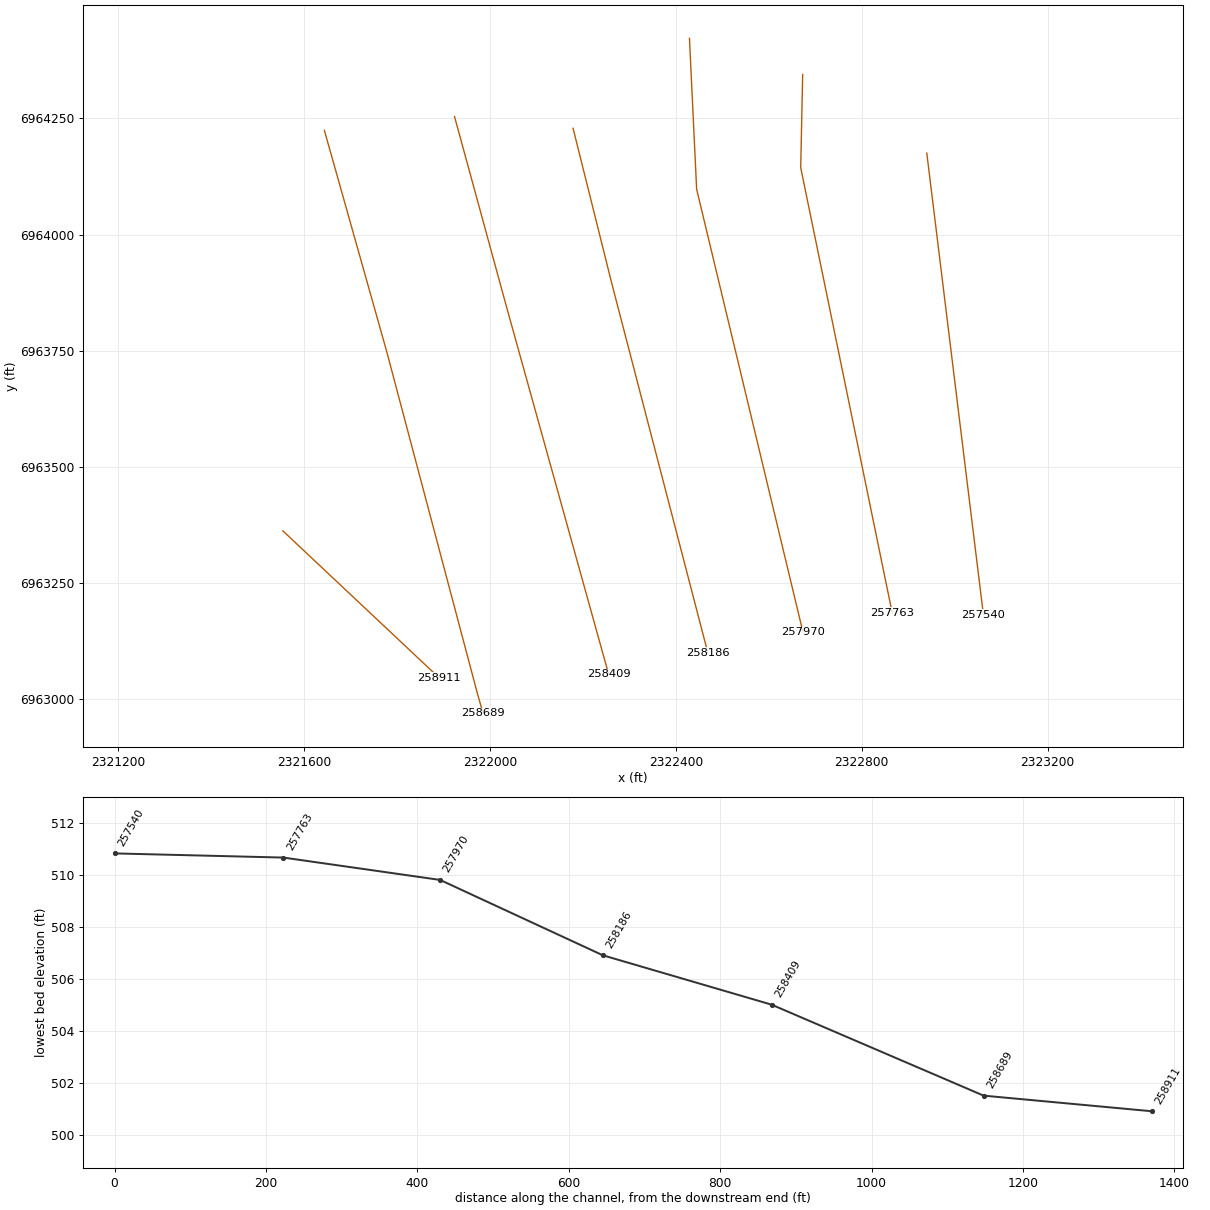
HEC-RAS study CDC_Consolidated_Model.prj: Upper Trinity CDC Consolidated Model

--- CDC_Consolidated_Model.g03 (geometry) --- (continued)

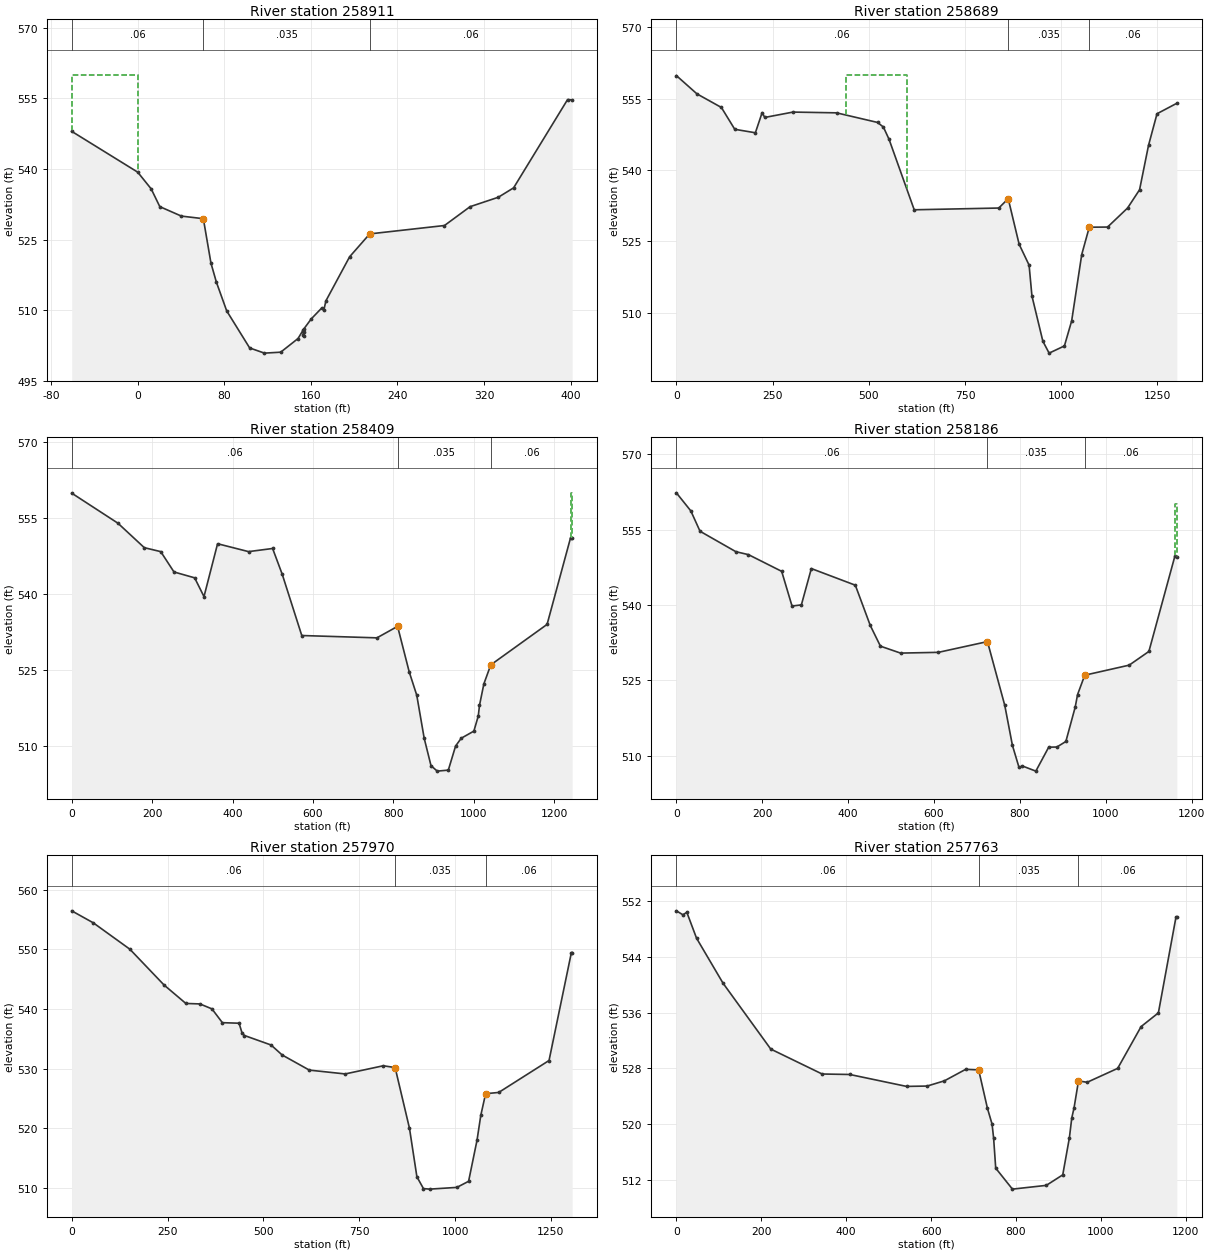
Type RM Length L Ch R = 1 ,258911  ,222,222,98
BEGIN DESCRIPTION:
This cross section corresponds to cross section 258790 of the non-georeferenced CDC model which was the source of this model.
Downstream of Henderson Street.
Cross-section skewed.
END DESCRIPTION:
XS GIS Cut Line= 2
2321554.412542526963362.497848852321891.232584336963045.72543424
#Sta/Elev= 30
     -61     548       0  539.33  12.471  535.77    20.4  532.01  40.348     530
   60.64  529.45  67.688     520  72.652     516  82.212  509.87 103.431     502
 117.075   500.9 132.097   501.1 148.122     504  153.14  505.91 153.155   504.8
  153.24  504.54 153.263  505.29  153.37     506 160.295  508.16  169.84  510.44
 171.985  510.04 173.869     512 195.786  521.36 214.347  526.22 283.436     528
 307.092     532 333.145     534 347.294     536 397.148  554.74 401.377  554.67
#Mann= 3 ,-1,0
     -61     .06       0   60.64    .035       0 214.347     .06       0
#XS Ineff= 1 ,-1
     -61       0     560
Permanent Ineff=
       F
Bank Sta=60.64,214.347
XS Rating Curve= 0 ,0
Skew Angle= 40
Exp/Cntr=0.5,0.3

Type RM Length L Ch R = 1 ,258689  ,280,280,284
BEGIN DESCRIPTION:
This cross section corresponds to cross section 258568.1 of the non-georeferenced CDC model which was the source of this model.
Effective flow in ROB set at Clear Fork Levee Loop.
Ineffective flow in LOB due to Henderson Street.
Oakwood Cemetery in LOB.
END DESCRIPTION:
XS GIS Cut Line= 4
 2321643.8179219 6964224.2531043 2321777.9794876 6963748.1522685
 2321973.1695103 6963012.1898772 2321985.3248505 6962969.6643359
#Sta/Elev= 30
       0  559.84    53.4     556  116.95  553.14  151.71  548.55  205.25  547.82
  222.83  552.06  229.61  551.04  303.08  552.17  416.16  552.01  522.73  549.99
   537.9  549.02   552.5  546.46  617.94  531.63  837.73     532  862.16  533.97
  890.54  524.39  916.41     520  923.81  513.52  952.21     504  968.46   501.5
 1008.18  503.01 1027.02  508.27 1053.21  522.23 1072.79  527.97 1120.33     528
 1172.31     532 1203.48  535.85 1226.71  545.17  1248.8  551.82 1300.28  554.02
#Mann= 3 ,0,0
       0     .06       0  862.16    .035       0 1072.79     .06       0
#XS Ineff= 1 ,-1
     440     600     560
Permanent Ineff=
       F
Bank Sta=862.16,1072.79
XS Rating Curve= 0 ,0
Exp/Cntr=0.3,0.1

Type RM Length L Ch R = 1 ,258409  ,223,223,218
BEGIN DESCRIPTION:
This cross section corresponds to cross section 258288 of the non-georeferenced CDC model which was the source of this model.
Effective flow in ROB set at Clear Fork Levee Loop.
Oakwood Cemetery in LOB.
END DESCRIPTION:
XS GIS Cut Line= 3
 2321923.9103327  6964253.856499 2322035.6885404 6963844.7919156
 2322255.4714645 6963054.0792867
#Sta/Elev= 30
       0  559.94  114.98     554   180.6  549.16  221.49  548.38  254.43  544.36
  305.83   543.2  329.05  539.49  362.86  549.94  439.94  548.38  499.74     549
  523.72  543.89  572.28   531.8  759.25  531.34  810.58  533.61  839.44  524.63
  858.27     520  876.77  511.49   893.7  506.08  909.17     505  936.78   505.2
  954.87  509.96  968.87   511.5 1000.35  512.91  1011.3   515.9  1014.3     518
 1025.21  522.25 1042.36     526 1182.42     534 1240.89  551.14 1244.75  551.07
#Mann= 3 ,0,0
       0     .06       0  810.58    .035       0 1042.36     .06       0
#XS Ineff= 2 , 0
       0                 1240.89       0     560
Permanent Ineff=
       F       T
Bank Sta=810.58,1042.36
XS Rating Curve= 0 ,0
Exp/Cntr=0.3,0.1

Type RM Length L Ch R = 1 ,258186  ,215,215,209
BEGIN DESCRIPTION:
This cross section corresponds to cross section 258064.6 of the non-georeferenced CDC model which was the source of this model.
Effective flow in ROB set at Clear Fork Levee Loop.
Oakwood Cemetery in LOB.
END DESCRIPTION:
XS GIS Cut Line= 3
 2322178.9536475 6964228.8076622 2322262.4556903 6963894.3159428
 2322468.9936702 6963100.1270816
#Sta/Elev= 30
       0  562.31   33.66  558.71   55.09  554.66  138.56  550.59  167.91     550
   245.2  546.68  269.31  539.77  291.09     540  314.31  547.23  416.71  543.92
  451.53   535.9  475.15  531.78  522.05   530.4  610.11  530.55   724.4  532.69
  764.68     520  782.55  512.02   797.9  507.63  805.84  507.92  837.04   506.9
  867.02  511.67  886.07   511.7  906.96   512.8  928.75  519.66  934.25  522.15
  950.93     526 1054.43     528 1100.31  530.73  1160.6  549.64 1165.36  549.63
#Mann= 3 ,0,0
       0     .06       0   724.4    .035       0  950.93     .06       0
#XS Ineff= 2 , 0
       0                  1160.6       0     560
Permanent Ineff=
       F       T
Bank Sta=724.4,950.93
XS Rating Curve= 0 ,0
Exp/Cntr=0.3,0.1

Type RM Length L Ch R = 1 ,257970  ,207,207,195
BEGIN DESCRIPTION:
This cross section corresponds to cross section 257849.1 of the non-georeferenced CDC model which was the source of this model.
Effective flow in ROB set at Clear Fork Levee Loop.
Oakwood Cemetery in LOB.
END DESCRIPTION:
XS GIS Cut Line= 3
  2322429.442923 6964422.3671031 2322444.9119299 6964097.6241314
 2322673.7871168 6963144.2925385
#Sta/Elev= 30
       0  556.43   56.32  554.42  151.75     550  240.97     544  297.87  540.91
  334.59  540.83  365.89     540   393.1  537.69  436.59   537.6  444.26     536
  450.67  535.54  520.09  533.95  548.98  532.28  619.98  529.74  713.54   529.1
  812.82  530.47  843.71  530.17  881.17     520  900.52  511.87  917.65  509.89
  933.89   509.8 1004.77  510.09  1035.4  511.11 1057.41     518 1067.23  522.16
 1079.78  525.79 1113.97     526 1245.24  531.35 1303.48  549.42 1305.53  549.43
#Mann= 3 ,0,0
       0     .06       0  843.71    .035       0 1079.78     .06       0
Bank Sta=843.71,1079.78
XS Rating Curve= 0 ,0
Exp/Cntr=0.3,0.1

Type RM Length L Ch R = 1 ,257763  ,223,223,194
BEGIN DESCRIPTION:
This cross section corresponds to cross section 257641.7 of the non-georeferenced CDC model which was the source of this model.
Effective flow in ROB set at Clear Fork Levee Loop.
END DESCRIPTION:
XS GIS Cut Line= 3
 2322673.1006857 6964344.4880913 2322668.8676291 6964144.1627343
 2322865.8317424 6963185.7086412
#Sta/Elev= 30
       0  550.62   15.45  550.05   24.59  550.41   47.52  546.69   109.9  540.23
  222.33  530.77  343.31  527.19  408.61  527.12  542.17  525.41  590.78  525.46
  631.36  526.21  681.46  527.86  712.07  527.78  732.74  522.26  743.62     520
  747.27     518  752.22  513.67   791.6  510.66   871.4   511.2  910.12  512.71
   925.7     518  931.41  520.89   936.7  522.31  947.22   526.2  967.59     526
  1039.5     528 1094.71     534 1135.42  535.97 1176.96  549.76 1178.85  549.75
#Mann= 3 ,0,0
       0     .06       0  712.07    .035       0  947.22     .06       0
#XS Ineff= 2 , 0
       0  712.07  527.78               0
Permanent Ineff=
       F       F
Bank Sta=712.07,947.22
XS Rating Curve= 0 ,0
Exp/Cntr=0.3,0.1

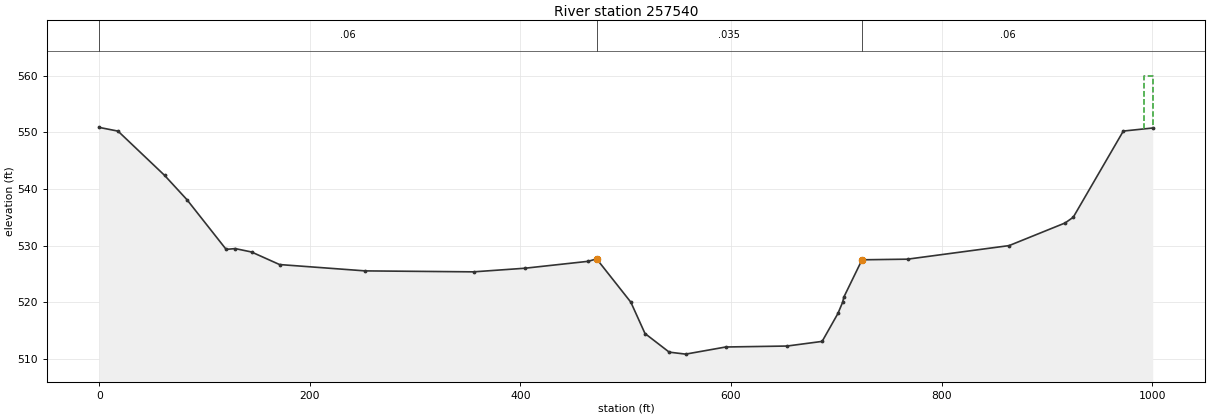
Type RM Length L Ch R = 1 ,257540  ,149,149,89
BEGIN DESCRIPTION:
This cross section corresponds to cross section 257418.7 of the non-georeferenced CDC model which was the source of this model.
Effective flow in LOB set at North Main Levee.
Effective flow in ROB set at Clear Fork Levee Loop.
END DESCRIPTION:
XS GIS Cut Line= 2
  2322940.201205 6964175.3792096 2323062.0031217 6963182.2689667
#Sta/Elev= 30
       0  550.88   17.73  550.23   61.92  542.42   83.23  538.11  120.45  529.33
  129.08  529.47  144.54  528.87  171.17  526.65  252.48  525.53  355.41  525.36
  404.25     526  464.25  527.22  472.35  527.65  504.83     520  518.29  514.46
  541.28  511.17  556.93  510.82  594.95  512.08  653.25  512.25  686.53  513.07
  701.52     518  706.03     520   707.1  520.88  724.41  527.49  767.64   527.6
  864.13     530  917.33     534  925.04  535.01   972.6  550.24 1000.55  550.78
#Mann= 3 ,0,0
       0     .06       0  472.35    .035       0  724.41     .06       0
#XS Ineff= 2 , 0
       0  472.35  527.65  991.84       0     560
Permanent Ineff=
       F       T
Bank Sta=472.35,724.41
XS Rating Curve= 0 ,0
Exp/Cntr=0.3,0.1