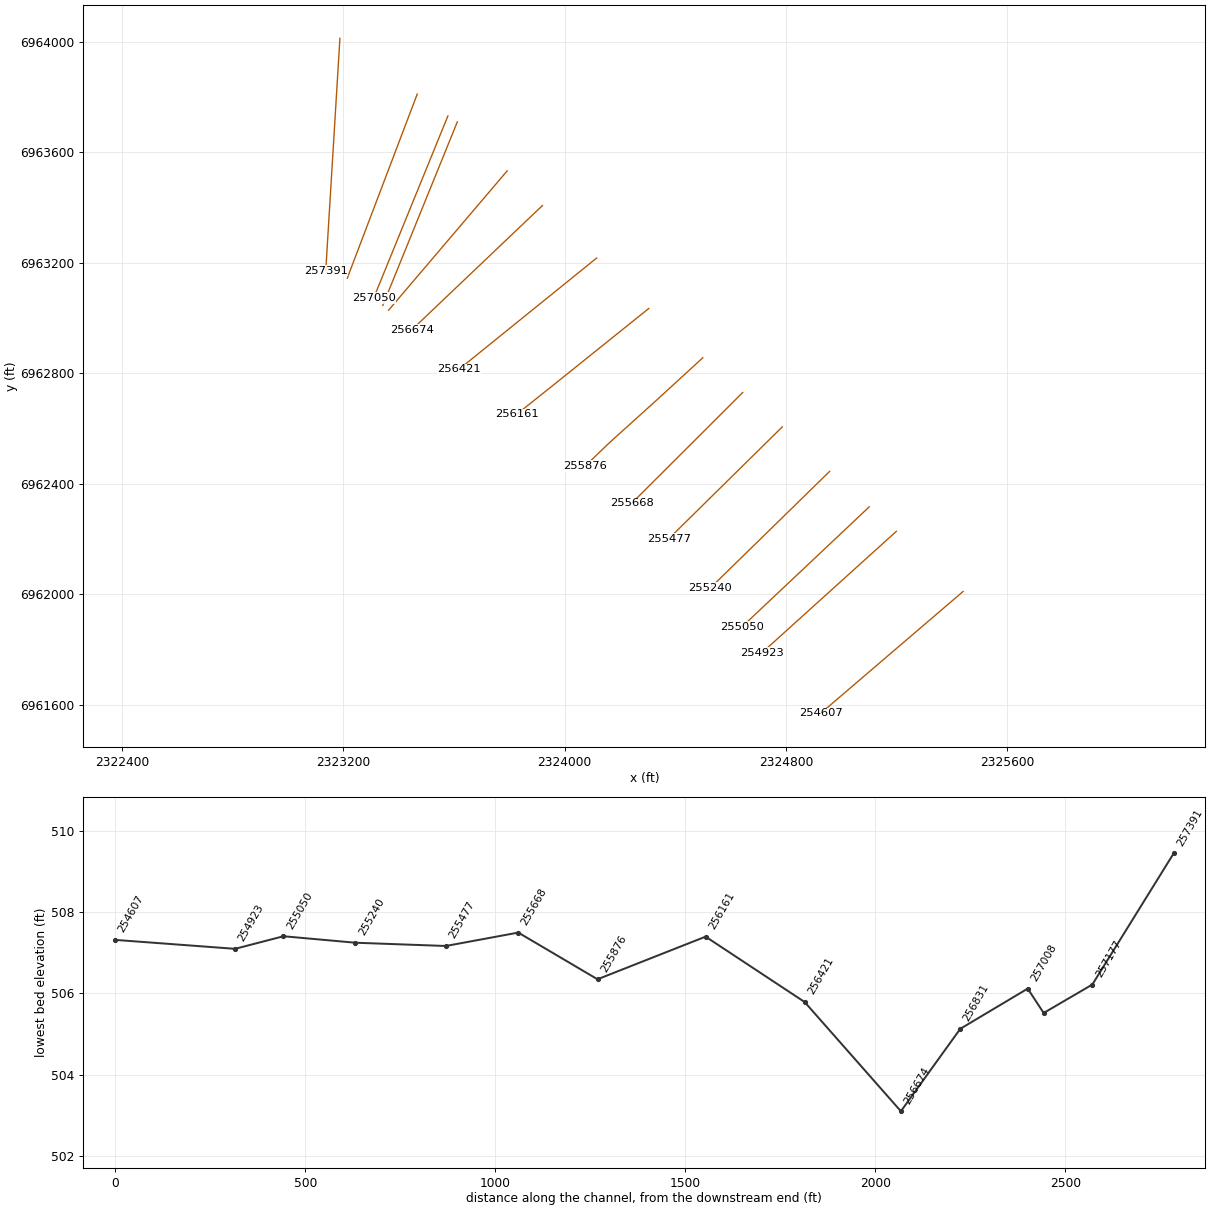
HEC-RAS study CDC_Consolidated_Model.prj: Upper Trinity CDC Consolidated Model

--- CDC_Consolidated_Model.g03 (geometry) --- (continued)

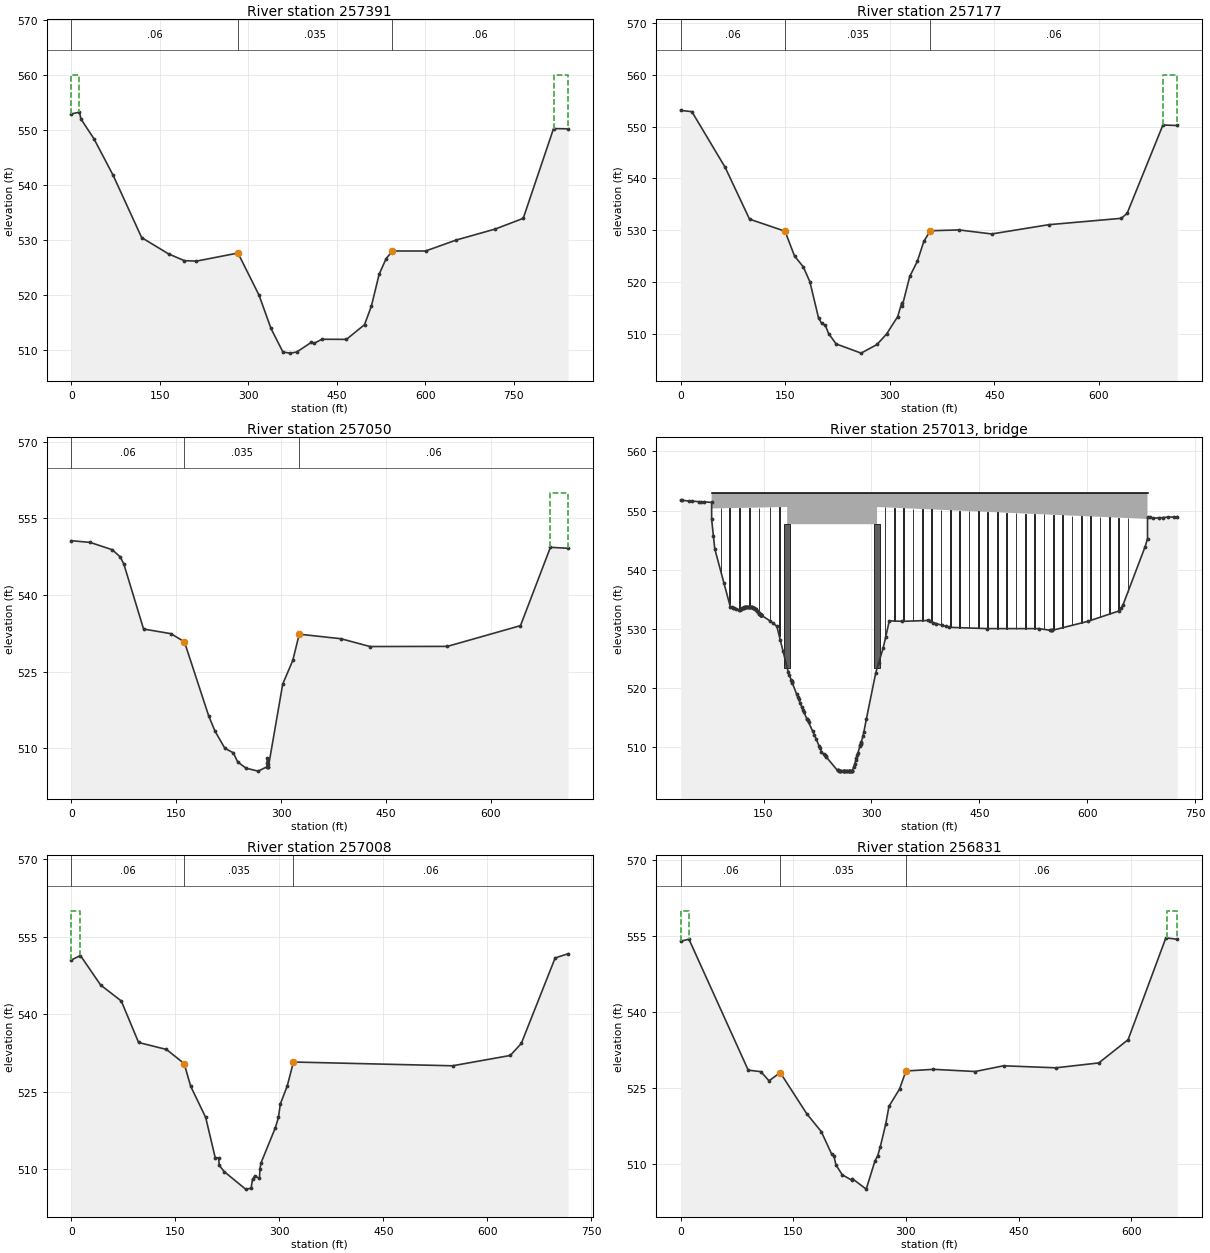
Type RM Length L Ch R = 1 ,257391  ,214,214,116
BEGIN DESCRIPTION:
This cross section corresponds to cross section 257269.8 of the non-georeferenced CDC model which was the source of this model.
Effective flow in LOB set at North Main Levee.
Effective flow in ROB set at Clear Fork Levee Loop.
END DESCRIPTION:
XS GIS Cut Line= 2
 2323187.7692267 6964011.6090637 2323136.6185069 6963171.3536102
#Sta/Elev= 30
       0   552.9   13.55  553.23   15.89     552   38.14  548.37   70.68  541.73
  118.99  530.43  164.57  527.47  191.26  526.25   211.7  526.16  282.17  527.63
  317.83     520  338.18  513.93  358.42  509.65  370.51  509.45   381.6  509.64
  406.29  511.39  410.85  511.22  424.66  511.97   466.1  511.95  496.75  514.62
   508.4     518  521.52  523.78  533.43  526.63  544.01     528  600.24     528
  652.39     530  718.62     532  765.77  533.93  817.18  550.24  841.81  550.19
#Mann= 3 ,-1,0
       0     .06       0  282.17    .035       0  544.01     .06       0
#XS Ineff= 3 ,-1
       0   13.55     560  817.18  841.81     560   13.55  282.17  527.63
Permanent Ineff=
       T       T       F
Bank Sta=282.17,544.01
XS Rating Curve= 0 ,0
Exp/Cntr=0.3,0.1

Type RM Length L Ch R = 1 ,257177  ,128,128,116
BEGIN DESCRIPTION:
This cross section corresponds to cross section 257056.1 of the non-georeferenced CDC model which was the source of this model.
Effective flow in LOB set at North Main Levee.
Effective flow in ROB set at Clear Fork Levee Loop.
END DESCRIPTION:
XS GIS Cut Line= 2
 2323467.0931459 6963809.8422661   2323214.26093 6963143.7015207
#Sta/Elev= 30
       0  553.12   16.04  552.89   63.77  542.13   98.79  532.11  149.71  529.78
   163.4  524.97  175.96  522.89   185.4     520  197.77  513.04  202.11     512
  207.51   511.6  212.25     510  223.03     508  258.89  506.22  281.72  507.89
  295.33   509.9  311.35  513.27  317.37     516   317.9  515.35  328.68  521.05
  339.51  523.94  348.99  527.86  358.35  529.87  399.15  530.03  446.29  529.25
  528.13  531.04  632.12  532.27  640.54  533.23  691.91   550.3  712.51  550.21
#Mann= 3 ,-1,0
       0     .06       0  149.71    .035       0  358.35     .06       0
#XS Ineff= 2 , 0
       0                  691.91       0     560
Permanent Ineff=
       F       T
Bank Sta=149.71,358.35
XS Rating Curve= 0 ,0
Exp/Cntr=0.5,0.3

Type RM Length L Ch R = 1 ,257050  ,42,42,41
BEGIN DESCRIPTION:
This cross section corresponds to cross section 256928.4 of the non-georeferenced CDC model which was the source of this model.
Upstream of the Fort Worth and Western Railroad.
Effective flow in LOB set at North Main Levee.
Effective flow in ROB set at Clear Fork Levee Loop.
END DESCRIPTION:
XS GIS Cut Line= 2
 2323578.0293574 6963730.8911514 2323309.8003428 6963072.3353724
#Sta/Elev= 30
       0  550.63   26.82  550.29   58.41  548.86   69.96  547.43   75.08     546
  103.19  533.34  142.29  532.43   161.7  530.84  196.51  516.31  205.49  513.35
  219.56     510  231.82   509.1  238.01  507.31  249.93   506.1  267.21  505.52
  280.18  506.38  280.58  507.08  280.63     508  280.68  506.96  281.08  506.35
   281.9  506.32  302.46  522.56  316.86  527.19  326.11  532.33  385.77  531.44
   427.5  529.91  538.26  529.94  642.93     534  685.78  549.33  711.09  549.15
#Mann= 3 ,-1,0
       0     .06       0   161.7    .035       0  326.11     .06       0
#XS Ineff= 2 , 0
       0                  685.78       0     560
Permanent Ineff=
       F       T
Bank Sta=161.7,326.11
XS Rating Curve= 0 ,0
Exp/Cntr=0.5,0.3

Type RM Length L Ch R = 3 ,257013  ,,,
BEGIN DESCRIPTION:
Tarantula Railroad
Data from USACE 1975 survey, Fort Worth Floodway DPR.
Note:  Internal bridge cross-sections modified to represent geometry under bridge.
END DESCRIPTION:
Node Name=Tarantula RR
Bridge Culvert--1,0,-1,-1, 0
Deck Dist Width WeirC Skew NumUp NumDn MinLoCord MaxHiCord MaxSubmerge Is_Ogee
15.9,10,2.6,0, 6, 6, , , 0.95, 0, 0,0,,
   77.84  182.84  182.84  307.84  307.84  683.84
     553     553     553     553     553     553
  550.36   550.6  547.69  547.69   550.6  548.58
   70.34  175.34  175.34  300.34  300.34  676.34
     553     553     553     553     553     553
  550.36   550.6  547.69  547.69   550.6  548.58
Pier Skew, UpSta & Num, DnSta & Num=  ,90.84, 2 ,83.34, 2 , 0 , 0 , 0 ,,
       1       1
     450     552
       1       1
     450     552
Pier Skew, UpSta & Num, DnSta & Num=  ,102.84, 2 ,95.34, 2 , 0 , 0 , 0 ,,
       1       1
     450     552
       1       1
     450     552
Pier Skew, UpSta & Num, DnSta & Num=  ,116.84, 2 ,109.34, 2 , 0 , 0 , 0 ,,
       1       1
     450     552
       1       1
     450     552
Pier Skew, UpSta & Num, DnSta & Num=  ,130.84, 2 ,123.34, 2 , 0 , 0 , 0 ,,
       1       1
     450     552
       1       1
     450     552
Pier Skew, UpSta & Num, DnSta & Num=  ,143.84, 2 ,136.34, 2 , 0 , 0 , 0 ,,
       1       1
     450     552
       1       1
     450     552
Pier Skew, UpSta & Num, DnSta & Num=  ,158.84, 2 ,151.34, 2 , 0 , 0 , 0 ,,
       1       1
     450     552
       1       1
     450     552
Pier Skew, UpSta & Num, DnSta & Num=  ,171.84, 2 ,161.34, 2 , 0 , 0 , 0 ,,
       1       1
     450     552
       1       1
     450     552
Pier Skew, UpSta & Num, DnSta & Num=  ,182.84, 2 ,175.34, 2 , 0 , 0 , 0 ,,
       8       8
     450  547.69
       8       8
     450  547.69
Pier Skew, UpSta & Num, DnSta & Num=  ,307.84, 2 ,300.34, 2 , 0 , 0 , 0 ,,
       8       8
     450  547.69
       8       8
     450  547.69
Pier Skew, UpSta & Num, DnSta & Num=  ,318.84, 2 ,311.34, 2 , 0 , 0 , 0 ,,
       1       1
   505.9   550.6
       1       1
   505.9   550.6
Pier Skew, UpSta & Num, DnSta & Num=  ,331.84, 2 ,324.34, 2 , 0 , 0 , 0 ,,
       1       1
   505.9   550.6
       1       1
   505.9   550.6
Pier Skew, UpSta & Num, DnSta & Num=  ,344.84, 2 ,337.34, 2 , 0 , 0 , 0 ,,
       1       1
   505.9   550.6
       1       1
   505.9   550.6
Pier Skew, UpSta & Num, DnSta & Num=  ,357.84, 2 ,350.34, 2 , 0 , 0 , 0 ,,
       1       1
   505.9   550.6
       1       1
   505.9   550.6
Pier Skew, UpSta & Num, DnSta & Num=  ,370.84, 2 ,363.34, 2 , 0 , 0 , 0 ,,
       1       1
   505.9   550.6
       1       1
   505.9   550.6
Pier Skew, UpSta & Num, DnSta & Num=  ,383.84, 2 ,376.34, 2 , 0 , 0 , 0 ,,
       1       1
   505.9   550.6
       1       1
   505.9   550.6
Pier Skew, UpSta & Num, DnSta & Num=  ,396.84, 2 ,389.34, 2 , 0 , 0 , 0 ,,
       1       1
   505.9   550.6
       1       1
   505.9   550.6
Pier Skew, UpSta & Num, DnSta & Num=  ,409.84, 2 ,402.34, 2 , 0 , 0 , 0 ,,
       1       1
   505.9   550.6
       1       1
   505.9   550.6
Pier Skew, UpSta & Num, DnSta & Num=  ,422.84, 2 ,415.34, 2 , 0 , 0 , 0 ,,
       1       1
   505.9   550.6
       1       1
   505.9   550.6
Pier Skew, UpSta & Num, DnSta & Num=  ,435.84, 2 ,428.34, 2 , 0 , 0 , 0 ,,
       1       1
   505.9   550.6
       1       1
   505.9   550.6
Pier Skew, UpSta & Num, DnSta & Num=  ,448.84, 2 ,441.34, 2 , 0 , 0 , 0 ,,
       1       1
   505.9   550.6
       1       1
   505.9   550.6
Pier Skew, UpSta & Num, DnSta & Num=  ,461.84, 2 ,454.34, 2 , 0 , 0 , 0 ,,
       1       1
   505.9   550.6
       1       1
   505.9   550.6
Pier Skew, UpSta & Num, DnSta & Num=  ,474.84, 2 ,467.34, 2 , 0 , 0 , 0 ,,
       1       1
   505.9   550.6
       1       1
   505.9   550.6
Pier Skew, UpSta & Num, DnSta & Num=  ,487.84, 2 ,480.34, 2 , 0 , 0 , 0 ,,
       1       1
   505.9   550.6
       1       1
   505.9   550.6
Pier Skew, UpSta & Num, DnSta & Num=  ,500.84, 2 ,493.34, 2 , 0 , 0 , 0 ,,
       1       1
   505.9   550.6
       1       1
   505.9   550.6
Pier Skew, UpSta & Num, DnSta & Num=  ,513.84, 2 ,506.34, 2 , 0 , 0 , 0 ,,
       1       1
   505.9   550.6
       1       1
   505.9   550.6
Pier Skew, UpSta & Num, DnSta & Num=  ,526.84, 2 ,519.34, 2 , 0 , 0 , 0 ,,
       1       1
   505.9   550.6
       1       1
   505.9   550.6
Pier Skew, UpSta & Num, DnSta & Num=  ,539.84, 2 ,532.34, 2 , 0 , 0 , 0 ,,
       1       1
   505.9   550.6
       1       1
   505.9   550.6
Pier Skew, UpSta & Num, DnSta & Num=  ,552.84, 2 ,545.34, 2 , 0 , 0 , 0 ,,
       1       1
   505.9   550.6
       1       1
   505.9   550.6
Pier Skew, UpSta & Num, DnSta & Num=  ,565.84, 2 ,558.34, 2 , 0 , 0 , 0 ,,
       1       1
   505.9   550.6
       1       1
   505.9   550.6
Pier Skew, UpSta & Num, DnSta & Num=  ,578.84, 2 ,571.34, 2 , 0 , 0 , 0 ,,
       1       1
   505.9   550.6
       1       1
   505.9   550.6
Pier Skew, UpSta & Num, DnSta & Num=  ,591.84, 2 ,584.34, 2 , 0 , 0 , 0 ,,
       1       1
   505.9   550.6
       1       1
   505.9   550.6
Pier Skew, UpSta & Num, DnSta & Num=  ,604.84, 2 ,597.34, 2 , 0 , 0 , 0 ,,
       1       1
   505.9   550.6
       1       1
   505.9   550.6
Pier Skew, UpSta & Num, DnSta & Num=  ,617.84, 2 ,610.34, 2 , 0 , 0 , 0 ,,
       1       1
   505.9   550.6
       1       1
   505.9   550.6
Pier Skew, UpSta & Num, DnSta & Num=  ,630.84, 2 ,623.34, 2 , 0 , 0 , 0 ,,
       1       1
   505.9   550.6
       1       1
   505.9   550.6
Pier Skew, UpSta & Num, DnSta & Num=  ,643.84, 2 ,636.34, 2 , 0 , 0 , 0 ,,
       1       1
   505.9   550.6
       1       1
   505.9   550.6
Pier Skew, UpSta & Num, DnSta & Num=  ,656.84, 2 ,649.34, 2 , 0 , 0 , 0 ,,
       1       1
   505.9   550.6
       1       1
   505.9   550.6
BR Coef=-1 , 0 , 0 ,, 0 ,,,0.8,-1,,0,
WSPro=,,,, 1 ,,,, 0 ,,,, 0 ,,,,-1 ,-1 ,-1 , 0 , 0 , 0 , 0 , 0
BR U #Sta/Elev= 166
    34.8  551.73   36.72  551.73   46.76  551.61   50.39  551.61   60.63   551.5
   62.62  551.47   67.03  551.47   77.84  551.38   77.84   548.5   80.34  545.72
   82.22  543.51   95.05  537.69  103.72  533.74  106.16   533.6  106.98  533.57
  108.48  533.51  111.93  533.38  115.38  533.23   116.8   533.2  117.38  533.26
  118.51  533.35  118.78  533.37  119.96  533.45  120.94  533.51  121.77  533.55
  122.33  533.58  123.06  533.61  123.68  533.64  124.34  533.67  125.56  533.71
  126.23  533.73  127.29  533.75  128.08  533.76  129.13  533.76  129.92  533.75
  131.06  533.73  131.84  533.72   133.1  533.67  133.84  533.65  134.52  533.63
  135.84  533.53  136.28  533.52  136.69  533.52  138.23  533.34  138.59  533.33
  138.91  533.32  140.74  533.07  140.97  533.04  143.24  532.72  143.38   532.7
   143.5  532.67  144.25  532.56  145.54  532.41  146.08  532.36   146.1  532.36
  146.12  532.36  146.15  532.36  146.19  532.35  146.24  532.35  146.31  532.34
  146.41  532.33  146.58  532.32  146.94  532.29  158.62  531.36  162.74  530.98
   168.5  530.42  173.27  528.08  177.24  526.19  184.17  522.75  185.59  522.25
  188.65  521.25  189.04  521.13  189.54  520.97  190.21  520.77  196.02  518.91
   197.3  518.52  198.95  518.03  201.15  517.36  202.94   516.8  205.01  516.19
  206.12  515.86  210.24  514.78  210.82  514.64  211.39  514.48  212.68  514.15
  218.59  512.61  220.52  512.08  223.19  511.34  227.24  510.13  228.44   509.8
  230.55   509.2  233.38  508.79     235  508.63  236.33  508.43  237.46  508.26
  252.84  506.01  252.85  506.02  252.88  506.03  254.26  505.99  255.67  505.99
  256.66  505.98  258.31  505.98     262  505.97  262.23  505.96  262.25  505.96
  262.27  505.97   262.3  505.97  265.16  505.93  265.67  505.92  266.38  505.95
  268.22  505.94  268.68  505.94  269.21  505.93  269.86  505.93  270.85  505.92
  271.54  505.92  273.02   505.9  273.38   505.9  273.39   505.9  275.18  506.57
  277.01  507.18  278.36  507.74  279.21  508.13  280.55   508.7  281.22     509
  284.13  510.16  284.42  510.27  284.99  510.53  285.24   510.6  285.63  510.76
  288.41  511.86  289.51  512.55  292.88  514.66  306.05  522.57  310.09  524.21
  316.31  526.74  319.74  528.54  324.85  531.34  343.05  531.25  378.95   531.4
  381.91  531.28  385.82  531.03  389.91  530.88  397.59  530.61  403.63   530.4
  408.01  530.24  461.09  530.02  533.13  530.02  548.36  529.73  549.56  529.72
  550.48  529.72  551.42  529.73  600.62  531.24  644.25  533.01  647.17  533.51
  649.68     534  680.53  543.89  683.84  545.24  683.84  548.91  687.38  548.91
  691.23  548.67  700.43   548.8  704.72   548.8  712.18   548.9  721.23   548.9
  725.23  548.96
BR U #Mann= 3
    34.8     .06   168.5    .035  324.85     .06
BR U Banks=168.5,324.85
BR D #Sta/Elev= 168
    27.3  551.73   29.22  551.73   39.26  551.61   42.89  551.61   53.13   551.5
   55.12  551.47   59.53  551.47   70.34  551.38   70.34   548.5   72.84  545.72
   74.72  543.51   87.55  537.69   96.22  533.74   98.66   533.6   99.48  533.57
  100.98  533.51  104.43  533.38  107.88  533.23   109.3   533.2  109.88  533.26
  111.01  533.35  111.28  533.37  112.46  533.45  113.44  533.51  114.27  533.55
  114.83  533.58  115.56  533.61  116.18  533.64  116.84  533.67  118.06  533.71
  118.73  533.73  119.79  533.75  120.58  533.76  121.63  533.76  122.42  533.75
  123.56  533.73  124.34  533.72   125.6  533.67  126.34  533.65  127.02  533.63
  128.34  533.53  128.78  533.52  129.19  533.52  130.73  533.34  131.09  533.33
  131.41  533.32  133.24  533.07  133.47  533.04  135.74  532.72  135.88   532.7
     136  532.67  136.75  532.56  138.04  532.41  138.58  532.36   138.6  532.36
  138.62  532.36  138.65  532.36  138.69  532.35  138.74  532.35  138.81  532.34
  138.91  532.33  139.08  532.32  139.44  532.29  151.12  531.36  155.24  530.98
     161  530.42  165.77  528.08  169.74  526.19  176.67  522.75  178.09  522.25
  181.15  521.25  181.54  521.13  182.04  520.97  182.71  520.77  188.52  518.91
   189.8  518.52  191.45  518.03  193.65  517.36  195.44   516.8  197.51  516.19
  198.62  515.86  202.74  514.78  203.32  514.64  203.89  514.48  205.18  514.15
  211.09  512.61  213.02  512.08  215.69  511.34  219.74  510.13  220.94   509.8
  223.05   509.2  225.88  508.79   227.5  508.63  228.83  508.43  229.96  508.26
  245.34  506.01  245.35  506.02  245.38  506.03  246.76  505.99  248.17  505.99
  249.16  505.98  250.81  505.98   254.5  505.97  254.73  505.96  254.75  505.96
  254.77  505.97   254.8  505.97  257.66  505.93  258.17  505.92  258.88  505.95
  260.72  505.94  261.18  505.94  261.71  505.93  262.36  505.93  263.35  505.92
  264.04  505.92  265.52   505.9  265.88   505.9  265.89   505.9  267.68  506.57
  269.51  507.18  270.86  507.74  271.71  508.13  273.05   508.7  273.72     509
  276.63  510.16  276.92  510.27  277.49  510.53  277.74   510.6  278.13  510.76
  280.91  511.86  282.01  512.55  285.38  514.66  298.55  522.57  302.59  524.21
  308.81  526.74  312.24  528.54  317.35  531.34  335.55  531.25  371.45   531.4
  374.41  531.28  378.32  531.03  382.41  530.88  390.09  530.61  396.13   530.4
  400.51  530.24  453.59  530.02  525.63  530.02  540.86  529.73  542.06  529.72
  542.98  529.72  543.92  529.73  593.12  531.24  636.75  533.01  639.67  533.51
  642.18     534  673.03  543.89  676.34     545  676.34  548.91  678.82  548.91
  678.97  548.91  679.88  548.91  683.73  548.67  692.93   548.8  697.22   548.8
  704.68   548.9  713.73   548.9  717.73  548.96
BR D #Mann= 3
    27.3     .06     161    .035  317.35     .06
BR D Banks=161,317.35
BC Design=,, 0 ,, 0 ,,27,318.84,311.34,13,1
BC Use User HTab Curves=0
BC User HTab FreeFlow(D)= 0

Type RM Length L Ch R = 1 ,257008  ,211.81,177.37,87.61
BEGIN DESCRIPTION:
This cross section corresponds to cross section 256886.7 of the non-georeferenced CDC model which was the source of this model.
Downstream of the Fort Worth and Western Railroad.
Effective flow in LOB set at North Main Levee.
Effective flow in ROB set at Clear Fork Levee Loop.
END DESCRIPTION:
XS GIS Cut Line= 2
 2323612.0703768 6963709.3053239 2323342.6556967 6963045.4535896
#Sta/Elev= 30
       0  550.49   12.85  551.35   42.02  545.64   71.86  542.54    96.8  534.51
     137  533.16  162.52  530.43  171.93  526.04   193.6     520  207.29  512.24
  212.32  512.16  213.21  510.73  220.11  509.53  251.14  506.12  259.08  506.28
  261.14     508  264.28  508.65   271.2   508.2  271.87     510  273.27  511.15
  294.09     518  298.62     520  301.19  522.58  311.19  526.06  320.21  530.73
   549.7     530  633.07     532  648.96  534.33  697.77  550.88  716.44  551.69
#Mann= 3 ,-1,0
       0     .06       0  162.52    .035       0  320.21     .06       0
#XS Ineff= 2 , 0
       0   12.42     560               0
Permanent Ineff=
       T       F
Bank Sta=162.52,320.21
XS Rating Curve= 0 ,0
Exp/Cntr=0.5,0.3

Type RM Length L Ch R = 1 ,256831  ,167.4,156.29,129.16
BEGIN DESCRIPTION:
This cross section corresponds to cross section 256709.4 of the non-georeferenced CDC model which was the source of this model.
Upstream of Sump 16W outfall.
Effective flow in LOB set at North Main Levee.
Effective flow in ROB set at Clear Fork Levee Loop.
END DESCRIPTION:
XS GIS Cut Line= 2
 2323792.1218389 6963532.1382985 2323363.7509755 6963028.1936392
#Sta/Elev= 30
       0  554.02   11.02   554.4   89.96  528.59  106.77  528.29  117.61  526.49
  132.58   528.1  167.87     520  187.25  516.47  201.22     512  204.06  511.67
  206.82  509.91  215.05  507.98  227.68   506.9  228.43  507.22  247.13  505.13
   258.7  510.66  262.43  511.72  265.91  513.51  273.17     518  277.36  521.44
  291.49  524.87  300.05  528.42  336.59  528.75  392.24  528.32  430.04  529.45
  499.69  529.05  556.85  530.01  595.89  534.59  646.24  554.68  661.41  554.39
#Mann= 3 ,-1,0
       0     .06       0  132.58    .035       0  300.05     .06       0
#XS Ineff= 2 , 0
       0   11.02     560  647.09       0     560
Permanent Ineff=
       T       T
Bank Sta=132.58,300.05
XS Rating Curve= 0 ,0
Exp/Cntr=0.3,0.1

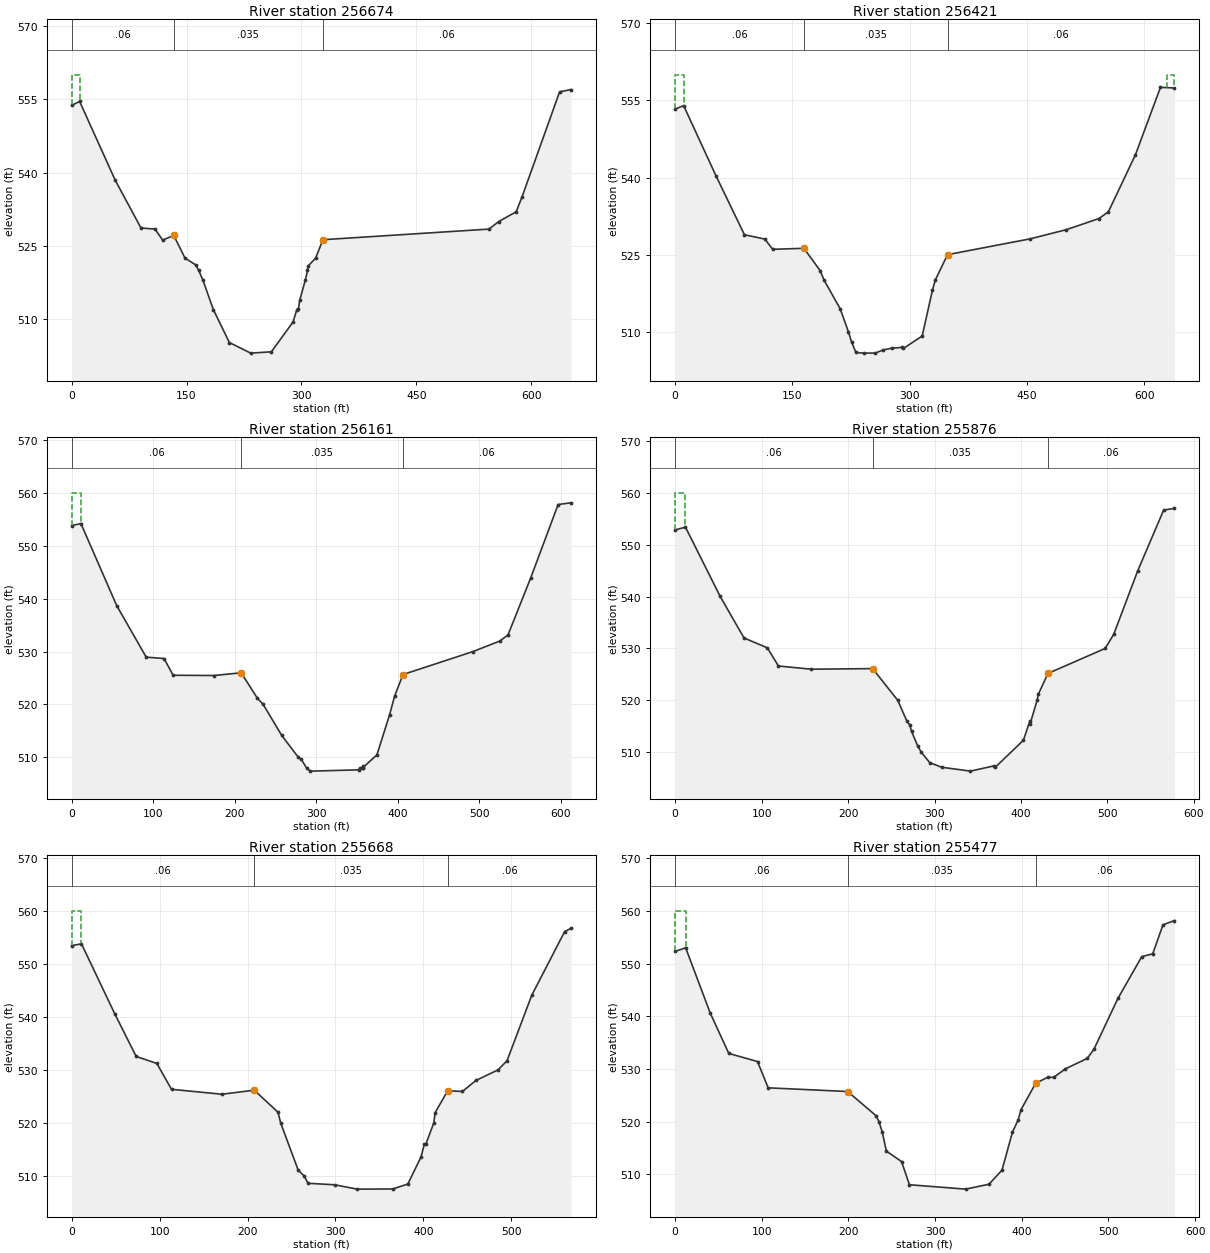
Type RM Length L Ch R = 1 ,256674  ,262.62,253.23,234.44
BEGIN DESCRIPTION:
This cross section corresponds to cross section 256553.1 of the non-georeferenced CDC model which was the source of this model.
Downstream of Sump 16W outfall.
Effective flow in LOB set at North Main Levee.
Effective flow in ROB set at Clear Fork Levee Loop.
END DESCRIPTION:
XS GIS Cut Line= 2
 2323919.7488916 6963406.9297648 2323447.7538084 6962957.4015262
#Sta/Elev= 30
       0  553.75    10.4  554.57   56.84  538.47   90.52  528.68  108.84  528.46
  118.74  526.22  133.36  527.15  147.95  522.54  161.89  521.15  165.94     520
  171.43     518  184.98     512  205.86  505.27  233.73   503.1  260.73  503.37
  289.01  509.47  293.96     512  296.03   512.2  297.88     514  304.97     518
  307.85     520  308.51  520.88  318.47  522.52  328.02  526.29  544.87  528.46
  557.47     530  580.26     532  587.72  534.96  636.94  556.52  651.81  556.99
#Mann= 3 ,-1,0
       0     .06       0  133.36    .035       0  328.02     .06       0
#XS Ineff= 2 , 0
       0    10.4     560               0
Permanent Ineff=
       T       F
Bank Sta=133.36,328.02
XS Rating Curve= 0 ,0
Exp/Cntr=0.3,0.1

Type RM Length L Ch R = 1 ,256421  ,260.26,260.55,260.14
BEGIN DESCRIPTION:
This cross section corresponds to cross section 256299.8 of the non-georeferenced CDC model which was the source of this model.
Effective flow in LOB set at North Main Levee.
Effective flow in ROB set at Clear Fork Levee Loop.
END DESCRIPTION:
XS GIS Cut Line= 2
 2324115.2600267 6963216.6836017 2323618.6794314 6962814.9068554
#Sta/Elev= 30
       0  553.32   10.87     554   52.25  540.34   88.67  528.85  114.88     528
  124.79  526.01  164.76  526.21  185.46  521.87  190.62     520  211.22   514.4
  221.55     510  225.63     508  231.24  505.92  241.27  505.79  255.98   505.8
  265.84   506.4  277.17  506.75  289.89   506.9  292.09  506.71  316.04  509.12
  329.07     518  332.71     520  348.46  524.97  454.16  528.05  500.46  529.84
  542.02     532  554.16   533.3  588.88  544.45  620.83  557.56  638.76  557.44
#Mann= 3 ,-1,0
       0     .06       0  164.76    .035       0  348.46     .06       0
#XS Ineff= 2 , 0
       0   10.77     560  629.06       0     560
Permanent Ineff=
       T       T
Bank Sta=164.76,348.46
XS Rating Curve= 0 ,0
Exp/Cntr=0.3,0.1

Type RM Length L Ch R = 1 ,256161  ,272.91,284.38,294.82
BEGIN DESCRIPTION:
This cross section corresponds to cross section 256039.3 of the non-georeferenced CDC model which was the source of this model.
Effective flow in LOB set at North Main Levee.
Effective flow in ROB set at Clear Fork Levee Loop.
END DESCRIPTION:
XS GIS Cut Line= 3
 2324304.0469889 6963034.5629939 2323963.5113053 6962760.9494814
 2323826.1943603 6962651.3804281
#Sta/Elev= 30
       0  553.81    11.4  554.19   55.29  538.68    91.5  528.94  113.37  528.68
  124.49  525.52  174.13  525.47  208.01  525.98  227.82  521.18  235.02     520
  257.72  514.14  278.14     510  281.73   509.6  288.21     508  292.49   507.4
  352.27  507.64  353.62     508  356.78  507.94  357.16   508.3  357.24  508.07
  374.44  510.47   389.9     518  396.28  521.64  406.47  525.66  492.36     530
  525.36     532  535.22  533.14  563.19  543.96  596.72  557.79  612.51  558.12
#Mann= 3 ,-1,0
       0     .06       0  208.01    .035       0  406.47     .06       0
#XS Ineff= 2 , 0
       0    11.4     560               0
Permanent Ineff=
       T       F
Bank Sta=208.01,406.47
XS Rating Curve= 0 ,0
Exp/Cntr=0.3,0.1

Type RM Length L Ch R = 1 ,255876  ,199.03,208.45,213.72
BEGIN DESCRIPTION:
This cross section corresponds to cross section 255754.9 of the non-georeferenced CDC model which was the source of this model.
Effective flow in LOB set at North Main Levee.
Effective flow in ROB set at Clear Fork Levee Loop.
END DESCRIPTION:
XS GIS Cut Line= 4
 2324499.2162696 6962856.2082287 2324330.7142216 6962701.5303457
 2324161.6376197 6962548.8159537 2324074.5122059 6962464.8807917
#Sta/Elev= 30
       0  552.85   11.99  553.38   52.13  540.02    79.7  532.02   106.6  530.12
   119.5  526.62  157.23     526  228.46  526.11  257.52     520  268.02     516
  271.31   515.3  273.46     514  280.41  511.27  284.67     510  294.48  507.99
  308.25   507.1   341.6  506.35   368.4  507.35  370.48  507.13  402.82   512.3
  410.25     516  410.62   515.5  418.63  519.99  420.27  521.24  431.21  525.18
  497.34     530  507.29  532.72  534.88   544.9  565.03  556.68  577.55     557
#Mann= 3 ,-1,0
       0     .06       0  228.46    .035       0  431.21     .06       0
#XS Ineff= 2 , 0
       0   11.99     560               0
Permanent Ineff=
       T       F
Bank Sta=228.46,431.21
XS Rating Curve= 0 ,0
Exp/Cntr=0.3,0.1

Type RM Length L Ch R = 1 ,255668  ,189.83,190.44,186.47
BEGIN DESCRIPTION:
This cross section corresponds to cross section 255546.4 of the non-georeferenced CDC model which was the source of this model.
Effective flow in LOB set at North Main Levee.
Effective flow in ROB set at Clear Fork Levee Loop.
END DESCRIPTION:
XS GIS Cut Line= 2
 2324643.4132118 6962730.6052079 2324241.7597509  6962329.342345
#Sta/Elev= 30
       0  553.44   11.19  553.77   48.96   540.6   73.39  532.53    96.9  531.21
  113.55  526.33  171.01   525.4  207.67  526.17   234.7  521.99  237.64     520
  257.54   511.1  264.21     510  268.85   508.6   299.1  508.32  324.66   507.5
  365.25  507.53  382.25  508.47  397.24  513.57  401.06     516  402.77     516
  411.77     520  413.32  521.94   427.6  526.07   444.3  525.92  459.65     528
  484.88     530     495  531.72  523.14  544.07  560.51  556.08  567.75   556.7
#Mann= 3 ,-1,0
       0     .06       0  207.67    .035       0   427.6     .06       0
#XS Ineff= 2 , 0
       0   11.19     560               0
Permanent Ineff=
       T       F
Bank Sta=207.67,427.6
XS Rating Curve= 0 ,0
Exp/Cntr=0.3,0.1

Type RM Length L Ch R = 1 ,255477  ,236.53,237.86,233.46
BEGIN DESCRIPTION:
This cross section corresponds to cross section 255356 of the non-georeferenced CDC model which was the source of this model.
Effective flow in LOB set at North Main Levee.
Effective flow in ROB set at Clear Fork Levee Loop.
END DESCRIPTION:
XS GIS Cut Line= 2
 2324786.3413908 6962606.1073475  2324376.108643 6962201.4705364
#Sta/Elev= 30
       0   552.3   12.14  552.99   40.51   540.6   61.92  532.93   95.09  531.39
  107.35   526.4  199.13   525.7  231.99  521.09  235.18     520  239.03     518
  243.75  514.39  261.24  512.41  270.41     508  335.32  507.17  362.14   508.1
  377.15  510.77  389.28     518  395.79  520.29  399.18  522.27  416.04  527.27
  429.81  528.39  436.85  528.38  450.31     530   475.7     532  483.42  533.77
  510.89  543.36  538.49  551.31   551.1  551.84  562.93  557.34  576.21  558.16
#Mann= 3 ,-1,0
       0     .06       0  199.13    .035       0  416.04     .06       0
#XS Ineff= 2 , 0
       0   12.14     560               0
Permanent Ineff=
       T       F
Bank Sta=199.13,416.04
XS Rating Curve= 0 ,0
Exp/Cntr=0.3,0.1

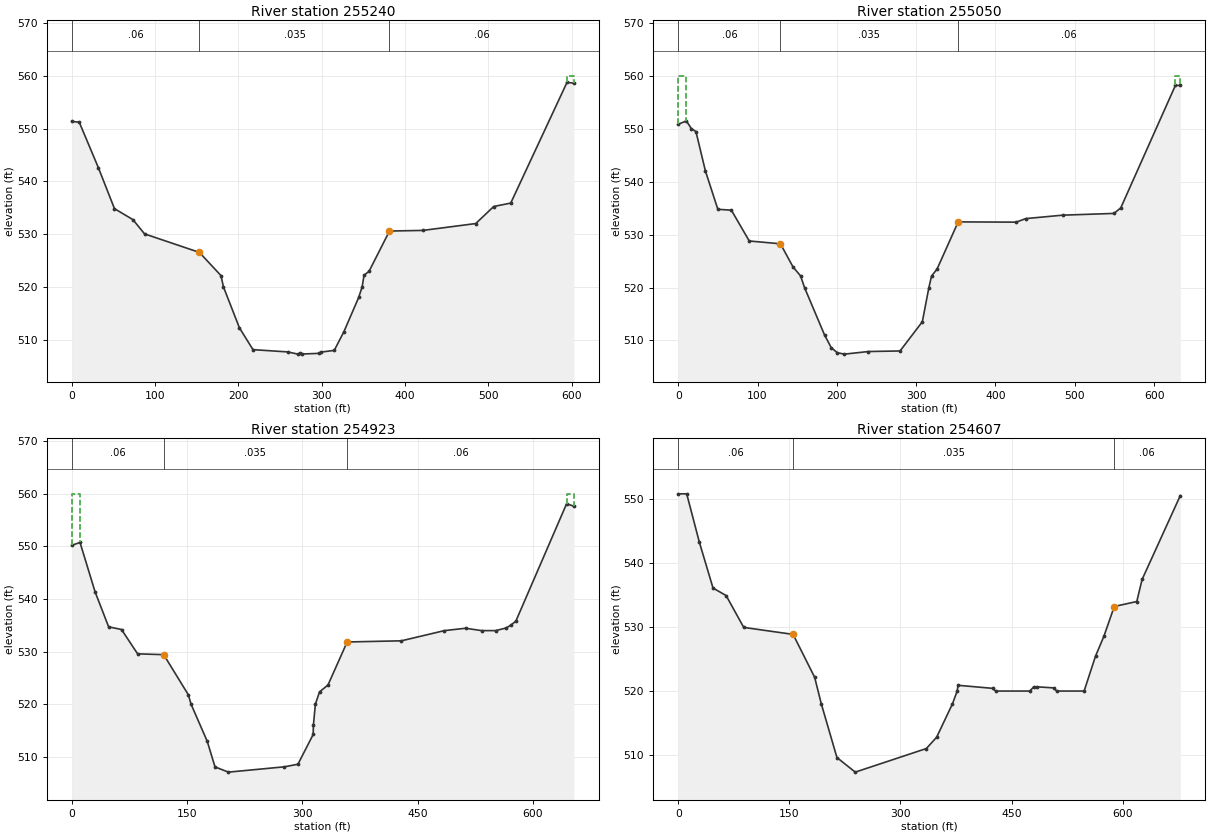
Type RM Length L Ch R = 1 ,255240  ,191.52,189.47,183.55
BEGIN DESCRIPTION:
This cross section corresponds to cross section 255118.2 of the non-georeferenced CDC model which was the source of this model.
Effective flow in LOB set at North Main Levee.
Effective flow in ROB set at Clear Fork Levee Loop.
END DESCRIPTION:
XS GIS Cut Line= 2
 2324957.5452161 6962445.2386208 2324526.8143002 6962023.8054434
#Sta/Elev= 30
       0  551.35    8.96  551.22   31.93  542.59   51.23  534.83   73.42  532.74
   87.37  530.04   153.2  526.53  179.06  522.14  182.05     520  201.26  512.22
  217.51   508.1  259.16  507.67  271.48  507.25  273.82   507.4  276.58  507.27
  297.24   507.4  298.94  507.63  315.04  507.96  326.57  511.48  344.38     518
  348.53     520   350.8  522.22  356.75  522.93  381.32  530.58  421.47   530.7
  484.86     532  506.42  535.23  526.87  535.88  594.44  558.77  602.61   558.6
#Mann= 3 ,-1,0
       0     .06       0   153.2    .035       0  381.32     .06       0
#XS Ineff= 2 , 0
       0                  594.44       0     560
Permanent Ineff=
       F       T
Bank Sta=153.2,381.32
XS Rating Curve= 0 ,0
Exp/Cntr=0.3,0.1

Type RM Length L Ch R = 1 ,255050  ,129.97,127.29,121.47
BEGIN DESCRIPTION:
This cross section corresponds to cross section 254928.7 of the non-georeferenced CDC model which was the source of this model.
Effective flow in LOB set at North Main Levee.
Effective flow in ROB set at Clear Fork Levee Loop.
END DESCRIPTION:
XS GIS Cut Line= 2
 2325100.4443563  6962316.709031 2324640.0425045 6961882.2319773
#Sta/Elev= 30
       0  550.85   10.27  551.48   16.67     550   22.31  549.47    34.3     542
   49.94  534.78   67.02  534.61   89.54  528.79  128.86  528.26  144.79  523.87
  154.24   522.2   159.2     520  184.44  511.04  192.92  508.63  200.63  507.67
  209.63  507.41  239.66   507.9  279.69  508.01  307.78  513.53  316.05     520
  319.38  522.17  326.26  523.46  352.98   532.4  426.12  532.35  438.13  533.02
  484.76  533.67  549.37     534  557.94  535.04  626.88   558.2  633.04  558.18
#Mann= 3 ,-1,0
       0     .06       0  128.86    .035       0  352.98     .06       0
#XS Ineff= 2 , 0
       0   10.27     560  626.88       0     560
Permanent Ineff=
       T       T
Bank Sta=128.86,352.98
XS Rating Curve= 0 ,0
Exp/Cntr=0.3,0.1

Type RM Length L Ch R = 1 ,254923  ,319.73,315.49,309.65
BEGIN DESCRIPTION:
This cross section corresponds to cross section 254801.4 of the non-georeferenced CDC model which was the source of this model.
Effective flow in LOB set at North Main Levee.
Effective flow in ROB set at Clear Fork Levee Loop.
END DESCRIPTION:
XS GIS Cut Line= 2
 2325198.5101466 6962228.2295525 2324713.8586738  6961789.936616
#Sta/Elev= 30
       0  550.21   10.72  550.76   30.36  541.36   47.97  534.72   64.74  534.21
   85.71  529.58  119.64  529.43  151.73   521.8  155.29     520  176.36  512.94
  186.44  508.09  203.88   507.1  276.76  508.11  294.36   508.6  314.19  514.26
  314.47     516  317.04     520  322.42  522.35  333.46  523.66   358.4  531.84
  428.96  532.06     485     534  512.56  534.45  533.31     534  551.65     534
  565.01  534.49  571.31  535.02  577.97   535.8     644  558.11  653.44  557.65
#Mann= 3 ,-1,0
       0     .06       0  119.64    .035       0   358.4     .06       0
#XS Ineff= 2 , 0
       0   10.72     560     644       0     560
Permanent Ineff=
       T       T
Bank Sta=119.64,358.4
XS Rating Curve= 0 ,0
Exp/Cntr=0.3,0.1

Type RM Length L Ch R = 1 ,254607  ,0,0,0
BEGIN DESCRIPTION:
This cross section corresponds to cross section 254485.9 of the non-georeferenced CDC model which was the source of this model.
Upstream of West Fork/Clear Fork confluence.
Effective flow in LOB set at North Main Levee.
Effective flow in ROB set at Clear Fork Levee Loop.
END DESCRIPTION:
XS GIS Cut Line= 2
 2325439.6496989 6962010.6621351  2324924.825852 6961569.7857804
#Sta/Elev= 30
       0  550.84   11.43  550.84   28.47  543.29   46.96  536.11   64.67  534.93
   88.42  529.95  155.07  528.86  184.13  522.16  193.13     518  214.26   509.6
  238.96  507.32  334.97  511.01  348.85  512.78  370.21     518  376.56     520
  377.73   520.9  424.54  520.42  428.56     520  474.64     520  479.93  520.65
  484.22  520.66  507.14  520.49  510.75     520  547.95     520  563.31  525.45
  574.64  528.56  588.65  533.22  619.04     534  626.21  537.45   677.8  550.57
#Mann= 3 ,-1,0
       0     .06       0  155.07    .035       0  588.65     .06       0
Bank Sta=155.07,588.65
XS Rating Curve= 0 ,0
Exp/Cntr=0.3,0.1

River Reach=West Fork       ,wf3