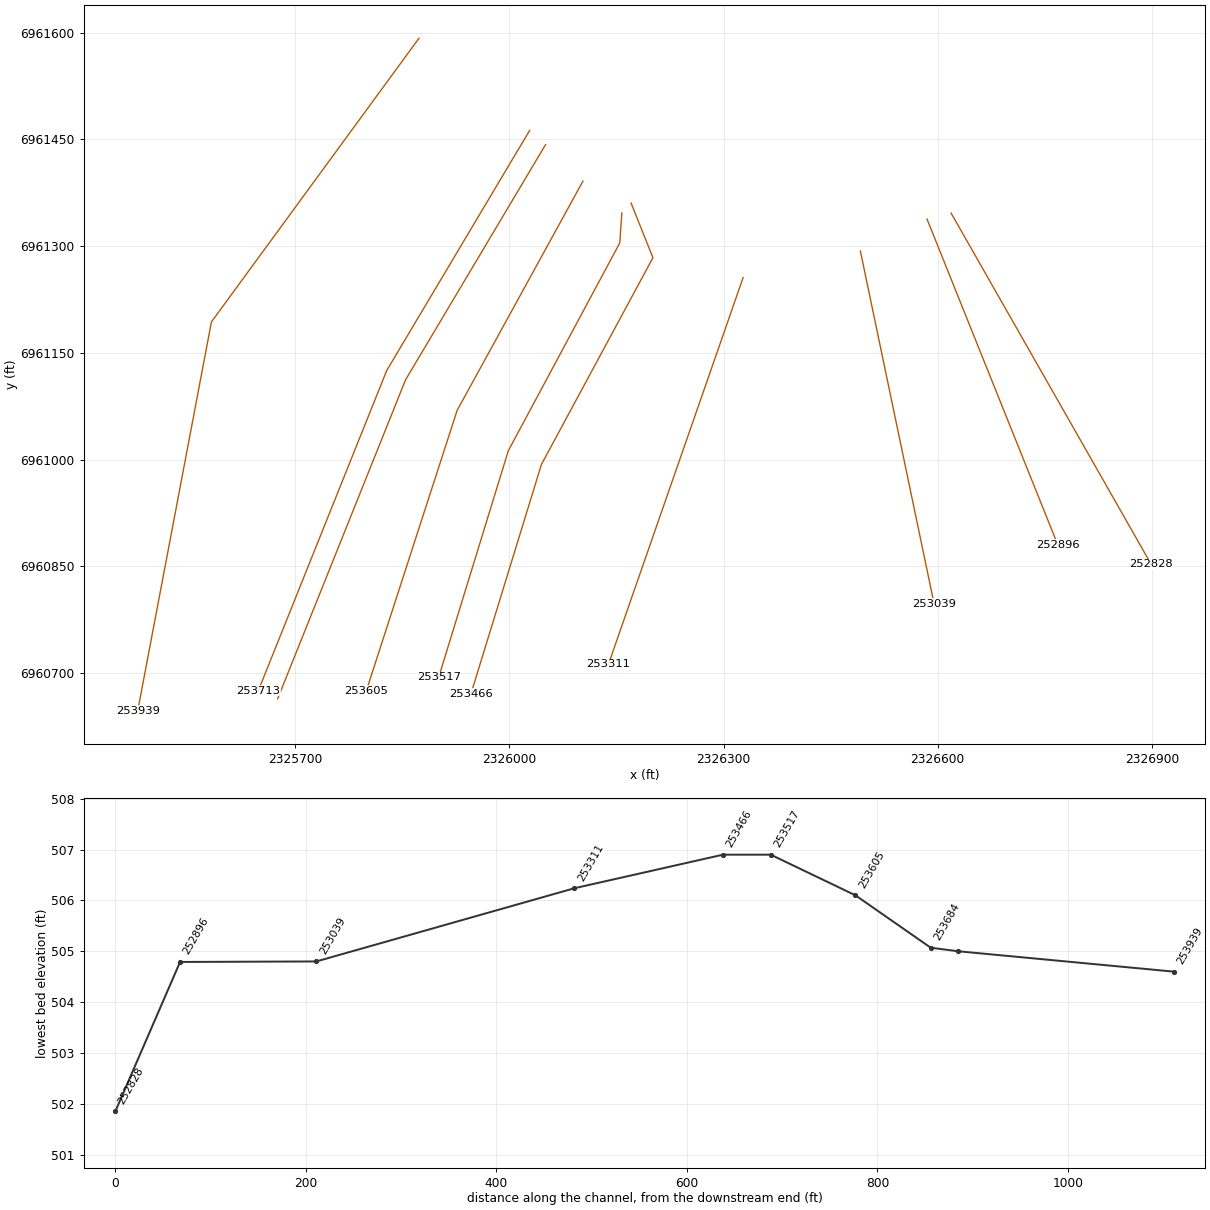
HEC-RAS study CDC_Consolidated_Model.prj: Upper Trinity CDC Consolidated Model

--- CDC_Consolidated_Model.g03 (geometry) --- (continued)

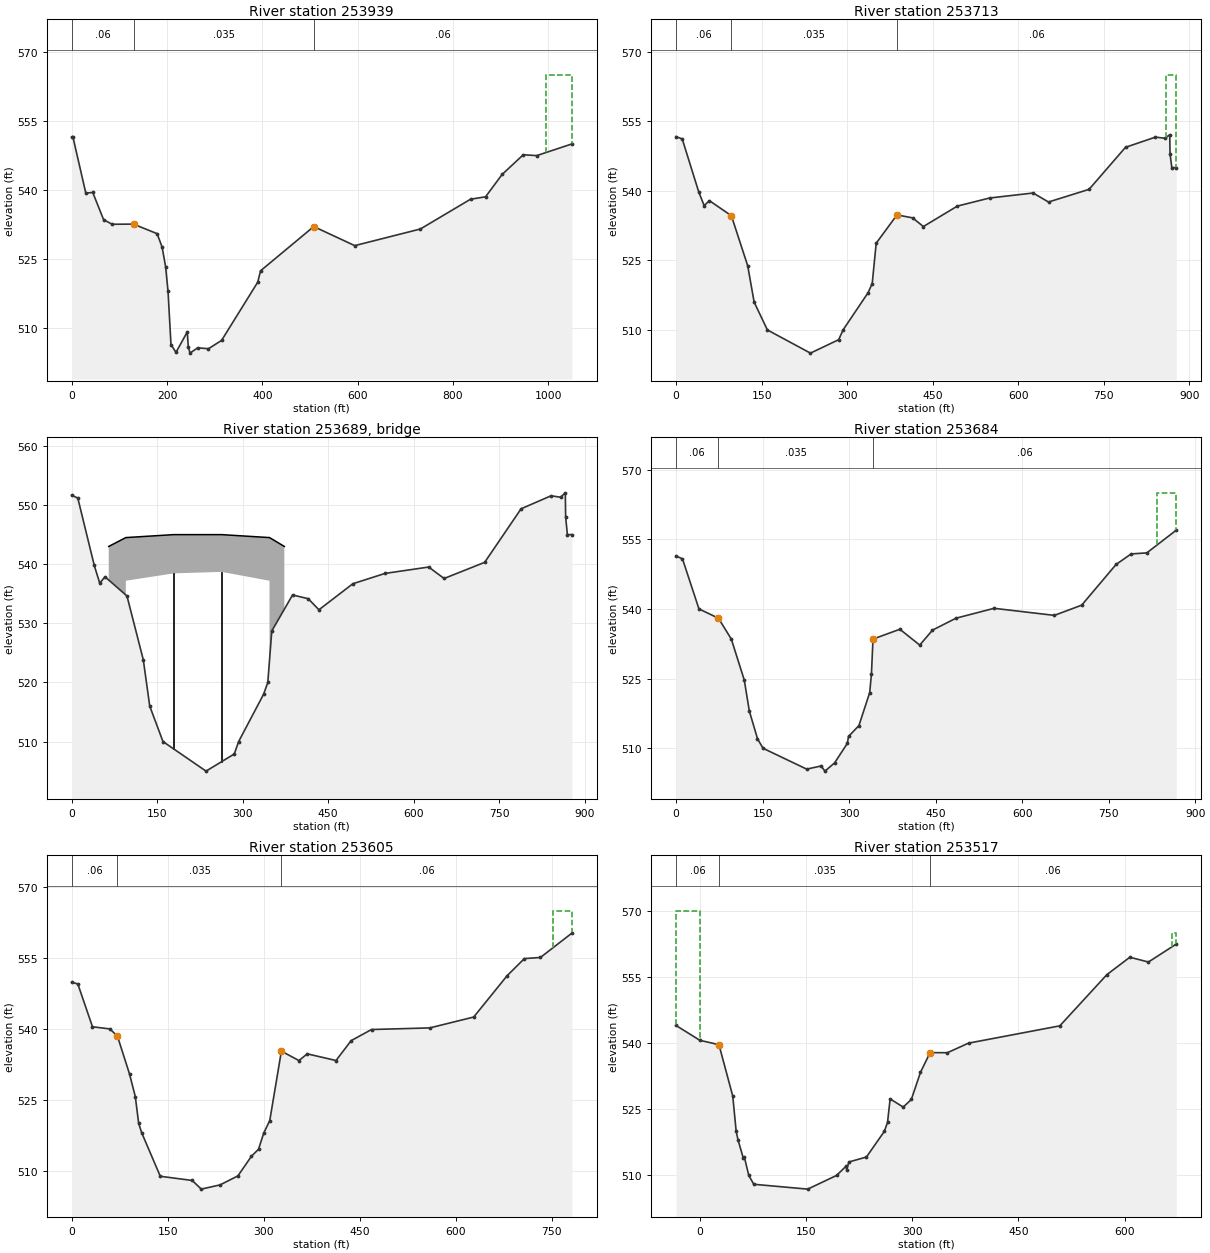
Type RM Length L Ch R = 1 ,253939  ,226,226,268
BEGIN DESCRIPTION:
This cross section corresponds to cross section 253818.1 of the non-georeferenced CDC model which was the source of this model.
Downstream of the West Fork/Clear Fork confluence.
---------------------------------------------------------------------
RADIO SHACK RIVERFRONT CAMPUS
CDC FW080602-01
LOCATED IN ROB.
---------------------------------------------------------------------
END DESCRIPTION:
XS GIS Cut Line= 3
  2325873.498788 6961592.2998132 2325582.7374618 6961193.5034353
 2325479.5651167 6960647.2140793
#Sta/Elev= 30
       0  551.48    2.48  551.57   29.63  539.34   44.22  539.47   66.97  533.56
   84.99  532.57  129.71   532.6   179.2  530.53  189.75  527.62  197.04  523.39
  202.17     518  208.35  506.47  218.81  504.76  242.52   509.2  244.73     506
  248.31   504.6  264.26  505.75     287  505.56  314.44  507.35  390.38     520
  396.29  522.47   507.9  532.07  593.87  527.93  731.62  531.54  836.78     538
  868.43  538.53  903.04  543.37  947.47  547.65  975.72  547.47 1049.49     550
#Mann= 3 ,-1,0
       0     .06       0  129.71    .035       0   507.9     .06       0
#XS Ineff= 1 ,-1
  995.05 1049.49     565
Permanent Ineff=
       F
Bank Sta=129.71,507.9
XS Rating Curve= 0 ,0
Exp/Cntr=0.5,0.3

Type RM Length L Ch R = 1 ,253713  ,29,29,30
BEGIN DESCRIPTION:
This cross section corresponds to cross section 253592 of the non-georeferenced CDC model which was the source of this model.
Upstream of Pedestrian Bridge.
Effective flow limit in LOB set at North Main Levee.
---------------------------------------------------------------------
RADIO SHACK RIVERFRONT CAMPUS CDC FW080602-01 IN ROB.
---------------------------------------------------------------------
END DESCRIPTION:
XS GIS Cut Line= 3
 2326028.4870235 6961462.6894347 2325828.2693953 6961125.2051609
 2325648.3021977 6960674.8796511
#Sta/Elev= 30
       0  551.66   10.73  551.19   39.64  539.78   49.19   536.8   58.47  537.87
   96.99  534.62  125.64  523.82   136.9     516  160.13     510  235.66     505
   285.2   507.9  292.84     510  336.62     518     344     520  350.99   528.7
  387.44   534.8  414.88  534.16  433.71  532.29  493.29   536.7  549.73  538.44
  626.24  539.52  653.22  537.58  724.35  540.31  788.26  549.37  840.81  551.57
   857.4  551.33  865.82  552.07  866.41     548  869.45     545  877.36     545
#Mann= 3 ,-1,0
       0     .06       0   96.99    .035       0  387.44     .06       0
#XS Ineff= 1 ,-1
  858.69  877.36     565
Permanent Ineff=
       F
Bank Sta=96.99,387.44
XS Rating Curve= 0 ,0
Exp/Cntr=0.5,0.3

Type RM Length L Ch R = 3 ,253689  ,,,
BEGIN DESCRIPTION:
Pedestrian Bridge
Data from bridge plans, TRWD May 2007 survey.
Bridge width 10 feet.
Note:  Internal bridge cross-sections modified to represent geometry under bridge.
END DESCRIPTION:
Node Name=ped. bridge
Bridge Culvert--1,0,-1,-1, 0
Deck Dist Width WeirC Skew NumUp NumDn MinLoCord MaxHiCord MaxSubmerge Is_Ogee
8,10,2.6,0, 8, 8, , , 0.95, 0, 0,0,,
      65      95      95     179     263     347     347     373
     543   544.5   544.5     545     545   544.5   544.5     543
     450     450   537.2  538.45   538.7   537.2     450     450
      65      95      95     179     263     347     347     373
     543   544.5   544.5     545     545   544.5   544.5     543
     450     450   537.2  538.45   538.7   537.2     450     450
Pier Skew, UpSta & Num, DnSta & Num=  ,179, 2 ,179, 2 , 0 , 0 , 0 ,,
     2.5     2.5
     450     542
     2.5     2.5
     450     542
Pier Skew, UpSta & Num, DnSta & Num=  ,263, 2 ,263, 2 , 0 , 0 , 0 ,,
     2.5     2.5
     450     542
     2.5     2.5
     450     542
BR Coef=-1 , 0 , 0 ,, 0 ,,,0.8,-1,,0,
WSPro=,,,, 1 ,,,, 0 ,,,, 0 ,,,,-1 ,-1 ,-1 , 0 , 0 , 0 , 0 , 0
BR U #Sta/Elev= 286
       0  551.54    5.73  551.28   10.67  551.02   35.68  541.26   39.05  539.97
   41.44  539.77    50.7  537.61   56.88  538.29   77.78  535.92   93.62  534.14
   96.59  533.89  110.28  528.47  110.58  528.35  110.61  528.34  110.63  528.34
  122.07  524.19  128.54  520.23  138.81  514.67  138.94  514.64  139.41  514.48
  139.79  514.29   139.9  514.28  139.95  514.28  140.14  514.17  140.18  514.16
  140.64  513.89  140.95  513.73  150.41  511.89   151.1  511.74  151.85  511.59
  152.66  511.42  153.54  511.23   154.5  511.03  155.56  510.81  156.72  510.57
  158.01   510.3  159.45     510  161.05  509.67  162.52  509.36  162.67  509.35
  162.68  509.35  163.49  509.33   163.5  509.32  163.52  509.32  164.29  509.29
  164.33  509.29  165.06  509.27  165.14  509.26  165.17  509.26  165.26  509.25
     166  509.21  166.18   509.2  166.91  509.17  167.59  509.14  167.63  509.14
  167.75  509.12   168.4  509.09  168.61  509.07  182.99   508.2  183.63  508.15
  183.92  508.15  184.34   508.1  184.65   508.1  184.77   508.1  184.89  508.05
  184.99  508.05   185.1  508.05  185.61     508  185.88  507.95  186.45  507.95
  186.56  507.95  186.73  507.95  186.96   507.9  187.16  507.85  187.28  507.85
  187.42  507.85  187.65  507.85  188.03  507.85  188.61   507.8  188.72   507.8
  188.84   507.8  189.05  507.75  189.26  507.75   189.4  507.75  189.58  507.75
  189.62  507.75  189.75   507.7  190.08   507.7  190.29   507.7  190.39   507.7
  190.59   507.7  190.88   507.7     191   507.7   191.1   507.7  191.85   507.7
   192.4   507.7   192.5   507.7  192.62  507.65  193.19   507.6  193.32   507.6
  194.17  507.55  194.29  507.55   194.4  507.55  194.62   507.5  194.73  507.45
  195.08  507.45  195.73  507.45  195.96  507.45  196.08  507.45  196.19  507.45
  196.42   507.4  196.52   507.4  196.97   507.4  197.19   507.4  197.29  507.35
  197.41  507.35  197.53  507.35  197.63  507.35   198.1   507.3  198.21   507.3
  198.55   507.3  198.87   507.3  199.09   507.3  199.32  507.25  199.75  507.25
  199.87  507.25  200.35  507.25  200.67   507.2   201.1   507.2  201.22   507.2
  201.34  507.15  202.28   507.1  202.76   507.1  202.89   507.1  203.45  507.05
  203.81  507.05  203.93  507.05   204.4     507  204.84  506.95  205.16   506.9
  205.38  506.85  205.73  506.85  205.85  506.85  205.96   506.9  206.08   506.9
  206.51  506.95  206.63  506.95  206.99  506.95  207.09   506.9  207.38  506.85
  207.72   506.8  208.09   506.8   208.2  506.75  208.31  506.75  208.53  506.74
  208.99  506.69  209.11   506.6  228.83  505.43  228.85  505.43  228.91  505.43
  228.96  505.43  228.98  505.43  228.99  505.43  230.04  505.41  230.05  505.41
  230.07  505.41  230.08  505.41  230.09  505.41  230.68  505.34   230.7  505.32
  230.73  505.34  230.87  505.36  230.91   505.3  230.92   505.3  234.02   505.3
  235.36   505.3   235.4  505.29  235.46  505.28  235.56  505.26  242.37  505.55
   245.1  505.66  246.48  505.71  247.47  505.74  248.41  505.78  249.09   505.8
  254.01     506  254.53  506.01  256.63   506.1  258.41  506.22  258.67  506.23
  258.84  506.25   263.6  506.55   264.1  506.58  264.66  506.62  265.28  506.66
     281  507.76  281.03  507.71  281.05  507.75  281.07  507.74   281.1  507.74
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BR U #Mann= 3
       0     .06   77.78    .035  353.82     .06
BR U Banks=77.78,353.82
BR D #Sta/Elev= 286
       0  551.54    5.73  551.28   10.67  551.02   35.68  541.26   39.05  539.97
   41.44  539.77    50.7  537.61   56.88  538.29   77.78  535.92   93.62  534.14
   96.59  533.89  110.28  528.47  110.58  528.35  110.61  528.34  110.63  528.34
  122.07  524.19  128.54  520.23  138.81  514.67  138.94  514.64  139.41  514.48
  139.79  514.29   139.9  514.28  139.95  514.28  140.14  514.17  140.18  514.16
  140.64  513.89  140.95  513.73  150.41  511.89   151.1  511.74  151.85  511.59
  152.66  511.42  153.54  511.23   154.5  511.03  155.56  510.81  156.72  510.57
  158.01   510.3  159.45     510  161.05  509.67  162.52  509.36  162.67  509.35
  162.68  509.35  163.49  509.33   163.5  509.32  163.52  509.32  164.29  509.29
  164.33  509.29  165.06  509.27  165.14  509.26  165.17  509.26  165.26  509.25
     166  509.21  166.18   509.2  166.91  509.17  167.59  509.14  167.63  509.14
  167.75  509.12   168.4  509.09  168.61  509.07  182.99   508.2  183.63  508.15
  183.92  508.15  184.34   508.1  184.65   508.1  184.77   508.1  184.89  508.05
  184.99  508.05   185.1  508.05  185.61     508  185.88  507.95  186.45  507.95
  186.56  507.95  186.73  507.95  186.96   507.9  187.16  507.85  187.28  507.85
  187.42  507.85  187.65  507.85  188.03  507.85  188.61   507.8  188.72   507.8
  188.84   507.8  189.05  507.75  189.26  507.75   189.4  507.75  189.58  507.75
  189.62  507.75  189.75   507.7  190.08   507.7  190.29   507.7  190.39   507.7
  190.59   507.7  190.88   507.7     191   507.7   191.1   507.7  191.85   507.7
   192.4   507.7   192.5   507.7  192.62  507.65  193.19   507.6  193.32   507.6
  194.17  507.55  194.29  507.55   194.4  507.55  194.62   507.5  194.73  507.45
  195.08  507.45  195.73  507.45  195.96  507.45  196.08  507.45  196.19  507.45
  196.42   507.4  196.52   507.4  196.97   507.4  197.19   507.4  197.29  507.35
  197.41  507.35  197.53  507.35  197.63  507.35   198.1   507.3  198.21   507.3
  198.55   507.3  198.87   507.3  199.09   507.3  199.32  507.25  199.75  507.25
  199.87  507.25  200.35  507.25  200.67   507.2   201.1   507.2  201.22   507.2
  201.34  507.15  202.28   507.1  202.76   507.1  202.89   507.1  203.45  507.05
  203.81  507.05  203.93  507.05   204.4     507  204.84  506.95  205.16   506.9
  205.38  506.85  205.73  506.85  205.85  506.85  205.96   506.9  206.08   506.9
  206.51  506.95  206.63  506.95  206.99  506.95  207.09   506.9  207.38  506.85
  207.72   506.8  208.09   506.8   208.2  506.75  208.31  506.75  208.53  506.74
  208.99  506.69  209.11   506.6  228.83  505.43  228.85  505.43  228.91  505.43
  228.96  505.43  228.98  505.43  228.99  505.43  230.04  505.41  230.05  505.41
  230.07  505.41  230.08  505.41  230.09  505.41  230.68  505.34   230.7  505.32
  230.73  505.34  230.87  505.36  230.91   505.3  230.92   505.3  234.02   505.3
  235.36   505.3   235.4  505.29  235.46  505.28  235.56  505.26  242.37  505.55
   245.1  505.66  246.48  505.71  247.47  505.74  248.41  505.78  249.09   505.8
  254.01     506  254.53  506.01  256.63   506.1  258.41  506.22  258.67  506.23
  258.84  506.25   263.6  506.55   264.1  506.58  264.66  506.62  265.28  506.66
     281  507.76  281.03  507.71  281.05  507.75  281.07  507.74   281.1  507.74
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BR D #Mann= 3
       0     .06   77.78    .035  353.82     .06
BR D Banks=77.78,353.82
BC Design=,, 0 ,, 0 ,,,,,,
BC Use User HTab Curves=0
BC User HTab FreeFlow(D)= 0

Type RM Length L Ch R = 1 ,253684  ,79,79,94
BEGIN DESCRIPTION:
This cross section corresponds to cross section 253562.6 of the non-georeferenced CDC model which was the source of this model.
Downstream of Pedestrian Bridge.
Effective flow limit in LOB set at North Main Levee.
---------------------------------------------------------------------
RADIO SHACK RIVERFRONT CAMPUS CDC FW080602-01 IN ROB.
---------------------------------------------------------------------
END DESCRIPTION:
XS GIS Cut Line= 3
 2326050.7432071 6961442.6811672 2325854.6633519  6961112.171526
 2325675.4178468 6960663.6517383
#Sta/Elev= 30
       0  551.39   11.05  550.79   39.66     540   73.43     538   95.73  533.51
  118.24  524.67  127.01     518  141.15  512.06  150.61     510  226.45   505.5
  251.36  506.18  258.13  505.07   274.8  506.84  297.02  511.06  298.95  512.53
  317.02  514.88  335.74     522  338.72     526  341.42  533.51  388.04  535.62
  422.45  532.21  444.56  535.43  485.26     538  551.33  540.13  655.87  538.61
  703.25  540.81  762.84  549.57  788.95  551.84  816.19  552.07  867.31  556.96
#Mann= 3 ,-1,0
       0     .06       0   73.43    .035       0  341.42     .06       0
#XS Ineff= 1 ,-1
  834.08  867.31     565
Permanent Ineff=
       F
Bank Sta=73.43,341.42
XS Rating Curve= 0 ,0
Exp/Cntr=0.5,0.3

Type RM Length L Ch R = 1 ,253605  ,89,89,89
BEGIN DESCRIPTION:
This cross section corresponds to cross section 253483.7 of the non-georeferenced CDC model which was the source of this model.
Effective flow limit in LOB set at North Main Levee.
---------------------------------------------------------------------
RADIO SHACK RIVERFRONT CAMPUS CDC FW080602-01 IN ROB.
---------------------------------------------------------------------
END DESCRIPTION:
XS GIS Cut Line= 3
 2326103.0814074 6961391.3204344 2325926.9426674 6961069.2629057
 2325799.6017248 6960674.6838983
#Sta/Elev= 30
       0  549.89    9.57  549.53   32.51  540.46   59.86     540   71.59  538.44
   90.44  530.45   99.42  525.69  104.72     520   109.5     518  138.49  508.82
  188.42  507.93  202.58   506.1  232.02     507  259.76   508.9  280.91  513.05
  291.99  514.54  300.25     518  309.54   520.6  327.73   535.3  355.15  533.31
  368.16  534.73  413.09  533.32  436.69  537.52  468.56  539.88  559.56  540.22
  628.26  542.52  680.56  551.28  707.43  554.89  732.57  555.13   781.7  560.28
#Mann= 3 ,-1,0
       0     .06       0   71.59    .035       0  327.73     .06       0
#XS Ineff= 1 ,-1
   751.9   781.7     565
Permanent Ineff=
       F
Bank Sta=71.59,327.73
XS Rating Curve= 0 ,0
Exp/Cntr=0.3,0.1

Type RM Length L Ch R = 1 ,253517  ,50,50,51
BEGIN DESCRIPTION:
This cross section corresponds to cross section 253395.2 of the non-georeferenced CDC model which was the source of this model.
Effective flow limit in LOB set at North Main Levee.
---------------------------------------------------------------------
RADIO SHACK RIVERFRONT CAMPUS CDC FW080602-01 IN ROB.
---------------------------------------------------------------------
END DESCRIPTION:
XS GIS Cut Line= 6
2326157.577512556961346.63859262     2326157.088     6961339.518
     2326154.701     6961304.796 2326154.7388806 6961304.5528204
 2325998.5857216 6961012.47126482325900.973630716960693.73348845
#Sta/Elev= 30
   -33.6     544       0  540.64   26.95  539.65   46.46     528   51.29     520
      54     518   61.25     514   62.95   514.1   69.12     510   76.16     508
  152.34   506.9   193.1     510  206.44  512.08  207.47   511.3  210.44  513.05
  235.32  514.18  260.64     520  265.13  522.02  268.82  527.36  287.32   525.5
   298.8  527.24  311.71  533.39  325.26  537.85  349.72  537.83  379.59     540
  508.54  543.92  575.18  555.55  607.53  559.48  633.75  558.39  673.14  562.47
#Mann= 3 ,-1,0
   -33.6     .06       0   26.95    .035       0  325.26     .06       0
#XS Ineff= 2 ,-1
   -33.6       0     570  667.63  673.14     565
Permanent Ineff=
       F       F
Bank Sta=26.95,325.26
XS Rating Curve= 0 ,0
Exp/Cntr=0.3,0.1

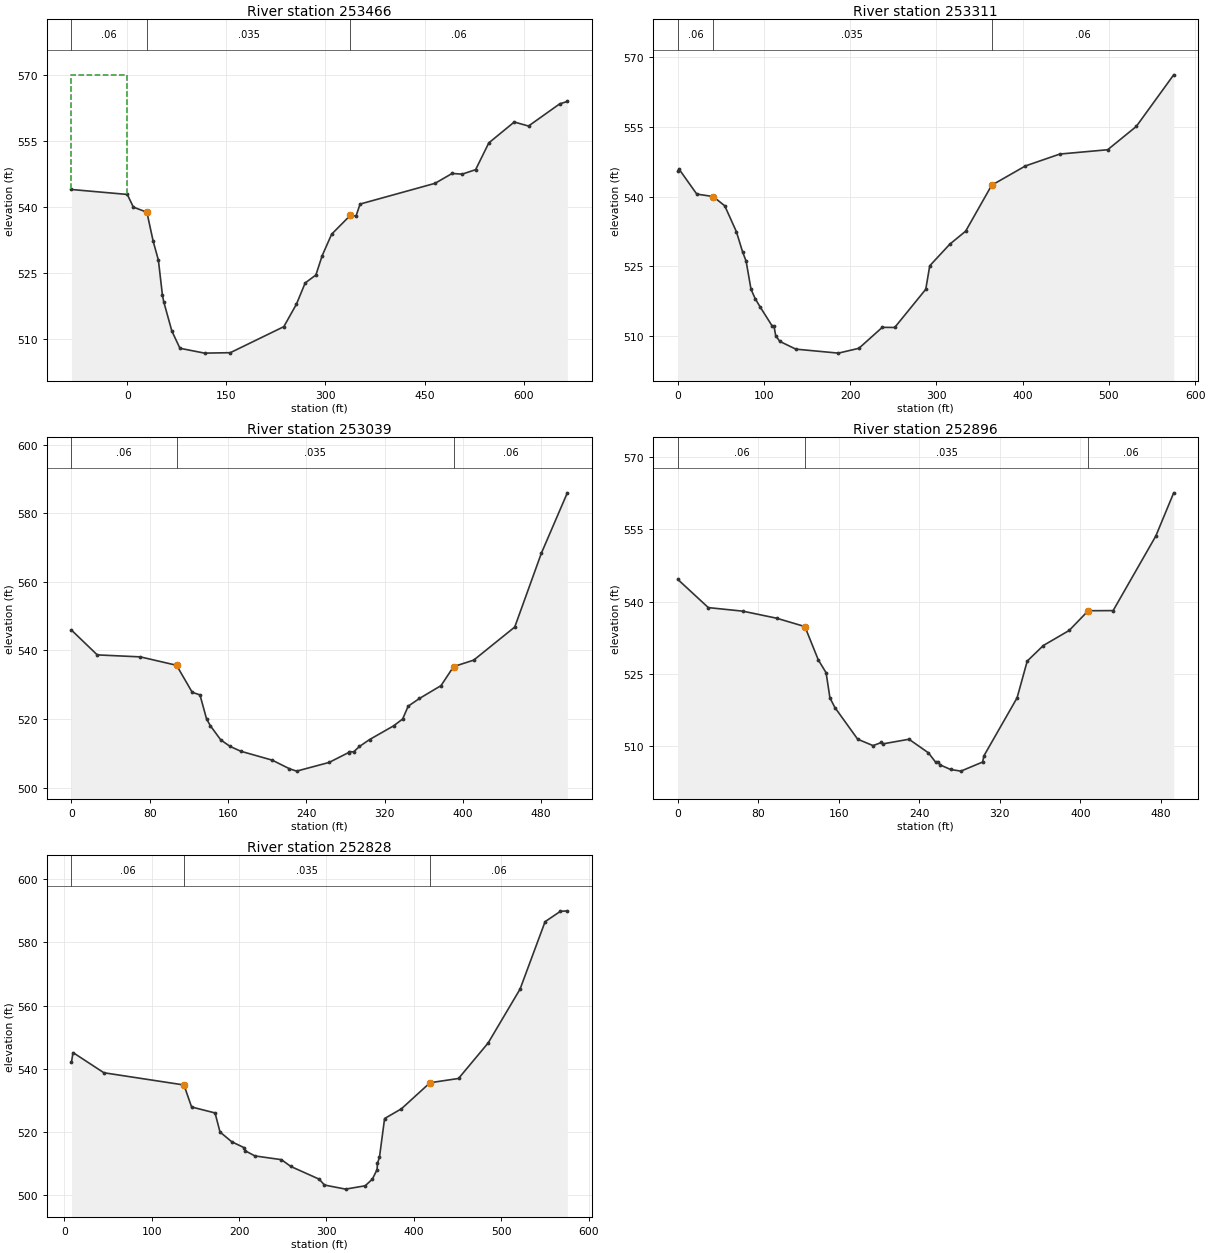
Type RM Length L Ch R = 1 ,253466  ,156,156,210
BEGIN DESCRIPTION:
This cross section corresponds to cross section 253345.2 of the non-georeferenced CDC model which was the source of this model.
Effective flow limit in LOB set at floodwall.
---------------------------------------------------------------------
RADIO SHACK RIVERFRONT CAMPUS CDC FW080602-01 IN ROB.
---------------------------------------------------------------------
END DESCRIPTION:
XS GIS Cut Line= 4
     2326170.543     6961360.568     2326201.142     6961283.745
 2326044.9709632 6960993.1833934 2325946.2676152 6960670.8818867
#Sta/Elev= 30
   -84.5     544       0  542.88    9.24     540   29.67  538.85   39.18  532.27
   47.08  527.99   53.23     520   55.15  518.56   67.41  511.93   79.71     508
  116.89   506.9  155.94     507  236.92   512.9  256.03     518  269.26  522.81
  285.45  524.61  294.99     529  309.32  533.87  337.36  538.11  346.24  537.99
  352.39   540.7  465.82   545.4   491.7  547.64  506.83  547.48  527.26   548.5
  547.22  554.57  585.72   559.3  607.29  558.39  654.46  563.41  666.05  563.96
#Mann= 3 ,-1,0
   -84.5     .06       0   29.67    .035       0  337.36     .06       0
#XS Ineff= 1 ,-1
   -84.5       0     570
Permanent Ineff=
       F
Bank Sta=29.67,337.36
XS Rating Curve= 0 ,0
Exp/Cntr=0.3,0.1

Type RM Length L Ch R = 1 ,253311  ,271,271,538
BEGIN DESCRIPTION:
This cross section corresponds to cross section 253189.2 of the non-georeferenced CDC model which was the source of this model.
Effective flow limit in LOB set at floodwall.
END DESCRIPTION:
XS GIS Cut Line= 2
 2326327.4376868 6961255.7276695 2326138.8949618 6960712.3377881
#Sta/Elev= 30
       0   545.4    1.34  545.93   21.98  540.53   40.93     540   54.44     538
   67.94  532.42   75.24     528    79.2  526.08    84.9     520    89.7     518
   95.35  516.24  109.76     512  111.53   512.1  113.52     510  118.32  508.77
  136.88   507.1  186.28  506.24     210  507.28  237.18   511.8  251.56  511.77
  287.57     520  292.21  525.07  315.53  529.74  333.85  532.53  364.05  542.44
  403.21   546.6  443.14  549.16  498.58  550.09  531.77  555.11  575.17  566.24
#Mann= 3 ,-1,0
       0     .06       0   40.93    .035       0  364.05     .06       0
Bank Sta=40.93,364.05
XS Rating Curve= 0 ,0
Exp/Cntr=0.3,0.1

Type RM Length L Ch R = 1 ,253039  ,143,143,222
BEGIN DESCRIPTION:
This cross section corresponds to cross section 252918.1 of the non-georeferenced CDC model which was the source of this model.
Effective flow limit in LOB set at floodwall.
END DESCRIPTION:
XS GIS Cut Line= 2
 2326491.7179567 6961293.0946713 2326595.0109944 6960797.0682768
#Sta/Elev= 30
       0  545.95   26.36  538.71    70.4  538.13  107.39  535.68  123.41  527.79
   131.3  527.05  138.07     520  142.05     518   152.5  513.93  162.13     512
  173.06   510.6  205.15     508  222.66  505.51  230.04   504.8  263.21  507.33
  283.11  510.21  283.89   510.5  288.21   510.4  294.31     512  304.54     514
  329.11     518  338.38     520  344.04  523.74  355.59     526  377.59  529.74
  390.45  535.29  410.99  537.18  452.95  546.84  480.17  568.39  506.67  585.99
#Mann= 3 ,-1,0
       0     .06       0  107.39    .035       0  390.45     .06       0
Bank Sta=107.39,390.45
XS Rating Curve= 0 ,0
Exp/Cntr=0.3,0.1

Type RM Length L Ch R = 1 ,252896  ,68,68,146
BEGIN DESCRIPTION:
This cross section corresponds to cross section 252774.7 of the non-georeferenced CDC model which was the source of this model.
Effective flow limit in LOB set at floodwall.
END DESCRIPTION:
XS GIS Cut Line= 2
 2326585.0785502 6961338.0115078 2326768.0893794 6960880.5092603
#Sta/Elev= 30
       0  544.59   30.31  538.74   64.63     538   98.16  536.54  126.27   534.8
  139.58  527.89  147.36  525.21  151.15     520  156.07     518  178.73  511.42
  193.99  510.09  202.33  510.74  204.05  510.46  229.73  511.41  248.95   508.6
  256.11  506.67  258.51  506.74  260.81  506.07  271.05  505.13  281.27  504.79
  302.81  506.67  304.25     508  337.11     520  347.22  527.64  363.21  530.87
  388.91     534  407.79  538.09  432.57  538.12     475  553.61  492.75  562.57
#Mann= 3 ,-1,0
       0     .06       0  126.27    .035       0  407.79     .06       0
Bank Sta=126.27,407.79
XS Rating Curve= 0 ,0
Exp/Cntr=0.5,0.3

Type RM Length L Ch R = 1 ,252828  ,126,126,135
BEGIN DESCRIPTION:
This cross section corresponds to cross section 252706.3 of the non-georeferenced CDC model which was the source of this model.
Upstream of North Main Street.
Effective flow limit in LOB set at floodwall.
END DESCRIPTION:
XS GIS Cut Line= 3
2326618.785971086961346.45629209 2326777.4314138 6961066.9943691
 2326899.0348186 6960852.7838583
#Sta/Elev= 30
    8.05     542    9.82  545.11   45.18  538.71  136.83  534.84  145.57  527.87
  172.43  525.98  178.13  519.94  191.55  516.85  205.78  514.97  206.96     514
  218.03  512.37  248.44  511.18  259.24  509.02  291.68     505  297.71  503.15
  321.85  501.85  344.34  502.91  352.55  505.03  357.86     508   358.4     510
  360.68     512  366.53  524.21  385.76  527.29  418.53  535.55  451.18   536.9
  485.11  548.16  521.64  565.23  550.27  586.57  567.66  589.82  575.72     590
#Mann= 3 ,-1,0
    8.05     .06       0  136.83    .035       0  418.53     .06       0
Bank Sta=136.83,418.53
XS Rating Curve= 0 ,0
Exp/Cntr=0.5,0.3