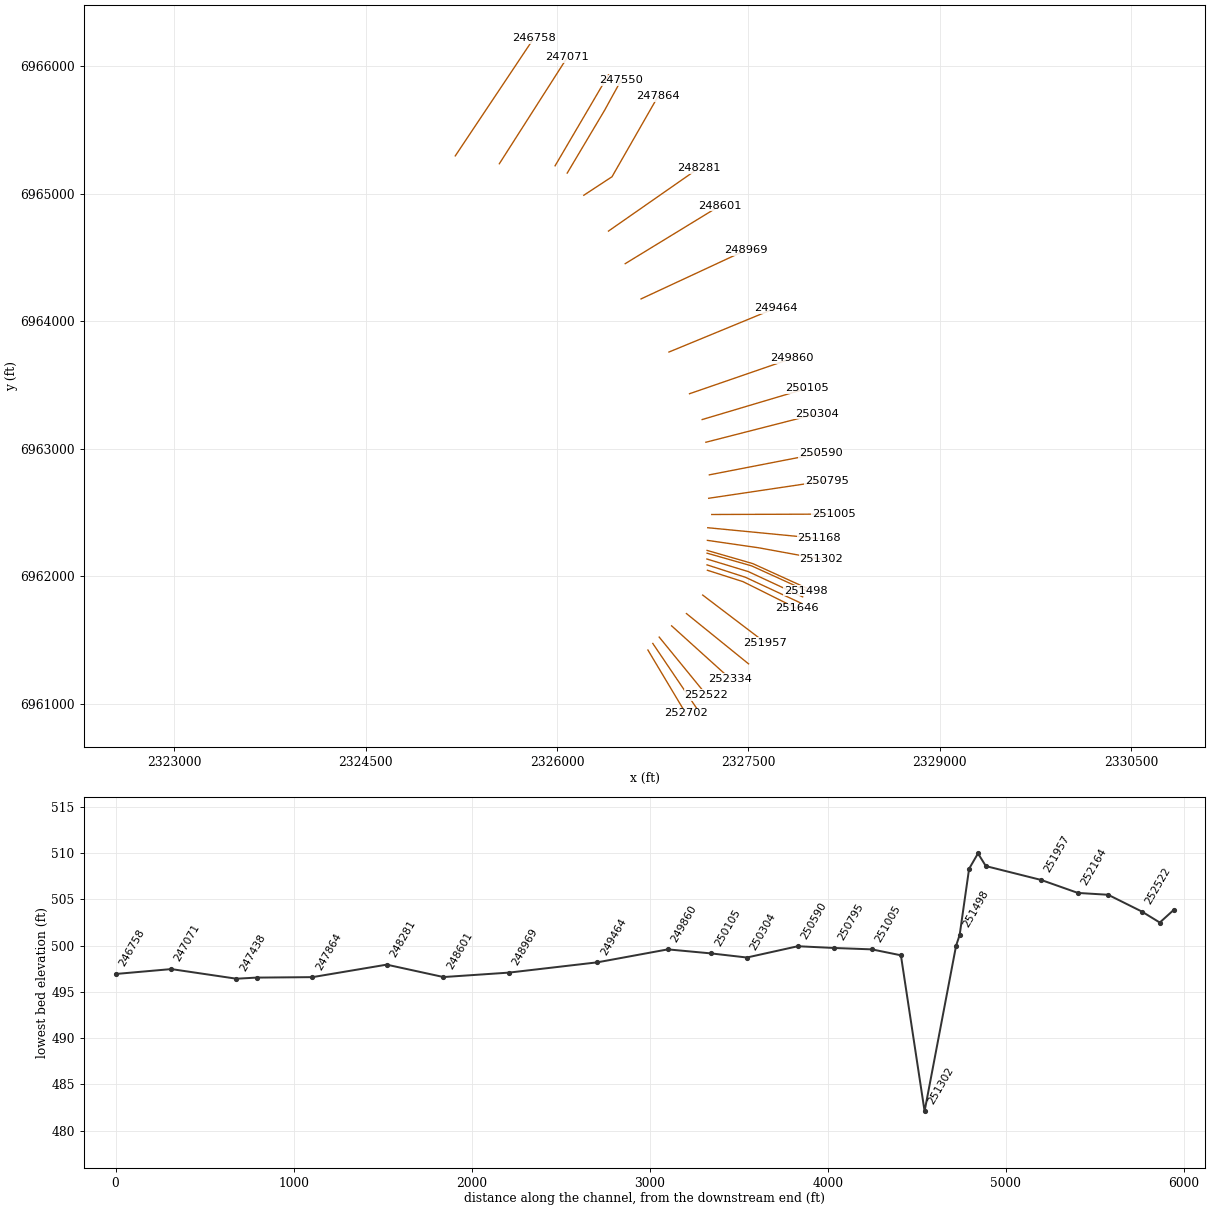
HEC-RAS study CDC_Consolidated_Model.prj: Upper Trinity CDC Consolidated Model

--- CDC_Consolidated_Model.g03 (geometry) --- (continued)

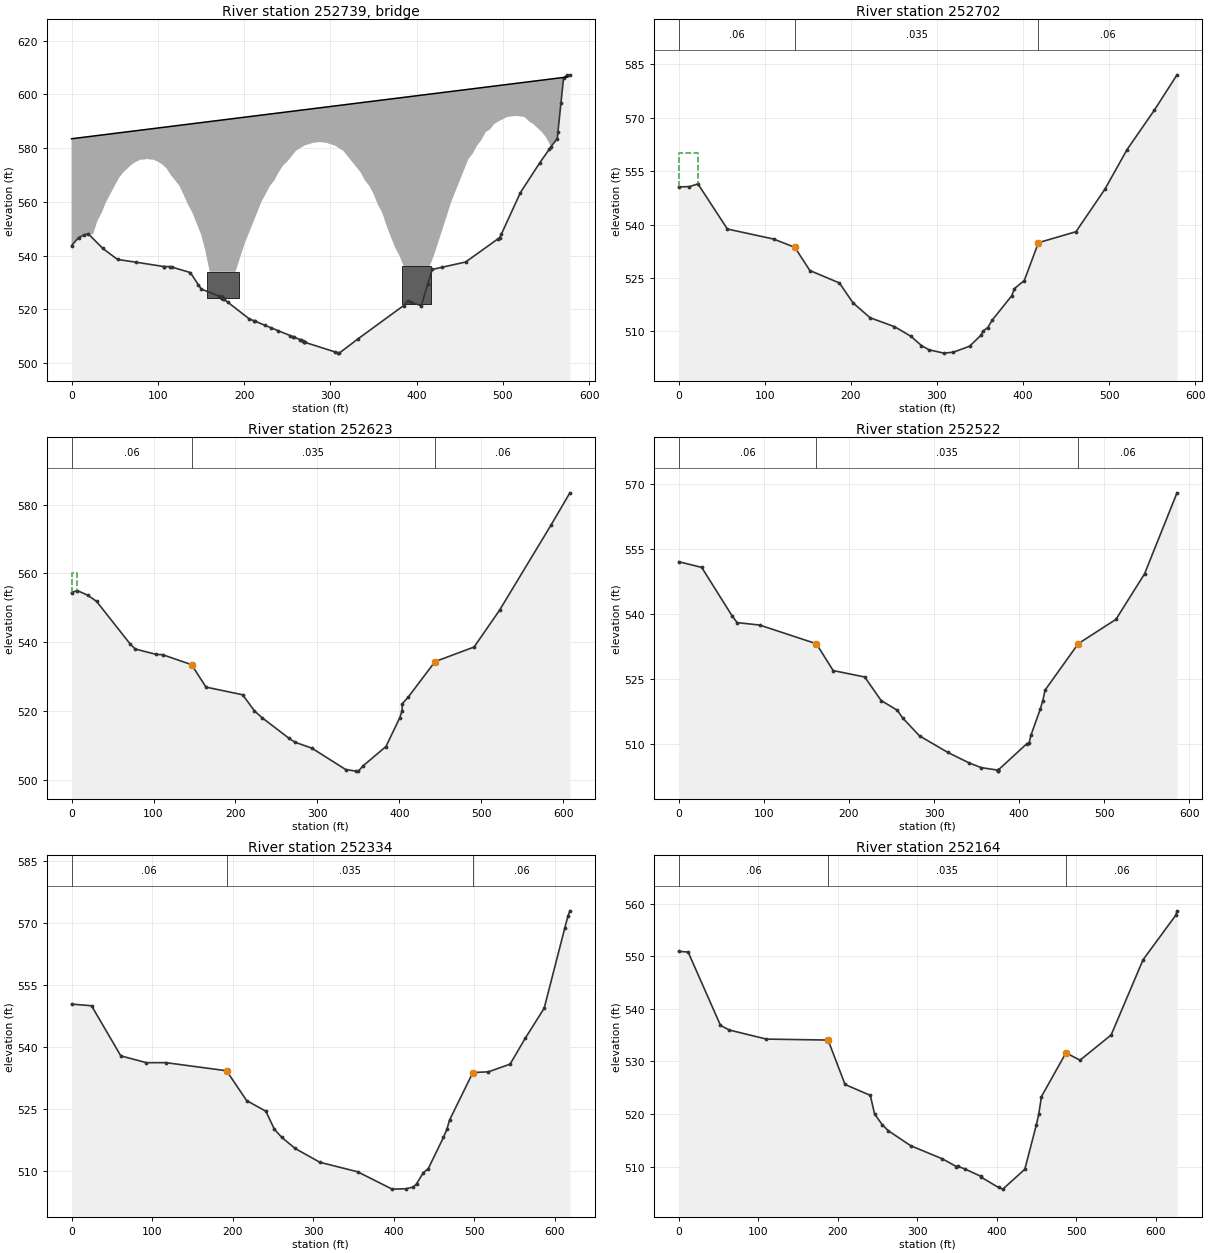
Type RM Length L Ch R = 3 ,252739  ,,,
BEGIN DESCRIPTION:
North Main Street
Data from bridge plans, USACE 1939 survey, USACE 1975 survey.
Note:  Internal bridge cross-sections modified to represent geometry under bridge.
END DESCRIPTION:
Node Name=North Main Stree
Bridge Culvert--1,0,-1,-1, 0
Deck Dist Width WeirC Skew NumUp NumDn MinLoCord MaxHiCord MaxSubmerge Is_Ogee
30,75,2.6,0, 105, 105, , , 0.95, 0, 0,0,,
       0      15      20      25      30      35      40      45      50      55
      60      65      70      75      80      85    87.5      90      95     100
     105     110     115     120     125     130     135     140     145     150
     155     160     190     195     200     205     210     215     220     225
     230     235     240     245     250     255     260     265     270     275
     280     285   287.5     290     295     300     305     310     315     320
     325     330     335     340     345     350     355     360     365     370
     375     380     385     415     420     425     430     435     440     445
     450     455     460     465     470     475     480     485     490     495
     500     505     510     515     520     525     530     535     540     545
     550     555     560     565     575
   583.5   584.1   584.3   584.5   584.7   584.9   585.1   585.3   585.5   585.7
   585.9   586.1   586.3   586.5   586.7   586.9     587   587.1   587.3   587.5
   587.7   587.9   588.1   588.3   588.5   588.7   588.9   589.1   589.3   589.5
   589.7   589.9   591.1   591.3   591.5   591.7   591.9   592.1   592.3   592.5
   592.7   592.9   593.1   593.3   593.5   593.7   593.9   594.1   594.3   594.5
   594.7   594.9     595   595.1   595.3   595.5   595.7   595.9   596.1   596.3
   596.5   596.7   596.9   597.1   597.3   597.5   597.7   597.9   598.1   598.3
   598.5   598.7   598.9   600.1   600.3   600.5   600.7   600.9   601.1   601.3
   601.5   601.7   601.9   602.1   602.3   602.5   602.7   602.9   603.1   603.3
   603.5   603.7   603.9   604.1   604.3   604.5   604.7   604.9   605.1   605.3
   605.5   605.7   605.9   606.1   606.5
     538     538     544     548     553     556     560     563     566     569
     571   572.5     574     575   575.7   575.8     576   575.8   575.7     575
     574   572.5     570     568     566   562.5     559     556     552     548
     542     534     534     539     544     548     552     556     560     563
     566     568     571   573.5     575     577     579     580     581   581.5
     582   582.2   582.3   582.2     582   581.5     581     580     579     577
     575     573     571     568     566     563     559     556   551.2     547
     543     540     536     536   540.1     545     550     555     560     564
     568     572     576     578     581     583     586     587     589     590
   590.8   591.6   591.8     592   591.8   591.6     590     589   587.5     586
     584     581     578     576     576
       0      15      20      25      30      35      40      45      50      55
      60      65      70      75      80      85    87.5      90      95     100
     105     110     115     120     125     130     135     140     145     150
     155     160     190     195     200     205     210     215     220     225
     230     235     240     245     250     255     260     265     270     275
     280     285   287.5     290     295     300     305     310     315     320
     325     330     335     340     345     350     355     360     365     370
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Pier Skew, UpSta & Num, DnSta & Num=  ,0, 2 ,0, 2 , 0 , 0 , 0 ,,
      34      30
     516     538
      34      30
     516     538
Pier Skew, UpSta & Num, DnSta & Num=  ,175, 2 ,175, 2 , 0 , 0 , 0 ,,
      37      30
     506     534
      37      30
     506     534
Pier Skew, UpSta & Num, DnSta & Num=  ,400, 2 ,400, 2 , 0 , 0 , 0 ,,
      34      30
     510     536
      34      30
     510     536
BR Coef=-1 , 0 , 0 ,, 0 ,,,0.8,-1,,0,
WSPro=,,,, 1 ,,,, 0 ,,,, 0 ,,,,-1 ,-1 ,-1 , 0 , 0 , 0 , 0 , 0
BR U #Sta/Elev= 71
       0  543.72     8.2  546.75   13.82  547.58   19.22  548.19   36.21  542.69
   53.23   538.6   74.91  537.58  107.17  535.95  107.64  535.95  114.17  535.95
  116.42  535.75  137.63  533.73  147.06  529.11  150.39  527.59  171.19  524.91
   172.7  524.72  173.27  524.65   173.7  524.53  173.73  524.53  173.78  524.52
  173.83   524.5  173.89  524.49  173.96  524.47  174.05  524.45  174.17  524.42
  174.33  524.38  174.56  524.32  174.91  524.23  175.51  524.08  176.77  523.77
  181.24  522.65  205.76  516.54  210.89  515.86  212.69  515.63  224.48  514.07
  231.54  513.15  239.49   512.1  253.17  510.31  256.16  509.92  257.95  509.69
  265.11  508.75  266.12  508.57  267.68  508.29  268.86  508.07  269.77  507.91
  270.51  507.77  305.09  504.23  309.17  503.85  310.18  503.76  332.45  509.18
  384.82  521.45  389.93  523.17   393.2  522.61  405.37  521.43  412.61  529.33
  418.04   534.9  429.27  535.69  456.75  537.66  494.49  546.34  496.27  546.71
  498.04  547.97  520.24   563.5  542.52  574.51  553.75  579.64   555.3  580.42
  562.99  583.56  563.63  585.85  567.13  596.63  570.16  605.98  574.08  607.13
  577.53  607.28
BR U #Mann= 3
       0     .06  137.63    .035  418.04     .06
BR U Banks=137.63,418.04
BR D #Sta/Elev= 71
       0  543.72     8.2  546.75   13.82  547.58   19.22  548.19   36.21  542.69
   53.23   538.6   74.91  537.58  107.17  535.95  107.64  535.95  114.17  535.95
  116.42  535.75  137.63  533.73  147.06  529.11  150.39  527.59  171.19  524.91
   172.7  524.72  173.27  524.65   173.7  524.53  173.73  524.53  173.78  524.52
  173.83   524.5  173.89  524.49  173.96  524.47  174.05  524.45  174.17  524.42
  174.33  524.38  174.56  524.32  174.91  524.23  175.51  524.08  176.77  523.77
  181.24  522.65  205.76  516.54  210.89  515.86  212.69  515.63  224.48  514.07
  231.54  513.15  239.49   512.1  253.17  510.31  256.16  509.92  257.95  509.69
  265.11  508.75  266.12  508.57  267.68  508.29  268.86  508.07  269.77  507.91
  270.51  507.77  305.09  504.23  309.17  503.85  310.18  503.76  332.45  509.18
  384.82  521.45  389.93  523.17   393.2  522.61  405.37  521.43  412.61  529.33
  418.04   534.9  429.27  535.69  456.75  537.66  494.49  546.34  496.27  546.71
  498.04  547.97  520.24   563.5  542.52  574.51  553.75  579.64   555.3  580.42
  562.99  583.56  563.63  585.85  567.13  596.63  570.16  605.98  574.08  607.13
  577.53  607.28
BR D #Mann= 3
       0     .06  137.63    .035  418.04     .06
BR D Banks=137.63,418.04
BC Design=,, 0 ,, 0 ,,,,,,
BC Use User HTab Curves=0
BC User HTab FreeFlow(D)= 0

Type RM Length L Ch R = 1 ,252702  ,78,78,103
BEGIN DESCRIPTION:
This cross section corresponds to cross section 252580.2 of the non-georeferenced CDC model which was the source of this model.
Downstream of North Main Street.
Effective flow limit in LOB set at North Main Levee.
END DESCRIPTION:
XS GIS Cut Line= 3
 2326712.0880094 6961421.3841722 2326984.0880523 6960966.4374708
 2327009.1965929 6960924.4409784
#Sta/Elev= 30
       0  550.59   12.38  550.65   22.37  551.42   56.56  538.74   110.2  535.93
  134.91   533.6  152.41  527.08  186.77  523.57  202.51     518  222.34  513.81
  250.74   511.3  269.68  508.62  281.99     506   290.7  504.81     308  503.86
  319.27  504.13  337.99   505.8  351.79  509.03  353.27     510  359.13  511.06
  364.45  513.19  386.97     520  390.16  522.01  401.56  524.27  417.97   534.9
  461.61  537.99  495.38     550  520.89  561.05  552.72  572.17  578.99  582.08
#Mann= 3 ,-1,0
       0     .06       0  134.91    .035       0  417.97     .06       0
#XS Ineff= 2 , 0
       0   22.37     560               0
Permanent Ineff=
       T       F
Bank Sta=134.91,417.97
XS Rating Curve= 0 ,0
Exp/Cntr=0.5,0.3

Type RM Length L Ch R = 1 ,252623  ,101,101,146
BEGIN DESCRIPTION:
This cross section corresponds to cross section 252502.1 of the non-georeferenced CDC model which was the source of this model.
Effective flow limit in LOB set at North Main Levee.
END DESCRIPTION:
XS GIS Cut Line= 2
  2326750.565098 6961472.6703634 2327091.3321848 6960968.9278091
#Sta/Elev= 30
       0  554.41    6.91     555   19.91  553.63   30.59  551.83    71.3  539.53
   77.69     538  103.52  536.43  111.03  536.36  146.48  533.45  164.05  526.93
  208.76  524.71  223.24     520  232.67     518  265.63     512  272.75   510.9
   293.4  509.16  334.48  502.97  347.03   502.5  350.11   502.5   355.6     504
  383.65  509.64  400.52     518  403.25     520  403.77  522.16  410.81     524
  443.56  534.34  491.28  538.59  522.35   549.3  585.03     574  608.18  583.42
#Mann= 3 ,-1,0
       0     .06       0  146.48    .035       0  443.56     .06       0
#XS Ineff= 2 , 0
       0    6.91     560               0
Permanent Ineff=
       T       F
Bank Sta=146.48,443.56
XS Rating Curve= 0 ,0
Exp/Cntr=0.3,0.1

Type RM Length L Ch R = 1 ,252522  ,189,189,269
BEGIN DESCRIPTION:
This cross section corresponds to cross section 252401.1 of the non-georeferenced CDC model which was the source of this model.
Effective flow limit in LOB set at North Main Levee.
END DESCRIPTION:
XS GIS Cut Line= 2
 2326800.8651359  6961522.335177 2327171.2081342 6961068.9246812
#Sta/Elev= 30
       0  552.07   27.03  550.75   62.54  539.62   68.61     538   94.98  537.44
  161.72  533.12  181.47  526.92  218.53  525.44  237.82     520  256.95  517.74
  263.01     516  282.94  511.83   316.3     508  341.37  505.57   355.5   504.5
  375.14  503.91  375.19  503.69  375.52     504   375.6  503.76  375.72     504
  408.85     510  411.83   510.3  413.87     512  424.78     518  427.81     520
  430.44   522.4   469.4  533.13  513.72  538.75   547.4   549.3  585.44  567.98
#Mann= 3 ,-1,0
       0     .06       0  161.72    .035       0   469.4     .06       0
Bank Sta=161.72,469.4
XS Rating Curve= 0 ,0
Exp/Cntr=0.3,0.1

Type RM Length L Ch R = 1 ,252334  ,170,170,194
BEGIN DESCRIPTION:
This cross section corresponds to cross section 252212.3 of the non-georeferenced CDC model which was the source of this model.
Effective flow limit in LOB set at North Main Levee.
END DESCRIPTION:
XS GIS Cut Line= 2
 2326898.1466187  6961610.727928 2327357.3784911 6961196.0365541
#Sta/Elev= 30
       0  550.27   24.79  549.86   61.14  537.74   92.98  536.09  117.05   536.1
  192.41  534.14   217.4  526.92  241.23  524.35  251.79     520  261.11     518
  277.69  515.33  308.24     512  355.08   509.7  398.05   505.5   415.2  505.59
   424.2     506  428.33  506.78  436.75  509.49  442.73  510.38   461.7     518
  466.06     520  469.36  522.23  498.28  533.71  517.57  533.88  544.51  535.74
  563.32     542  586.83  549.26  612.52  568.74  616.22  571.47  618.76  572.83
#Mann= 3 ,-1,0
       0     .06       0  192.41    .035       0  498.28     .06       0
Bank Sta=192.41,498.28
XS Rating Curve= 0 ,0
Exp/Cntr=0.3,0.1

Type RM Length L Ch R = 1 ,252164  ,206,206,220
BEGIN DESCRIPTION:
This cross section corresponds to cross section 252042.2 of the non-georeferenced CDC model which was the source of this model.
Effective flow limit in LOB set at North Main Levee.
END DESCRIPTION:
XS GIS Cut Line= 2
 2327014.5329246 6961706.8316532 2327501.4469624 6961312.7658811
#Sta/Elev= 30
       0  550.96   11.84  550.84   52.48  536.89   63.34     536  110.24  534.26
  187.79  534.08  209.12  525.62  240.87  523.55  246.26     520  255.71     518
  263.43  516.82   291.7  513.96  331.41  511.47  349.08     510  350.96  510.04
  359.72  509.55  379.84  508.14  379.95     508  402.09  506.01  407.44   505.7
  435.11  509.49   449.7     518  452.65     520     456  523.32  486.78  531.64
  504.48  530.25  543.58  535.04  583.73  549.37   624.9  557.86   626.4  558.68
#Mann= 3 ,-1,0
       0     .06       0  187.79    .035       0  486.78     .06       0
Bank Sta=187.79,486.78
XS Rating Curve= 0 ,0
Exp/Cntr=0.3,0.1

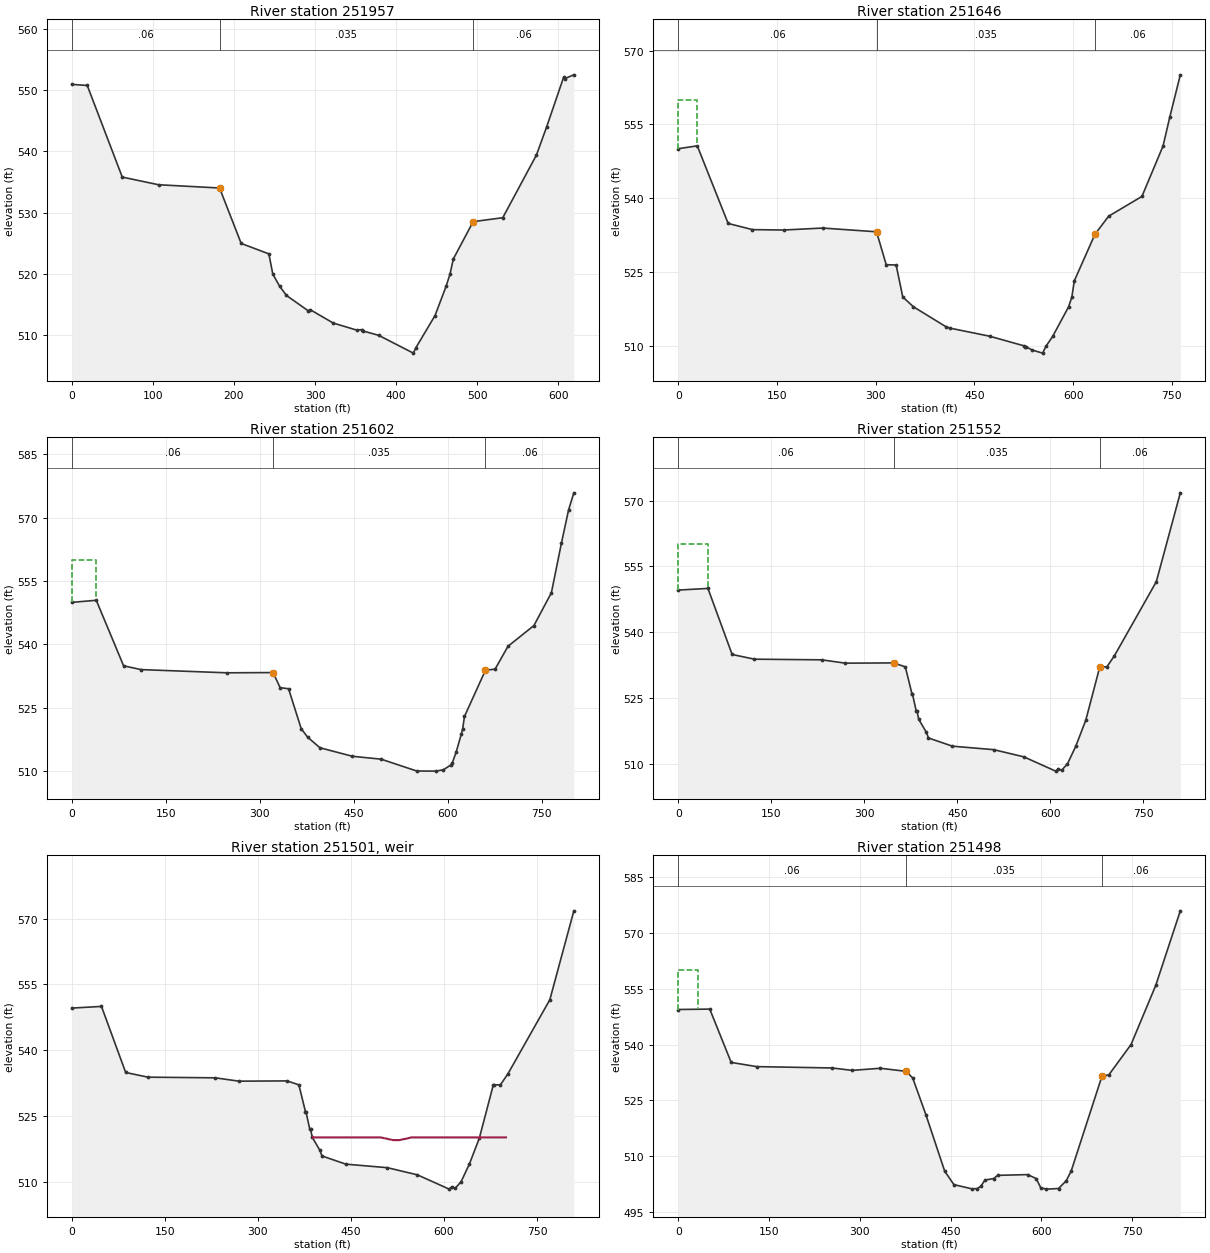
Type RM Length L Ch R = 1 ,251957  ,311,311,439
BEGIN DESCRIPTION:
This cross section corresponds to cross section 251835.9 of the non-georeferenced CDC model which was the source of this model.
Effective flow limit in LOB set at North Main Levee.
END DESCRIPTION:
XS GIS Cut Line= 2
 2327141.7009306 6961852.0960314 2327634.7068987 6961477.4548984
#Sta/Elev= 30
       0  550.91   19.09  550.74   62.27   535.8  107.06  534.55  182.28  534.02
  208.95  524.98  243.06  523.28  247.93     520  256.33     518   264.8   516.5
  291.61     514  293.94  514.19  322.54     512  351.23  510.86     358  510.93
  359.55   510.7  378.53     510  421.27   507.1  424.44  507.99  448.01  513.23
  461.67     518   466.5     520  470.57  522.45  494.99  528.53  531.56  529.18
  573.12  539.41  585.69     544  606.62  552.08   607.8  551.85   619.2  552.47
#Mann= 3 ,-1,0
       0     .06       0  182.28    .035       0  494.99     .06       0
Bank Sta=182.28,494.99
XS Rating Curve= 0 ,0
Exp/Cntr=0.3,0.1

Type RM Length L Ch R = 1 ,251646  ,44,44,54
BEGIN DESCRIPTION:
This cross section corresponds to cross section 251524.5 of the non-georeferenced CDC model which was the source of this model.
Effective flow limit in LOB set at North Main Levee.
At USGS gaging station 08048000 - Fort Worth Gage - located on left bank of West Fork.  Gage datum elev. 519.24 MSL.
END DESCRIPTION:
Node Name=FW Gage
XS GIS Cut Line= 3
 2327178.7941378  6962046.491246 2327458.0305516 6961957.1923281
 2327878.4237761 6961747.8798443
#Sta/Elev= 30
       0  550.08   28.93  550.66   75.83  534.91  112.79  533.66  160.09  533.58
  219.54  533.98  301.26  533.22  315.98  526.54  331.05  526.48  341.12     520
  357.34     518  406.21     514  412.21  513.69  473.25  512.03  524.78   510.1
  526.87  509.78  528.81  509.85  538.14  509.21  553.53   508.6  558.72     510
  568.79  511.98  593.09     518  598.05     520  601.72  523.26   633.1  532.71
  653.87  536.38  704.48   540.4  736.51  550.61  746.71  556.44  762.79  565.07
#Mann= 3 ,-1,0
       0     .06       0  301.26    .035       0   633.1     .06       0
#XS Ineff= 2 , 0
       0   28.93     560               0
Permanent Ineff=
       T       F
Bank Sta=301.26,633.1
XS Rating Curve= 0 ,0
Exp/Cntr=0.3,0.1

Type RM Length L Ch R = 1 ,251602  ,50,50,52
BEGIN DESCRIPTION:
This cross section corresponds to cross section 251480.3 of the non-georeferenced CDC model which was the source of this model.
Effective flow limit in LOB set at North Main Levee.
END DESCRIPTION:
XS GIS Cut Line= 3
 2327176.1076578 6962088.7917363 2327476.0535489  6961991.832014
 2327916.7245576 6961786.8421664
#Sta/Elev= 30
       0  549.91   39.09  550.41   82.72   534.9   110.6     534  247.86  533.24
  321.25   533.3  332.51  529.73  345.98  529.47  366.18     520  376.48     518
  396.06   515.5  447.95  513.48  493.71   512.8  550.44     510  581.45  509.97
  593.08   510.3  605.12  511.43  607.45     512  613.28   514.4  621.83  518.83
  623.83     520  626.72  522.92  660.21  533.87  675.52   534.1  696.21  539.53
  737.56  544.43  765.38  552.18  781.52     564  792.86  571.81  801.24  575.84
#Mann= 3 ,-1,0
       0     .06       0  321.25    .035       0  660.21     .06       0
#XS Ineff= 2 , 0
       0   39.09     560               0
Permanent Ineff=
       T       F
Bank Sta=321.25,660.21
XS Rating Curve= 0 ,0
Exp/Cntr=0.3,0.1

Type RM Length L Ch R = 1 ,251552  ,53,53,59
BEGIN DESCRIPTION:
This cross section corresponds to cross section 251430.2 of the non-georeferenced CDC model which was the source of this model.
Upstream of Nutt Dam.
Effective flow limit in LOB set at North Main Levee.
END DESCRIPTION:
XS GIS Cut Line= 3
 2327174.7353141 6962134.7109307 2327499.6455183 6962036.0026565
2327925.672625786961837.82479722
#Sta/Elev= 30
       0  549.58   47.89  549.96    86.9   534.9  122.84  533.83  231.39  533.68
  269.52  532.92  347.24  532.98  366.12  532.08  376.69     526  377.46     526
  383.68     522  384.91     522  387.81   520.1  400.13  517.13  403.42  515.87
  441.91     514  508.71   513.2  557.12  511.57  608.51  508.31  612.54   508.8
  618.12  508.51  627.52  509.97  640.96     514  657.04  519.91  679.48     532
  680.34  532.07  691.11  532.09  703.13  534.59  770.72  551.48  809.44  571.75
#Mann= 3 ,-1,0
       0     .06       0  347.24    .035       0  680.34     .06       0
#XS Ineff= 1 ,-1
       0   47.89     560
Permanent Ineff=
       T
Bank Sta=347.24,680.34
XS Rating Curve= 0 ,0
Exp/Cntr=0.3,0.1

Type RM Length L Ch R = 5 ,251501  ,,,
BEGIN DESCRIPTION:
Nutt Dam
Ogee weir.  Structure weir length 262.4 feet.  Crest elev. 520.1 feet, notch length 50 feet - minimum weir crest elev. 519.48
Data from project plans, design computations.
END DESCRIPTION:
Node Name=Nutt Dam
IW Pilot Flow=0
#Inline Weir SE= 6
  389.05   520.1  498.13   520.1  518.13  519.48  528.13  519.48  548.13   520.1
     700   520.1
IW Dist,WD,Coef,Skew,MaxSub,Min_El,Is_Ogee,SpillHt,DesHd
22.7,5,3.94,0,0.95,,-1 ,15.9,7,0,0,
Inline Weir Flap Gates= 0
IW Outlet Rating Curve= 0 ,False,,

Type RM Length L Ch R = 1 ,251498  ,20,20,20
BEGIN DESCRIPTION:
This cross section corresponds to cross section 251377 of the non-georeferenced CDC model which was the source of this model.
Downstream of Nutt Dam.
Effective flow limit in LOB set at North Main Levee.
END DESCRIPTION:
XS GIS Cut Line= 3
 2327175.9798351 6962180.5656952 2327525.3363205 6962080.9600695
 2327949.9562495 6961887.7745034
#Sta/Elev= 30
       0   549.4   52.11  549.51    87.5  535.19  129.66  534.06  254.35   533.7
  287.36  533.05  334.18  533.62  376.71  532.79  387.53     531  409.36  521.12
  440.35     506  455.56  502.37  485.73  501.22  494.47  501.32  500.12  501.94
  506.94  503.59  521.24     504  528.08  504.86  577.37  505.06  591.64     504
  599.17  501.51  608.49  501.16  628.49  501.32  641.05  503.37  649.39     506
   700.3   531.5  711.67  531.85  748.36     540  789.12  555.85  829.78   575.9
#Mann= 3 ,-1,0
       0     .06       0  376.71    .035       0   700.3     .06       0
#XS Ineff= 2 , 0
       0   32.45     560               0
Permanent Ineff=
       T       F
Bank Sta=376.71,700.3
XS Rating Curve= 0 ,0
Exp/Cntr=0.3,0.1

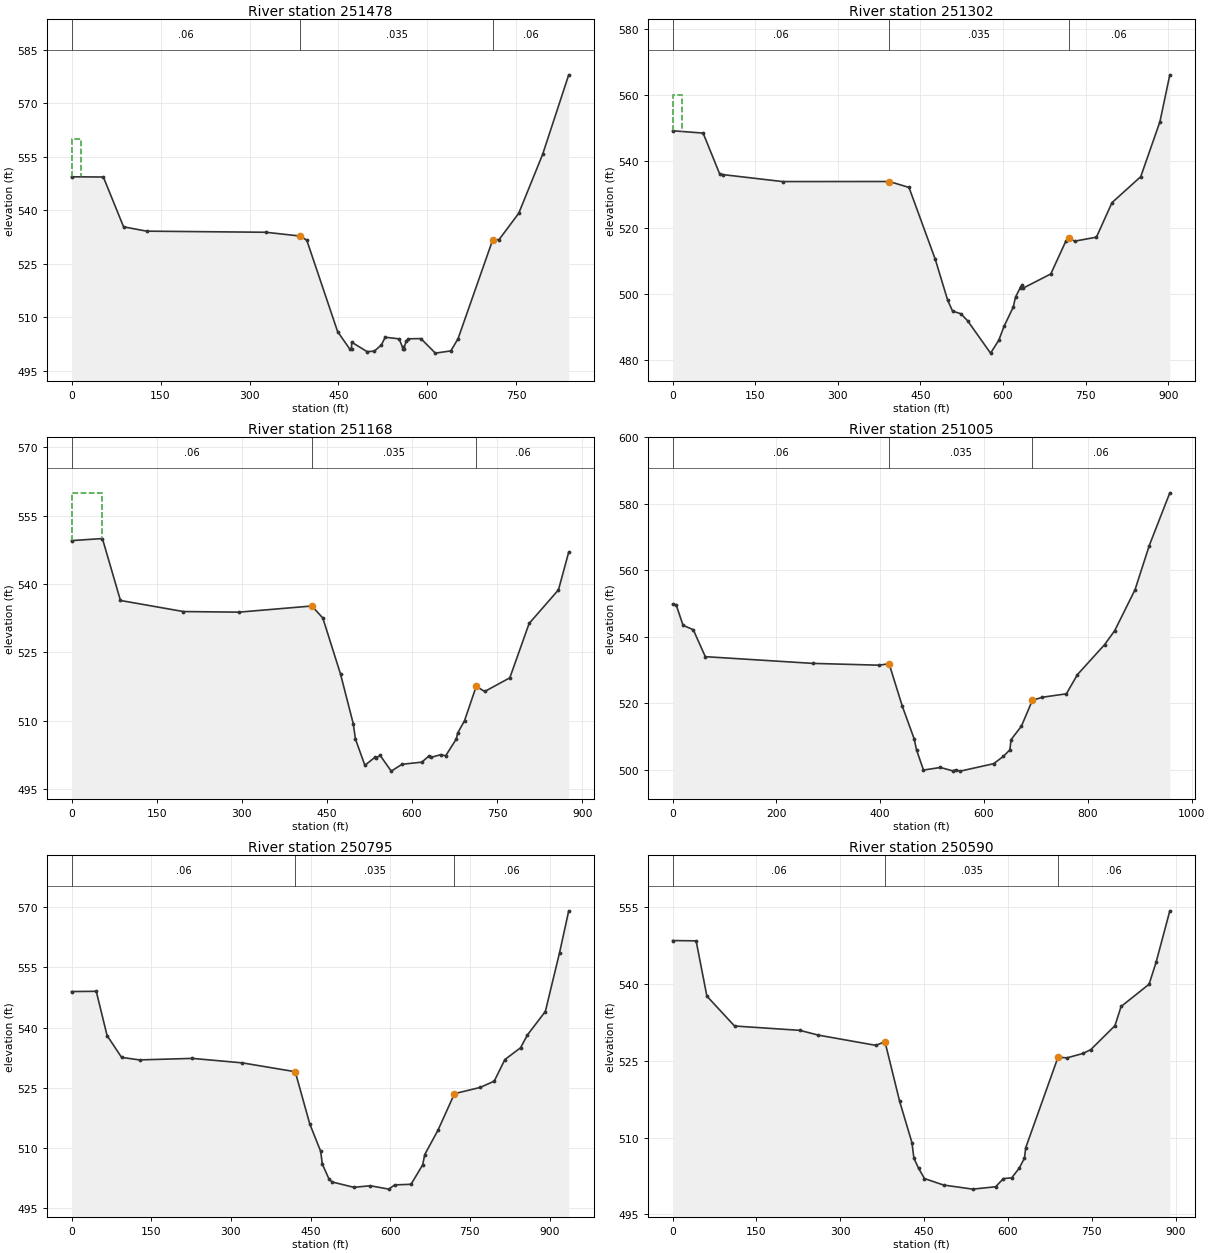
Type RM Length L Ch R = 1 ,251478  ,177,177,342
BEGIN DESCRIPTION:
This cross section corresponds to cross section 251357 of the non-georeferenced CDC model which was the source of this model.
Effective flow limit in LOB set at North Main Levee.
END DESCRIPTION:
XS GIS Cut Line= 3
 2327176.5641118 6962202.0933155 2327534.4327318 6962098.7941848
 2327958.2385366 6961905.9789933
#Sta/Elev= 30
       0  549.37   53.65  549.31   87.75  535.36  126.62  534.15  327.65  533.84
  385.41  532.78  396.56  531.62  448.59     506  469.44  501.05  471.95  501.17
  472.24  503.06  498.07  500.44  510.22  500.53  522.38  502.29  528.66  504.45
  552.15     504  559.42  501.07  559.58  501.85  560.09  501.11  563.76  503.29
  567.51     504  588.81  504.08  613.26     500  639.42  500.63  651.45     504
  710.07  531.76   720.6  531.77  753.81  539.15  794.05  555.62  838.09  577.92
#Mann= 3 ,-1,0
       0     .06       0  385.41    .035       0  710.07     .06       0
#XS Ineff= 2 , 0
       0   15.22     560               0
Permanent Ineff=
       T       F
Bank Sta=385.41,710.07
XS Rating Curve= 0 ,0
Exp/Cntr=0.3,0.1

Type RM Length L Ch R = 1 ,251302  ,133,133,178
BEGIN DESCRIPTION:
This cross section corresponds to cross section 251180.3 of the non-georeferenced CDC model which was the source of this model.
Effective flow limit in LOB set at North Main Levee.
END DESCRIPTION:
XS GIS Cut Line= 4
 2327178.7045582 6962280.9556285 2327583.3610742 6962222.2868352
 2327985.6781501 6962148.7417381 2328069.5106391 6962134.7696566
#Sta/Elev= 30
       0  549.21   55.39  548.51   85.16   536.3   90.68  535.99  199.67  533.88
  393.46   533.9  429.23  532.11  476.96  510.41  499.62     498  508.41  494.79
  523.42     494  535.55   491.9  577.37  482.11  592.33     486  601.84   490.2
  618.54     496  622.66     499  631.96   502.1   632.8  501.63  634.16  502.72
  635.56  501.65   686.7     506  714.34     516  719.29  516.75  730.48  515.91
   769.6   517.1   797.9  527.53  850.06  535.36  884.87  551.92  902.86  566.09
#Mann= 3 ,-1,0
       0     .06       0  393.46    .035       0  719.29     .06       0
#XS Ineff= 2 , 0
       0   17.93     560               0
Permanent Ineff=
       T       F
Bank Sta=393.46,719.29
XS Rating Curve= 0 ,0
Exp/Cntr=0.3,0.1

Type RM Length L Ch R = 1 ,251168  ,163,163,224
BEGIN DESCRIPTION:
This cross section corresponds to cross section 251047 of the non-georeferenced CDC model which was the source of this model.
Effective flow limit in LOB set at North Main Levee.
END DESCRIPTION:
XS GIS Cut Line= 2
 2327181.3945385  6962380.064094 2328053.6725539 6962295.7016465
#Sta/Elev= 30
       0  549.52   54.43  549.97   86.24  536.39  197.27  533.96  295.38  533.83
  423.58  535.18  442.95  532.54  474.17  520.23  496.64  509.33  500.42     506
  517.04  500.24  535.48  502.06  536.69  501.82  544.02   502.4  563.54  498.96
  582.47  500.46  617.43  500.93  630.23   502.3  634.34     502  650.75  502.57
  659.49  502.33  678.16     506  680.59   507.3  692.74  510.04  713.31  517.55
  728.29  516.43  772.54  519.43  806.57  531.35  858.31  538.73  876.35  547.01
#Mann= 3 ,0,0
       0     .06       0  423.58    .035       0  713.31     .06       0
#XS Ineff= 2 , 0
       0   54.43     560               0
Permanent Ineff=
       T       F
Bank Sta=423.58,713.31
XS Rating Curve= 0 ,0
Exp/Cntr=0.3,0.1

Type RM Length L Ch R = 1 ,251005  ,211,211,303
BEGIN DESCRIPTION:
This cross section corresponds to cross section 250884 of the non-georeferenced CDC model which was the source of this model.
Effective flow limit in LOB set at North Main Levee.
END DESCRIPTION:
XS GIS Cut Line= 2
 2327212.9072357 6962483.7148019 2328170.8142582 6962486.8555321
#Sta/Elev= 30
       0  549.72     6.7  549.68   20.09  543.45   39.76  542.13   62.99  534.02
  270.07     532  397.13  531.46  417.14  531.88  442.44  519.16  465.49  509.26
  469.91     506  483.29  499.92  515.86   500.7  539.35   499.7  545.58     500
  554.02   499.6  618.39  501.83  636.91     504  649.71     506  652.11  509.08
  672.01  513.12  692.95  520.85   711.8  521.81  758.61  522.85  779.89  528.62
  832.26  537.64  851.81  541.86  890.86  554.14  918.29  567.42  957.91  583.29
#Mann= 3 ,0,0
       0     .06       0  417.14    .035       0  692.95     .06       0
Bank Sta=417.14,692.95
XS Rating Curve= 0 ,0
Exp/Cntr=0.3,0.1

Type RM Length L Ch R = 1 ,250795  ,205,205,229
BEGIN DESCRIPTION:
This cross section corresponds to cross section 250673.4 of the non-georeferenced CDC model which was the source of this model.
Effective flow limit in LOB set at North Main Levee.
END DESCRIPTION:
XS GIS Cut Line= 2
 2327188.7806409 6962610.9036796 2328114.7001034  6962748.807494
#Sta/Elev= 30
       0  548.97   46.56  549.03   66.98     538   94.27  532.57  128.01  531.94
  227.52  532.32  321.65   531.2  421.21     529  448.55     516  469.12  509.16
  472.16     506  484.48  502.36   490.5  501.54  531.66   500.2  562.53  500.59
  597.41  499.75   608.3   500.8  639.25  500.96  661.14   505.8  665.06  508.36
   690.3  514.52  720.99  523.53  769.58  525.09  795.88  526.65  815.93  532.03
   845.4  534.96  858.51  538.19  892.12     544  918.92  558.68  936.13  569.08
#Mann= 3 ,0,0
       0     .06       0  421.21    .035       0  720.99     .06       0
Bank Sta=421.21,720.99
XS Rating Curve= 0 ,0
Exp/Cntr=0.3,0.1

Type RM Length L Ch R = 1 ,250590  ,286,286,317
BEGIN DESCRIPTION:
This cross section corresponds to cross section 250468.9 of the non-georeferenced CDC model which was the source of this model.
Effective flow limit in LOB set at North Main Levee.
END DESCRIPTION:
XS GIS Cut Line= 2
 2327194.0631139  6962794.642035 2328067.1718471  6962964.238743
#Sta/Elev= 30
       0  548.46   42.04   548.4    61.3  537.61  110.73  531.78  227.62  530.93
   260.7     530   363.7     528  379.84  528.73   406.1  517.08  428.15  509.01
  431.62     506  440.03     504  450.58     502  484.63  500.74  536.82  499.94
  577.78   500.4  591.78     502  606.59  502.14  619.79     504  629.47     506
  631.62  508.01  689.47   525.7  705.36  525.56  734.01  526.42  747.89  527.16
  791.25  531.84   802.3  535.59  852.31  539.93  864.81  544.19  889.43  554.26
#Mann= 3 ,0,0
       0     .06       0  379.84    .035       0  689.47     .06       0
Bank Sta=379.84,689.47
XS Rating Curve= 0 ,0
Exp/Cntr=0.3,0.1

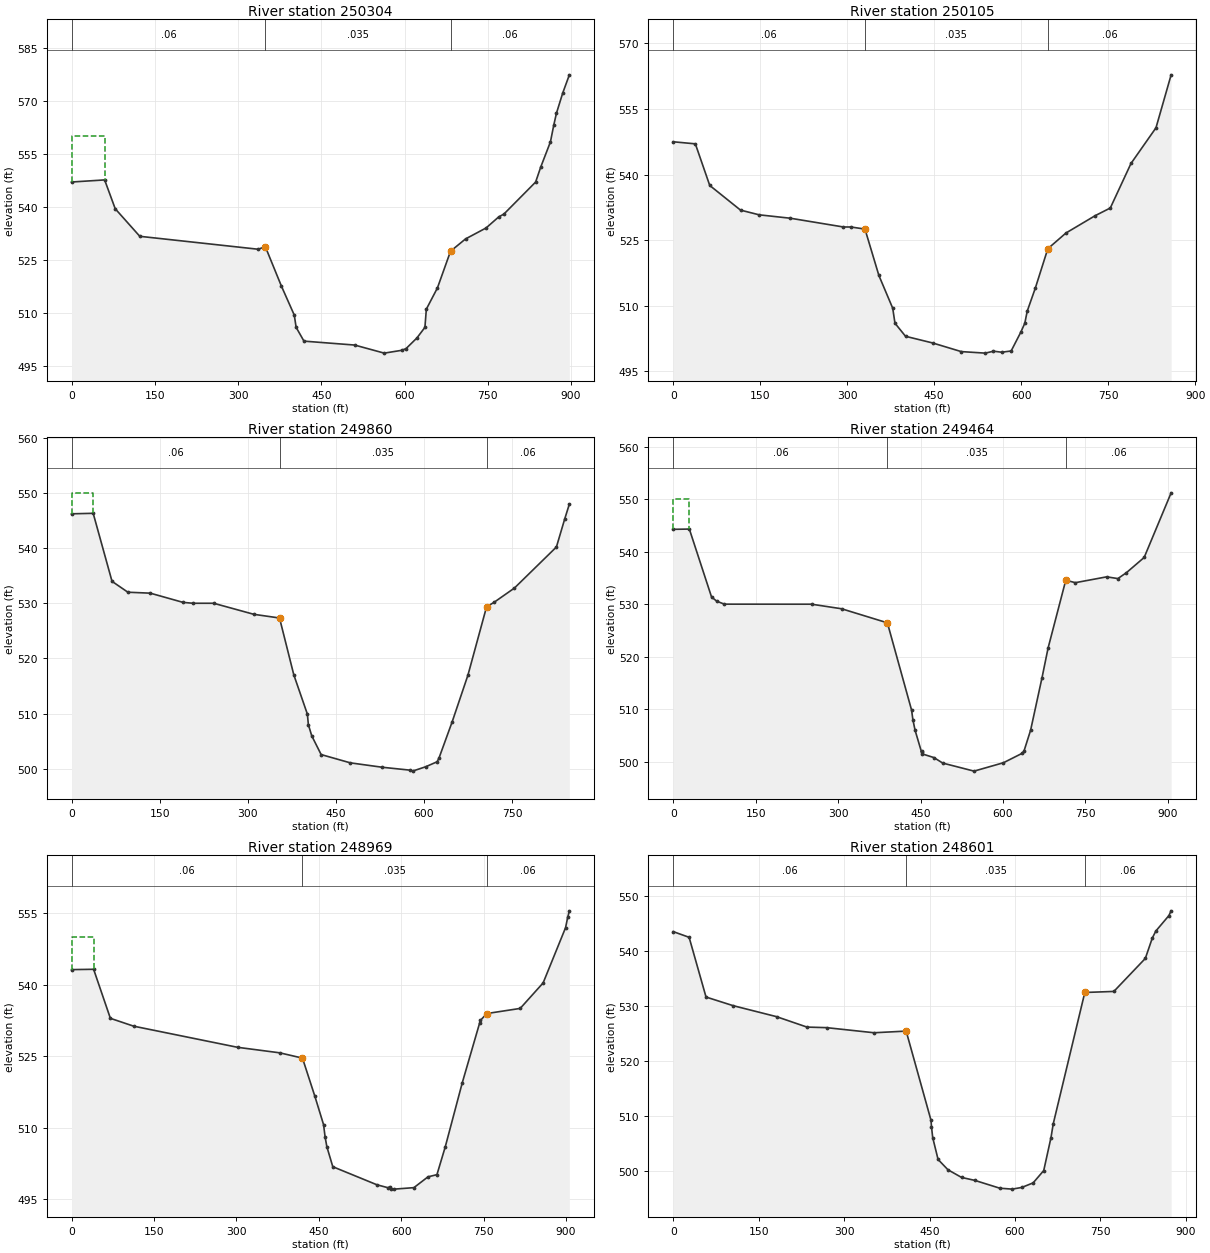
Type RM Length L Ch R = 1 ,250304  ,199,199,218
BEGIN DESCRIPTION:
This cross section corresponds to cross section 250182.7 of the non-georeferenced CDC model which was the source of this model.
Effective flow limit in LOB set at North Main Levee.
END DESCRIPTION:
XS GIS Cut Line= 2
 2327166.7837325 6963050.1515266 2328035.7690825 6963272.5977256
#Sta/Elev= 30
       0  547.06   59.61  547.65   78.67  539.51  122.94  531.72  336.74  528.06
  349.04  528.84  378.16  517.65  401.33  509.46  404.68     506  418.77  502.11
  510.16     501  563.43  498.72  595.18  499.52  602.73     500  622.24  502.99
  636.75     506  639.29  511.14  659.31  517.15   682.9  527.51  709.89  530.98
  746.95  534.08  769.61  537.19  779.15  538.02  836.23  547.05  845.51  551.32
  862.95  558.42  868.91  563.13  873.73  566.49  885.04  572.19  897.01  577.34
#Mann= 3 ,0,0
       0     .06       0  349.04    .035       0   682.9     .06       0
#XS Ineff= 2 , 0
       0   59.61     560               0
Permanent Ineff=
       T       F
Bank Sta=349.04,682.9
XS Rating Curve= 0 ,0
Exp/Cntr=0.3,0.1

Type RM Length L Ch R = 1 ,250105  ,245,245,267
BEGIN DESCRIPTION:
This cross section corresponds to cross section 249983.8 of the non-georeferenced CDC model which was the source of this model.
Effective flow limit in LOB set at North Main Levee.
END DESCRIPTION:
XS GIS Cut Line= 2
 2327137.5308779 6963228.0558011 2327960.3888355 6963473.0287373
#Sta/Elev= 30
       0  547.48   37.99  547.01    62.8   537.5  115.86  531.86  148.08  530.78
  202.02     530  293.39     528  306.24     528  330.52  527.52  354.54  516.91
  378.39  509.42  382.26     506  400.47  503.01  447.36  501.48  496.56  499.51
  538.13  499.16  552.18   499.6  566.32  499.37  582.62  499.65  599.48     504
  606.19     506  610.35  508.76  624.26     514  645.88  523.03  677.23  526.63
  727.57  530.59  753.63  532.34  789.31  542.52  832.43  550.68  858.55  562.79
#Mann= 3 ,-1,0
       0     .06       0  330.52    .035       0  645.88     .06       0
Bank Sta=330.52,645.88
XS Rating Curve= 0 ,0
Exp/Cntr=0.3,0.1

Type RM Length L Ch R = 1 ,249860  ,396,396,423
BEGIN DESCRIPTION:
This cross section corresponds to cross section 249738.4 of the non-georeferenced CDC model which was the source of this model.
Effective flow limit in LOB set at North Main Levee.
END DESCRIPTION:
XS GIS Cut Line= 2
 2327038.4845087 6963430.5944609 2327839.5852579 6963706.8361165
#Sta/Elev= 30
       0   546.2   36.82  546.29   68.89  533.97   95.87     532  133.98  531.83
  189.79  530.16   206.7     530  241.92     530  310.27     528  354.02  527.33
  378.32  517.04  401.43  509.92  403.15     508  408.84     506  424.85   502.6
  474.47   501.1     529   500.3  576.69  499.77  580.45   499.6  602.79  500.39
  622.34   501.3  625.59     502  647.94  508.54  674.79     517   706.4  529.34
  719.47  530.19  753.83  532.75  825.36  540.19  839.31  545.21  847.39  547.96
#Mann= 3 ,-1,0
       0     .06       0  354.02    .035       0   706.4     .06       0
#XS Ineff= 2 , 0
       0   36.82     550               0
Permanent Ineff=
       T       F
Bank Sta=354.02,706.4
XS Rating Curve= 0 ,0
Exp/Cntr=0.3,0.1

Type RM Length L Ch R = 1 ,249464  ,496,496,519
BEGIN DESCRIPTION:
This cross section corresponds to cross section 249342.9 of the non-georeferenced CDC model which was the source of this model.
Effective flow limit in LOB set at North Main Levee.
END DESCRIPTION:
XS GIS Cut Line= 2
  2326877.343543 6963757.4803422 2327715.2765389 6964102.7824116
#Sta/Elev= 30
       0  544.25   29.17   544.3   69.56  531.37   79.01  530.56   92.93     530
  251.76  529.99  306.35  529.12  389.73  526.44  433.73  509.83  436.15     508
  440.08     506  451.83  501.84  452.12     502  452.61   501.5  474.39  500.78
  490.54  499.73  547.51   498.2  601.04   499.8  635.22   501.6  638.35     502
  650.48     506  671.25     516  682.23  521.62  714.46  534.55  731.99  534.09
  788.99   535.2  809.34  534.87     825     536   857.2  538.89  906.29   551.2
#Mann= 3 ,-1,0
       0     .06       0  389.73    .035       0  714.46     .06       0
#XS Ineff= 2 , 0
       0   29.17     550               0
Permanent Ineff=
       T       F
Bank Sta=389.73,714.46
XS Rating Curve= 0 ,0
Exp/Cntr=0.3,0.1

Type RM Length L Ch R = 1 ,248969  ,368,368,434
BEGIN DESCRIPTION:
This cross section corresponds to cross section 248847.2 of the non-georeferenced CDC model which was the source of this model.
Effective flow limit in LOB set at North Main Levee.
END DESCRIPTION:
XS GIS Cut Line= 2
 2326658.6521676 6964174.1448004 2327480.4710798 6964556.2791165
#Sta/Elev= 30
       0   543.2   40.17  543.27   70.67  532.97  113.12  531.32   302.3  526.88
   379.1  525.72  420.41  524.61  443.06  516.57  458.78  510.65  461.68     508
  464.81     506   475.6   501.8  556.02     498  576.69  497.37  579.48  497.61
  581.02   497.2  587.46  497.09  623.26   497.4  648.92  499.67  665.23  500.13
  680.44     506  711.39  519.45  743.08  532.03  744.49  532.54  755.87  533.97
   816.8  535.05  858.57  540.41  899.38     552  903.32  554.19  906.32  555.55
#Mann= 3 ,-1,0
       0     .06       0  420.41    .035       0  755.87     .06       0
#XS Ineff= 2 , 0
       0   40.17     550               0
Permanent Ineff=
       T       F
Bank Sta=420.41,755.87
XS Rating Curve= 0 ,0
Exp/Cntr=0.3,0.1

Type RM Length L Ch R = 1 ,248601  ,319,319,354
BEGIN DESCRIPTION:
This cross section corresponds to cross section 248479.3 of the non-georeferenced CDC model which was the source of this model.
Effective flow limit in LOB set at North Main Levee.
END DESCRIPTION:
XS GIS Cut Line= 2
 2326534.3434485 6964450.3864559 2327280.1958925 6964906.1852653
#Sta/Elev= 30
       0  543.47   27.73  542.44   57.43  531.57  105.01     530  181.22     528
  234.69   526.1  268.97     526   352.5  525.07  408.82  525.37  452.43  509.15
  453.29     508  455.43     506  464.88  502.01  482.26  500.13  506.12  498.74
  529.43   498.2  573.18  496.78  595.06  496.61  611.97  496.92  631.81  497.75
  650.39  499.99  663.16     506  667.08  508.49  722.53   532.4  773.53  532.59
  828.81   538.6  841.06  542.31  847.22  543.58  870.07  546.38   874.1  547.26
#Mann= 3 ,-1,0
       0     .06       0  408.82    .035       0  722.53     .06       0
Bank Sta=408.82,722.53
XS Rating Curve= 0 ,0
Exp/Cntr=0.3,0.1

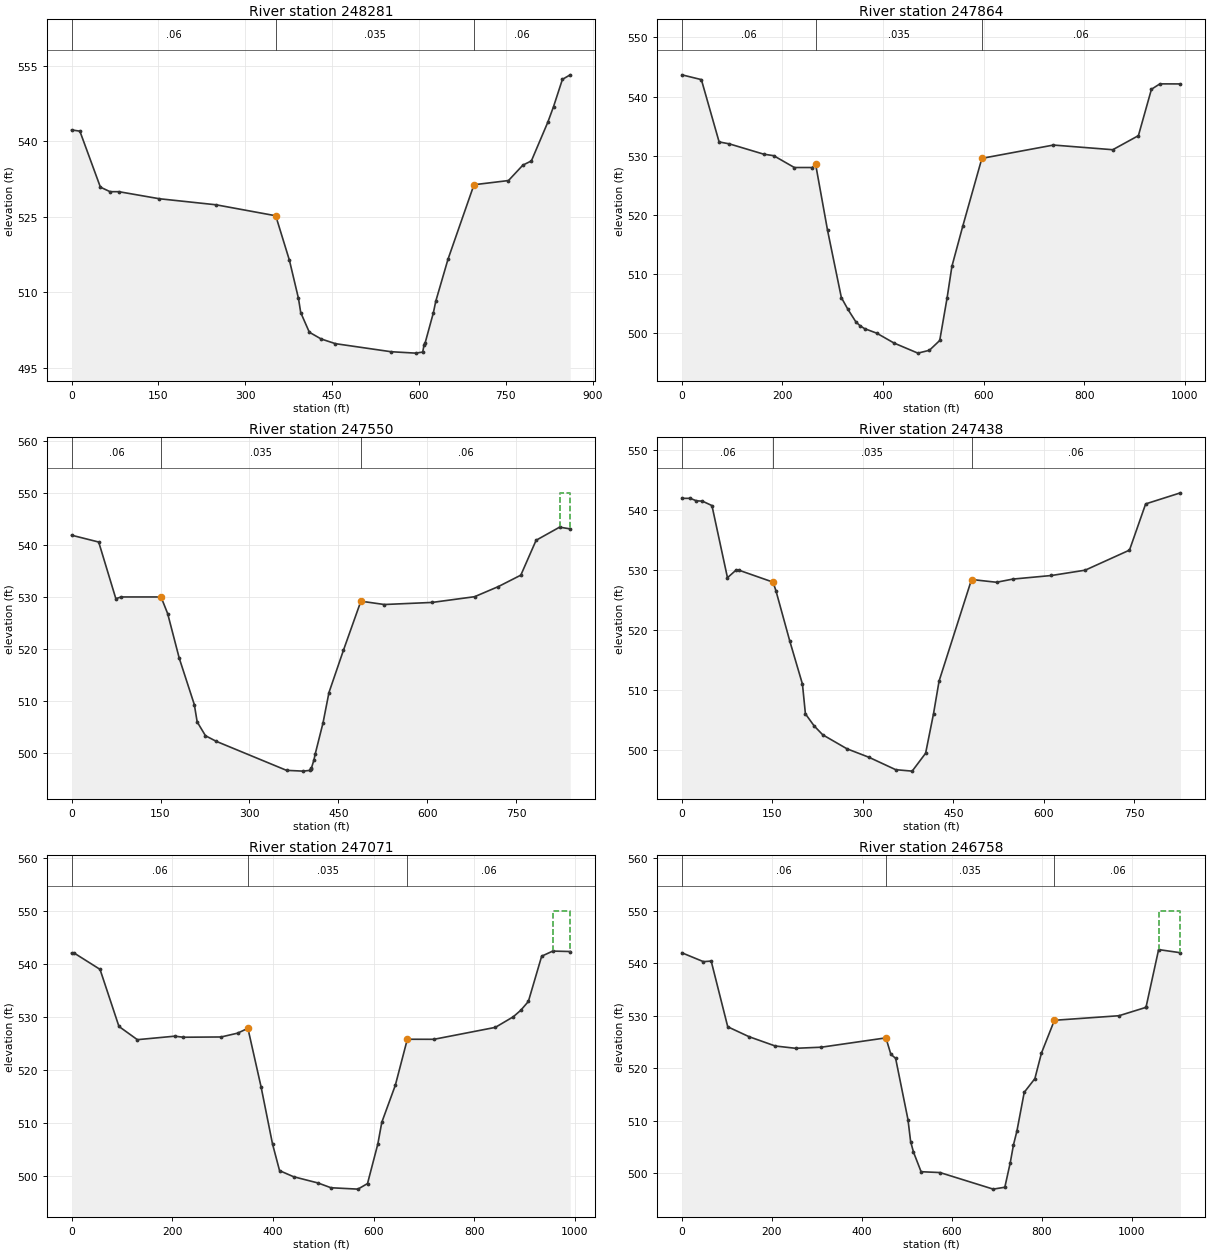
Type RM Length L Ch R = 1 ,248281  ,417,417,620
BEGIN DESCRIPTION:
This cross section corresponds to cross section 248160 of the non-georeferenced CDC model which was the source of this model.
Effective flow limit in LOB set at North Main Levee.
END DESCRIPTION:
XS GIS Cut Line= 2
 2326403.1286751  6964705.910078 2327109.8468975 6965198.5410045
#Sta/Elev= 30
       0  542.26   14.28  542.02   49.76   530.9    66.5     530    81.7     530
  151.57   528.6  249.55   527.4  352.69  525.22  376.31   516.4     392   508.8
  395.87     506  410.74   502.1     431  500.77  455.74  499.83  551.84  498.23
  594.51  497.95  606.58  498.16  609.02   499.6  610.87     500  625.13     506
  629.22  508.26   650.3  516.58  695.21  531.38  754.81  532.21  779.67  535.27
   794.4  536.11  822.84  543.81  832.71   546.9  848.01   552.3  861.47   553.2
#Mann= 3 ,-1,0
       0     .06       0  352.69    .035       0  695.21     .06       0
Bank Sta=352.69,695.21
XS Rating Curve= 0 ,0
Exp/Cntr=0.3,0.1

Type RM Length L Ch R = 1 ,247864  ,314,314,354
BEGIN DESCRIPTION:
This cross section corresponds to cross section 247743 of the non-georeferenced CDC model which was the source of this model.
Effective flow limit in LOB set at North Main Levee.
Effective flow limit in ROB set at West Fork Levee Loop.
END DESCRIPTION:
XS GIS Cut Line= 3
 2326209.7595421 6964986.7556834 2326430.7527629 6965131.7825655
 2326791.9382906  6965762.769223
#Sta/Elev= 30
       0  543.68   38.77  542.87   74.03  532.33    94.4     532  162.59  530.26
  182.61     530  223.62     528  259.45     528  265.82   528.6  289.61  517.39
  317.09     506  330.18     504  345.94  501.89   354.3  501.23  363.29  500.74
  387.37  499.98  421.96   498.3  469.25   496.6  492.14  497.08  512.69  498.74
  527.45     506   536.9  511.28  558.47  518.07  596.49  529.55  738.79   531.8
  856.78  531.01  907.72  533.39  933.64  541.24  950.44  542.15  991.38  542.14
#Mann= 3 ,-1,0
       0     .06       0  265.82    .035       0  596.49     .06       0
Bank Sta=265.82,596.49
XS Rating Curve= 0 ,0
Exp/Cntr=0.3,0.1

Type RM Length L Ch R = 1 ,247550  ,113,113,115
BEGIN DESCRIPTION:
This cross section corresponds to cross section 247429.1 of the non-georeferenced CDC model which was the source of this model.
Effective flow limit in LOB set at North Main Levee.
Effective flow limit in ROB set at West Fork Levee Loop.
END DESCRIPTION:
XS GIS Cut Line= 3
  2326079.776326 6965160.6962881 2326373.3159157 6965654.0634265
 2326501.7117194 6965887.9725712
#Sta/Elev= 30
       0  541.86    45.7  540.55   74.66  529.66   83.38     530  150.87     530
  162.05  526.79  181.55  518.24  206.97  509.33   211.8     506   225.8  503.35
  244.03  502.27  362.47   496.7  390.61  496.55  402.33   496.7  404.03  497.13
  404.16  497.01  408.76  498.72  410.82  499.82  424.08  505.84  434.07  511.65
   458.4  519.74  487.87  529.19   527.4  528.55  608.08  528.95   679.7  530.05
  719.85     532  757.63  534.19  783.42  540.89  823.08  543.41  840.92  543.07
#Mann= 3 ,-1,0
       0     .06       0  150.87    .035       0  487.87     .06       0
#XS Ineff= 2 , 0
       0                  823.08       0     550
Permanent Ineff=
       F       T
Bank Sta=150.87,487.87
XS Rating Curve= 0 ,0
Exp/Cntr=0.3,0.1

Type RM Length L Ch R = 1 ,247438  ,366,366,338
BEGIN DESCRIPTION:
This cross section corresponds to cross section 247316.2 of the non-georeferenced CDC model which was the source of this model.
Effective flow limit in LOB set at North Main Levee.
Effective flow limit in ROB set at West Fork Levee Loop.
END DESCRIPTION:
XS GIS Cut Line= 2
 2325984.5523215 6965217.6880894  2326402.833231 6965930.4384791
#Sta/Elev= 30
       0     542   13.96     542   23.98  541.59   34.07  541.53   49.84  540.79
   75.58  528.74   89.65     530   94.45     530  151.11     528  155.83  526.59
  178.93  518.13  199.84  510.97  204.76     506  219.12     504  233.45   502.5
  273.64  500.16  310.17  498.74  354.44  496.67   381.7  496.43  403.99  499.42
  417.06     506  426.31  511.48  480.12  528.44  521.55  527.98  548.48  528.51
  612.61  529.11  668.49     530  741.89  533.35  768.68  541.07  826.42  542.92
#Mann= 3 ,-1,0
       0     .06       0  151.11    .035       0  480.12     .06       0
Bank Sta=151.11,480.12
XS Rating Curve= 0 ,0
Exp/Cntr=0.3,0.1

Type RM Length L Ch R = 1 ,247071  ,313,313,293
BEGIN DESCRIPTION:
This cross section corresponds to cross section 246949.8 of the non-georeferenced CDC model which was the source of this model.
Effective flow limit in LOB set at North Main Levee.
Effective flow limit in ROB set at West Fork Levee Loop.
END DESCRIPTION:
XS GIS Cut Line= 2
 2325547.3947511 6965233.7495402 2326080.9254337 6966068.6902409
#Sta/Elev= 30
       0     542    5.56     542    56.5  538.95    94.1  528.18  130.66  525.68
  204.98  526.34  221.93  526.14  297.19  526.19  329.86  526.91  350.36  527.82
  376.52  516.78  399.26     506  413.28  500.96  441.13  499.81  489.73  498.63
  515.44  497.73  568.98  497.47  588.04  498.52  608.58     506  616.43  510.08
  643.33  517.08  667.17  525.76  720.04  525.75     842     528  877.71     530
  892.62  531.23  907.69  532.89  934.14  541.44  956.18   542.4  990.85  542.32
#Mann= 3 ,-1,0
       0     .06       0  350.36    .035       0  667.17     .06       0
#XS Ineff= 2 , 0
       0                  956.18       0     550
Permanent Ineff=
       F       T
Bank Sta=350.36,667.17
XS Rating Curve= 0 ,0
Exp/Cntr=0.3,0.1

Type RM Length L Ch R = 1 ,246758  ,102,102,109
BEGIN DESCRIPTION:
This cross section corresponds to cross section 246637.1 of the non-georeferenced CDC model which was the source of this model.
Effective flow limit in LOB set at North Main Levee.
Effective flow limit in ROB set at West Fork Levee Loop.
END DESCRIPTION:
XS GIS Cut Line= 2
 2325201.8916138 6965295.3468469 2325817.1882323 6966217.0152332
#Sta/Elev= 30
       0     542   47.89  540.31   65.16  540.42  101.96  527.89  149.38     526
  207.47  524.23  252.78  523.79  310.06     524  453.48  525.78  464.51  522.64
  475.03  521.89  502.49  510.21  508.44     506  514.78     504  531.69  500.26
  573.65   500.1  691.94  496.94  717.77   497.3  729.89     502  737.01  505.39
  744.61     508   760.9   515.4  784.53     518  799.25   522.9  827.98  529.13
  971.51     530 1030.46  531.57  1031.7  531.67 1059.58  542.61 1108.18  542.01
#Mann= 3 ,-1,0
       0     .06       0  453.48    .035       0  827.98     .06       0
#XS Ineff= 2 , 0
       0                 1059.58       0     550
Permanent Ineff=
       F       T
Bank Sta=453.48,827.98
XS Rating Curve= 0 ,0
Exp/Cntr=0.3,0.1