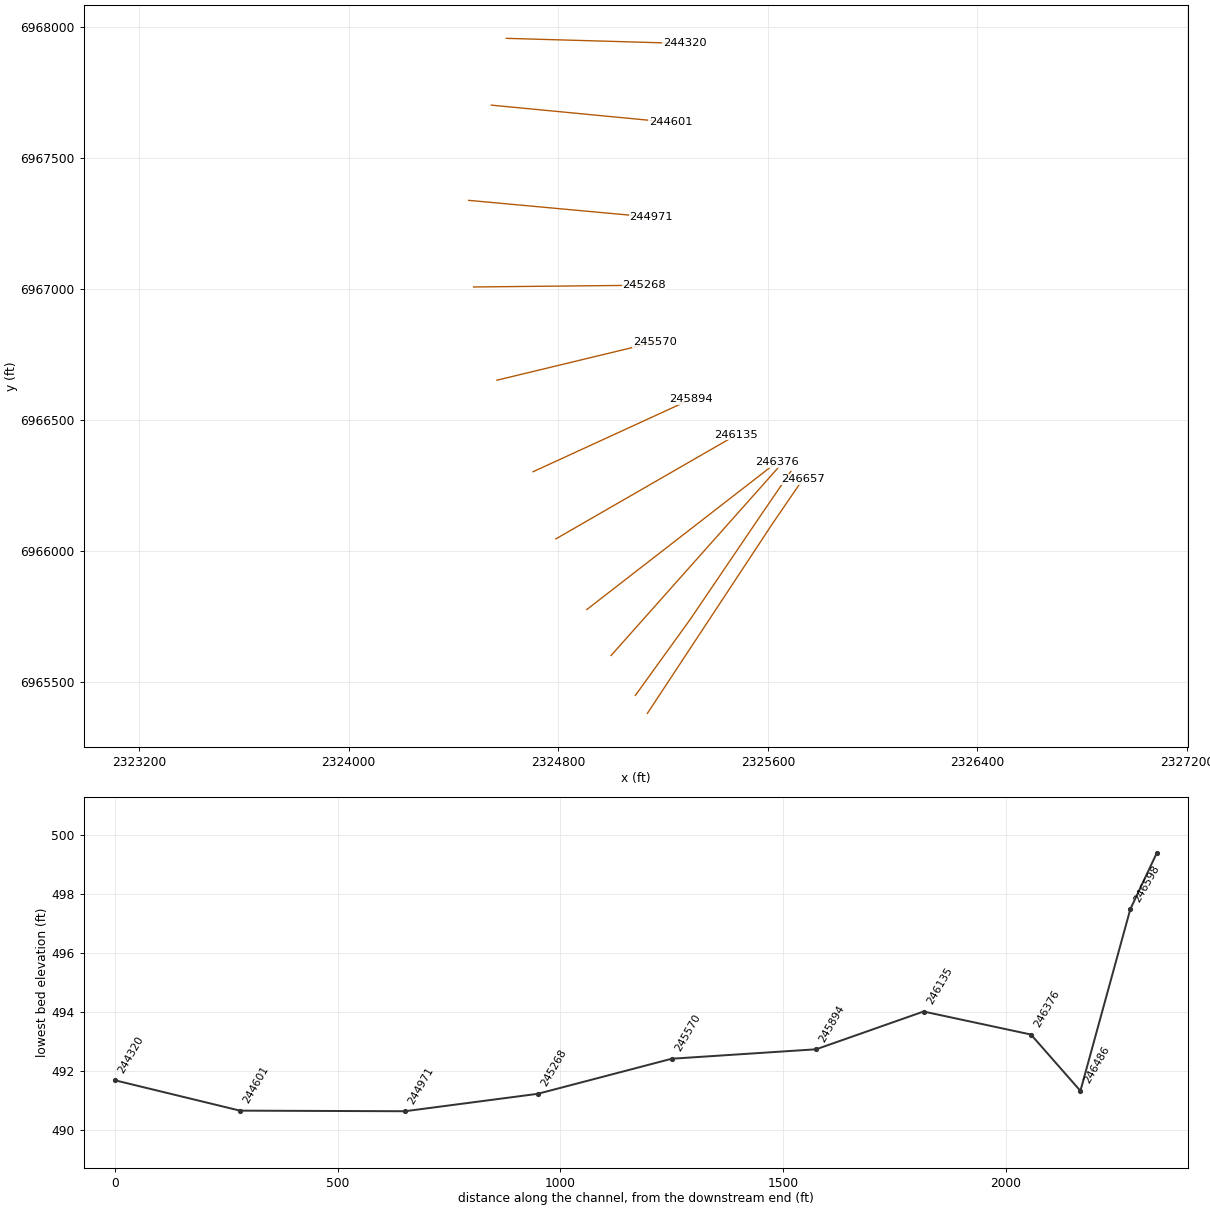
HEC-RAS study CDC_Consolidated_Model.prj: Upper Trinity CDC Consolidated Model

--- CDC_Consolidated_Model.g03 (geometry) --- (continued)

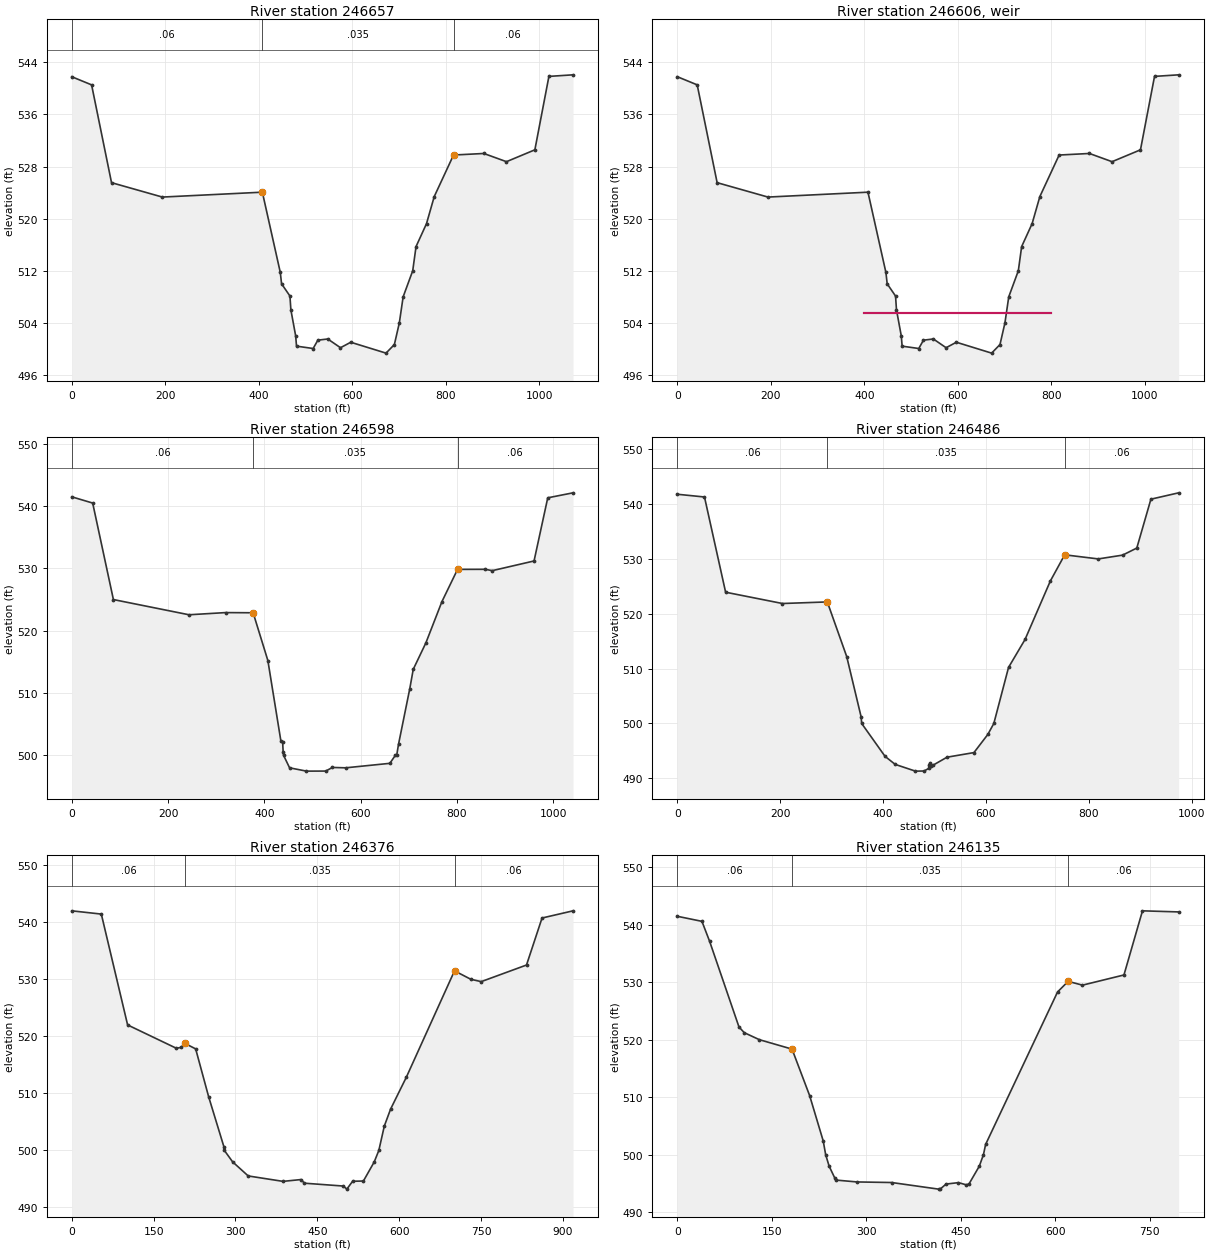
Type RM Length L Ch R = 1 ,246657  ,59,59,49
BEGIN DESCRIPTION:
This cross section corresponds to cross section 246535.4 of the non-georeferenced CDC model which was the source of this model.
Upstream of TRWD Dam.
Effective flow limit in LOB set at North Main Levee.
Effective flow limit in ROB set at West Fork Levee Loop.
END DESCRIPTION:
XS GIS Cut Line= 3
 2325140.1972085 6965380.0140725 2325616.7740735 6966102.7486318
 2325733.4444154 6966273.1603714
#Sta/Elev= 30
       0  541.78   42.49  540.53   85.11  525.52  193.81  523.31  407.73  524.06
  446.12  511.74  448.83     510  466.73  508.12  468.74     506  479.01     502
  480.81  500.43  516.39  500.07  526.45  501.35  547.64  501.53  574.86  500.19
  596.82  501.03  672.26  499.36  690.14  500.68  700.71     504  708.88     508
  729.36     512  736.45  515.71  758.83  519.23  775.41  523.39  816.63  529.76
  881.45     530  929.86  528.74  990.61  530.56 1020.67  541.83 1072.24  542.07
#Mann= 3 ,-1,0
       0     .06       0  407.73    .035       0  816.63     .06       0
#XS Ineff= 1 ,-1
  407.73  816.63   505.5
Permanent Ineff=
       T
Bank Sta=407.73,816.63
XS Rating Curve= 0 ,0
Exp/Cntr=0.3,0.1

Type RM Length L Ch R = 5 ,246606  ,,,
BEGIN DESCRIPTION:
TRWD Dam
Constructed by TRWD.  Data from TRWD plans.  Top of dam road surface elevation 505.5
END DESCRIPTION:
Node Name=TRWD Dam
IW Pilot Flow=0
#Inline Weir SE= 2
     400  505.54     800  505.54
IW Dist,WD,Coef,Skew,MaxSub,Min_El,Is_Ogee,SpillHt,DesHd
18.9,15,3,0,0.95,, 0 ,,,1.33,1.33,
Inline Weir Flap Gates= 0
IW Outlet Rating Curve= 0 ,False,,

Type RM Length L Ch R = 1 ,246598  ,112,112,52
BEGIN DESCRIPTION:
This cross section corresponds to cross section 246476.7 of the non-georeferenced CDC model which was the source of this model.
Downstream of TRWD Dam.
Effective flow limit in LOB set at North Main Levee.
Effective flow limit in ROB set at West Fork Levee Loop.
END DESCRIPTION:
XS GIS Cut Line= 4
 2325094.3235169 6965448.5892528 2325305.2015044 6965740.8978039
 2325570.5800474 6966132.4652001 2325687.8386847 6966303.7363073
#Sta/Elev= 30
       0  541.47    43.5  540.47   86.53  524.99  243.59  522.55  319.53   522.9
  376.72  522.87  407.31  515.21   434.5  502.23  437.97  502.16  439.11  500.47
  439.94     500   452.4     498  487.47  497.47  527.45  497.48   541.4  498.06
  568.74     498  660.63  498.72  672.01     500  674.83     500  678.63  501.78
  702.03   510.7  709.21   513.8  735.44  518.04  768.78  524.66  801.21  529.83
  858.37  529.84  873.53  529.63  960.07  531.18  988.53  541.31 1041.02  542.11
#Mann= 3 ,-1,0
       0     .06       0  376.72    .035       0  801.21     .06       0
Bank Sta=376.72,801.21
XS Rating Curve= 0 ,0
Exp/Cntr=0.3,0.1

Type RM Length L Ch R = 1 ,246486  ,111,111,34
BEGIN DESCRIPTION:
This cross section corresponds to cross section 246365.1 of the non-georeferenced CDC model which was the source of this model.
Upstream of Sump 26 outfall.
Effective flow limit in LOB set at North Main Levee.
Effective flow limit in ROB set at West Fork Levee Loop.
END DESCRIPTION:
XS GIS Cut Line= 2
 2325001.7946782 6965601.0935022 2325649.7397491 6966329.2794523
#Sta/Elev= 30
       0  541.79   52.79  541.29   93.86  523.93  204.45  521.87  291.61  522.16
  329.31   512.2  357.37   501.2  358.42     500   403.9     494  423.58  492.54
  462.86  491.31  479.86  491.33  488.74  491.81  489.03  492.41  490.92  492.73
  492.51  492.26  496.93  492.38  524.37  493.85  576.73  494.69  603.73     498
  615.39     500     644  510.22  676.06  515.31   725.3  525.98  753.16  530.75
  818.42     530  865.72  530.69  893.37  531.98   920.8  540.89  974.72  542.05
#Mann= 3 ,-1,0
       0     .06       0  291.61    .035       0  753.16     .06       0
Bank Sta=291.61,753.16
XS Rating Curve= 0 ,0
Exp/Cntr=0.3,0.1

Type RM Length L Ch R = 1 ,246376  ,241,241,175
BEGIN DESCRIPTION:
This cross section corresponds to cross section 246254.2 of the non-georeferenced CDC model which was the source of this model.
Downstream of Sump 26 outfall.
Effective flow limit in LOB set at North Main Levee.
Effective flow limit in ROB set at West Fork Levee Loop.
END DESCRIPTION:
XS GIS Cut Line= 2
 2324909.0415665 6965776.3107781 2325634.9793413 6966339.1753387
#Sta/Elev= 30
       0     542   54.21  541.43   102.4     522  191.93   517.9  200.33  518.07
  207.68  518.75   227.1   517.8  250.86  509.42   278.8  500.66  279.57  500.02
  294.83     498  323.39  495.53  387.15  494.58  420.27   494.9  426.33  494.26
  497.75  493.76  504.08  493.22  514.75   494.6  534.47  494.64  554.36     498
  562.74     500  572.78  504.27   584.3  507.25  613.08  512.82  701.42  531.48
  731.35     530  750.37  529.59  833.34   532.5  861.82  540.74  918.59     542
#Mann= 3 ,-1,0
       0     .06       0  207.68    .035       0  701.42     .06       0
Bank Sta=207.68,701.42
XS Rating Curve= 0 ,0
Exp/Cntr=0.3,0.1

Type RM Length L Ch R = 1 ,246135  ,241,241,203
BEGIN DESCRIPTION:
This cross section corresponds to cross section 246013.2 of the non-georeferenced CDC model which was the source of this model.
Effective flow limit in LOB set at North Main Levee.
Effective flow limit in ROB set at West Fork Levee Loop.
END DESCRIPTION:
XS GIS Cut Line= 2
 2324790.7810898 6966045.9121363 2325480.1080389 6966443.0074095
#Sta/Elev= 30
       0  541.47   39.03  540.59   51.24  537.11   97.83  522.21  106.21  521.22
  130.19     520  182.02  518.36  209.92  510.28  231.51  502.38  235.38     500
  240.85     498  249.55     496  252.18  495.57  285.19  495.25  340.11  495.15
  414.57     494  417.04     494  426.47  494.88     446  495.13  458.53  494.75
  462.83   494.9  479.23     498  485.79     500  489.22  501.78  603.42  528.31
  620.19  530.15  642.95  529.49  708.74  531.26  738.14  542.42  795.52  542.23
#Mann= 3 ,-1,0
       0     .06       0  182.02    .035       0  620.19     .06       0
Bank Sta=182.02,620.19
XS Rating Curve= 0 ,0
Exp/Cntr=0.3,0.1

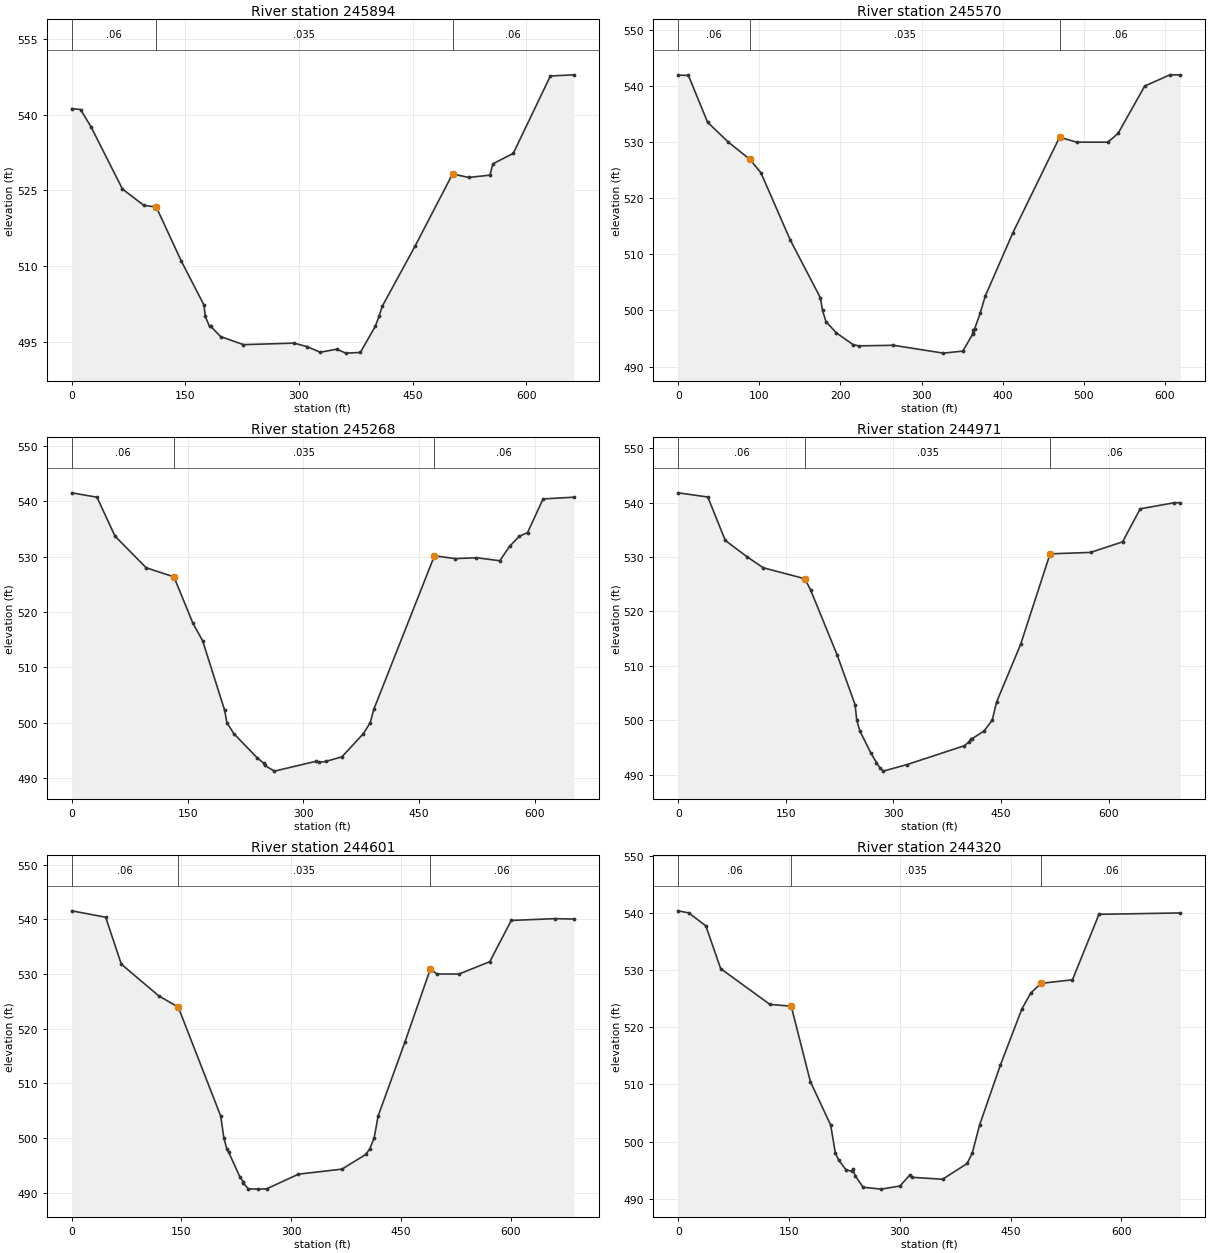
Type RM Length L Ch R = 1 ,245894  ,324,324,250
BEGIN DESCRIPTION:
This cross section corresponds to cross section 245772.4 of the non-georeferenced CDC model which was the source of this model.
Effective flow limit in LOB set at North Main Levee.
Effective flow limit in ROB set at West Fork Levee Loop.
Located at TRWD office (in LOB).
END DESCRIPTION:
XS GIS Cut Line= 2
 2324703.7610714 6966302.2494937 2325306.2673848  6966578.743424
#Sta/Elev= 30
       0   541.2   11.63     541   25.31   537.6   66.94  525.24   95.22     522
  111.58  521.68  144.58  510.98  174.56  502.25  176.31     500  181.87     498
   183.6     498   196.6     496  226.73   494.4  293.39   494.7  310.57  494.02
  328.04   492.9     350   493.5  361.77  492.72  381.02  492.85  400.61     498
  405.72     500  409.93     502  453.13  513.89   502.8  528.24  524.04  527.54
  552.18     528  556.04  530.25  582.93  532.31  631.92  547.65  662.92  547.88
#Mann= 3 ,-1,0
       0     .06       0  111.58    .035       0   502.8     .06       0
Bank Sta=111.58,502.8
XS Rating Curve= 0 ,0
Exp/Cntr=0.3,0.1

Type RM Length L Ch R = 1 ,245570  ,301,301,219
BEGIN DESCRIPTION:
This cross section corresponds to cross section 245448.4 of the non-georeferenced CDC model which was the source of this model.
Effective flow limit in LOB set at North Main Levee.
Effective flow limit in ROB set at West Fork Levee Loop.
END DESCRIPTION:
XS GIS Cut Line= 2
 2324566.2523924  6966651.683632 2325168.1076657 6966796.7396826
#Sta/Elev= 30
       0  541.95   12.53  541.89   36.18  533.55   61.84     530   88.36  526.93
  101.95  524.55  138.13  512.56  175.35  502.25   177.9     500  182.22     498
  195.08     496  215.58  493.92   222.6  493.69  265.36   493.8  326.81   492.4
  350.81  492.76  363.06  495.77  363.89     496  363.95   496.6  365.33  496.68
  372.26  499.49  378.51  502.54  412.74  513.89  470.25  530.89  491.19     530
  529.81     530  542.34  531.56  575.19     540  606.24     542  619.09     542
#Mann= 3 ,-1,0
       0     .06       0   88.36    .035       0  470.25     .06       0
Bank Sta=88.36,470.25
XS Rating Curve= 0 ,0
Exp/Cntr=0.3,0.1

Type RM Length L Ch R = 1 ,245268  ,298,298,257
BEGIN DESCRIPTION:
This cross section corresponds to cross section 245146.9 of the non-georeferenced CDC model which was the source of this model.
Effective flow limit in LOB set at North Main Levee.
Effective flow limit in ROB set at West Fork Levee Loop.
END DESCRIPTION:
XS GIS Cut Line= 2
 2324476.8902114 6967007.4482338 2325127.1114593 6967014.1660543
#Sta/Elev= 30
       0  541.55   32.63  540.76   55.99  533.72   96.31     528  132.32  526.35
  156.78     518   169.5  514.78  197.85  502.28  200.89     500  209.85     498
  240.41  493.58  248.32  492.68  249.62  492.27  262.43  491.21  316.72     493
  320.51   492.8  329.32  492.98  349.92   493.8  377.71     498  386.62     500
   391.1  502.36  469.68  530.16  496.82  529.65  524.11  529.81  554.39  529.27
  567.19   531.9  579.54  533.68  590.39  534.37  610.38  540.45  650.26  540.76
#Mann= 3 ,-1,0
       0     .06       0  132.32    .035       0  469.68     .06       0
Bank Sta=132.32,469.68
XS Rating Curve= 0 ,0
Exp/Cntr=0.3,0.1

Type RM Length L Ch R = 1 ,244971  ,370,370,366
BEGIN DESCRIPTION:
This cross section corresponds to cross section 244849.2 of the non-georeferenced CDC model which was the source of this model.
Effective flow limit in LOB set at North Main Levee.
Effective flow limit in ROB set at West Fork Levee Loop.
END DESCRIPTION:
XS GIS Cut Line= 2
  2324457.764387 6967338.0639185 2325154.7931061 6967274.0295545
#Sta/Elev= 30
       0  541.78   41.25  541.01   65.58  533.03   96.19     530  118.58     528
  176.48  525.99  184.56  523.92  221.48     512  246.53  502.84   248.9     500
  253.23     498  268.37     494  276.27   492.2   281.2  491.24  285.75  490.62
  319.06  491.83  398.94  495.29  405.16     496   408.6   496.6  409.35  496.56
  426.46     498  437.77     500  443.71  503.29  477.26   513.9  518.39  530.56
  574.96  530.83   619.4  532.76  644.03  538.84   691.6  539.96  699.96  539.96
#Mann= 3 ,-1,0
       0     .06       0  176.48    .035       0  518.39     .06       0
Bank Sta=176.48,518.39
XS Rating Curve= 0 ,0
Exp/Cntr=0.3,0.1

Type RM Length L Ch R = 1 ,244601  ,281,281,305
BEGIN DESCRIPTION:
This cross section corresponds to cross section 244479.4 of the non-georeferenced CDC model which was the source of this model.
Effective flow limit in LOB set at North Main Levee.
Effective flow limit in ROB set at West Fork Levee Loop.
END DESCRIPTION:
XS GIS Cut Line= 2
 2324544.6888625 6967701.4609341 2325227.9814406 6967635.8981427
#Sta/Elev= 30
       0  541.56   46.32  540.39   67.77   531.8  118.93     526  144.84     524
  146.07  523.78  203.75  503.97  207.92     500  211.97     498  214.52  497.41
   229.9  492.85  234.48     492  234.77   491.7   241.5  490.69  255.06  490.64
  266.38  490.69  309.94  493.38   369.5   494.3     402     497  407.38     498
  413.39     500  418.92  504.05  455.43  517.53  490.41  530.98  498.99     530
   529.6     530  571.54  532.26  600.81   539.8   660.4  540.13  686.43  540.05
#Mann= 3 ,-1,0
       0     .06       0  144.84    .035       0  490.41     .06       0
Bank Sta=144.84,490.41
XS Rating Curve= 0 ,0
Exp/Cntr=0.5,0.3

Type RM Length L Ch R = 1 ,244320  ,128,128,128
BEGIN DESCRIPTION:
This cross section corresponds to cross section 244198.7 of the non-georeferenced CDC model which was the source of this model.
Upstream of Northside Drive.
Effective flow limit in LOB set at North Main Levee.
Effective flow limit in ROB set at West Fork Levee Loop.
END DESCRIPTION:
XS GIS Cut Line= 2
  2324602.057261 6967956.4237439 2325281.6464817 6967936.8431508
#Sta/Elev= 30
       0  540.37    14.4     540   37.38  537.74   57.49  530.25  124.09     524
  152.99  523.68  178.93  510.48  206.43  502.88  212.73     498   217.1   496.8
  227.33  495.03  235.21   494.8  236.29  495.22  239.68     494  250.36     492
  274.67  491.67  300.27  492.22  313.93  494.19  316.47  493.74  357.98   493.4
  391.24  496.16   398.2     498  408.11  502.92  436.27  513.39  465.33  523.21
  477.44     526  491.28  527.68  533.83   528.3  569.72  539.76  679.87     540
#Mann= 3 ,-1,0
       0     .06       0  152.99    .035       0  491.28     .06       0
Bank Sta=152.99,491.28
XS Rating Curve= 0 ,0
Exp/Cntr=0.5,0.3