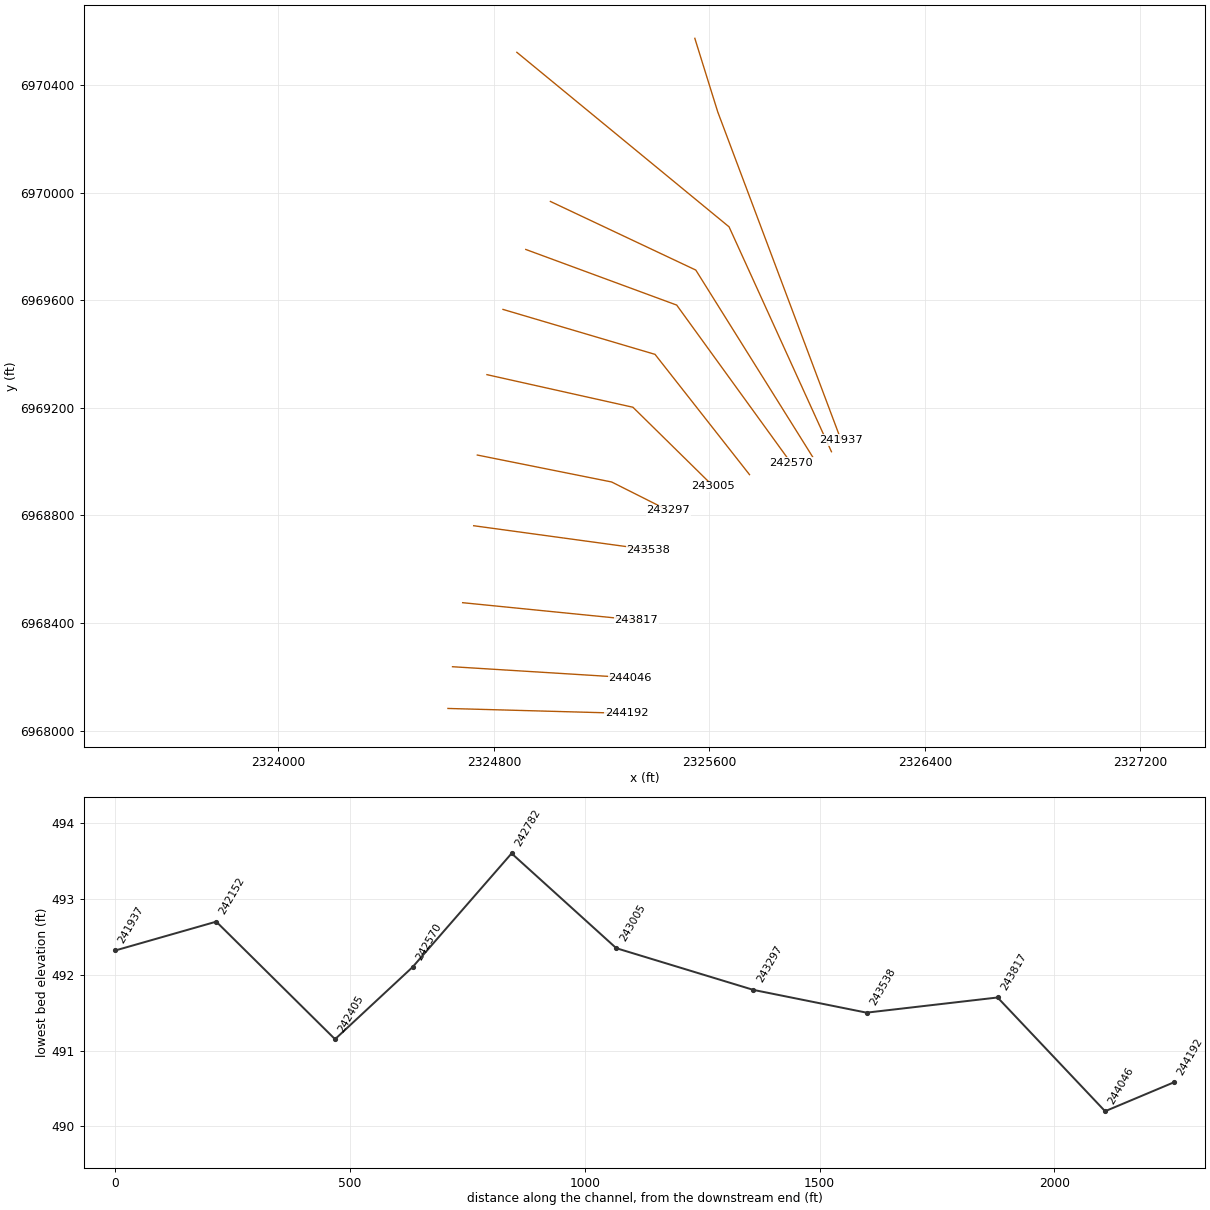
HEC-RAS study CDC_Consolidated_Model.prj: Upper Trinity CDC Consolidated Model

--- CDC_Consolidated_Model.g03 (geometry) --- (continued)

Type RM Length L Ch R = 3 ,244224  ,,,
BEGIN DESCRIPTION:
Northside Drive
Bridge length 504 feet.
Data from USACE 1975 survey.
END DESCRIPTION:
Node Name=Northside Drive
Bridge Culvert--1,0,-1,-1, 0
Deck Dist Width WeirC Skew NumUp NumDn MinLoCord MaxHiCord MaxSubmerge Is_Ogee
38.8,63,2.6,0, 6, 6, , , 0.95, 0, 0,0,,
       0    44.5    44.5   548.3   548.3  679.87
     542     542     545     545     542     542
     450     450  538.31  538.29     450     450
       0    44.5    44.5   548.3   548.3  664.36
     542     542     545     545     542     542
     450     450  538.31  538.29     450     450
Pier Skew, UpSta & Num, DnSta & Num=  ,101.5, 2 ,101.5, 2 , 0 , 0 , 0 ,,
       3       3
     400     540
       3       3
     400     540
Pier Skew, UpSta & Num, DnSta & Num=  ,161.5, 2 ,161.5, 2 , 0 , 0 , 0 ,,
       3       3
     400     540
       3       3
     400     540
Pier Skew, UpSta & Num, DnSta & Num=  ,226.5, 2 ,226.5, 2 , 0 , 0 , 0 ,,
       3       3
     400     540
       3       3
     400     540
Pier Skew, UpSta & Num, DnSta & Num=  ,311.5, 2 ,311.5, 2 , 0 , 0 , 0 ,,
       3       3
     400     540
       3       3
     400     540
Pier Skew, UpSta & Num, DnSta & Num=  ,379.5, 2 ,379.5, 2 , 0 , 0 , 0 ,,
       3       3
     400     540
       3       3
     400     540
Pier Skew, UpSta & Num, DnSta & Num=  ,436.5, 2 ,436.5, 2 , 0 , 0 , 0 ,,
       3       3
     400     540
       3       3
     400     540
Pier Skew, UpSta & Num, DnSta & Num=  ,490.5, 2 ,490.534, 2 , 0 , 0 , 0 ,,
       3       3
     400     540
       3       3
     400     540
BR Coef=-1 , 0 , 0 ,, 0 ,,,0.8,-1,,0,
WSPro=,,,, 1 ,,,, 0 ,,,, 0 ,,,,-1 ,-1 ,-1 , 0 , 0 , 0 , 0 , 0
BC Design=,, 0 ,, 0 ,,,,,,
BC Use User HTab Curves=0
BC User HTab FreeFlow(D)= 0

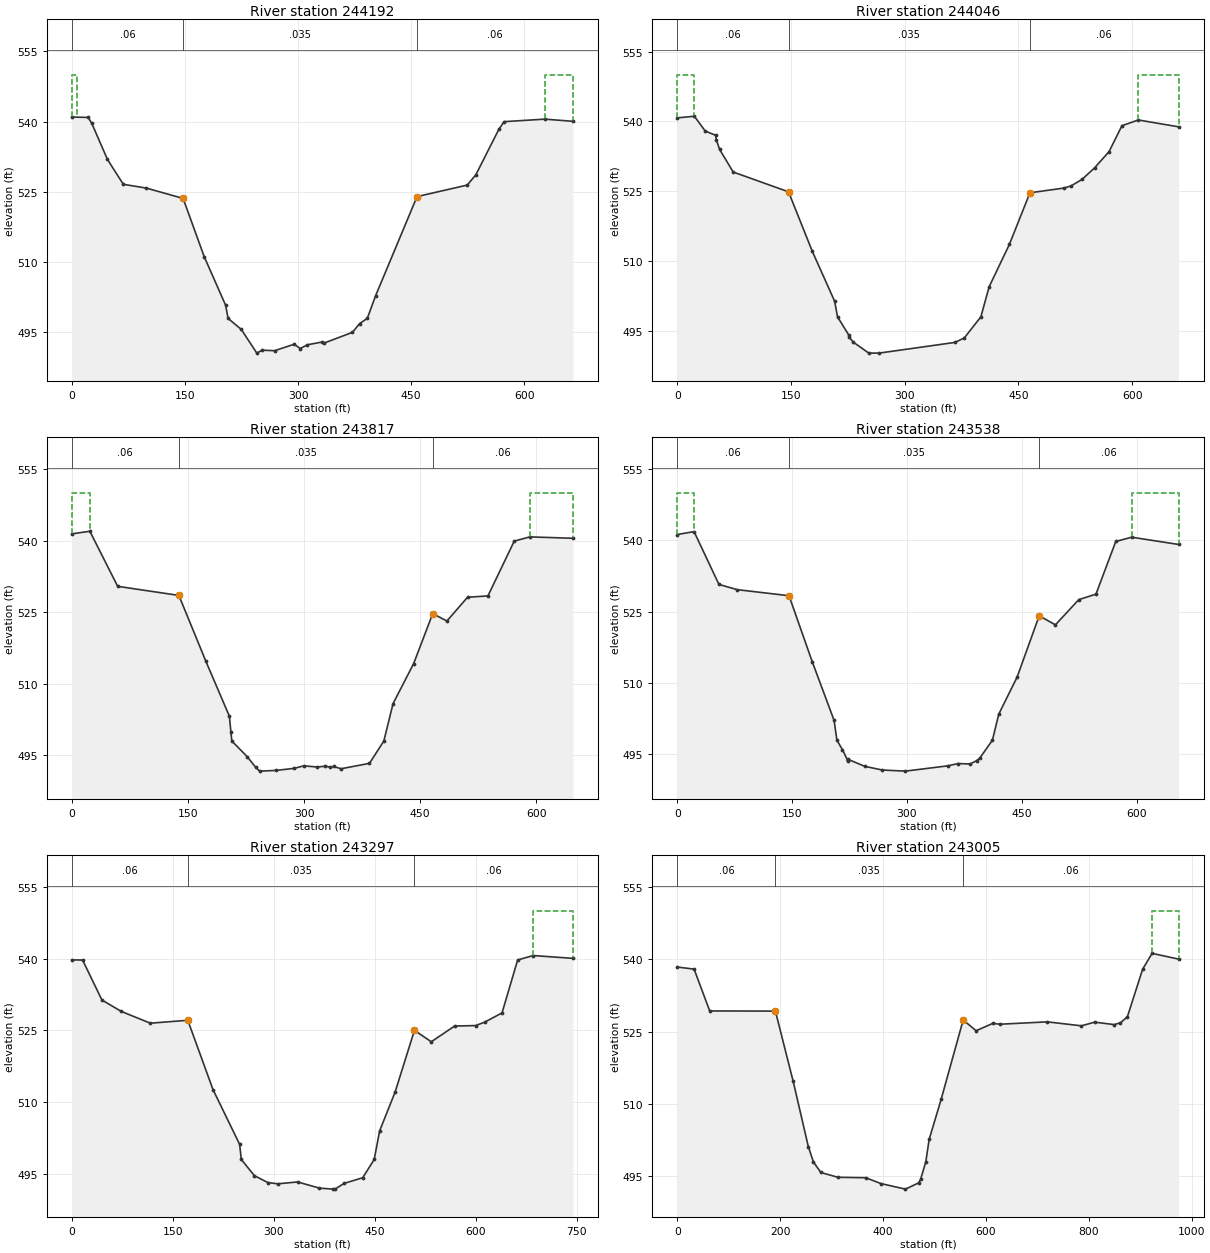
Type RM Length L Ch R = 1 ,244192  ,146,146,135
BEGIN DESCRIPTION:
This cross section corresponds to cross section 244071 of the non-georeferenced CDC model which was the source of this model.
Downstream of Northside Drive.
Effective flow limit in LOB set at North Main Levee.
Effective flow limit in ROB set at West Fork Levee Loop.
END DESCRIPTION:
XS GIS Cut Line= 2
 2324629.3196599 6968082.1646992 2325293.4270395 6968063.8568881
#Sta/Elev= 30
       0  540.99   21.78   540.9   26.57  539.64   47.37  531.93    68.4  526.62
   98.58  525.83  147.65  523.61  175.53   511.2  203.95  500.81  207.23     498
  224.72  495.64  245.36  490.58   252.2  491.21  268.95   491.1  294.88  492.48
   302.9  491.56  312.36  492.36  331.39  492.94  334.27  492.71   372.1  495.02
  381.64   496.9  391.76     498  402.66  502.79  457.68     524  524.22  526.46
  535.63  528.66  566.39  538.45   573.2     540  627.03  540.54  664.36  540.07
#Mann= 3 ,-1,0
       0     .06       0  147.65    .035       0  457.68     .06       0
#XS Ineff= 2 , 0
       0    6.54     550  627.03       0     550
Permanent Ineff=
       T       T
Bank Sta=147.65,457.68
XS Rating Curve= 0 ,0
Exp/Cntr=0.5,0.3

Type RM Length L Ch R = 1 ,244046  ,229,229,216
BEGIN DESCRIPTION:
This cross section corresponds to cross section 243924.9 of the non-georeferenced CDC model which was the source of this model.
Effective flow limit in LOB set at North Main Levee.
Effective flow limit in ROB set at West Fork Levee Loop.
END DESCRIPTION:
XS GIS Cut Line= 2
 2324646.3491146 6968237.2406994 2325306.1689898 6968196.3668708
#Sta/Elev= 30
       0  540.75   22.56   541.1    36.9  537.91   50.47  537.02   51.58     536
   55.74     534   73.79  529.11  146.73  524.86  178.08  512.07  207.59  501.33
  211.34     498   226.5     494  226.91  493.62     232  492.58  252.43  490.22
  265.84   490.2  366.12   492.5  378.61  493.47  400.41     498  411.37  504.48
  437.98  513.55  465.12  524.65  509.54  525.66  518.97   526.1  533.69  527.51
  550.34     530  569.53  533.51  586.44  539.06  608.07   540.3  661.08  538.83
#Mann= 3 ,-1,0
       0     .06       0  146.73    .035       0  465.12     .06       0
#XS Ineff= 2 , 0
       0   22.56     550  608.07       0     550
Permanent Ineff=
       T       T
Bank Sta=146.73,465.12
XS Rating Curve= 0 ,0
Exp/Cntr=0.3,0.1

Type RM Length L Ch R = 1 ,243817  ,279,279,265
BEGIN DESCRIPTION:
This cross section corresponds to cross section 243695.5 of the non-georeferenced CDC model which was the source of this model.
Effective flow limit in LOB set at North Main Levee.
Effective flow limit in ROB set at West Fork Levee Loop.
END DESCRIPTION:
XS GIS Cut Line= 2
 2324683.9805771 6968475.3114704 2325328.1373779 6968410.8958421
#Sta/Elev= 30
       0   541.4    23.4  541.95   59.35  530.41  138.37  528.51  173.26  514.71
  203.64  503.19  205.52     500   206.8     498  226.45  494.76  237.61  492.49
  242.73   491.7  264.06  491.85  287.27  492.28  299.62   492.8  316.98  492.57
  327.62  492.73  334.13  492.53   338.3  492.67  347.83   492.2  384.56  493.33
  403.08     498  415.02  505.85  441.64  514.24  466.25   524.7  484.54  523.14
  511.23  528.13  537.53   528.4  571.51  539.88  591.57  540.77  647.37  540.48
#Mann= 3 ,-1,0
       0     .06       0  138.37    .035       0  466.25     .06       0
#XS Ineff= 2 , 0
       0    23.4     550  591.57       0     550
Permanent Ineff=
       T       T
Bank Sta=138.37,466.25
XS Rating Curve= 0 ,0
Exp/Cntr=0.3,0.1

Type RM Length L Ch R = 1 ,243538  ,241,241,207
BEGIN DESCRIPTION:
This cross section corresponds to cross section 243416.7 of the non-georeferenced CDC model which was the source of this model.
Effective flow limit in LOB set at North Main Levee.
Effective flow limit in ROB set at West Fork Levee Loop.
END DESCRIPTION:
XS GIS Cut Line= 2
 2324724.9568193 6968761.4005278 2325373.6400467 6968672.6555515
#Sta/Elev= 30
       0  541.23   21.92  541.85   54.42  530.75    78.1  529.65  145.97  528.37
   176.2  514.54  204.84  502.16  208.52     498  215.77     496   222.4   493.8
  222.48   493.6   222.8     494  245.03   492.5  267.96  491.73     298   491.5
  353.25  492.61  366.93  493.09  382.37     493  390.92  493.69  395.17  494.25
  411.65     498  419.94  503.48  443.97  511.29  472.74  524.15  493.91  522.25
  524.48  527.55   546.9   528.7  572.78  539.78  593.67  540.67  654.73  539.15
#Mann= 3 ,-1,0
       0     .06       0  145.97    .035       0  472.74     .06       0
#XS Ineff= 2 , 0
       0   21.92     550  593.67       0     550
Permanent Ineff=
       T       T
Bank Sta=145.97,472.74
XS Rating Curve= 0 ,0
Exp/Cntr=0.3,0.1

Type RM Length L Ch R = 1 ,243297  ,292,292,276
BEGIN DESCRIPTION:
This cross section corresponds to cross section 243175.6 of the non-georeferenced CDC model which was the source of this model.
Effective flow limit in LOB set at North Main Levee.
Effective flow limit in ROB set at West Fork Levee Loop.
END DESCRIPTION:
XS GIS Cut Line= 3
  2324738.376515 6969024.1471682  2325237.112854 6968924.0546236
  2325447.792496 6968818.0839212
#Sta/Elev= 30
       0  539.74   16.12  539.71   44.84  531.35   73.67  528.96  116.74   526.5
  172.41  527.11  209.85  512.61   249.4  501.16  251.89     498  271.27  494.62
  291.39  493.17  305.94  492.91  335.46   493.3  367.95  492.01  388.33   491.8
  391.29  491.82  404.71  493.01  432.21  494.18  449.26     498  457.34  503.98
  480.37  512.11  509.01  524.99   534.1  522.62  568.79  525.91  599.87     526
  613.33  526.72  639.13  528.65  662.36  539.72   685.3  540.65  744.51  540.06
#Mann= 3 ,-1,0
       0     .06       0  172.41    .035       0  509.01     .06       0
#XS Ineff= 2 , 0
       0                   685.3       0     550
Permanent Ineff=
       F       T
Bank Sta=172.41,509.01
XS Rating Curve= 0 ,0
Exp/Cntr=0.3,0.1

Type RM Length L Ch R = 1 ,243005  ,223,223,195
BEGIN DESCRIPTION:
This cross section corresponds to cross section 242883.7 of the non-georeferenced CDC model which was the source of this model.
Effective flow limit in LOB set at North Main Levee.
Effective flow limit in ROB set at West Fork Levee Loop.
END DESCRIPTION:
XS GIS Cut Line= 3
 2324774.1838468 6969322.9528966 2325316.3447638  6969201.807724
 2325614.9089773 6968907.8875182
#Sta/Elev= 30
       0  538.36   32.73  537.92   63.08  529.26  190.77  529.23  225.29   514.7
  254.85  501.13  264.62     498  279.06   495.8  312.35   494.8  366.44  494.71
  395.95   493.5  443.62  492.35  469.17  493.64  473.02  494.37   483.2     498
  489.67  502.64   513.1  510.98  555.84  527.39  581.01  525.16  613.54  526.69
  627.22  526.51   719.3     527  785.84  526.18  811.41  526.94  849.54  526.43
  861.64  526.81  875.11  528.06   904.8  537.92  923.14  541.19  974.49     540
#Mann= 3 ,-1,0
       0     .06       0  190.77    .035       0  555.84     .06       0
#XS Ineff= 2 , 0
       0                  923.14       0     550
Permanent Ineff=
       F       T
Bank Sta=190.77,555.84
XS Rating Curve= 0 ,0
Exp/Cntr=0.3,0.1

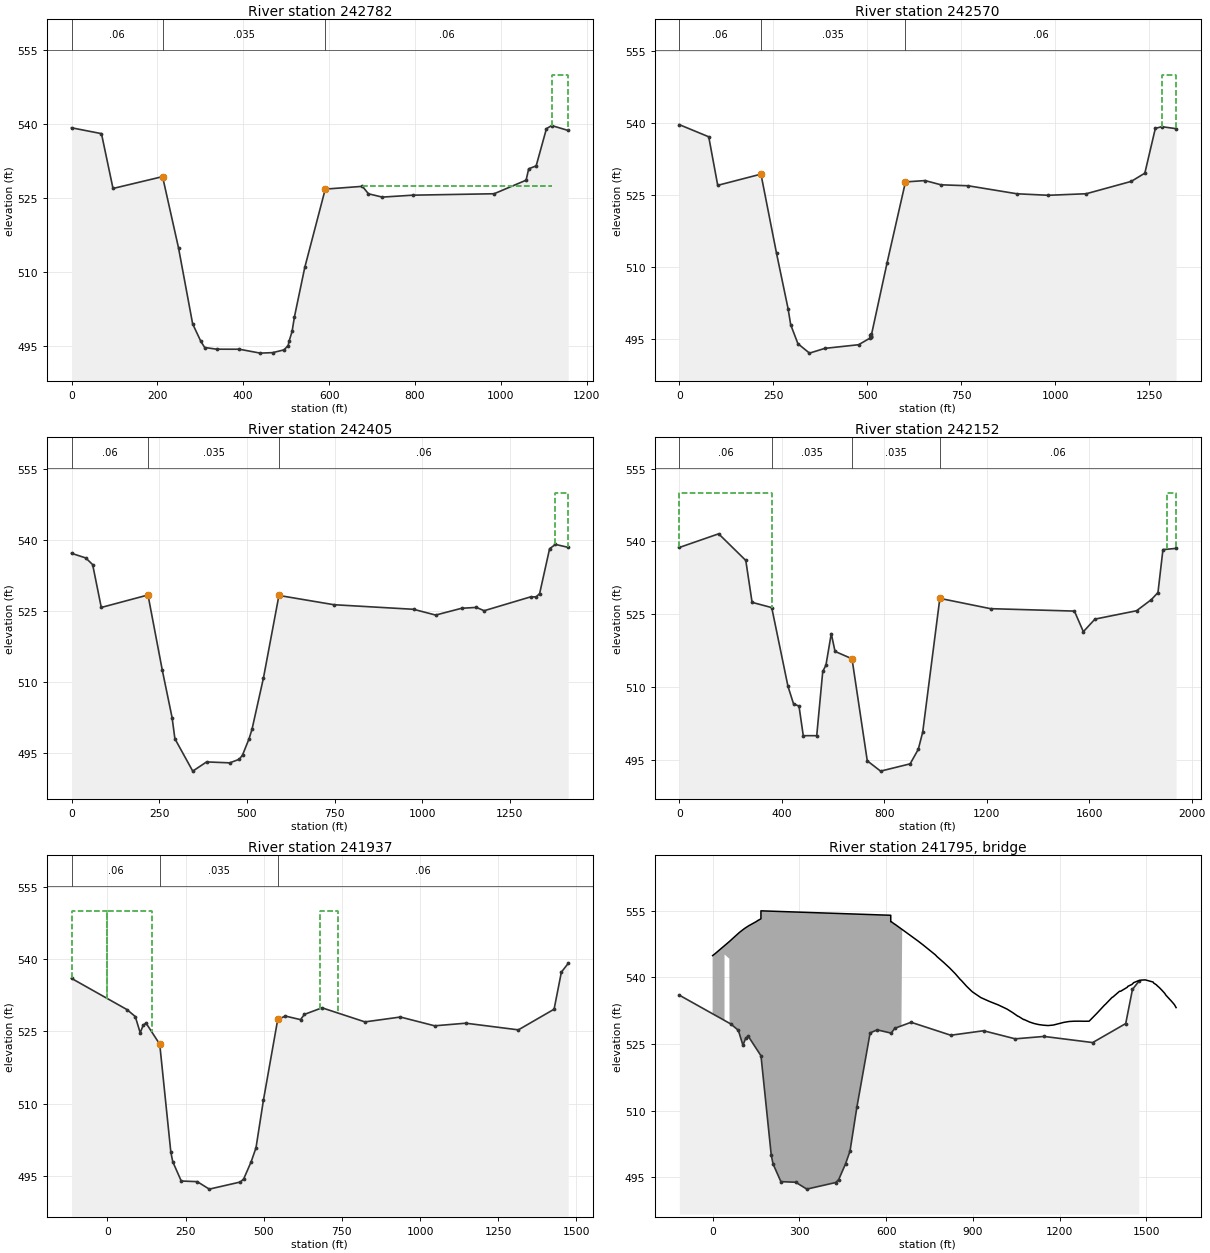
Type RM Length L Ch R = 1 ,242782  ,211,211,180
BEGIN DESCRIPTION:
This cross section corresponds to cross section 242660.3 of the non-georeferenced CDC model which was the source of this model.
Effective flow limit in LOB set at North Main Levee.
Effective flow limit in ROB set at West Fork Levee Loop.
END DESCRIPTION:
XS GIS Cut Line= 3
 2324833.7704744 6969565.4817751 2325398.2883033 6969398.4605774
 2325749.2296084 6968951.3139112
#Sta/Elev= 30
       0  539.27    69.8  538.08   96.69  526.97  212.14  529.37  249.28  514.93
  282.23  499.52  301.23     496  310.21  494.74  338.04   494.4   391.1  494.39
  439.59   493.6  468.62   493.7  495.05  494.26   504.7  495.14  506.78     496
  513.85     498  519.39  500.98  543.37  510.96  591.14  526.84  677.55   527.4
  691.76  525.89  723.94  525.22   794.9  525.61  984.51   525.9 1059.02  528.65
 1064.96  530.95 1082.43  531.55 1106.35  539.09 1118.59  539.72 1157.13  538.72
#Mann= 3 ,-1,0
       0     .06       0  212.14    .035       0  591.14     .06       0
#XS Ineff= 2 ,-1
 1118.59 1157.13     550  677.99 1118.59   527.4
Permanent Ineff=
       F       F
Bank Sta=212.14,591.14
XS Rating Curve= 0 ,0
Exp/Cntr=0.3,0.1

Type RM Length L Ch R = 1 ,242570  ,165,165,129
BEGIN DESCRIPTION:
This cross section corresponds to cross section 242448.8 of the non-georeferenced CDC model which was the source of this model.
Effective flow limit in LOB set at North Main Levee.
Effective flow limit in ROB set at West Fork Levee Loop.
END DESCRIPTION:
XS GIS Cut Line= 3
  2324918.416569 6969788.3596673 2325478.8146446 6969581.5717461
 2325903.5701745 6968994.5283466
#Sta/Elev= 30
       0  539.63   78.14  537.11  102.07  527.01  217.12  529.34  258.53  512.88
  289.32  501.34   296.3     498  315.49  494.06  346.27   492.1  387.18  493.09
  477.04  493.85  507.44  495.23  508.54  495.84  508.86  495.64  509.01     496
  509.23  495.53  509.76   495.4  552.82  510.91  601.73  527.72  653.75     528
  696.18  527.12  768.32  526.92  898.54  525.25  981.81  524.94 1082.75  525.26
 1202.58  527.83 1238.68  529.54  1266.7  538.86 1283.84  539.21 1321.93   538.8
#Mann= 3 ,-1,0
       0     .06       0  217.12    .035       0  601.73     .06       0
#XS Ineff= 2 ,-1
 1283.84 1321.93     550  653.75 1283.84     528
Permanent Ineff=
       F       F
Bank Sta=217.12,601.73
XS Rating Curve= 0 ,0
Exp/Cntr=0.3,0.1

Type RM Length L Ch R = 1 ,242405  ,253,253,162
BEGIN DESCRIPTION:
This cross section corresponds to cross section 242283.8 of the non-georeferenced CDC model which was the source of this model.
Effective flow limit in LOB set at North Main Levee.
Effective flow limit in ROB set at West Fork Levee Loop.
END DESCRIPTION:
XS GIS Cut Line= 3
 2325009.7904663 6969966.7920853 2325549.6986706 6969711.7667902
 2325983.8342588 6969017.0018028
#Sta/Elev= 30
       0  537.21   40.66  536.23    60.3  534.82   84.89  525.76  218.08   528.4
  218.71  528.16  258.85  512.51  286.81  502.47  294.81     498  345.72  491.15
  385.21   493.1  451.22   492.9  478.74  493.67  487.76  494.58  506.29     498
  514.68     500  547.37  510.87  591.46   528.3  748.24  526.34  975.32  525.37
 1038.33  524.15 1112.38  525.59 1154.68  525.77 1176.56  525.07 1309.03     528
 1325.13     528 1334.84  528.71 1363.19  538.18 1379.88  539.09 1416.36  538.47
#Mann= 3 ,-1,0
       0     .06       0  218.71    .035       0  591.46     .06       0
#XS Ineff= 2 ,-1
 1379.88 1416.36     550  608.69 1379.88     528
Permanent Ineff=
       F       F
Bank Sta=218.08,591.46
XS Rating Curve= 0 ,0
Exp/Cntr=0.3,0.1

Type RM Length L Ch R = 1 ,242152  ,215,215,81
BEGIN DESCRIPTION:
This cross section corresponds to cross section 242030.7 of the non-georeferenced CDC model which was the source of this model.
Ineffective flow in LOB.
Marine Creek in LOB.
Effective flow limit in ROB set at West Fork Levee Loop.
END DESCRIPTION:
XS GIS Cut Line= 3
 2324885.1901922 6970521.2125711   2325673.28466 6969872.4354861
 2326053.4661153 6969036.4982611
#Sta/Elev= 30
       0  538.75  153.35  541.56  259.28  536.08  283.85  527.45  360.53  526.37
  423.93  510.17  445.68  506.55  467.04  506.09  483.68     500  536.22     500
  559.74  513.23  572.15  514.51     593  521.01  607.67  517.35  673.93  515.83
  733.57  494.82  785.55   492.7   900.9   494.2  932.72   497.2  949.94  500.73
  1016.8  528.27 1214.68  526.15 1542.17  525.65 1577.04  521.41 1622.38     524
 1784.67  525.72  1842.2     528 1868.33  529.47 1887.74  538.31 1939.12  538.56
#Mann= 4 ,-1,0
       0     .06       0  360.53    .035       0  673.93    .035       0
  1016.8     .06       0
#XS Ineff= 2 , 0
       0  360.53     550  1904.5       0     550
Permanent Ineff=
       F       T
Bank Sta=673.93,1016.8
XS Rating Curve= 0 ,0
Exp/Cntr=0.5,0.3

Type RM Length L Ch R = 1 ,241937  ,163,163,164
BEGIN DESCRIPTION:
This cross section corresponds to cross section 241815.4 of the non-georeferenced CDC model which was the source of this model.
Upstream of Samuels Avenue.
Downstream of the Marine Creek/West Fork confluence.
Ineffective flow in LOB and ROB.
Effective flow limit in ROB set at West Fork Levee Loop.
END DESCRIPTION:
XS GIS Cut Line= 4
2325546.115700446970573.16981782 2325580.2870518 6970463.3639949
 2325631.1394755 6970299.95540822326089.008415346969080.27124256
#Sta/Elev= 30
    -115     536    62.2  529.54   88.96  528.09  104.78  524.72  114.67  526.34
  123.55  526.72  167.26  522.35  202.71     500  208.88     498  236.09     494
  287.24  493.87  325.75  492.32  425.34   493.8  435.93  494.46   459.7     498
  475.19  500.89  499.06  510.81   544.7  527.49  569.04  528.19  617.57  527.45
  630.21  528.54  686.36   529.9  823.69  526.98  937.05  527.99 1046.54  526.17
 1146.17  526.71 1314.41  525.33 1428.69  529.61    1452   537.3 1473.93  539.11
#Mann= 3 ,-1,0
    -115     .06       0  167.26    .035       0   544.7     .06       0
#XS Ineff= 3 ,-1
    -115       0     550       0  141.43     550  680.14  736.04     550
Permanent Ineff=
       F       F       F
Bank Sta=167.26,544.7
XS Rating Curve= 0 ,0
Exp/Cntr=0.5,0.3

Type RM Length L Ch R = 3 ,241795  ,,,
BEGIN DESCRIPTION:
Samuels Avenue
Data from USACE 1975 survey, Fort Worth Floodway as-built plans.
Bridge length 449 feet.  Minimum low chord elev. 544.21
END DESCRIPTION:
Node Name=Samuels Avenue
Bridge Culvert--1,0,-1,-1, 0
Deck Dist Width WeirC Skew NumUp NumDn MinLoCord MaxHiCord MaxSubmerge Is_Ogee
61.6,41,2.6,0, 158, 158, , , 0.95, 0, 0,0,,
       0    6.85    7.43   23.69   24.29   40.54   41.14   57.81   58.52   75.23
   75.85    92.6  101.86  102.43  104.71  109.97  123.81  124.58  138.35   138.7
  152.23  152.68  153.12  153.86   166.1  167.07  167.07  616.07  616.07  618.38
   629.1  629.77  630.19   641.1  641.63  652.38  653.03  663.63  665.05  679.42
  681.04  695.27  697.05  711.16  725.06  727.08  747.62  750.13  770.63  773.17
  775.58  796.22  798.53  819.29  837.02   839.3  857.33  859.03  877.35  878.46
  885.52  897.06  897.78  927.21  927.56  949.35  957.41  957.49  957.56  987.47
  987.83  988.17  1017.6  1018.2  1036.8 1037.63 1055.86 1056.95 1057.64 1075.73
 1076.52 1077.29 1095.33 1096.05  1111.2 1111.82 1112.39 1127.79 1128.08 1141.09
 1143.92 1144.03 1157.32 1159.66 1160.27  1177.9 1178.19 1196.07 1196.17  1210.9
 1214.15 1214.17 1214.18 1232.17 1232.22 1249.57 1249.61 1259.55 1266.96 1266.99
 1267.02 1284.32 1284.44 1301.57 1301.77  1302.1 1328.17 1329.28 1353.92 1355.81
  1357.7 1381.75 1384.24 1407.36 1408.31 1409.22 1410.11 1410.93 1433.73 1434.74
 1435.07 1435.38 1435.68 1435.95 1449.91 1450.22 1456.42 1469.51 1482.49 1492.46
 1495.37 1496.17 1509.34  1523.5  1523.9 1524.36  1524.9 1525.54 1535.41 1535.96
 1545.46 1554.78 1563.91 1567.38 1576.93 1587.07 1597.09 1602.94
  544.92  545.27  545.29  546.19  546.21  547.11  547.13  548.09  548.12  549.13
  549.15  550.13   550.6  550.63  550.74  551.01  551.58  551.63  552.12  552.15
  552.61  552.64  552.68  552.73  553.17   553.2     555     554  552.53  552.53
  552.01  552.01  551.99  551.47  551.45  550.94  550.91  550.41  550.35  549.67
  549.59  548.92  548.84  548.16  547.47  547.36  546.31  546.15  545.07  544.88
  544.71  543.56  543.41  542.16  540.95  540.83  539.47   539.4  538.05     538
  537.55  536.81  536.78  535.48  535.46  534.84   534.6   534.6  534.59  533.83
  533.81   533.8  532.88  532.87  532.09  532.08  531.25  531.24  531.24   530.5
  530.51  530.52  529.96  529.96  529.64  529.63  529.61  529.39  529.38  529.27
  529.24  529.24  529.18  529.17  529.16  529.28  529.27  529.56  529.56  529.82
  529.87  529.87  529.87  530.07  530.07  530.14  530.14  530.15  530.15  530.15
  530.15  530.12  530.13  530.12  530.13  530.14  531.87  531.94  533.69   533.8
  533.89  535.51  535.58  536.89  536.89  536.88  536.87  536.88  537.77  537.84
  537.87  537.91  537.95  537.99   538.4  538.43  538.83  539.18   539.4  539.43
  539.43  539.45  539.21  538.96  538.91  538.86  538.79  538.72  538.31  538.23
  537.68  537.05  536.39  536.02  535.35  534.63  533.87   533.2
                                                  545.18  544.21     450
       0    6.85    7.43   23.69   24.29   40.54   41.14   57.81   58.52   75.23
   75.85    92.6  101.86  102.43  104.71  109.97  123.81  124.58  138.35   138.7
  152.23  152.68  153.12  153.86   166.1  167.07  167.07  616.07  616.07  618.38
   629.1  629.77  630.19   641.1  641.63  652.38  653.03  663.63  665.05  679.42
  681.04  695.27  697.05  711.16  725.06  727.08  747.62  750.13  770.63  773.17
  775.58  796.22  798.53  819.29  837.02   839.3  857.33  859.03  877.35  878.46
  885.52  897.06  897.78  927.21  927.56  949.35  957.41  957.49  957.56  987.47
  987.83  988.17  1017.6  1018.2  1036.8 1037.63 1055.86 1056.95 1057.64 1075.73
 1076.52 1077.29 1095.33 1096.05  1111.2 1111.82 1112.39 1127.79 1128.08 1141.09
 1143.92 1144.03 1157.32 1159.66 1160.27  1177.9 1178.19 1196.07 1196.17  1210.9
 1214.15 1214.17 1214.18 1232.17 1232.22 1249.57 1249.61 1259.55 1266.96 1266.99
 1267.02 1284.32 1284.44 1301.57 1301.77  1302.1 1328.17 1329.28 1353.92 1355.81
  1357.7 1381.75 1384.24 1407.36 1408.31 1409.22 1410.11 1410.93 1433.73 1434.74
 1435.07 1435.38 1435.68 1435.95 1449.91 1450.22 1456.42 1469.51 1482.49 1492.46
 1495.37 1496.17 1509.34  1523.5  1523.9 1524.36  1524.9 1525.54 1535.41 1535.96
 1545.46 1554.78 1563.91 1567.38 1576.93 1587.07 1597.09 1602.94
  544.92  545.27  545.29  546.19  546.21  547.11  547.13  548.09  548.12  549.13
  549.15  550.13   550.6  550.63  550.74  551.01  551.58  551.63  552.12  552.15
  552.61  552.64  552.68  552.73  553.17   553.2     555     554  552.53  552.53
  552.01  552.01  551.99  551.47  551.45  550.94  550.91  550.41  550.35  549.67
  549.59  548.92  548.84  548.16  547.47  547.36  546.31  546.15  545.07  544.88
  544.71  543.56  543.41  542.16  540.95  540.83  539.47   539.4  538.05     538
  537.55  536.81  536.78  535.48  535.46  534.84   534.6   534.6  534.59  533.83
  533.81   533.8  532.88  532.87  532.09  532.08  531.25  531.24  531.24   530.5
  530.51  530.52  529.96  529.96  529.64  529.63  529.61  529.39  529.38  529.27
  529.24  529.24  529.18  529.17  529.16  529.28  529.27  529.56  529.56  529.82
  529.87  529.87  529.87  530.07  530.07  530.14  530.14  530.15  530.15  530.15
  530.15  530.12  530.13  530.12  530.13  530.14  531.87  531.94  533.69   533.8
  533.89  535.51  535.58  536.89  536.89  536.88  536.87  536.88  537.77  537.84
  537.87  537.91  537.95  537.99   538.4  538.43  538.83  539.18   539.4  539.43
  539.43  539.45  539.21  538.96  538.91  538.86  538.79  538.72  538.31  538.23
  537.68  537.05  536.39  536.02  535.35  534.63  533.87   533.2
                                                  545.18  544.21     450
Pier Skew, UpSta & Num, DnSta & Num=  ,213.27, 2 ,213.27, 2 , 0 , 0 , 0 ,,
       6       3
     450     550
       6       3
     450     550
Pier Skew, UpSta & Num, DnSta & Num=  ,263.27, 4 ,263.27, 4 , 0 , 0 , 0 ,,
      19      19       8       3
     450     500   502.5     550
      19      19       8       3
     450     500   502.5     550
Pier Skew, UpSta & Num, DnSta & Num=  ,313.77, 4 ,313.77, 4 , 0 , 0 , 0 ,,
      19      19       8       3
     450     500   502.5     550
      19      19       8       3
     450     500   502.5     550
Pier Skew, UpSta & Num, DnSta & Num=  ,363.77, 4 ,363.77, 4 , 0 , 0 , 0 ,,
      19      19       8       3
     450     500   502.5     550
      19      19       8       3
     450     500   502.5     550
Pier Skew, UpSta & Num, DnSta & Num=  ,413.27, 4 ,413.27, 4 , 0 , 0 , 0 ,,
      19      19       8       3
     450     500   502.5     550
      19      19       8       3
     450     500   502.5     550
Pier Skew, UpSta & Num, DnSta & Num=  ,461.07, 4 ,461.07, 4 , 0 , 0 , 0 ,,
      19      19       8       3
     450     500   502.5     550
      19      19       8       3
     450     500   502.5     550
Pier Skew, UpSta & Num, DnSta & Num=  ,519.47, 2 ,519.47, 2 , 0 , 0 , 0 ,,
       6       3
     450     550
       6       3
     450     550
Pier Skew, UpSta & Num, DnSta & Num=  ,569.47, 2 ,569.47, 2 , 0 , 0 , 0 ,,
       6       3
     450     550
       6       3
     450     550
BR Coef=-1 , 0 , 0 ,, 0 ,,,0.8,-1,,0,
WSPro=,,,, 1 ,,,, 0 ,,,, 0 ,,,,-1 ,-1 ,-1 , 0 , 0 , 0 , 0 , 0
BR U #Sta/Elev= 357
  167.07  545.18  167.07  520.37  202.13  521.39   207.4  521.57  215.17  515.06
  226.97  505.16  231.37   501.2  255.73  496.65  261.12  495.64  265.98  494.58
   269.6  493.77  283.83  490.76  292.59  489.01  297.18   488.1  298.69  488.15
     299  488.15  299.19  488.15   305.2  488.24  305.96  488.26  308.73  488.34
  310.73   488.4  312.06  488.44  315.26  488.54  318.37  488.63  323.16   488.7
  324.42  488.73  325.98  488.77   326.6  488.79  331.62  488.83  334.68  488.86
  334.68   488.8  334.69   488.8   334.7   488.8  335.63  488.91  336.27  488.99
  336.38     489   336.5  489.01  336.69  489.03  337.84  489.16  338.27  489.21
  338.82  489.27  339.11   489.3  339.48  489.34  339.79  489.31  340.22  489.35
  340.53  489.38  340.78  489.41  341.53  489.47  341.75  489.52  342.36  489.57
   342.9  489.61  342.99  489.62  343.51  489.66  343.56  489.66  344.07   489.7
  344.21   489.7  344.22   489.7  347.72  489.66  347.87  489.67  348.05  489.69
  351.38  489.77  351.55  489.77  353.48  489.98  353.89  489.97  354.35  489.98
  355.35  490.16  358.17   490.2  358.79  490.24  359.12  490.22   361.7  490.25
  363.97  490.16  365.77  490.19  366.29  490.24  368.35  490.06  370.01  490.21
  370.65  490.28  371.26   490.3   371.9  490.38  373.01  490.41  374.38  490.47
  375.95  490.48  376.41  490.54  378.76   490.5  379.99  490.54  380.79  490.43
  381.47  490.42  383.16  490.26   384.1  490.13  385.06  490.08  386.12  490.18
  386.84  490.19  388.91  490.24  390.03  490.27   390.2  490.27  390.59  490.29
  394.05  490.37  394.17  490.37  394.27  490.37  395.61  490.36  395.61  490.38
  399.44  491.27  404.87   492.5  405.16  492.55  407.38   493.1  408.35  493.35
  409.61  493.65  411.36  493.92  412.03  494.03  412.84  494.07  415.24  494.29
  416.65  494.44  418.06  494.74  418.69  494.77  419.41  494.89  420.57  495.01
  421.21  494.97  460.22  501.81  474.16  508.83  478.11  510.82  505.12  526.13
  507.39  527.36  521.91  527.67  543.42  528.11  577.21  528.46  591.04  528.61
   593.2  528.65  598.92  529.63  611.47  531.75  616.07  532.05  616.07  544.21
  617.57  527.45  620.87  527.82  622.58     528  622.73     528  625.93  528.28
  628.28  528.45  630.21  528.54  632.21  528.61  634.05  528.62  634.32  528.64
  635.78  528.63  636.29  528.65  637.23  528.65  638.19  528.69  639.22  528.71
  640.36  528.69  642.01  528.68  642.92  528.71   643.8  528.72  644.32  528.75
  645.96  528.76  647.48  528.79   648.5  528.85   650.5  528.93  653.08  529.06
  653.63  529.07  655.19  529.14  658.72  529.32  659.42  529.34  663.98  529.55
   667.9   529.7   668.8  529.73  674.01  529.85  675.79  529.87  681.08   529.9
  686.36   529.9  689.71  529.88  692.93  529.85  694.44  529.83  698.13  529.74
  700.42  529.69   706.4  529.54  707.61   529.5  712.84  529.26  714.44  529.18
  720.03  528.94  720.99  528.92  725.31  528.72  727.48  528.64  732.87  528.41
  735.39  528.37   737.7   528.3  743.37  528.16  745.03  528.11  747.45  528.08
  749.45  528.08  752.37  528.04     760  527.98  764.65  527.96  767.17  527.96
  769.74  527.93  772.36  527.91  772.54   527.9  775.69  527.86  779.33  527.78
  779.88  527.78   783.2  527.71  786.56  527.66  790.39  527.59   793.7  527.49
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BR U #Mann= 3
  167.07     .06   207.4    .035  507.39     .06
BR U Banks=207.4,507.39
BR D #Sta/Elev= 369
  167.07  545.18  168.89  544.88  174.38  520.37  202.13  521.39   207.4  521.57
  215.17  515.06  226.97  505.16  231.37   501.2  255.73  496.65  261.12  495.64
  265.98  494.58   269.6  493.77  271.51  494.33  271.64  494.34  271.75   494.3
  271.81  494.26  271.98  494.32  272.08  494.37  272.17  494.37  272.35  494.39
  272.44  494.39  272.53  494.35  272.73  494.31  272.83  494.26  272.95  494.27
  273.04  494.22  273.22  494.22  273.32  494.28  273.44  494.29   273.8   494.3
  273.95  494.24  274.42  494.07  274.59  494.07  274.78  494.14  275.16  494.14
  275.57  494.15  275.92  494.15  276.11  494.24  276.37  494.24  276.73  494.25
  277.12  494.17  277.46  494.18  277.76  494.18  278.19  494.19   278.4   494.1
  278.62   494.1  278.77  494.03  278.99  494.01  280.95  494.19  281.55  494.13
  281.68  494.14  282.51  494.18  283.03  494.21  283.28   494.2  284.04  494.24
  284.79  494.27  285.67  494.32  286.16  494.34  286.49  494.36  286.78  494.37
  287.22   494.4  287.94  494.43  290.57   494.6  291.23  494.55  291.29  494.54
  292.08   494.6  292.71  494.56   293.7  494.58   294.1  494.55  295.56  494.43
  295.79  494.47  301.73   494.2  301.93  494.19   302.1  494.17  302.41  494.16
  305.15     494  317.55  493.44  318.55  493.44  319.06  493.42  319.63  493.39
  320.22  493.42  321.73  493.36  322.55  493.27  323.42  493.23   325.7  493.06
  328.41  493.01  330.36  492.84  332.34  492.75  332.88  492.72  333.32   492.7
  334.09  492.72  336.98  492.71  339.36  492.78  340.46  492.72  342.64  492.79
  344.45  492.85  345.45  492.88  347.01  492.86  347.73  492.88  348.55  492.91
  351.16  492.87  352.27  492.92  353.38  492.96  354.33  492.99  355.29  492.98
  355.71  492.99  356.51  492.97  357.32  493.01  358.74  493.07  359.06  493.08
  359.71  493.11  360.55  493.14  360.87  493.16  361.38  493.18  362.14  493.25
  362.58  493.31  363.05  493.36  363.87  493.46  364.24  493.47  370.01  493.57
  370.15   493.6  370.28  493.61  370.97  493.63  388.09     494  395.54     494
   396.2  493.98  396.44  493.95   396.6  493.85  396.77   493.8  396.82   493.8
  396.88  493.86   396.9  493.85  399.83  494.72   400.5  494.92  401.65  495.28
  402.05   495.4  402.31  495.43  402.67  495.39  402.95  495.35  403.52  495.46
  403.66  495.55   403.8  495.57  403.92  495.65  404.01  495.66  404.12  495.62
  404.38  495.66  404.45  495.72  404.53  495.68  404.86  495.73  404.95  495.68
  407.25     496  413.07  496.68  420.81  497.44  426.48     498  435.84  499.36
  440.16     500  440.82  500.21  445.53  501.69  445.83  501.82  446.28     502
   450.4   503.8  452.86  504.85  455.51     506  459.98     508  463.66  509.62
  464.52     510  465.47  510.43  466.36  510.83  468.77  511.94  469.04  512.07
  473.18  513.92  473.35     514  477.06  515.71  477.68     516  481.03  517.54
  482.05     518  486.43     520  488.23  520.82  490.78     522  491.27  522.23
  492.06  522.58  494.16  523.53  494.34  523.62  495.15     524  496.72  524.74
  499.37     526  501.14  526.82  501.88  527.16  502.33  527.38  505.12  526.13
  507.39  527.36  521.91  527.67  543.42  528.11  577.21  528.46  591.04  528.61
   593.2  528.65  598.92  529.63  611.47  531.75  613.12  532.05  616.07  532.05
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BR D #Mann= 3
  167.07     .06   207.4    .035  502.33     .06
BR D Banks=207.4,
BC Design=,, 0 ,, 0 ,,,,,,
BC Use User HTab Curves=0
BC User HTab FreeFlow(D)= 0