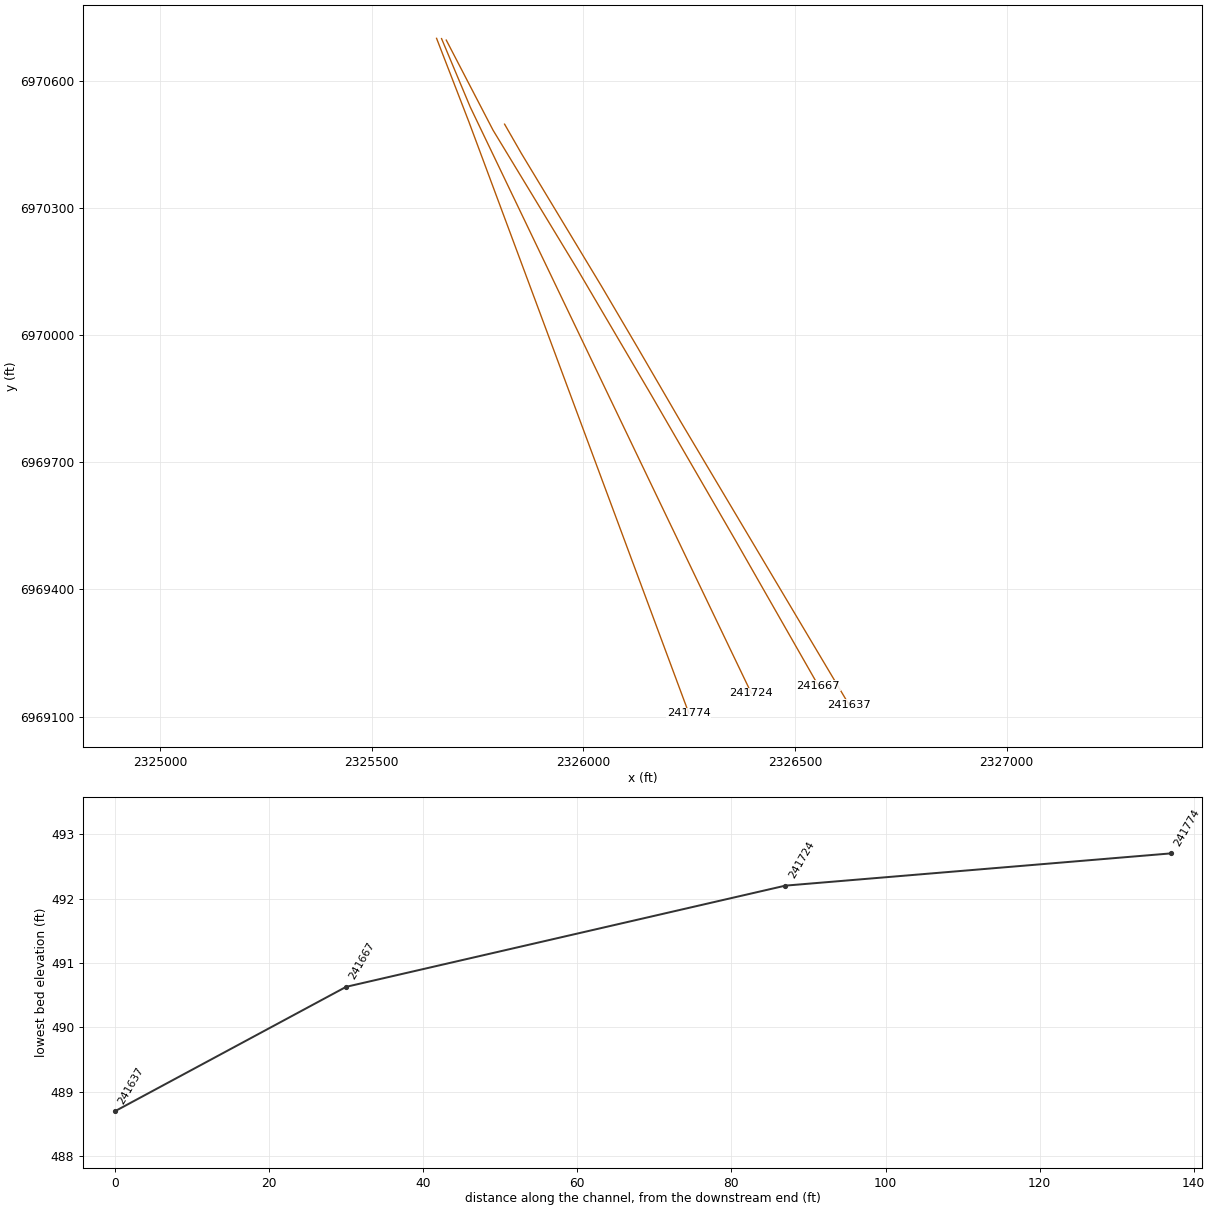
HEC-RAS study CDC_Consolidated_Model.prj: Upper Trinity CDC Consolidated Model

--- CDC_Consolidated_Model.g03 (geometry) --- (continued)

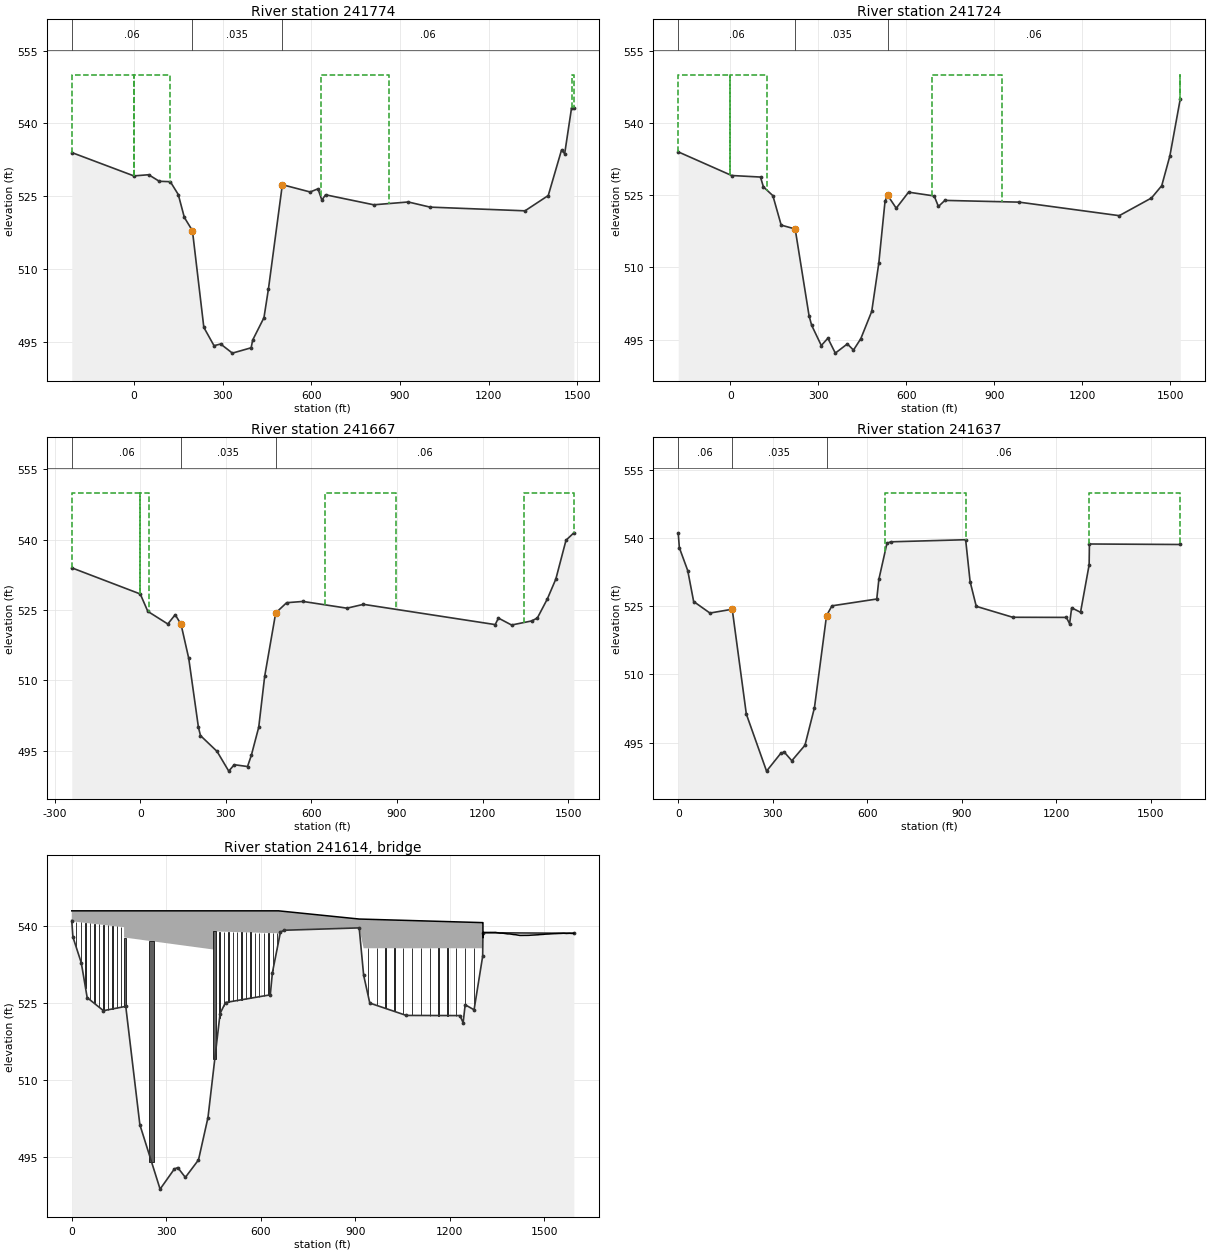
Type RM Length L Ch R = 1 ,241774  ,50,50,97
BEGIN DESCRIPTION:
This cross section corresponds to cross section 241652.8 of the non-georeferenced CDC model which was the source of this model.
Downstream of Samuels Avenue.
Ineffective flow in LOB and ROB due to railroad bridges and Samuels Avenue bridge.
Effective flow limit in ROB set at West Fork Levee Loop.
END DESCRIPTION:
XS GIS Cut Line= 3
     2325652.921     6970700.238  2325729.656664 6970502.2852219
  2326249.237085  6969107.444601
#Sta/Elev= 30
    -210     534       0  529.19   50.08  529.43   86.09  528.08  123.36     528
  150.33  525.35  170.84  520.64  198.19  517.91  236.76     498  271.22  494.23
   293.7  494.58  333.32   492.7  396.82   493.8  402.05   495.4  440.16     500
  455.51     506  502.33  527.38  596.37  525.88  622.83  526.53  636.07  524.21
  648.61   525.3  811.66  523.24  928.35  523.82 1002.16  522.76 1323.32     522
  1401.9  525.15 1446.73   534.5 1457.46  533.77  1480.7  543.18 1488.47  543.18
#Mann= 3 ,-1,0
    -210     .06       0  198.19    .035       0  502.33     .06       0
#XS Ineff= 4 ,-1
    -210       0     550       0  121.14     550  631.56  864.84     550
  1480.7 1488.47     550
Permanent Ineff=
       F       F       F       T
Bank Sta=198.19,502.33
XS Rating Curve= 0 ,0
Exp/Cntr=0.5,0.3

Type RM Length L Ch R = 1 ,241724  ,57,57,109
BEGIN DESCRIPTION:
This cross section corresponds to cross section 241602.9 of the non-georeferenced CDC model which was the source of this model.
Ineffective flow in LOB and ROB due to railroad bridges and Samuels Avenue bridge.
Effective flow limit in ROB set at West Fork Levee Loop.
END DESCRIPTION:
XS GIS Cut Line= 3
     2325664.727     6970699.544 2325732.4669479 6970538.2718425
 2326397.0062317 6969154.7011744
#Sta/Elev= 30
    -178     534    4.28  529.09  102.65  528.77  112.49  526.74   144.9   524.9
  173.22  518.79  220.98  517.98  268.22     500  277.04     498  310.09  493.78
  332.57   495.3   357.9   492.2  398.89  494.11  419.89  492.83  444.83   495.2
  482.07  500.86  506.16  510.85  527.45   523.7  535.98  525.01  565.71   522.3
  607.86  525.63  695.22  524.84  709.61  522.66  731.67  523.92  984.78  523.56
  1326.6  520.75 1436.52  524.42 1471.56  526.98 1499.35  533.18 1534.89  545.05
#Mann= 3 ,-1,0
    -178     .06       0  220.98    .035       0  535.98     .06       0
#XS Ineff= 4 ,-1
    -178       0     550       0  126.44     550  687.54  927.39     550
 1533.21 1534.89     550
Permanent Ineff=
       F       F       F       T
Bank Sta=220.98,535.98
XS Rating Curve= 0 ,0
Exp/Cntr=0.3,0.1

Type RM Length L Ch R = 1 ,241667  ,30,30,30
BEGIN DESCRIPTION:
This cross section corresponds to cross section 241545.7 of the non-georeferenced CDC model which was the source of this model.
END DESCRIPTION:
XS GIS Cut Line= 6
     2325675.838     6970696.072 2325786.4906963 6970483.3797814
 2325986.1004538 6970154.6512313 2326160.3068156 6969858.6551386
 2326358.7140547 6969516.6532536 2326555.2234671 6969172.9453593
#Sta/Elev= 30
    -240     534       0  528.42   26.46  524.71   96.52  522.02  122.43     524
  142.81  521.96  169.81  514.71  203.79     500     211  498.21  269.07  494.84
  310.11  490.63   329.3     492  375.89  491.61  389.23     494  415.14     500
     436  510.86  474.65  524.38  512.95  526.56  570.18  526.83  724.23  525.39
  782.16  526.21 1243.79  521.89 1255.06  523.28 1301.14   521.8 1371.64  522.67
 1391.53   523.3 1426.64  527.38 1456.26  531.61 1491.91  539.89 1519.35  541.46
#Mann= 3 ,-1,0
    -240     .06       0  142.81    .035       0  474.65     .06       0
#XS Ineff= 4 ,-1
    -240       0     550       0   29.61     550  648.11  895.76     550
 1344.39 1519.35     550
Permanent Ineff=
       F       F       F       F
Bank Sta=142.81,474.65
XS Rating Curve= 0 ,0
Exp/Cntr=0.5,0.3

Type RM Length L Ch R = 1 ,241637  ,33,33,32
BEGIN DESCRIPTION:
This cross section corresponds to cross section 241515.2 of the non-georeferenced CDC model which was the source of this model.
Upstream of BNSF Railroad.
Copy of cross-section 241482.4
END DESCRIPTION:
XS GIS Cut Line= 6
  2325813.645107 6970497.7372755 2325853.4247942 6970428.5210372
 2326043.6038051 6970113.8751495  2326127.789038 6969970.9919547
 2326229.0614144 6969797.0510907 2326627.7506411 6969127.8228072
#Sta/Elev= 30
       0  541.11    3.54  537.91    30.2  532.86   48.92  526.06  100.61  523.52
  171.36  524.36  216.12  501.27  280.34   488.7  325.55  492.63  336.41   492.9
  360.53  490.99  402.23   494.4  432.34  502.67  470.76  522.96  487.94  525.11
  630.12  526.61  636.85  530.96   662.4  538.86  674.61  539.21  912.26  539.67
  926.37  530.45  945.92     525 1061.74  522.59 1232.04  522.56 1242.17  521.16
 1248.68  524.67 1276.91  523.69  1304.2  534.14 1305.08  538.73 1593.59  538.62
#Mann= 3 ,0,0
       0     .06       0  171.36    .035       0  470.76     .06       0
#XS Ineff= 2 ,-1
     656  912.26     550 1305.08 1593.59     550
Permanent Ineff=
       F       F
Bank Sta=171.36,470.76
XS Rating Curve= 0 ,0
Exp/Cntr=0.5,0.3

Type RM Length L Ch R = 3 ,241614  ,,,
BEGIN DESCRIPTION:
Burlington Northern Railroad
Two bridges: West Fork channel bridge, and ROB relief bridge.  West Fork bridge: data from 1975 USACE field survey, Fort Worth Floodway as-built plans.  Relief bridge: data from USACE 1949 field survey, EA Inc. 1995 field survey, USACE May 2007 field measurement.
Note:  West Fork bridge internal bridge cross-sections modified to represent geometry under bridges.
END DESCRIPTION:
Node Name=BNSF Railroad
Bridge Culvert--1,0,-1,-1, 0
Deck Dist Width WeirC Skew NumUp NumDn MinLoCord MaxHiCord MaxSubmerge Is_Ogee
6.4,20,2.6,0, 56, 56, , , 0.95, 0, 0,0,,
       0     166     166     451     451     656     656  912.26  912.26 1304.54
 1304.54 1305.08 1305.08 1306.77 1310.34 1313.29 1324.27 1329.16 1339.34 1344.26
 1359.84 1364.29 1368.48 1383.15 1386.39 1389.72 1403.46 1406.83 1422.01 1425.08
  1427.8 1438.83 1440.82 1443.58 1451.58 1456.93 1468.79  1480.6 1486.06 1497.75
 1500.55 1503.41 1514.98 1517.87 1520.83 1532.28 1535.26 1546.63 1549.65 1560.93
 1565.24 1569.66 1580.82 1585.31  1593.3 1593.59
     543     543     543     543     543     543     543   541.4   541.4   540.7
   540.7   540.7  537.73  538.76  538.76  538.77  538.77  538.78  538.78  538.79
  538.64  538.64  538.64   538.5   538.5   538.5  538.36  538.36   538.2   538.2
   538.2  538.21  538.21  538.21  538.22  538.25  538.29  538.33  538.37  538.41
  538.43  538.45  538.48   538.5  538.51  538.55  538.55  538.59  538.59  538.63
  538.62  538.59  538.63   538.6  538.62  538.62
  540.95   539.8   537.8  535.44  538.98  538.62     500     500   535.7   535.7
     500     500
       0     166     166     451     451     656     656  912.26  912.26 1304.54
 1304.54 1305.08 1305.08 1306.77 1310.34 1313.29 1324.27 1329.16 1339.34 1344.26
 1359.84 1364.29 1368.48 1383.15 1386.39 1389.72 1403.46 1406.83 1422.01 1425.08
  1427.8 1438.83 1440.82 1443.58 1451.58 1456.93 1468.79  1480.6 1486.06 1497.75
 1500.55 1503.41 1514.98 1517.87 1520.83 1532.28 1535.26 1546.63 1549.65 1560.93
 1565.24 1569.66 1580.82 1585.31  1593.3 1593.59
     543     543     543     543     543     543     543   541.4   541.4   540.7
   540.7   540.7  537.73  538.76  538.76  538.77  538.77  538.78  538.78  538.79
  538.64  538.64  538.64   538.5   538.5   538.5  538.36  538.36   538.2   538.2
   538.2  538.21  538.21  538.21  538.22  538.25  538.29  538.33  538.37  538.41
  538.43  538.45  538.48   538.5  538.51  538.55  538.55  538.59  538.59  538.63
  538.62  538.59  538.63   538.6  538.62  538.62
  540.95   539.8   537.8  535.44  538.98  538.62     500     500   535.7   535.7
     500     500
Pier Skew, UpSta & Num, DnSta & Num=  ,14, 2 ,14, 2 , 0 , 0 , 0 ,,
     1.2     1.2
     450     541
     1.2     1.2
     450     541
Pier Skew, UpSta & Num, DnSta & Num=  ,29, 2 ,29, 2 , 0 , 0 , 0 ,,
     1.2     1.2
     450     541
     1.2     1.2
     450     541
Pier Skew, UpSta & Num, DnSta & Num=  ,44, 2 ,44, 2 , 0 , 0 , 0 ,,
     1.2     1.2
     450     541
     1.2     1.2
     450     541
Pier Skew, UpSta & Num, DnSta & Num=  ,58, 2 ,58, 2 , 0 , 0 , 0 ,,
     1.2     1.2
     450     541
     1.2     1.2
     450     541
Pier Skew, UpSta & Num, DnSta & Num=  ,72, 2 ,72, 2 , 0 , 0 , 0 ,,
     1.2     1.2
     450     541
     1.2     1.2
     450     541
Pier Skew, UpSta & Num, DnSta & Num=  ,87, 2 ,87, 2 , 0 , 0 , 0 ,,
     1.2     1.2
     450     541
     1.2     1.2
     450     541
Pier Skew, UpSta & Num, DnSta & Num=  ,101, 2 ,101, 2 , 0 , 0 , 0 ,,
     1.2     1.2
     450     541
     1.2     1.2
     450     541
Pier Skew, UpSta & Num, DnSta & Num=  ,115, 2 ,115, 2 , 0 , 0 , 0 ,,
     1.2     1.2
     450     541
     1.2     1.2
     450     541
Pier Skew, UpSta & Num, DnSta & Num=  ,129, 2 ,129, 2 , 0 , 0 , 0 ,,
     1.2     1.2
     450     541
     1.2     1.2
     450     541
Pier Skew, UpSta & Num, DnSta & Num=  ,143, 2 ,143, 2 , 0 , 0 , 0 ,,
     1.2     1.2
     450     541
     1.2     1.2
     450     541
Pier Skew, UpSta & Num, DnSta & Num=  ,156, 2 ,156, 2 , 0 , 0 , 0 ,,
     1.2     1.2
     450     541
     1.2     1.2
     450     541
Pier Skew, UpSta & Num, DnSta & Num=  ,168.75, 2 ,168.75, 2 , 0 , 0 , 0 ,,
     5.5     5.5
     450     541
     5.5     5.5
     450     541
Pier Skew, UpSta & Num, DnSta & Num=  ,253.75, 4 ,253.75, 4 , 0 , 0 , 0 ,,
      16      16       9       7
     450   509.3   511.3     542
      16      16       9       7
     450   509.3   511.3     542
Pier Skew, UpSta & Num, DnSta & Num=  ,454, 2 ,454, 2 , 0 , 0 , 0 ,,
     8.5     6.5
     450     542
     8.5     6.5
     450     542
Pier Skew, UpSta & Num, DnSta & Num=  ,469, 2 ,469, 2 , 0 , 0 , 0 ,,
     1.2     1.2
  490.63  540.95
     1.2     1.2
  490.63  540.95
Pier Skew, UpSta & Num, DnSta & Num=  ,483, 2 ,483, 2 , 0 , 0 , 0 ,,
     1.2     1.2
  490.63  540.95
     1.2     1.2
  490.63  540.95
Pier Skew, UpSta & Num, DnSta & Num=  ,497, 2 ,497, 2 , 0 , 0 , 0 ,,
     1.2     1.2
  490.63  540.95
     1.2     1.2
  490.63  540.95
Pier Skew, UpSta & Num, DnSta & Num=  ,511, 2 ,511, 2 , 0 , 0 , 0 ,,
     1.2     1.2
  490.63  540.95
     1.2     1.2
  490.63  540.95
Pier Skew, UpSta & Num, DnSta & Num=  ,525, 2 ,525, 2 , 0 , 0 , 0 ,,
     1.2     1.2
  490.63  540.95
     1.2     1.2
  490.63  540.95
Pier Skew, UpSta & Num, DnSta & Num=  ,539, 2 ,539, 2 , 0 , 0 , 0 ,,
     1.2     1.2
  490.63  540.95
     1.2     1.2
  490.63  540.95
Pier Skew, UpSta & Num, DnSta & Num=  ,553, 2 ,553, 2 , 0 , 0 , 0 ,,
     1.2     1.2
  490.63  540.95
     1.2     1.2
  490.63  540.95
Pier Skew, UpSta & Num, DnSta & Num=  ,567, 2 ,567, 2 , 0 , 0 , 0 ,,
     1.2     1.2
  490.63  540.95
     1.2     1.2
  490.63  540.95
Pier Skew, UpSta & Num, DnSta & Num=  ,581, 2 ,581, 2 , 0 , 0 , 0 ,,
     1.2     1.2
  490.63  540.95
     1.2     1.2
  490.63  540.95
Pier Skew, UpSta & Num, DnSta & Num=  ,595, 2 ,595, 2 , 0 , 0 , 0 ,,
     1.2     1.2
  490.63  540.95
     1.2     1.2
  490.63  540.95
Pier Skew, UpSta & Num, DnSta & Num=  ,610, 2 ,610, 2 , 0 , 0 , 0 ,,
     1.2     1.2
  490.63  540.95
     1.2     1.2
  490.63  540.95
Pier Skew, UpSta & Num, DnSta & Num=  ,624, 2 ,624, 2 , 0 , 0 , 0 ,,
     1.2     1.2
  490.63  540.95
     1.2     1.2
  490.63  540.95
Pier Skew, UpSta & Num, DnSta & Num=  ,638, 2 ,638, 2 , 0 , 0 , 0 ,,
     1.2     1.2
  490.63  540.95
     1.2     1.2
  490.63  540.95
Pier Skew, UpSta & Num, DnSta & Num=  ,652, 2 ,652, 2 , 0 , 0 , 0 ,,
     1.2     1.2
  490.63  540.95
     1.2     1.2
  490.63  540.95
Pier Skew, UpSta & Num, DnSta & Num=  ,940.26, 2 ,940.26, 2 , 0 , 0 , 0 ,,
   1.167   1.167
   488.7  540.95
   1.167   1.167
   488.7  540.95
Pier Skew, UpSta & Num, DnSta & Num=  ,968.26, 2 ,968.26, 2 , 0 , 0 , 0 ,,
   1.167   1.167
   488.7  540.95
   1.167   1.167
   488.7  540.95
Pier Skew, UpSta & Num, DnSta & Num=  ,996.26, 2 ,996.26, 2 , 0 , 0 , 0 ,,
   1.167   1.167
   488.7  540.95
   1.167   1.167
   488.7  540.95
Pier Skew, UpSta & Num, DnSta & Num=  ,1024.26, 2 ,1024.26, 2 , 0 , 0 , 0 ,,
   1.167   1.167
   488.7  540.95
   1.167   1.167
   488.7  540.95
Pier Skew, UpSta & Num, DnSta & Num=  ,1052.26, 2 ,1052.26, 2 , 0 , 0 , 0 ,,
   1.167   1.167
   488.7  540.95
   1.167   1.167
   488.7  540.95
Pier Skew, UpSta & Num, DnSta & Num=  ,1080.26, 2 ,1080.26, 2 , 0 , 0 , 0 ,,
   1.167   1.167
   488.7  540.95
   1.167   1.167
   488.7  540.95
Pier Skew, UpSta & Num, DnSta & Num=  ,1108.26, 2 ,1108.26, 2 , 0 , 0 , 0 ,,
   1.167   1.167
   488.7  540.95
   1.167   1.167
   488.7  540.95
Pier Skew, UpSta & Num, DnSta & Num=  ,1136.26, 2 ,1136.26, 2 , 0 , 0 , 0 ,,
   1.167   1.167
   488.7  540.95
   1.167   1.167
   488.7  540.95
Pier Skew, UpSta & Num, DnSta & Num=  ,1164.26, 2 ,1164.26, 2 , 0 , 0 , 0 ,,
   1.167   1.167
   488.7  540.95
   1.167   1.167
   488.7  540.95
Pier Skew, UpSta & Num, DnSta & Num=  ,1192.26, 2 ,1192.26, 2 , 0 , 0 , 0 ,,
   1.167   1.167
   488.7  540.95
   1.167   1.167
   488.7  540.95
Pier Skew, UpSta & Num, DnSta & Num=  ,1220.26, 2 ,1220.26, 2 , 0 , 0 , 0 ,,
   1.167   1.167
   488.7  540.95
   1.167   1.167
   488.7  540.95
Pier Skew, UpSta & Num, DnSta & Num=  ,1248.26, 2 ,1248.26, 2 , 0 , 0 , 0 ,,
   1.167   1.167
   488.7  540.95
   1.167   1.167
   488.7  540.95
Pier Skew, UpSta & Num, DnSta & Num=  ,1276.26, 2 ,1276.26, 2 , 0 , 0 , 0 ,,
   1.167   1.167
   488.7  540.95
   1.167   1.167
   488.7  540.95
BR Coef=-1 , 0 , 0 ,, 0 ,,,0.8,-1,,0,
WSPro=,,,, 1 ,,,, 0 ,,,, 0 ,,,,-1 ,-1 ,-1 , 0 , 0 , 0 , 0 , 0
BR U #Sta/Elev= 488
       0  541.11     .62  541.18    3.22  538.26    3.54  537.91    4.02  537.81
   18.15  534.53   20.56  534.13   25.88  533.44    28.9  533.04    30.2  532.86
   30.88  532.62   31.09  532.55   32.05   532.2   32.76  531.94   33.64  531.62
   35.33     531   38.48  529.84   39.06  529.64   42.42  528.42   48.08   526.4
   48.92  526.06   52.18  525.84   55.34  525.62   55.68  525.59   57.36  525.48
   58.93  525.37   60.35  525.28   60.85  525.24    62.1  525.15   79.67   524.4
  100.61  523.52  104.26  523.54  105.19  523.52  106.13  523.52  109.92  523.54
  110.86  523.56  111.79   523.6   113.8  523.79  115.77   524.1  119.76  524.12
  161.75  524.12  162.94  524.15   166.6  524.29  167.26  524.32  171.36  524.36
  176.35  521.75  177.24  521.31     190  514.62  192.51  513.44   195.7  511.92
  199.96   509.8  202.37  508.55  205.25  507.05  208.74  505.21  213.03  502.94
   214.4  502.23  216.12  501.27  232.15  498.43  232.67  498.34  233.17  498.22
  233.76  498.12  234.33  497.99     235  497.87  235.66  497.76  236.43  497.56
  237.18  497.36  237.65  497.24  238.51  497.08  239.52  496.86  240.52  496.63
  241.72  496.37  242.92  496.14  244.38  495.83  245.84  495.45  257.74  493.09
  259.36  492.85  260.94  492.48  263.71  491.96  265.65  491.51  267.89  491.16
  270.19  490.64  272.85  490.13  275.61   489.6  278.83  488.99  280.34   488.7
  280.35   488.7   280.4   488.7  281.17  488.76  282.73  488.86  284.12  488.95
  284.18  488.97  284.25  488.97  284.37  488.98  285.84  489.08  285.93  489.09
  286.04  489.09  286.16   489.1  286.32  489.12  286.44  489.14  286.65  489.16
  287.02  489.18     302  490.86  302.28  490.88  303.22  490.92  304.24  490.97
  304.92  491.05  306.09  491.16  306.27  491.17  306.66  491.15  307.42  491.29
  308.74   491.3   309.5  491.38  310.39  491.42  310.95  491.45  311.99  491.54
  312.95  491.58  313.55  491.69  314.17  491.72  314.67  491.74  315.28  491.76
  315.81  491.89  318.69  492.13  319.15  492.15  319.63  492.19  320.82  492.24
  321.25  492.28  321.99   492.3  322.35  492.34  323.62  492.46  323.94  492.47
  324.58  492.57  325.38   492.6  325.55  492.63  325.82  492.64  328.76  492.56
  328.97  492.58  329.22  492.59  331.41  492.75   331.5  492.75  332.43  492.78
  332.53  492.79  334.09  492.83  334.15  492.83  336.41   492.9  341.15  492.53
  343.57  492.26   345.8   492.1  347.27  491.99  348.49  491.95  350.59  491.78
  351.53   491.7  352.25  491.68  352.87  491.66  353.99  491.56  354.78  491.47
  355.12  491.44  355.48  491.41  355.75  491.41  356.23  491.37  356.48  491.35
  356.67  491.33  357.01   491.3  357.19  491.28  357.48  491.24   357.6  491.22
  357.74  491.22  357.85  491.21  358.05   491.2  358.16  491.17  358.25  491.17
  358.41  491.15  358.58  491.15  358.64  491.16  358.78  491.13  358.84  491.14
  358.95  491.13  359.01  491.14  359.11  491.12  359.16  491.11  359.21   491.1
  359.29  491.09  359.33  491.09  359.38  491.08  359.42  491.08  359.49  491.08
  359.53  491.07  359.59  491.07  359.62  491.07  359.65  491.07  359.71  491.06
  359.74  491.05  359.77  491.05  359.82  491.05  359.87  491.04  359.91  491.04
  359.93  491.04  359.96  491.04  359.98  491.03     360  491.03  360.02  491.04
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BR U #Mann= 3
       0     .06  171.36    .035  470.76     .06
BR U Banks=171.36,470.76
BR D #Sta/Elev= 488
       0  541.11     .62  541.18    3.22  538.26    3.54  537.91    4.02  537.81
   18.15  534.53   20.56  534.13   25.88  533.44    28.9  533.04    30.2  532.86
   30.88  532.62   31.09  532.55   32.05   532.2   32.76  531.94   33.64  531.62
   35.33     531   38.48  529.84   39.06  529.64   42.42  528.42   48.08   526.4
   48.92  526.06   52.18  525.84   55.34  525.62   55.68  525.59   57.36  525.48
   58.93  525.37   60.35  525.28   60.85  525.24    62.1  525.15   79.67   524.4
  100.61  523.52  104.26  523.54  105.19  523.52  106.13  523.52  109.92  523.54
  110.86  523.56  111.79   523.6   113.8  523.79  115.77   524.1  119.76  524.12
  161.75  524.12  162.94  524.15   166.6  524.29  167.26  524.32  171.36  524.36
  176.35  521.75  177.24  521.31     190  514.62  192.51  513.44   195.7  511.92
  199.96   509.8  202.37  508.55  205.25  507.05  208.74  505.21  213.03  502.94
   214.4  502.23  216.12  501.27  232.15  498.43  232.67  498.34  233.17  498.22
  233.76  498.12  234.33  497.99     235  497.87  235.66  497.76  236.43  497.56
  237.18  497.36  237.65  497.24  238.51  497.08  239.52  496.86  240.52  496.63
  241.72  496.37  242.92  496.14  244.38  495.83  245.84  495.45  257.74  493.09
  259.36  492.85  260.94  492.48  263.71  491.96  265.65  491.51  267.89  491.16
  270.19  490.64  272.85  490.13  275.61   489.6  278.83  488.99  280.34   488.7
  280.35   488.7   280.4   488.7  281.17  488.76  282.73  488.86  284.12  488.95
  284.18  488.97  284.25  488.97  284.37  488.98  285.84  489.08  285.93  489.09
  286.04  489.09  286.16   489.1  286.32  489.12  286.44  489.14  286.65  489.16
  287.02  489.18     302  490.86  302.28  490.88  303.22  490.92  304.24  490.97
  304.92  491.05  306.09  491.16  306.27  491.17  306.66  491.15  307.42  491.29
  308.74   491.3   309.5  491.38  310.39  491.42  310.95  491.45  311.99  491.54
  312.95  491.58  313.55  491.69  314.17  491.72  314.67  491.74  315.28  491.76
  315.81  491.89  318.69  492.13  319.15  492.15  319.63  492.19  320.82  492.24
  321.25  492.28  321.99   492.3  322.35  492.34  323.62  492.46  323.94  492.47
  324.58  492.57  325.38   492.6  325.55  492.63  325.82  492.64  328.76  492.56
  328.97  492.58  329.22  492.59  331.41  492.75   331.5  492.75  332.43  492.78
  332.53  492.79  334.09  492.83  334.15  492.83  336.41   492.9  341.15  492.53
  343.57  492.26   345.8   492.1  347.27  491.99  348.49  491.95  350.59  491.78
  351.53   491.7  352.25  491.68  352.87  491.66  353.99  491.56  354.78  491.47
  355.12  491.44  355.48  491.41  355.75  491.41  356.23  491.37  356.48  491.35
  356.67  491.33  357.01   491.3  357.19  491.28  357.48  491.24   357.6  491.22
  357.74  491.22  357.85  491.21  358.05   491.2  358.16  491.17  358.25  491.17
  358.41  491.15  358.58  491.15  358.64  491.16  358.78  491.13  358.84  491.14
  358.95  491.13  359.01  491.14  359.11  491.12  359.16  491.11  359.21   491.1
  359.29  491.09  359.33  491.09  359.38  491.08  359.42  491.08  359.49  491.08
  359.53  491.07  359.59  491.07  359.62  491.07  359.65  491.07  359.71  491.06
  359.74  491.05  359.77  491.05  359.82  491.05  359.87  491.04  359.91  491.04
  359.93  491.04  359.96  491.04  359.98  491.03     360  491.03  360.02  491.04
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BR D #Mann= 3
       0     .06  171.36    .035  470.76     .06
BR D Banks=171.36,470.76
BC Design=,, 0 ,, 0 ,,13,940.26,940.26,28,1.167
BC Use User HTab Curves=0
BC User HTab FreeFlow(D)= 0