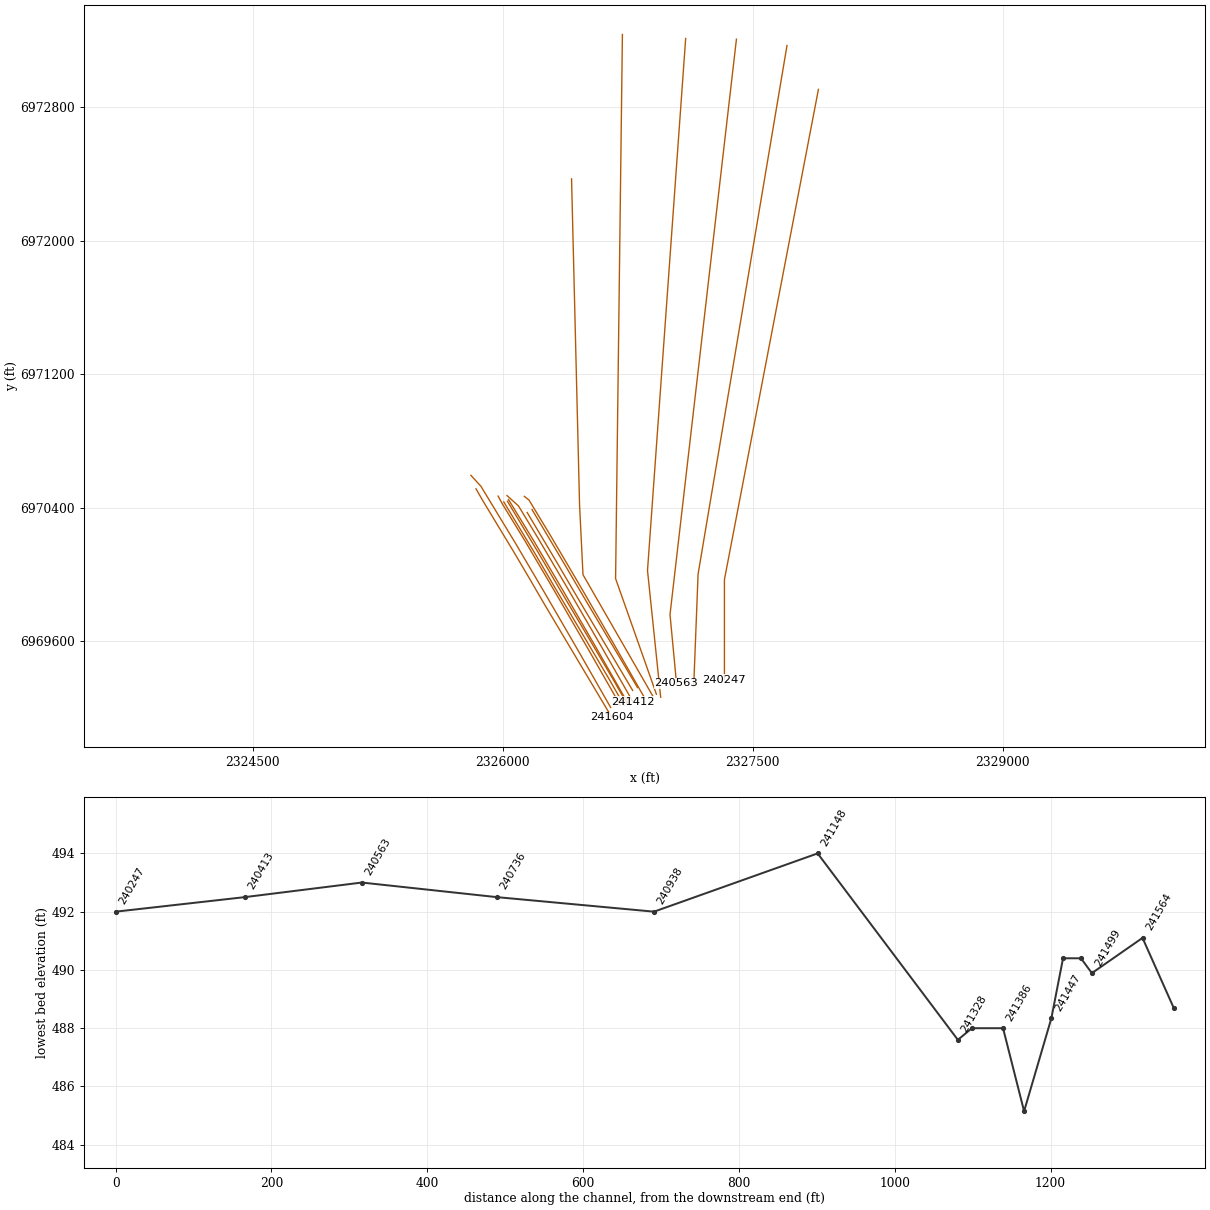
HEC-RAS study CDC_Consolidated_Model.prj: Upper Trinity CDC Consolidated Model

--- CDC_Consolidated_Model.g03 (geometry) --- (continued)

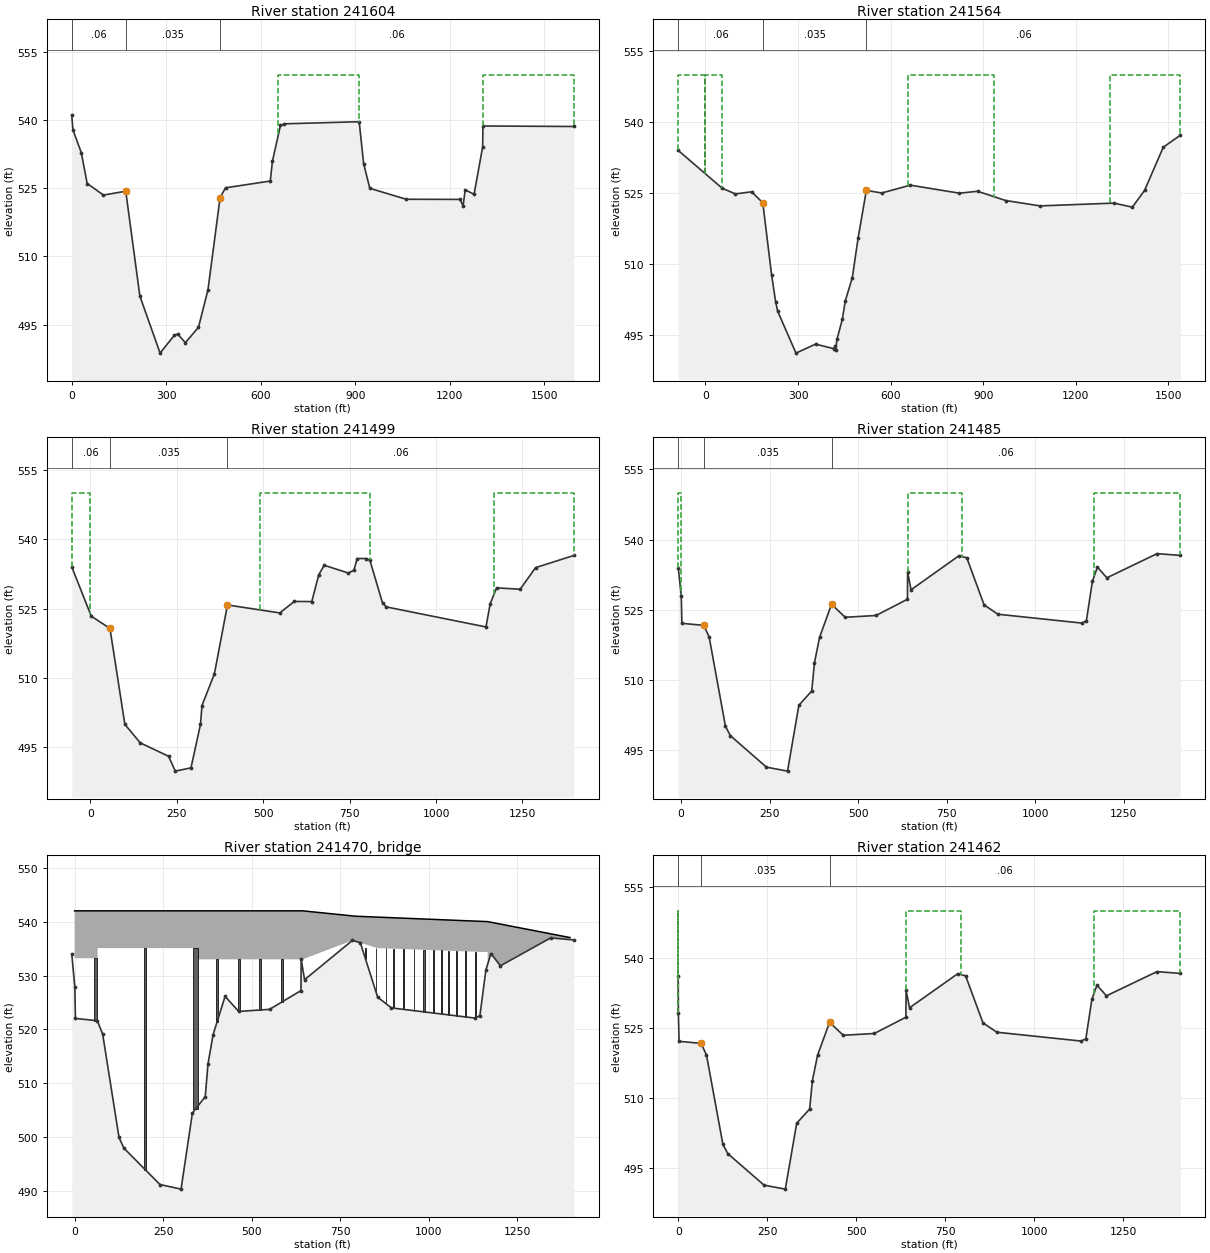
Type RM Length L Ch R = 1 ,241604  ,40,40,39
BEGIN DESCRIPTION:
This cross section corresponds to cross section 241482.4 of the non-georeferenced CDC model which was the source of this model.
Downstream of BNSF Railroad.
Ineffective flow in LOB and ROB due to railroad bridges.
Cross-section generated from ground points along centerline of railroad.
END DESCRIPTION:
XS GIS Cut Line= 6
 2325839.6555956 6970512.6857874 2325879.2703837 6970443.7563075
 2326069.3656487  6970129.249132 2326153.6758523 6969986.1538502
 2326254.9072632 6969812.2829904 2326653.7630855 6969142.7748676
#Sta/Elev= 30
       0  541.11    3.54  537.91    30.2  532.86   48.92  526.06  100.61  523.52
  171.36  524.36  216.12  501.27  280.34   488.7  325.55  492.63  336.41   492.9
  360.53  490.99  402.23   494.4  432.34  502.67  470.76  522.96  487.94  525.11
  630.12  526.61  636.85  530.96   662.4  538.86  674.61  539.21  912.26  539.67
  926.37  530.45  945.92     525 1061.74  522.59 1232.04  522.56 1242.17  521.16
 1248.68  524.67 1276.91  523.69  1304.2  534.14 1305.08  538.73 1593.59  538.62
#Mann= 3 ,0,0
       0     .06       0  171.36    .035       0  470.76     .06       0
#XS Ineff= 2 ,-1
     656  912.26     550 1305.08 1593.59     550
Permanent Ineff=
       F       F
Bank Sta=171.36,470.76
XS Rating Curve= 0 ,0
Exp/Cntr=0.5,0.3

Type RM Length L Ch R = 1 ,241564  ,65,65,64
BEGIN DESCRIPTION:
This cross section corresponds to cross section 241442.8 of the non-georeferenced CDC model which was the source of this model.
END DESCRIPTION:
XS GIS Cut Line= 6
     2325809.171     6970593.641 2325869.0113824 6970528.2399662
  2326077.177092 6970185.1824423 2326251.4428279 6969889.0853619
 2326449.8836431 6969547.0256586 2326647.4553367 6969201.4764307
#Sta/Elev= 30
     -88     534   54.29     526   97.02   524.8  149.99  525.24  185.88  522.92
  214.32  507.72  227.43     502  233.88     500  293.38   491.1  356.79  493.01
  415.84  492.04   419.8   492.6  421.76   491.8  426.22     494  443.59  498.27
   453.1  502.12  475.88  507.08   494.7  515.46  521.35  525.54  571.17  524.99
  663.53  526.65  822.89  524.95  881.39  525.36  972.46   523.4 1083.85  522.26
 1323.39  522.85 1382.91  521.99 1422.61  525.54 1483.17  534.68 1538.35  537.22
#Mann= 3 ,-1,0
     -88     .06       0  185.88    .035       0  521.35     .06       0
#XS Ineff= 4 ,-1
     -88       0     550       0    55.1     550  656.81  933.36     550
 1311.75 1538.35     550
Permanent Ineff=
       F       F       F       F
Bank Sta=185.88,521.35
XS Rating Curve= 0 ,0
Exp/Cntr=0.3,0.1

Type RM Length L Ch R = 1 ,241499  ,14,14,19
BEGIN DESCRIPTION:
This cross section corresponds to cross section 241377.9 of the non-georeferenced CDC model which was the source of this model.
END DESCRIPTION:
XS GIS Cut Line= 6
     2325972.365     6970468.988 2325998.2336259 6970421.3467627
 2326136.1601269 6970195.9293995 2326310.4852368 6969899.7313315
 2326508.9596281 6969557.6138097 2326705.0635252 6969214.6085767
#Sta/Elev= 30
     -54     534    2.36  523.36   56.49  520.71   99.59     500  144.03     496
  226.09   493.1  245.52  489.89  290.88   490.6  318.43     500  322.73  504.06
  358.63  510.89  396.46  525.78  547.73  524.06  589.84  526.54  640.43  526.51
  660.57   532.3  676.38  534.35   745.9  532.69  762.17  533.26  771.78  535.81
  797.63  535.81  808.49  535.44  844.99  526.22  855.94  525.36 1144.42  521.03
 1156.38     526 1175.11  529.48  1243.3  529.17 1287.76  533.84 1398.58  536.47
#Mann= 3 ,-1,0
     -54     .06       0   56.49    .035       0  396.46     .06       0
#XS Ineff= 3 ,-1
     -54       0     550  491.98  807.38     550 1166.94 1398.58     550
Permanent Ineff=
       F       F       F
Bank Sta=56.49,396.46
XS Rating Curve= 0 ,0
Exp/Cntr=0.5,0.3

Type RM Length L Ch R = 1 ,241485  ,23,23,25
BEGIN DESCRIPTION:
This cross section corresponds to cross section 241363.7 of the non-georeferenced CDC model which was the source of this model.
Upstream of Burlington Northern Railroad.
Copy of cross-section 241340.8
END DESCRIPTION:
XS GIS Cut Line= 6
      2326006.35     6970434.093   2326195.51224 6970121.0950564
 2326318.3897599 6969910.8896288  2326489.215951 6969623.3450004
 2326639.8925694 6969368.35367022326728.46938093 6969213.5156718
#Sta/Elev= 30
      -8     534     .65  527.85     2.3  522.05   64.13  521.62   79.32  519.13
  125.41     500   139.2     498  241.17  491.25  300.73   490.4  332.73   504.5
  369.07  507.55  376.82  513.62   391.3  519.06  425.03  526.13  463.61  523.35
  550.66  523.73  639.42  527.21     640     533   649.6  529.23  784.83  536.52
  807.16  536.08     856     526  894.94     524 1131.59  522.11 1144.88  522.58
 1161.81  531.02 1176.07  534.08 1202.75   531.8 1344.75  536.98 1410.23   536.6
#Mann= 3 ,0,0
      -8     .06       0   64.13    .035       0  425.03     .06       0
#XS Ineff= 3 ,-1
     640  793.75     550 1166.94 1410.23     550      -8       0     550
Permanent Ineff=
       F       F       F
Bank Sta=64.13,425.03
XS Rating Curve= 0 ,0
Exp/Cntr=0.5,0.3

Type RM Length L Ch R = 3 ,241470  ,,,
BEGIN DESCRIPTION:
Union Pacific Railroad
Two bridges: West Fork channel bridge, and ROB relief bridge.  West Fork bridge: data from 1975 USACE field survey, Fort Worth Floodway as-built plans, low chord elev. 533.1, total bridge length 640 feet.
Relief bridge: Structure designed by EA Inc. in 1995. Minimum low chord elev. 534.24, bridge length 353 feet.
Note: Internal bridge cross-sections modified to represent channel geometry under bridges.
END DESCRIPTION:
Node Name=UP RR
Bridge Culvert--1,0,-1,-1, 0
Deck Dist Width WeirC Skew NumUp NumDn MinLoCord MaxHiCord MaxSubmerge Is_Ogee
3.5,16,2.6,0, 13, 13, , , 0.95, 0, 0,0,,
       0      65      65     342     342     640     640  643.92  793.75  793.75
 1166.83 1166.83  1399.5
     542     542     542     542     542     542     542     542     541     541
     540     540  537.04
   533.2   533.2  535.09  535.09     533     533     533                  535.23
  534.34
       0      65      65     342     342     640     640  643.92  793.75  793.75
 1166.83 1166.83 1410.23
     542     542     542     542     542     542     542     542     541     541
     540     540  537.04
   533.2   533.2  535.09  535.09     533     533     533                  535.23
  534.34
Pier Skew, UpSta & Num, DnSta & Num=  ,60, 2 ,60, 2 , 0 , 0 , 0 ,,
       9       8
     450     540
       9       8
     450     540
Pier Skew, UpSta & Num, DnSta & Num=  ,200, 2 ,200, 2 , 0 , 0 , 0 ,,
       6       6
     450     540
       6       6
     450     540
Pier Skew, UpSta & Num, DnSta & Num=  ,342, 4 ,342, 4 , 0 , 0 , 0 ,,
    13.5    13.5     8.5     8.5
     450     511     513     540
    13.5    13.5     8.5     8.5
     450     511     513     540
Pier Skew, UpSta & Num, DnSta & Num=  ,402.5, 2 ,402.5, 2 , 0 , 0 , 0 ,,
     5.5     5.5
     450     541
     5.5     5.5
     450     541
Pier Skew, UpSta & Num, DnSta & Num=  ,465, 2 ,465, 2 , 0 , 0 , 0 ,,
     5.5     5.5
     450     540
     5.5     5.5
     450     540
Pier Skew, UpSta & Num, DnSta & Num=  ,525, 2 ,525, 2 , 0 , 0 , 0 ,,
     5.5     5.5
     450     541
     5.5     5.5
     450     541
Pier Skew, UpSta & Num, DnSta & Num=  ,585, 2 ,585, 2 , 0 , 0 , 0 ,,
     5.5     5.5
     450     541
     5.5     5.5
     450     541
Pier Skew, UpSta & Num, DnSta & Num=  ,821.75, 2 ,821.75, 2 , 0 , 0 , 0 ,,
       2       2
     450     539
       2       2
     450     539
Pier Skew, UpSta & Num, DnSta & Num=  ,851.75, 2 ,851.75, 2 , 0 , 0 , 0 ,,
       2       2
     450     539
       2       2
     450     539
Pier Skew, UpSta & Num, DnSta & Num=  ,879.75, 2 ,879.75, 2 , 0 , 0 , 0 ,,
       2       2
     450     539
       2       2
     450     539
Pier Skew, UpSta & Num, DnSta & Num=  ,901.75, 2 ,901.75, 2 , 0 , 0 , 0 ,,
       2       2
     450     539
       2       2
     450     539
Pier Skew, UpSta & Num, DnSta & Num=  ,929.75, 2 ,929.75, 2 , 0 , 0 , 0 ,,
       2       2
     450     539
       2       2
     450     539
Pier Skew, UpSta & Num, DnSta & Num=  ,958.75, 2 ,958.75, 2 , 0 , 0 , 0 ,,
       2       2
     450     539
       2       2
     450     539
Pier Skew, UpSta & Num, DnSta & Num=  ,986.75, 2 ,986.75, 2 , 0 , 0 , 0 ,,
       4       4
     450     539
       4       4
     450     539
Pier Skew, UpSta & Num, DnSta & Num=  ,1014.75, 2 ,1014.75, 2 , 0 , 0 , 0 ,,
       2       2
     450     539
       2       2
     450     539
Pier Skew, UpSta & Num, DnSta & Num=  ,1036.75, 2 ,1036.75, 2 , 0 , 0 , 0 ,,
       2       2
     450     539
       2       2
     450     539
Pier Skew, UpSta & Num, DnSta & Num=  ,1056.75, 2 ,1056.75, 2 , 0 , 0 , 0 ,,
       2       2
     450     539
       2       2
     450     539
Pier Skew, UpSta & Num, DnSta & Num=  ,1078.75, 2 ,1078.75, 2 , 0 , 0 , 0 ,,
       2       2
     450     539
       2       2
     450     539
Pier Skew, UpSta & Num, DnSta & Num=  ,1103.75, 2 ,1103.75, 2 , 0 , 0 , 0 ,,
       2       2
     450     539
       2       2
     450     539
Pier Skew, UpSta & Num, DnSta & Num=  ,1131.75, 2 ,1131.75, 2 , 0 , 0 , 0 ,,
       2       2
     450     539
       2       2
     450     539
Abutment Skew #Up #Dn= , 2 , 2
 1144.42 1166.94
  521.03  534.28
 1144.42 1166.94
  522.58  534.28
BR Coef=-1 , 0 , 0 ,, 0 ,,,0.8,-1,,0,
WSPro=,,,, 1 ,,,, 0 ,,,, 0 ,,,,-1 ,-1 ,-1 , 0 , 0 , 0 , 0 , 0
BR U #Sta/Elev= 499
       0  528.43     .46  528.06     .65  527.85     1.2     526    1.32  525.46
    1.56     524    1.71  523.66     2.3  522.05    3.61  522.03    4.65     522
   29.84     522   33.14  521.88   34.74   521.8   51.77  521.74   53.98   521.5
   60.96  521.49   62.91  521.55   64.13  521.62   65.84  521.39   68.15  521.02
   69.28  520.94   71.54  520.57   75.28     520   75.45  519.97   78.68  519.28
   79.32  519.13   79.68  518.99    80.1  518.81   82.07     518   84.71  516.87
   86.83     516   91.83  513.99   94.24  513.01   96.75     512  100.45  510.56
   103.6  509.34  106.41  508.23  109.85  506.77  111.68     506  113.64  505.14
  117.88  503.33  120.11  502.36  122.23  501.38   123.3   500.9  125.41     500
  128.43  499.59  131.39  499.18   139.2     498  144.56  497.49  157.97     496
  164.59  495.42  164.86   495.4  165.13  495.32  167.15  495.14  167.38  495.19
  168.46  494.94  170.21  494.76  170.69  494.82  171.41  494.78  174.86  494.68
  176.22  494.56  185.98  494.27  186.62  494.22  188.52  494.17  190.46  494.13
  191.16  494.09  195.15     494  196.06     494  204.35  493.83  209.59  493.74
  221.48  493.52  222.65  493.42  223.86  493.48  225.24  493.46  228.66   493.4
  228.98  493.25  229.22  493.31  229.77  493.21  229.94   493.1  230.12  493.07
  230.27  492.97  230.83  492.74  231.19   492.7  233.84  492.56  234.19  492.48
  234.81  492.43   235.2  492.36  235.44  492.39  235.64  492.33  236.26  492.32
  236.47  492.24  236.61  492.26  240.65  492.15   241.1  492.07  241.17  491.25
  264.93  491.69  265.52  491.67  265.89   491.6  266.88  491.56  267.29  491.55
  267.64  491.59  268.46  491.56  268.79   491.6  269.84  491.56  270.54  491.53
  271.43   491.5  271.74  491.44  272.09  491.43  273.48  491.38  274.41  491.35
  275.28  491.28  275.54  491.23   276.5   491.2  276.75  491.15  277.62  491.12
  278.32   491.1  278.83  491.05  279.16  491.04  279.38     491  279.85  490.99
  281.59  490.94  281.99  490.96  282.76  490.94  282.94  490.93  284.09   490.9
  284.64  490.88  285.38  490.78  285.54  490.75  285.73  490.75  286.55   490.8
  286.93  490.71  287.08  490.71  287.46  490.77   287.6  490.75  289.28  490.71
  289.95  490.69  290.18  490.66  291.21  490.64  291.52  490.59  291.62  490.59
  291.99  490.52  292.07  490.48  300.73   490.4  304.09   491.9  304.47  492.16
  304.84  492.33  306.56  493.08  307.03  493.29   307.5  493.42  308.45  493.84
  308.86  494.03  309.33  494.23  309.71  494.48  310.08  494.64  310.44  494.87
  310.79  495.02  311.18   495.2  311.51  495.34  311.82  495.48  312.48  495.64
  312.77  495.77  313.31  495.95  313.63  496.09  314.13  496.37  319.71   498.8
  320.44  499.13  320.65  499.22  320.86  499.28  321.28   499.5  321.47  499.58
  322.02  499.83  322.34  499.93  322.66  500.08  322.96  500.21   323.1  500.24
  323.48  500.42  323.62  500.48  332.73   504.5  332.86  504.51  350.36   505.2
   351.9  505.23  353.06  505.27  353.73  505.29  354.43  505.32  355.18  505.37
  357.93  505.67  358.22   505.7  362.67  506.44  369.07  507.55  370.47  508.59
  374.14  511.51  376.42  513.28  376.82  513.62     384   516.4   391.3  519.06
  401.38  522.23  402.75  522.68  405.12  523.45   408.5  523.96     409  523.91
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BR U #Mann= 3
       0     .06   64.13    .035  425.03     .06
BR U Banks=64.13,425.03
BR D #Sta/Elev= 499
       0  528.43     .46  528.06     .65  527.85     1.2     526    1.32  525.46
    1.56     524    1.71  523.66     2.3  522.05    3.61  522.03    4.65     522
   29.84     522   33.14  521.88   34.74   521.8   51.77  521.74   53.98   521.5
   60.96  521.49   62.91  521.55   64.13  521.62   65.84  521.39   68.15  521.02
   69.28  520.94   71.54  520.57   75.28     520   75.45  519.97   78.68  519.28
   79.32  519.13   79.68  518.99    80.1  518.81   82.07     518   84.71  516.87
   86.83     516   91.83  513.99   94.24  513.01   96.75     512  100.45  510.56
   103.6  509.34  106.41  508.23  109.85  506.77  111.68     506  113.64  505.14
  117.88  503.33  120.11  502.36  122.23  501.38   123.3   500.9  125.41     500
  128.43  499.59  131.39  499.18   139.2     498  144.56  497.49  157.97     496
  164.59  495.42  164.86   495.4  165.13  495.32  167.15  495.14  167.38  495.19
  168.46  494.94  170.21  494.76  170.69  494.82  171.41  494.78  174.86  494.68
  176.22  494.56  185.98  494.27  186.62  494.22  188.52  494.17  190.46  494.13
  191.16  494.09  195.15     494  196.06     494  204.35  493.83  209.59  493.74
  221.48  493.52  222.65  493.42  223.86  493.48  225.24  493.46  228.66   493.4
  228.98  493.25  229.22  493.31  229.77  493.21  229.94   493.1  230.12  493.07
  230.27  492.97  230.83  492.74  231.19   492.7  233.84  492.56  234.19  492.48
  234.81  492.43   235.2  492.36  235.44  492.39  235.64  492.33  236.26  492.32
  236.47  492.24  236.61  492.26  240.65  492.15   241.1  492.07  241.17  491.25
  264.93  491.69  265.52  491.67  265.89   491.6  266.88  491.56  267.29  491.55
  267.64  491.59  268.46  491.56  268.79   491.6  269.84  491.56  270.54  491.53
  271.43   491.5  271.74  491.44  272.09  491.43  273.48  491.38  274.41  491.35
  275.28  491.28  275.54  491.23   276.5   491.2  276.75  491.15  277.62  491.12
  278.32   491.1  278.83  491.05  279.16  491.04  279.38     491  279.85  490.99
  281.59  490.94  281.99  490.96  282.76  490.94  282.94  490.93  284.09   490.9
  284.64  490.88  285.38  490.78  285.54  490.75  285.73  490.75  286.55   490.8
  286.93  490.71  287.08  490.71  287.46  490.77   287.6  490.75  289.28  490.71
  289.95  490.69  290.18  490.66  291.21  490.64  291.52  490.59  291.62  490.59
  291.99  490.52  292.07  490.48  300.73   490.4  304.09   491.9  304.47  492.16
  304.84  492.33  306.56  493.08  307.03  493.29   307.5  493.42  308.45  493.84
  308.86  494.03  309.33  494.23  309.71  494.48  310.08  494.64  310.44  494.87
  310.79  495.02  311.18   495.2  311.51  495.34  311.82  495.48  312.48  495.64
  312.77  495.77  313.31  495.95  313.63  496.09  314.13  496.37  319.71   498.8
  320.44  499.13  320.65  499.22  320.86  499.28  321.28   499.5  321.47  499.58
  322.02  499.83  322.34  499.93  322.66  500.08  322.96  500.21   323.1  500.24
  323.48  500.42  323.62  500.48  332.73   504.5  332.86  504.51  350.36   505.2
   351.9  505.23  353.06  505.27  353.73  505.29  354.43  505.32  355.18  505.37
  357.93  505.67  358.22   505.7  362.67  506.44  369.07  507.55  370.47  508.59
  374.14  511.51  376.42  513.28  376.82  513.62     384   516.4   391.3  519.06
  401.38  522.23  402.75  522.68  405.12  523.45   408.5  523.96     409  523.91
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BR D #Mann= 3
       0     .06   64.13    .035  425.03     .06
BR D Banks=,425.03
BC Design=,, 0 ,, 0 ,,13,812,812,25,2
BC Use User HTab Curves=0
BC User HTab FreeFlow(D)= 0

Type RM Length L Ch R = 1 ,241462  ,15,15,17
BEGIN DESCRIPTION:
This cross section corresponds to cross section 241340.8 of the non-georeferenced CDC model which was the source of this model.
Downstream of Burlington Northern Railroad.
Ineffective flow in LOB and ROB due to railroad bridges.
Cross-section generated from ground points along centerline of railroad.
END DESCRIPTION:
XS GIS Cut Line= 6
     2326028.225     6970438.042 2326212.7107422 6970131.3042769
 2326335.6204122 6969921.0438829 2326506.4224906 6969633.5397014
  2326657.182855 6969378.4070663 2326745.5348911 6969223.9616496
#Sta/Elev= 30
       0     536     .46  528.06     2.3  522.05   64.13  521.62   79.32  519.13
  125.41     500   139.2     498  241.17  491.25  300.73   490.4  332.73   504.5
  369.07  507.55  376.82  513.62   391.3  519.06  425.03  526.13  463.61  523.35
  550.66  523.73  639.42  527.21     640     533   649.6  529.23  784.83  536.52
  807.16  536.08     856     526  894.94     524 1131.59  522.11 1144.88  522.58
 1161.81  531.02 1176.07  534.08 1202.75   531.8 1344.75  536.98 1410.23   536.6
#Mann= 3 ,0,0
       0     .06       0   64.13    .035       0  425.03     .06       0
#XS Ineff= 3 ,-1
     640  793.75     550 1166.94 1410.23     550       0     .46     550
Permanent Ineff=
       F       F       F
Bank Sta=64.13,425.03
XS Rating Curve= 0 ,0
Exp/Cntr=0.5,0.3

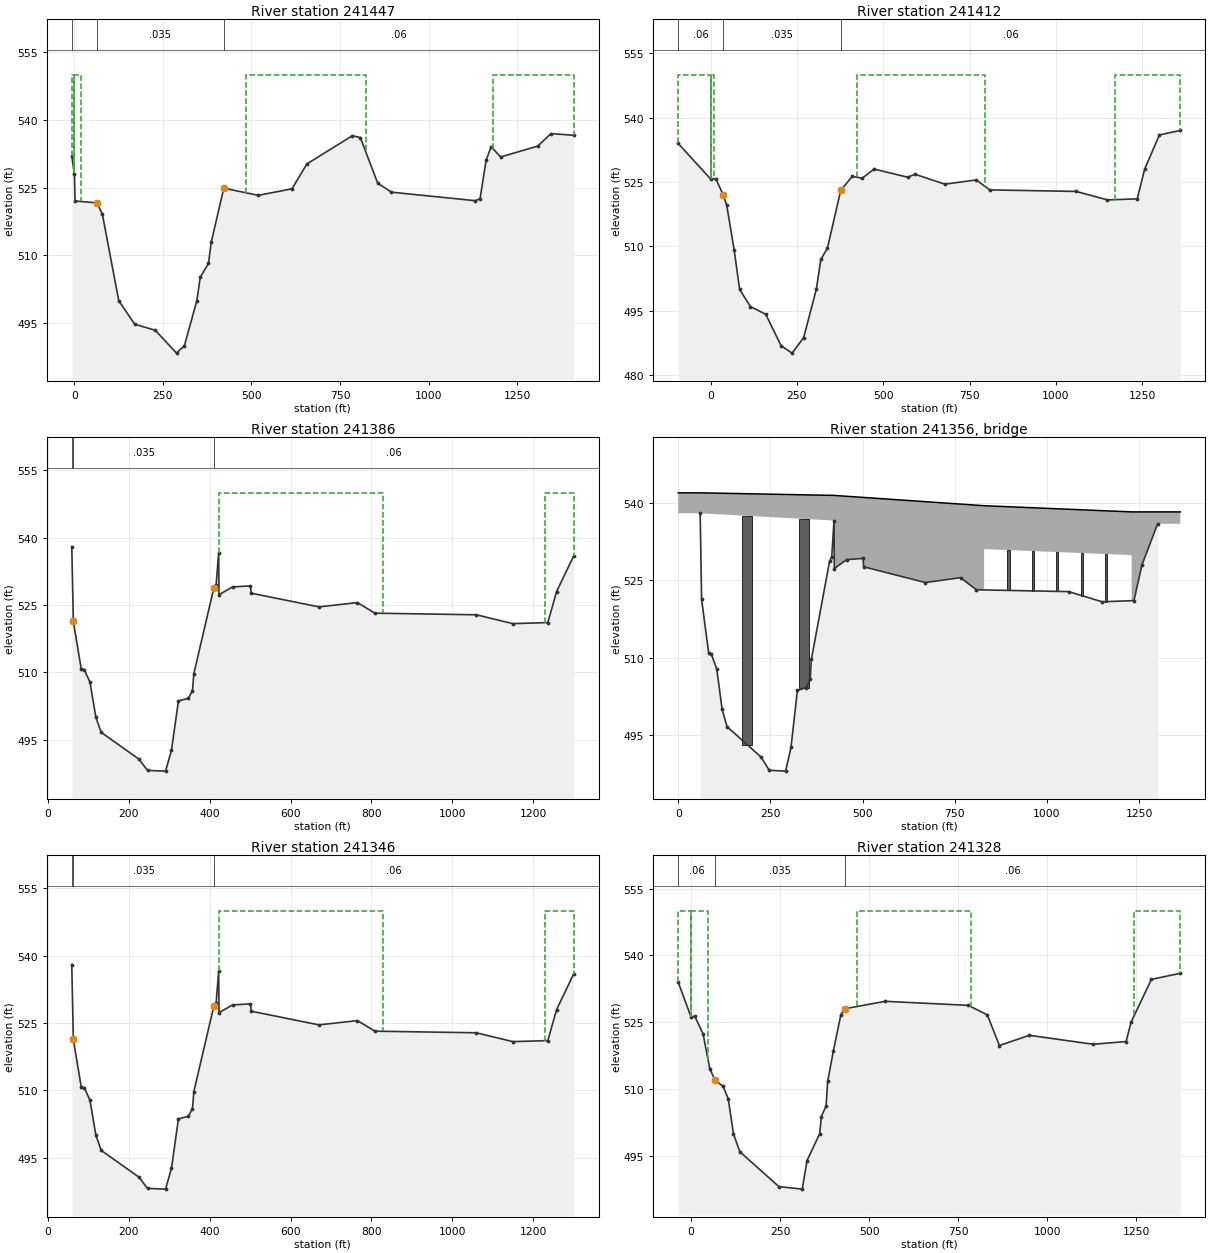
Type RM Length L Ch R = 1 ,241447  ,35,35,37
BEGIN DESCRIPTION:
This cross section corresponds to cross section 241326.1 of the non-georeferenced CDC model which was the source of this model.
END DESCRIPTION:
XS GIS Cut Line= 6
2326034.320058596970448.77960806 2326186.5566152 6970199.9748705
 2326360.9410991 6969903.6758148 2326559.4490666 6969561.5004747
 2326721.7830872 6969277.02968342326750.659233346969226.97742408
#Sta/Elev= 30
      -7     532     .46  528.06     2.3  522.05   64.13  521.62   79.32  519.13
  125.41     500  170.21  494.76  228.66   493.4   288.5  488.34  310.87     490
  345.98     500  355.38  505.16   378.7  508.22  386.35  512.89  421.89  524.89
  519.19   523.3  614.41  524.75  656.12  530.25  784.83  536.52  807.16  536.08
     856     526  894.94     524 1131.59  522.11 1144.88  522.58 1161.81  531.02
 1176.07  534.08 1202.75   531.8 1307.56  534.21 1344.75  536.98 1409.39   536.6
#Mann= 3 ,-1,0
      -7     .06       0   64.13    .035       0  421.89     .06       0
#XS Ineff= 4 ,-1
      -7       0     550       0   18.67     550  484.53  823.97     550
 1180.86 1409.39     550
Permanent Ineff=
       F       F       F       F
Bank Sta=64.13,421.89
XS Rating Curve= 0 ,0
Exp/Cntr=0.3,0.1

Type RM Length L Ch R = 1 ,241412  ,27,27,35
BEGIN DESCRIPTION:
This cross section corresponds to cross section 241290.9 of the non-georeferenced CDC model which was the source of this model.
END DESCRIPTION:
XS GIS Cut Line= 6
     2326025.838     6970472.113 2326094.5699209 6970409.9931015
  2326216.645373 6970208.7066112  2326391.089231 6969912.3065678
 2326589.6307746 6969570.0734093 2326781.0615791 6969235.1679429
#Sta/Elev= 30
     -94     534       0  525.71   14.81  525.81   36.49     522   46.57  519.58
   67.94  509.25   83.87     500  115.12     496  159.58   494.2  203.97  486.88
  235.95  485.15  269.43  488.78  306.03     500  319.24  506.97  338.24  509.62
  376.83  523.08  410.26  526.33  439.11  525.92  473.46  528.04  570.41  526.15
  592.34  526.83  678.47  524.52  769.67  525.51  808.42  523.19  1058.9  522.83
 1149.36  520.86 1235.87  521.09 1257.41     528 1300.09     536 1360.75  537.04
#Mann= 3 ,-1,0
     -94     .06       0   36.49    .035       0  376.83     .06       0
#XS Ineff= 4 ,-1
     -94       0     550       0    9.98     550  423.67  794.04     550
 1170.73 1360.75     550
Permanent Ineff=
       F       F       F       F
Bank Sta=36.49,376.83
XS Rating Curve= 0 ,0
Exp/Cntr=0.5,0.3

Type RM Length L Ch R = 1 ,241386  ,40,40,43
BEGIN DESCRIPTION:
This cross section corresponds to cross section 241264.2 of the non-georeferenced CDC model which was the source of this model.
Upstream of Union Pacific Railroad.
Copy of cross-section 241224.7
Ineffective flow in LOB and ROB due to railroad bridges.
END DESCRIPTION:
XS GIS Cut Line= 6
 2326146.7868138 6970370.5437384 2326146.8589886 6970370.4216123
 2326330.8986218 6970060.9470981 2326451.3906802 6969855.3250079
 2326777.5349048 6969306.5119966 2326779.4097597 6969303.3571201
#Sta/Elev= 30
   59.48  538.03   63.34  521.34   82.74  510.83   90.12  510.63  104.44  507.82
  119.05     500  132.26  496.63  225.31  490.68  246.61  488.16   291.2     488
  305.82  492.62  323.05  503.65  347.56  504.22  357.78  505.93  361.09  509.71
  410.52  528.78  416.24  529.56  422.48  536.62  423.24   527.3  456.68  529.04
  501.11  529.27  502.79  527.64  670.31  524.59  765.45  525.54  808.42  523.19
  1058.9  522.83 1149.36  520.86 1235.87  521.09 1257.41     528 1300.09     536
#Mann= 3 ,0,0
   59.48     .06       0   63.34    .035       0  410.52     .06       0
#XS Ineff= 2 ,-1
  422.48  829.48     550 1229.48 1300.09     550
Permanent Ineff=
       F       F
Bank Sta=63.34,410.52
XS Rating Curve= 0 ,0
Exp/Cntr=0.5,0.3

Type RM Length L Ch R = 3 ,241356  ,,,
BEGIN DESCRIPTION:
Burlington Northern Railroad
Two bridges: West Fork channel bridge, and ROB relief bridge.  West Fork bridge: data from 1975 USACE field survey, Fort Worth Floodway as-built plans, minimum low chord elev. 536.62, bridge length 363 feet.  Relief bridge: data from USACE 1949 field survey, top of rail and low chord refined by EA Inc. 1995 field survey, USACE May 2007 field measurement.  Bridge length 400 feet.  Note:  West Fork bridge internal bridge cross-sections modified to represent geo. under bridges.
END DESCRIPTION:
Node Name=BNSF Railroad
Bridge Culvert--1,0,-1,-1, 0
Deck Dist Width WeirC Skew NumUp NumDn MinLoCord MaxHiCord MaxSubmerge Is_Ogee
9.8,20,2.6,0, 10, 10, , , 0.95, 0, 0,0,,
       0   59.48   59.48  422.48  422.48  829.48  829.48 1229.48 1229.48 1361.48
     542     542     542   541.5   541.5   539.5   539.5   538.3   538.3   538.3
                  538.03  536.62     450     450  531.08  529.92     450     450
       0   59.48   59.48  422.48  422.48  829.48  829.48 1229.48 1229.48 1361.48
     542     542     542   541.5   541.5   539.5   539.5   538.3   538.3   538.3
                  538.03  536.62     450     450  531.08  529.92     450     450
Pier Skew, UpSta & Num, DnSta & Num=  ,186.48, 6 ,186.48, 6 , 0 , 0 , 0 ,,
      26      26      20      20      11     9.5
     450   506.4   509.2   510.2   512.5     540
      26      26      20      20      11     9.5
     450   506.4   509.2   510.2   512.5     540
Pier Skew, UpSta & Num, DnSta & Num=  ,341.48, 5 ,341.48, 5 , 0 , 0 , 0 ,,
      26      26      26    12.5      12
     450     450   505.6   507.6     540
      26      26      26    12.5      12
     450     450   505.6   507.6     540
Pier Skew, UpSta & Num, DnSta & Num=  ,894.98, 2 ,894.98, 2 , 0 , 0 , 0 ,,
       7     5.6
     520     531
       7     5.6
     520     531
Pier Skew, UpSta & Num, DnSta & Num=  ,961.98, 2 ,961.98, 2 , 0 , 0 , 0 ,,
       7     5.6
     520     531
       7     5.6
     520     531
Pier Skew, UpSta & Num, DnSta & Num=  ,1026.98, 2 ,1026.98, 2 , 0 , 0 , 0 ,,
       7     5.6
     520     531
       7     5.6
     520     531
Pier Skew, UpSta & Num, DnSta & Num=  ,1094.98, 2 ,1094.98, 2 , 0 , 0 , 0 ,,
       7     5.6
     520     531
       7     5.6
     520     531
Pier Skew, UpSta & Num, DnSta & Num=  ,1160, 2 ,1160, 2 , 0 , 0 , 0 ,,
       7     5.6
     520     531
       7     5.6
     520     531
BR Coef=-1 , 0 , 0 ,, 0 ,,,0.8,-1,,0,
WSPro=,,,, 1 ,,,, 0 ,,,, 0 ,,,,-1 ,-1 ,-1 , 0 , 0 , 0 , 0 , 0
BR U #Sta/Elev= 421
   59.48  538.03   63.25   521.7   63.34  521.34   64.72  520.65   79.23  513.12
      81  512.41   82.33  511.77   82.74  510.83   84.91  510.89   86.95  510.82
   87.49  510.75   88.77  510.74   89.16  510.69   90.12  510.63   91.55  510.37
    92.7  510.11   93.52  509.98    94.6  509.77   97.06  509.13   97.46  509.09
    98.8  508.81  100.02   508.6  102.09  508.15  102.58  508.08  102.92  507.98
  103.78  507.93  104.44  507.82   104.5  507.72  104.93  507.58  105.88  507.09
  107.89  506.08  109.39  505.35  110.81  504.64  113.05  503.48  114.12  502.95
  115.93     502  117.73  501.01  118.41  500.51  119.05     500  120.05  499.69
  125.35     498   126.3  497.78  127.54  497.57  132.26  496.63   136.8     496
  138.26     496   138.8  495.97  139.48  495.83  139.82  495.81  141.95  495.61
  143.35  495.56  143.77  495.46  145.49  495.46  146.83  495.39     147  495.32
  147.67  495.23  148.24   495.2     149  495.22  149.55  495.19  150.18   495.2
  151.04  494.93  152.85  494.84  153.38  494.89  154.51  494.83   154.8   494.9
  155.11  494.88  155.58  494.77  156.62   494.7  157.39  494.62  157.68  494.67
  158.47  494.58  158.86   494.6  162.18  494.38  163.53   494.3  164.38  494.21
  167.66     494  170.27  493.75  174.23  493.38  175.97  493.29   179.1  493.11
  188.87  492.57  193.76  492.31   198.7  491.89  203.54  491.64  208.32  491.37
  209.72   491.3  212.97  491.25   214.6  491.15  217.43  491.07  220.56  490.89
  222.78  490.85  225.31  490.68  226.97  490.52  228.25  490.42  232.12     490
  234.16   489.8     235  489.65  237.08  489.39  239.66     489  242.88  488.65
  243.76  488.53  245.33  488.41  246.61  488.16  247.73  488.14  248.33  488.22
  249.03  488.15  249.54  488.16  253.97  488.08   254.9  488.09  259.47  488.19
  259.85  488.18  264.39  488.19  269.68  488.13  270.73  488.06  271.12   488.1
  275.13  488.09  276.33  488.18  277.37   488.2  277.46  488.15  278.02  488.22
  278.74  488.23  281.19  488.21  281.48  488.24  283.22  488.09  287.95  488.07
   291.2     488  293.81  488.22  294.66  488.65  295.56     489  296.79   489.4
  298.61  490.12  300.58  490.73  301.23  490.83  301.78  491.05  302.38   491.3
  302.64  491.33  303.21  491.48   303.7  491.68  304.23  491.97  304.69  492.16
  305.18  492.36  305.82  492.62  323.05  503.65  338.63  503.66  347.56  504.22
  348.39  504.35  350.51  504.68  354.88  505.44  356.27  505.44  357.78  505.93
  358.73  506.92  361.09  509.71  368.81  512.52  377.43  516.02  387.21  519.77
  394.34  522.89  402.77   525.1  403.46  525.29  405.29  526.21  410.52  528.78
  411.85  529.01  416.24  529.56  422.48  536.62  423.24   527.3  423.96  527.35
  426.33  527.64  428.16  527.76  429.64  527.96   430.4  527.99  430.94  528.04
  436.07  528.22  437.26  528.29  438.14  528.32  438.71  528.29   441.4  528.35
  442.03  528.42  443.36  528.45  445.35  528.54  446.77  528.63  448.16  528.65
   448.9   528.7  449.56  528.71  451.62   528.8  453.98  528.92  456.68  529.04
   458.3  529.08  459.24  529.07  459.76   529.1  460.86   529.1  462.35  529.15
  464.72  529.21  467.51  529.27  471.07  529.31   473.3  529.31  475.56  529.29
  480.59  529.29  483.39  529.26  486.66  529.25  490.24  529.25  493.59  529.26
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BR U #Mann= 3
   59.48    .035  410.52     .06  475.56     .06
BR U Banks=63.34,410.52
BR D #Sta/Elev= 389
   59.48  538.03   63.25   521.7   63.34  521.34   64.72  520.65   79.23  513.12
      81  512.41   82.33  511.77   82.74  510.83   84.91  510.89   86.95  510.82
   87.49  510.75   88.77  510.74   89.16  510.69   90.12  510.63   91.55  510.37
    92.7  510.11   93.52  509.98    94.6  509.77   97.06  509.13   97.46  509.09
    98.8  508.81  100.02   508.6  102.09  508.15  102.58  508.08  102.92  507.98
  103.78  507.93  104.44  507.82   104.5  507.72  104.93  507.58  105.88  507.09
  107.89  506.08  109.39  505.35  110.81  504.64  113.05  503.48  114.12  502.95
  115.93     502  117.73  501.01  118.41  500.51  119.05     500  120.05  499.69
  125.35     498   126.3  497.78  127.54  497.57  132.26  496.63   136.8     496
  138.26     496   138.8  495.97  139.48  495.83  139.82  495.81  141.95  495.61
  143.35  495.56  143.77  495.46  145.49  495.46  146.83  495.39     147  495.32
  147.67  495.23  148.24   495.2     149  495.22  149.55  495.19  150.18   495.2
  151.04  494.93  152.85  494.84  153.38  494.89  154.51  494.83   154.8   494.9
  155.11  494.88  155.58  494.77  156.62   494.7  157.39  494.62  157.68  494.67
  158.47  494.58  158.86   494.6  162.18  494.38  163.53   494.3  164.38  494.21
  167.66     494  170.27  493.75  174.23  493.38  175.97  493.29   179.1  493.11
  188.87  492.57  193.76  492.31   198.7  491.89  203.54  491.64  208.32  491.37
  209.72   491.3  212.97  491.25   214.6  491.15  217.43  491.07  220.56  490.89
  222.78  490.85  225.31  490.68  226.97  490.52  228.25  490.42  232.12     490
  234.16   489.8     235  489.65  237.08  489.39  239.66     489  242.88  488.65
  243.76  488.53  245.33  488.41  246.61  488.16  247.73  488.14  248.33  488.22
  249.03  488.15  249.54  488.16  253.97  488.08   254.9  488.09  259.47  488.19
  259.85  488.18  264.39  488.19  269.68  488.13  270.73  488.06  271.12   488.1
  275.13  488.09  276.33  488.18  277.37   488.2  277.46  488.15  278.02  488.22
  278.74  488.23  281.19  488.21  281.48  488.24  283.22  488.09  287.95  488.07
   291.2     488  293.81  488.22  294.66  488.65  295.56     489  296.79   489.4
  298.61  490.12  300.58  490.73  301.23  490.83  301.78  491.05  302.38   491.3
  302.64  491.33  303.21  491.48   303.7  491.68  304.23  491.97  304.69  492.16
  305.18  492.36  305.82  492.62  323.05  503.65  338.63  503.66  347.56  504.22
  348.39  504.35  350.51  504.68  354.88  505.44  356.27  505.44  357.78  505.93
  358.73  506.92  361.09  509.71  368.81  512.52  377.43  516.02  387.21  519.77
  394.34  522.89  402.77   525.1  403.46  525.29  405.29  526.21  410.52  528.78
  411.85  529.01  416.24  529.56  422.48  536.62  423.24   527.3  423.96  527.35
  426.33  527.64  428.16  527.76  429.64  527.96   430.4  527.99  430.94  528.04
  436.07  528.22  437.26  528.29  438.14  528.32  438.71  528.29   441.4  528.35
  442.03  528.42  443.36  528.45  445.35  528.54  446.77  528.63  448.16  528.65
   448.9   528.7  449.56  528.71  451.62   528.8  453.98  528.92  456.68  529.04
   458.3  529.08  459.24  529.07  459.76   529.1  460.86   529.1  462.35  529.15
  464.72  529.21  467.51  529.27  471.07  529.31   473.3  529.31  475.56  529.29
  480.59  529.29  483.39  529.26  486.66  529.25  490.24  529.25  493.59  529.26
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BR D #Mann= 2
   59.48    .035  410.52     .06
BR D Banks=63.34,410.52
BC Design=,, 0 ,, 0 ,,,,,,
BC Use User HTab Curves=0
BC User HTab FreeFlow(D)= 0

Type RM Length L Ch R = 1 ,241346  ,18,18,22
BEGIN DESCRIPTION:
This cross section corresponds to cross section 241224.7 of the non-georeferenced CDC model which was the source of this model.
Downstream of Union Pacific Railroad.
Ineffective flow in LOB and ROB due to railroad bridges.
Cross-section generated from ground points along centerline of railroad.
END DESCRIPTION:
XS GIS Cut Line= 6
 2326176.0573526 6970387.8420164 2326176.1057502  6970387.760123
 2326360.1777929 6970078.2314203  2326480.672444 6969872.6049224
 2326806.7632579 6969323.8816204 2326808.6790219 6969320.6579039
#Sta/Elev= 30
   59.48  538.03   63.34  521.34   82.74  510.83   90.12  510.63  104.44  507.82
  119.05     500  132.26  496.63  225.31  490.68  246.61  488.16   291.2     488
  305.82  492.62  323.05  503.65  347.56  504.22  357.78  505.93  361.09  509.71
  410.52  528.78  416.24  529.56  422.48  536.62  423.24   527.3  456.68  529.04
  501.11  529.27  502.79  527.64  670.31  524.59  765.45  525.54  808.42  523.19
  1058.9  522.83 1149.36  520.86 1235.87  521.09 1257.41     528 1300.09     536
#Mann= 3 ,0,0
   59.48     .06       0   63.34    .035       0  410.52     .06       0
#XS Ineff= 2 ,-1
  422.48  829.48     550 1229.48 1300.09     550
Permanent Ineff=
       F       F
Bank Sta=63.34,410.52
XS Rating Curve= 0 ,0
Exp/Cntr=0.5,0.3

Type RM Length L Ch R = 1 ,241328  ,180,180,61
BEGIN DESCRIPTION:
This cross section corresponds to cross section 241206.6 of the non-georeferenced CDC model which was the source of this model.
END DESCRIPTION:
XS GIS Cut Line= 6
     2326129.541      6970467.44 2326157.7156192 6970445.2090265
 2326283.4687604  6970237.430674 2326458.2094885 6969940.5260811
 2326656.9190425 6969598.0033122 2326850.5406398 6969259.2999636
#Sta/Elev= 30
     -36     534       0  526.19   10.44  526.37   33.73  522.41   52.81  514.56
   67.29  512.07   90.12  510.63  104.44  507.82  119.05     500   136.8     496
  246.61  488.16  312.11   487.6  325.55     494  360.96     500  365.96  503.88
  379.16  506.29  383.54  511.75  399.62  518.65  420.64  526.72  430.94  528.04
  545.47  529.71  778.08  528.81  831.56  526.68   865.7   519.8  949.68  522.09
 1128.92  520.08 1221.45   520.7 1235.13     525 1292.27  534.62 1373.52     536
#Mann= 3 ,-1,0
     -36     .06       0   67.29    .035       0  430.94     .06       0
#XS Ineff= 4 ,-1
     -36       0     550       0   48.23     550  466.23  784.67     550
 1244.71 1373.52     550
Permanent Ineff=
       F       F       F       F
Bank Sta=67.29,430.94
XS Rating Curve= 0 ,0
Exp/Cntr=0.3,0.1

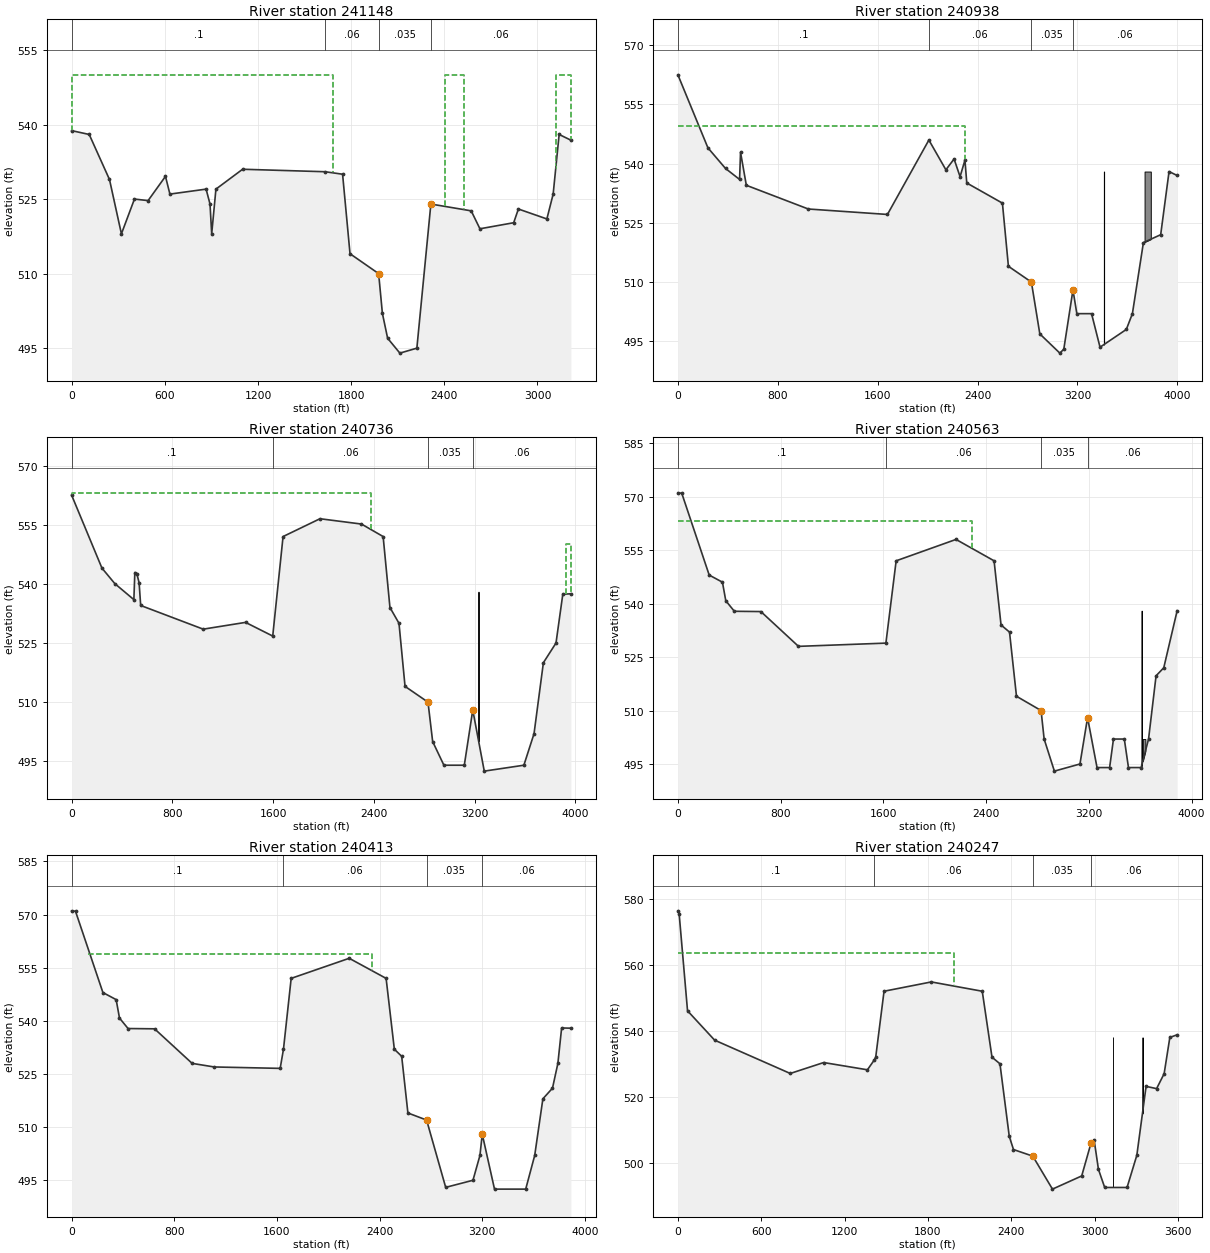
Type RM Length L Ch R = 1 ,241148  ,210,210,188
BEGIN DESCRIPTION:
This cross section corresponds to cross section 241026.7 of the non-georeferenced CDC model which was the source of this model.
Samuels Ave North Valley Storage Site in LOB.
Samuels Ave South Valley Storage Site in ROB - proposed land use is maintained grass and water feature.
Ineffective flow in LOB.
Landfills in LOB.
Effective flow limit in ROB set at West Fork Levee Loop.
Ineffective flow in ROB due to Union Pacific Railroad bridge.
END DESCRIPTION:
XS GIS Cut Line= 5
2326412.898050116972371.544876312326412.935689586972370.01181753
2326460.891361096970416.773082212326481.512295936969997.42019941
2326900.430244586969269.33575554
#Sta/Elev= 30
       0  538.77  113.28     538  243.78  528.94  320.63     518  404.55     525
  492.39  524.69  604.38  529.57  632.92     526  866.04     527   891.2     524
  902.04     518  929.25     527 1101.11     531 1632.34   530.5 1744.98     530
 1792.87     514  1977.2     510 2001.32     502    2035     497 2113.94     494
 2223.34     495 2313.58     524 2573.28  522.63 2629.47  519.02 2846.91  520.24
 2877.18     523 3060.62     521  3101.1     526 3139.66     538 3215.22  536.85
#Mann= 4 ,-1,0
       0      .1       0 1632.34     .06       0  1977.2    .035       0
 2313.58     .06       0
#XS Ineff= 3 ,-1
       0 1681.97     550 2401.45 2529.42     550 3117.21 3213.69     550
Permanent Ineff=
       F       F       F
Bank Sta=1977.2,2313.58
XS Rating Curve= 0 ,0
Exp/Cntr=0.3,0.1

Type RM Length L Ch R = 1 ,240938  ,202,202,182
BEGIN DESCRIPTION:
This cross section corresponds to cross section 240814 of the non-georeferenced CDC model which was the source of this model.
Interpolated Section.
Samuels Ave North Valley Storage Site in LOB.
Samuels Ave South Valley Storage Site in ROB - proposed land use is maintained grass and water feature.
Wake Park in ROB.  Pylon and building represented as blocked obstructions.
END DESCRIPTION:
XS GIS Cut Line= 4
2326717.864872476973237.56006312  2326711.9599876972766.15438402
2326676.989077026969974.316056282326921.784928266969280.72778948
#Sta/Elev= 30
       0   562.5  240.59     544   381.4  538.78  494.14     536  501.79  542.88
  548.21  534.52 1044.58  528.51 1678.51  527.13 2010.37  545.98 2146.75  538.44
 2212.23  541.18 2260.19   536.7 2299.35  540.89 2313.86   535.1 2599.47     530
 2647.43     514 2831.56     510 2899.11  496.87 3059.54     492 3091.11     493
 3164.54     508  3195.6     502 3313.42     502 3381.32   493.5 3591.95     498
 3640.68     502  3728.8     520  3867.2     522  3934.2     538 3999.02     537
#Mann= 4 ,-1,0
       0      .1       0 2010.37     .06       0 2831.56    .035       0
 3164.54     .06       0
#XS Ineff= 2 , 0
         2298.97  549.55
Permanent Ineff=
       F       F
#Block Obstruct= 2 ,-1
    34123414.125     538    3738    3788     538
Bank Sta=2831.56,3164.54
XS Rating Curve= 0 ,0
Exp/Cntr=0.3,0.1

Type RM Length L Ch R = 1 ,240736  ,173,173,147
BEGIN DESCRIPTION:
This cross section corresponds to cross section 240614.1 of the non-georeferenced CDC model which was the source of this model.
Samuels Ave North Valley Storage Site in LOB.
Samuels Ave South Valley Storage Site in ROB - proposed land use is maintained grass and water feature.
Ineffective flow in LOB.
Landfills in LOB.
Effective flow limit in ROB set at West Fork Levee Loop.
Ineffective flow in ROB due to Union Pacific Railroad bridge.
Wake Park in ROB.  Pylon represented as blocked obstructions.
END DESCRIPTION:
XS GIS Cut Line= 4
     2327097.343     6973213.822     2326868.427     6970022.865
     2326944.732     6969287.5572326947.31409251 6969262.6748392
#Sta/Elev= 30
       0   562.5  240.59     544  342.91  540.06  494.14     536  501.79  542.88
  517.19  542.62  535.69   540.3  548.21  534.52 1044.58  528.51 1380.77  530.23
 1596.45  526.76 1678.52     552 1971.65  556.52 2301.12  555.17 2473.01     552
 2527.08     534 2598.82     530 2646.89     514 2829.09     510 2866.11     500
 2955.36     494 3117.31     494 3184.55     508 3275.85   492.5 3590.24     494
 3670.96     502 3745.18     520 3845.38     525 3899.37  537.38 3963.43  537.48
#Mann= 4 ,-1,0
       0      .1       0 1596.45     .06       0 2829.09    .035       0
 3184.55     .06       0
#XS Ineff= 2 ,-1
     .18 2373.85563.0907 3921.38 3963.43     550
Permanent Ineff=
       F       F
#Block Obstruct= 1 ,-1
    32293231.125     538
Bank Sta=2829.09,3184.55
XS Rating Curve= 0 ,0
Exp/Cntr=0.3,0.1

Type RM Length L Ch R = 1 ,240563  ,150,150,127
BEGIN DESCRIPTION:
This cross section corresponds to cross section 240441 of the non-georeferenced CDC model which was the source of this model.
Interpolated Section.
Samuels Ave North Valley Storage Site in LOB.
Samuels Ave South Valley Storage Site in ROB - proposed land use is maintained grass and water feature.
Wake Park in ROB.  Pylon and dock represented as blocked obstructions.
END DESCRIPTION:
XS GIS Cut Line= 5
2327401.809881946973209.737159522327399.71974719 6973191.6329028
2327003.383631786969758.662478762327032.603267796969449.76907768
2327042.303206186969347.22683665
#Sta/Elev= 30
       0  571.07   30.18  570.95  243.73     548  346.92     546  372.97  540.79
  439.74  537.84  646.21  537.76  939.01     528 1619.57  528.91 1699.43     552
 2165.61     558  2461.9     552 2516.13     534 2582.07     532 2636.31     514
  2827.7     510  2851.7     502 2931.45     493  3130.6     495 3189.76     508
 3263.47     494 3361.53     494 3391.53     502 3475.91     502 3508.27     494
 3606.97     494 3664.72     502  3723.2  519.74 3783.18     522 3887.27     538
#Mann= 4 ,-1,0
       0      .1       0 1619.57     .06       0  2827.7    .035       0
 3189.76     .06       0
#XS Ineff= 2 , 0
       0 2287.84  563.12 3784.27       0
Permanent Ineff=
       F       F
#Block Obstruct= 2 ,-1
    36103612.125     538    3620    3640     502
Bank Sta=2827.7,3189.76
XS Rating Curve= 0 ,0
Exp/Cntr=0.3,0.1

Type RM Length L Ch R = 1 ,240413  ,166,166,151
BEGIN DESCRIPTION:
This cross section corresponds to cross section 240292 of the non-georeferenced CDC model which was the source of this model.
Samuels Ave North Valley Storage Site in LOB.
Samuels Ave South Valley Storage Site in ROB - proposed land use is maintained grass and water feature.
Ineffective flow in LOB.
Landfills in LOB.
Effective flow limit in ROB set at West Fork Levee Loop.
Wake Park in ROB.
END DESCRIPTION:
XS GIS Cut Line= 4
2327705.050386856973171.450362582327704.825992726973170.11630175
2327171.782617946970001.083758062327145.418089126969326.14100832
#Sta/Elev= 30
       0  571.07   30.18  570.95  243.73     548  346.92     546  372.97  540.79
  439.74  537.84  646.21  537.76  939.01     528 1110.51  526.99 1625.05  526.59
 1650.75     532 1710.75     552 2163.17  557.67 2450.56     552  2514.7     532
 2571.89     530  2620.4     514 2766.09     512 2914.84     493  3127.4     495
 3181.65     502 3199.76     508 3295.27   492.5 3538.32   492.5 3608.39     502
 3672.21     518 3747.05     521 3789.07     528 3818.27     538 3890.36  537.94
#Mann= 4 ,-1,0
       0      .1       0 1650.75     .06       0 2766.09    .035       0
 3199.76     .06       0
#XS Ineff= 1 ,-1
  130.89 2342.88558.9566
Permanent Ineff=
       F
Bank Sta=2766.09,3199.76
XS Rating Curve= 0 ,0
Exp/Cntr=0.3,0.1

Type RM Length L Ch R = 1 ,240247  ,116,116,106
BEGIN DESCRIPTION:
This cross section corresponds to cross section 240126 of the non-georeferenced CDC model which was the source of this model.
Interpolated Section.
Samuels Ave North Valley Storage Site in LOB.
Samuels Ave South Valley Storage Site in ROB - proposed land use is maintained grass and water feature.
Wake Park in ROB.  Pylon represented as blocked obstructions.
END DESCRIPTION:
XS GIS Cut Line= 3
2327893.600297476972908.418005272327329.778056896969968.48754968
2327329.778056896969368.15486994
#Sta/Elev= 30
       0  576.38    9.03  575.49   69.39  546.07  264.37  537.17  808.83  527.07
 1049.54  530.38  1364.3  528.18 1411.63  531.03 1423.97     532 1483.97     552
 1824.17  554.82 2190.95     552 2261.04     532 2318.36     530  2385.4     508
 2415.78     504 2554.77     502 2696.33     492 2906.84     496 2974.16     506
 2996.29   506.9 3027.33     498 3072.27   492.5 3233.27   492.5 3303.65  502.25
 3370.28  523.16 3445.95  522.47 3500.24     527 3541.29     538 3593.84  538.79
#Mann= 4 ,-1,0
       0      .1       0 1411.63     .06       0 2554.77    .035       0
 2974.16     .06       0
#XS Ineff= 2 , 0
         1990.41   563.6
Permanent Ineff=
       F       F
#Block Obstruct= 2 ,-1
    31293131.125     538    33443346.125     538
Bank Sta=2554.77,2974.16
XS Rating Curve= 0 ,0
Exp/Cntr=0.3,0.1