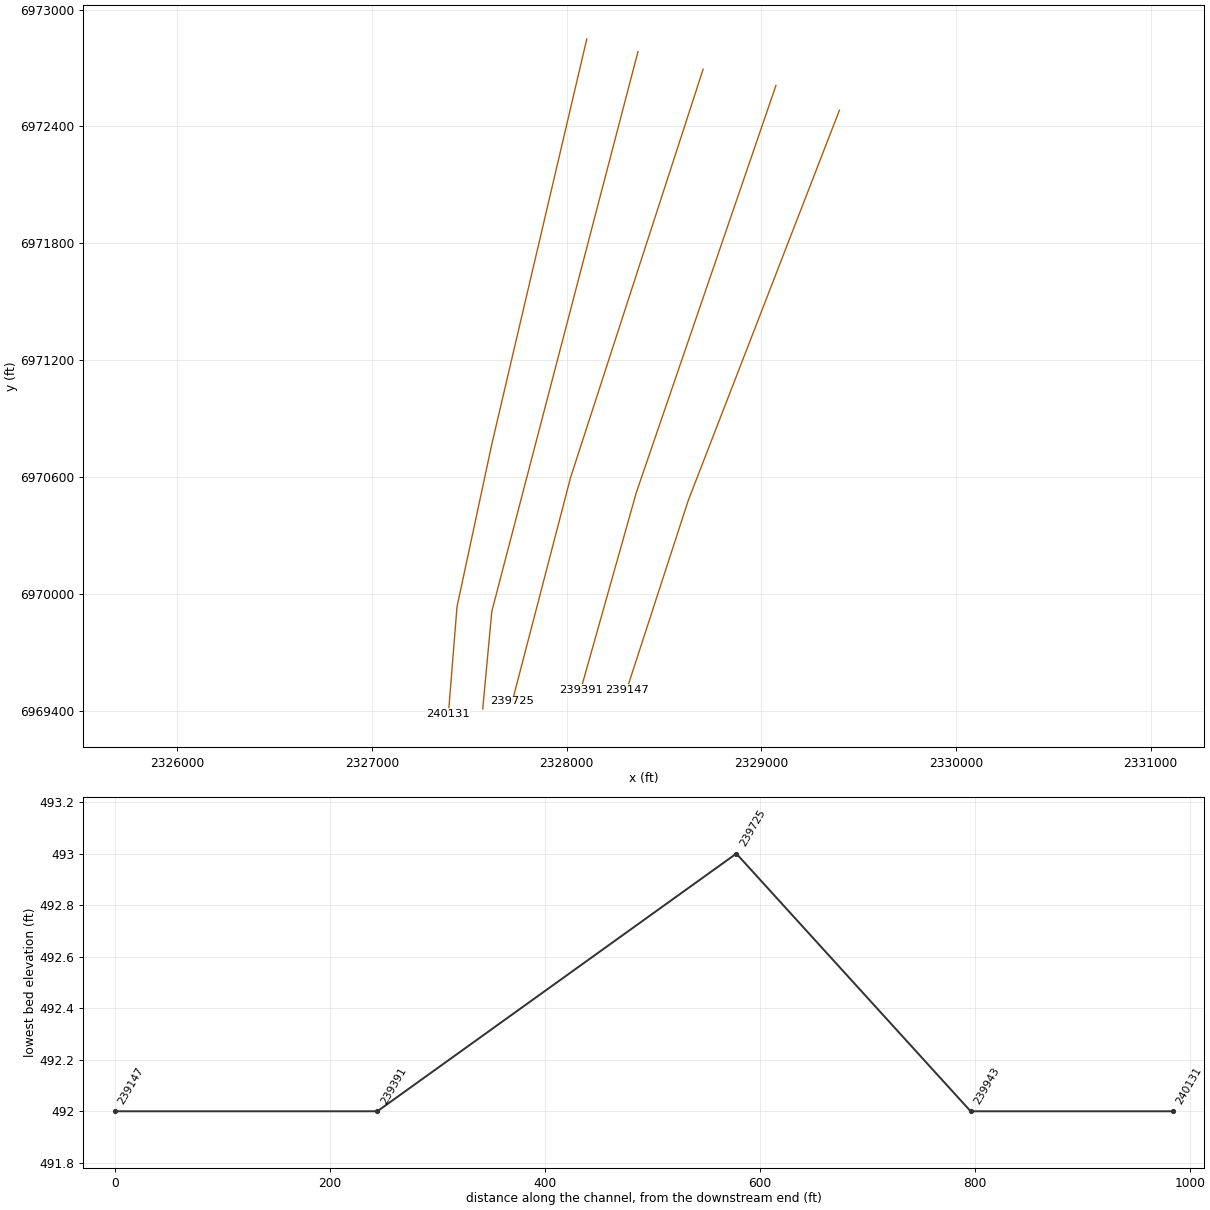
HEC-RAS study CDC_Consolidated_Model.prj: Upper Trinity CDC Consolidated Model

--- CDC_Consolidated_Model.g03 (geometry) --- (continued)

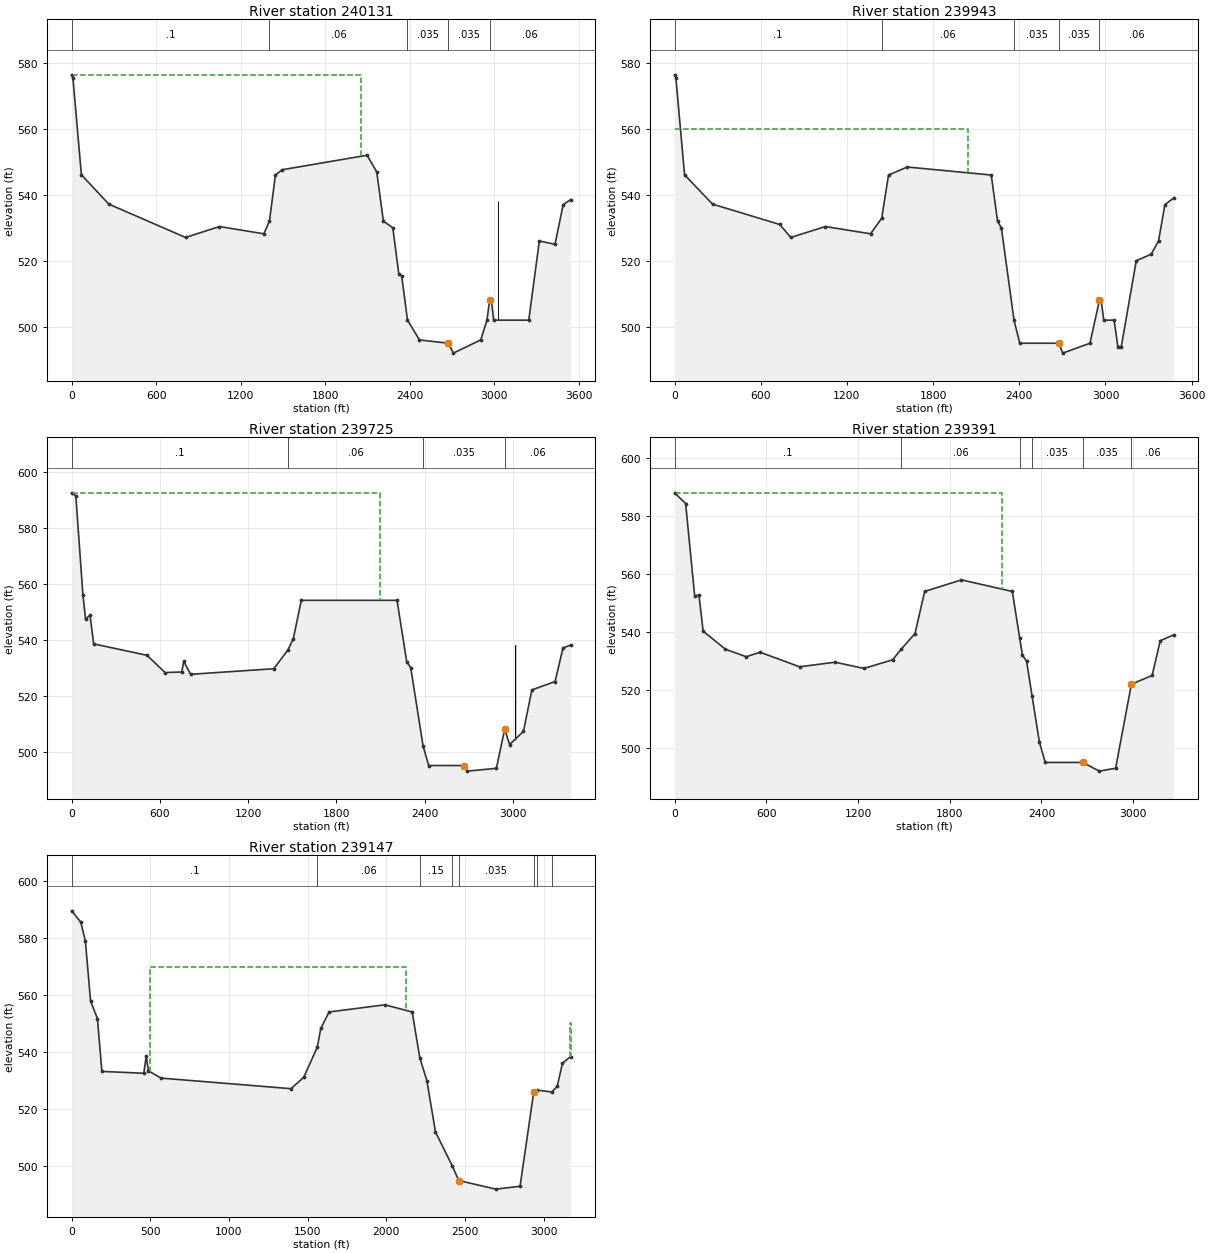
Type RM Length L Ch R = 1 ,240131  ,188,188,168
BEGIN DESCRIPTION:
This cross section corresponds to cross section 240009.9 of the non-georeferenced CDC model which was the source of this model.
Samuels Ave North Valley Storage Site in LOB.
Samuels Ave South Valley Storage Site in ROB - proposed land use is maintained grass and water feature.
Ineffective flow in LOB.
Landfills in LOB.
Effective flow limit in ROB set at West Fork Levee Loop.
Wake Park in ROB.  Pylon represented as blocked obstructions.
END DESCRIPTION:
XS GIS Cut Line= 4
 2328103.35240776972849.084207442327616.592825646970773.95099311
2327436.623683456969934.246629042327392.499580936969385.25860702
#Sta/Elev= 30
       0  576.38    9.03  575.49   69.39  546.07  264.37  537.17  808.83  527.07
 1049.54  530.38  1364.3  528.18 1404.15     532 1446.55     546 1493.97   547.6
 2097.38     552 2165.75  546.92 2212.86     532 2279.77     530 2322.25     516
    2343  515.33 2383.85     502 2468.73     496  2674.9     495 2709.04     492
 2903.78     496 2948.13     502 2966.22     508 2979.22     508 2995.73     502
 3244.68     502 3319.73     526 3430.91     525 3488.88     537 3540.99  538.53
#Mann= 5 ,-1,0
       0      .1       0 1404.15     .06       0 2383.85    .035       0
  2674.9    .035       0 2966.22     .06       0
#XS Ineff= 1 ,-1
     .06 2053.48576.3792
Permanent Ineff=
       F
#Block Obstruct= 1 ,-1
    30273029.125     538
Bank Sta=2674.9,2966.22
XS Rating Curve= 0 ,0
Exp/Cntr=0.3,0.1

Type RM Length L Ch R = 1 ,239943  ,218,218,196
BEGIN DESCRIPTION:
This cross section corresponds to cross section 239822 of the non-georeferenced CDC model which was the source of this model.
Interpolated Section.
Samuels Ave North Valley Storage Site in LOB.
Samuels Ave South Valley Storage Site in ROB - proposed land use is maintained grass and water feature.
Wake Park in ROB.
END DESCRIPTION:
XS GIS Cut Line= 4
2328366.324552296972783.922013792328355.589255416972742.84048724
2327615.373195076969910.202872572327568.745401536969408.95415689
#Sta/Elev= 30
       0  576.38    9.03  575.49   69.39  546.07  264.37  537.17  732.62     531
  808.83  527.07 1049.54  530.38  1364.3  528.18 1442.04   532.9 1489.52     546
 1620.49  548.43  2204.7     546  2248.8     532 2275.05     530 2363.25     502
 2403.14     495  2675.5     495 2702.26     492 2892.09     495 2957.82     508
 2970.29     508 2987.83     502 3059.95     502 3086.08     494 3110.29     494
 3214.26     520 3318.38     522 3369.49     526 3413.56     537 3473.63     539
#Mann= 5 ,-1,0
       0      .1       0 1442.04     .06       0 2363.25    .035       0
  2675.5    .035       0 2957.82     .06       0
#XS Ineff= 2 , 0
         2042.22  560.06
Permanent Ineff=
       F       F
Bank Sta=2675.5,2957.82
XS Rating Curve= 0 ,0
Exp/Cntr=0.3,0.1

Type RM Length L Ch R = 1 ,239725  ,334,334,322
BEGIN DESCRIPTION:
This cross section corresponds to cross section 239603.9 of the non-georeferenced CDC model which was the source of this model.
Samuels Ave North Valley Storage Site in LOB.
Samuels Ave South Valley Storage Site in ROB - proposed land use is maintained grass and water feature.
Ineffective flow in LOB.
Landfills in LOB.
Effective flow limit in ROB set at West Fork Levee Loop.
Wake Park in ROB.  Pylon represented as blocked obstructions.
END DESCRIPTION:
XS GIS Cut Line= 4
2328701.044740576972693.876803282328700.81341262 6972693.1646544
2328019.835254676970596.756354882327720.982597466969449.52839294
#Sta/Elev= 30
       0  592.39   28.65  591.32    76.7  556.02    94.4  547.37  124.95  548.65
  150.21  538.44  512.34  534.37  635.29  528.21  748.72  528.41  762.14  532.22
  808.66  527.58 1373.96  529.57 1469.89  536.27 1506.63  540.32 1560.91     554
 2211.49     554 2277.54  532.01 2304.37     530 2388.48     502 2426.53     495
 2669.57     495 2687.91     493 2886.57     494 2943.01     508 2976.34   502.5
 3070.61  507.19 3127.92     522  3285.7     525  3339.4     537  3390.5     538
#Mann= 4 ,-1,0
       0      .1       0 1469.89     .06       0 2388.48    .035       0
 2943.01     .06       0
#XS Ineff= 1 ,-1
     -.1 2093.29592.3987
Permanent Ineff=
       F
#Block Obstruct= 1 ,-1
    30133015.125     538
Bank Sta=2669.57,2943.01
XS Rating Curve= 0 ,0
Exp/Cntr=0.3,0.1

Type RM Length L Ch R = 1 ,239391  ,244,244,221
BEGIN DESCRIPTION:
This cross section corresponds to cross section 239269.4 of the non-georeferenced CDC model which was the source of this model.
Samuels Ave North Valley Storage Site in LOB.
Samuels Ave South Valley Storage Site in ROB - proposed land use is maintained grass and water feature.
Ineffective flow in LOB.
Landfills in LOB.
Effective flow limit in ROB set at West Fork Levee Loop.
END DESCRIPTION:
XS GIS Cut Line= 4
2329075.330638666972610.693426482329074.892048096972609.41565199
2328358.420799916970522.073298922328071.918587436969506.49517418
#Sta/Elev= 30
       0  588.02    72.2  584.35  131.34  552.44  159.12  552.79  186.78  540.29
  332.43  534.07   468.8  531.47  559.35  533.03  817.67     528 1049.81  529.59
    1238  527.43 1426.32  530.41 1481.01     534 1572.76  539.49 1635.58     554
 1876.68     558 2209.03     554 2257.16     538 2275.21     532 2302.03     530
 2338.13     518 2386.25     502 2424.35     495 2670.08     495 2777.78     492
 2884.85     493 2988.01     522 3123.52     525 3176.88     537 3263.45     539
#Mann= 6 ,-1,0
       0      .1       0 1481.01     .06       0 2257.16     .15       0
 2338.13    .035       0 2670.08    .035       0 2988.01     .06       0
#XS Ineff= 1 ,-1
       0  2138.5588.0345
Permanent Ineff=
       F
Bank Sta=2670.08,2988.01
XS Rating Curve= 0 ,0
Exp/Cntr=0.3,0.1

Type RM Length L Ch R = 1 ,239147  ,145,145,101
BEGIN DESCRIPTION:
This cross section corresponds to cross section 239025.7 of the non-georeferenced CDC model which was the source of this model.
Samuels Ave North Valley Storage Site in LOB.
Samuels Ave South Valley Storage Site in ROB - proposed land use is maintained grass and water feature.
Ineffective flow in LOB.
Landfills in LOB.
Effective flow limit in ROB set at West Fork Levee Loop.
END DESCRIPTION:
XS GIS Cut Line= 4
2329401.228101276972482.925549312329400.582541036972481.26006672
2328624.550463186970479.172845722328308.013162816969506.69403826
#Sta/Elev= 30
       0  589.41   58.29  585.45   87.55  578.82  120.48  557.86   164.4  551.66
   192.3  533.21  459.11  532.55  474.14   538.6   488.2  533.44  568.39  530.86
 1394.47  527.16 1475.58  531.11 1561.86  541.69 1583.96  548.23 1636.86     554
 1991.48  556.52 2165.13     554 2213.32     538 2258.49     530 2313.17     512
 2421.21  499.99 2461.45     495 2696.72     492 2850.97     493 2937.85     526
  2960.8  526.65 3052.99     526 3087.34     528 3120.14     536 3171.71   538.4
#Mann= 8 ,-1,0
       0      .1       0 1561.86     .06       0 2213.32     .15       0
 2421.21    .035       0 2461.45    .035       0 2937.85     .06       0
  2960.8     .15       0 3052.99     .06       0
#XS Ineff= 2 , 0
     499 2125.54   569.9 3166.49     499     550
Permanent Ineff=
       F       T
Bank Sta=2461.45,2937.85
XS Rating Curve= 0 ,0
Exp/Cntr=0.5,0.3