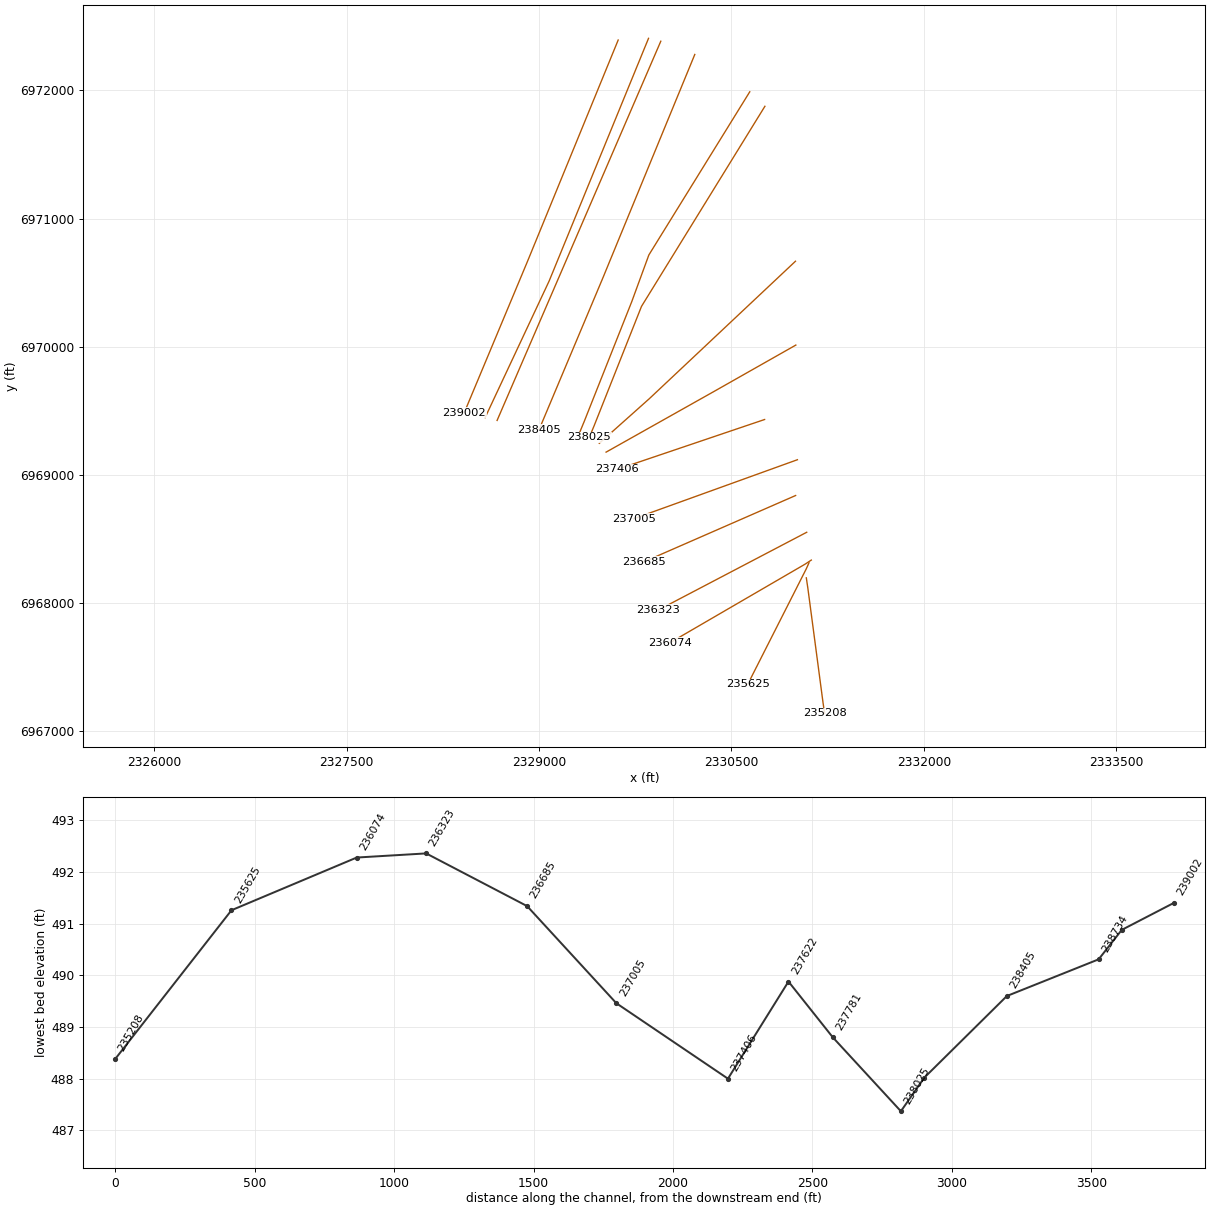
HEC-RAS study CDC_Consolidated_Model.prj: Upper Trinity CDC Consolidated Model

--- CDC_Consolidated_Model.g03 (geometry) --- (continued)

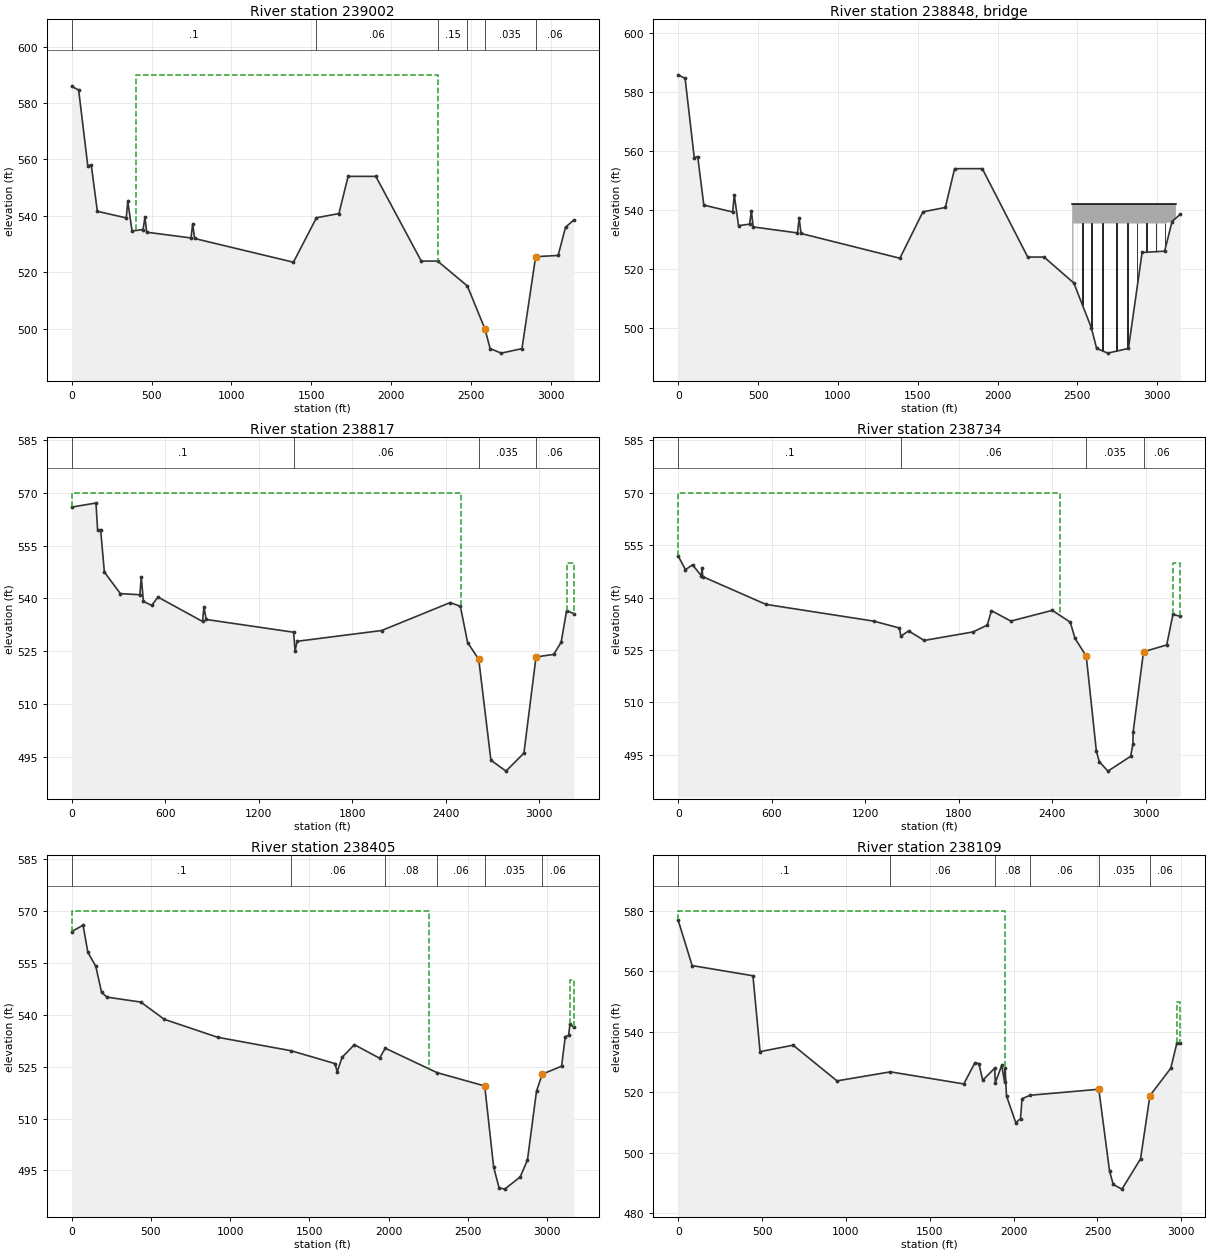
Type RM Length L Ch R = 1 ,239002  ,186,186,162
BEGIN DESCRIPTION:
This cross section corresponds to cross section 238881.1 of the non-georeferenced CDC model which was the source of this model.
--------------------
CDC FW090808-01 Fort Worth Central City
Cross-section 238881.1 - 241026.7
Samuels Ave North Valley Storage Site in LOB.
Samuels Ave South Valley Storage Site in ROB - proposed land use is maintained grass and water feature.
Upstream of Northside Drive.
Ineffective flow in LOB.
Landfills in LOB.
Effective flow limit in ROB set at West Fork Levee Loop.
END DESCRIPTION:
XS GIS Cut Line= 4
2329617.248059326972392.471778262329616.311437996972390.18342847
 2328910.93898356970666.820034182328417.44207788 6969485.2073835
#Sta/Elev= 30
       0  585.84   43.07  584.61  100.43   557.7  121.94  558.11   160.3  541.63
  341.27  539.29   350.9  545.14  377.59  534.67  446.56  535.16  458.36  539.54
  469.42  534.23  746.92  532.19  757.46  537.19  769.27     532 1388.45   523.6
 1532.85  539.35 1673.24  540.83 1731.24     554 1904.74     554 2189.42     524
 2291.71     524 2478.26  515.18 2587.87     500 2620.92     493 2690.56   491.4
 2820.22     493 2905.82  525.56 3046.85     526  3093.1     536 3145.13  538.56
#Mann= 6 ,-1,0
       0      .1       0 1532.85     .06       0 2291.71     .15       0
 2478.26    .035       0 2587.87    .035       0 2905.82     .06       0
#XS Ineff= 2 , 0
     405 2296.94  589.97             405
Permanent Ineff=
       F       F
Bank Sta=2587.87,2905.82
XS Rating Curve= 0 ,0
Exp/Cntr=0.5,0.3

Type RM Length L Ch R = 3 ,238848  ,,,
BEGIN DESCRIPTION:
Northside Drive
Bridge length 632 feet.
Data from USACE 1975 survey.
Note:  Internal bridge cross-sections modified to represent geometry under bridge.
END DESCRIPTION:
Node Name=Northside Drive
Bridge Culvert--1,0,-1,-1, 0
Deck Dist Width WeirC Skew NumUp NumDn MinLoCord MaxHiCord MaxSubmerge Is_Ogee
76.6,63,2.6,0, 6, 6, , , 0.95, 0, 0,0,,
 2467.47 2475.47 2475.47 3107.47 3107.47 3117.42
     542     542     542     542     542     542
     450     450   535.4   535.4     450     450
 2541.47 2549.47 2549.47 3181.47 3181.47 3191.42
     542     542     542     542     542     542
     450     450   535.4   535.4     450     450
Pier Skew, UpSta & Num, DnSta & Num=  ,2532.47, 2 ,2591, 2 , 0 , 0 , 0 ,,
     2.5     2.5
     450     540
     2.5     2.5
     450     540
Pier Skew, UpSta & Num, DnSta & Num=  ,2588.47, 2 ,2662.47, 2 , 0 , 0 , 0 ,,
     2.5     2.5
     450     540
     2.5     2.5
     450     540
Pier Skew, UpSta & Num, DnSta & Num=  ,2658.47, 2 ,2732.47, 2 , 0 , 0 , 0 ,,
     2.5     2.5
     450     540
     2.5     2.5
     450     540
Pier Skew, UpSta & Num, DnSta & Num=  ,2744.47, 2 ,2818.47, 2 , 0 , 0 , 0 ,,
     2.5     2.5
     450     540
     2.5     2.5
     450     540
Pier Skew, UpSta & Num, DnSta & Num=  ,2813.97, 2 ,2887.97, 2 , 0 , 0 , 0 ,,
     2.5     2.5
     450     540
     2.5     2.5
     450     540
Pier Skew, UpSta & Num, DnSta & Num=  ,2874.47, 2 ,2948.47, 2 , 0 , 0 , 0 ,,
     2.5     2.5
     450     540
     2.5     2.5
     450     540
Pier Skew, UpSta & Num, DnSta & Num=  ,2934.47, 2 ,3008.47, 2 , 0 , 0 , 0 ,,
     2.5     2.5
     450     540
     2.5     2.5
     450     540
Pier Skew, UpSta & Num, DnSta & Num=  ,2994.47, 2 ,3068.47, 2 , 0 , 0 , 0 ,,
     2.5     2.5
     450     540
     2.5     2.5
     450     540
Pier Skew, UpSta & Num, DnSta & Num=  ,3050.47, 2 ,3124.47, 2 , 0 , 0 , 0 ,,
     2.5     2.5
     450     540
     2.5     2.5
     450     540
Abutment Skew #Up #Dn= , 2 , 2
  2450.1  2475.1
   535.4     522
    2534    2559
   535.4     523
BR Coef=-1 , 0 , 0 ,, 0 ,,,0.8,-1,,0,
WSPro=,,,, 1 ,,,, 0 ,,,, 0 ,,,,-1 ,-1 ,-1 , 0 , 0 , 0 , 0 , 0
BR U #Sta/Elev= 498
       0  585.84   13.86  585.34   27.19  585.07   43.07  584.61   46.84  583.45
   47.25  583.31   48.01  583.09   48.63  582.88   49.14  582.74   49.85  582.51
   50.14  582.43   51.57     582   51.83  581.93    52.8  581.64   53.86  581.33
   54.43  581.14    54.7  581.06   57.86  579.86   60.26  578.88   61.27  578.54
   62.26  578.11   62.58     578   62.72     578   63.73  577.61   66.82  576.13
   67.35  575.86   76.26  572.03   76.86   571.8   79.45  570.64   83.66     568
   83.75  567.95   96.16  560.25  100.43   557.7  107.29   558.2  121.01  558.13
  121.53  558.11  121.94  558.11  135.75  552.25  136.49  551.95  137.72  551.44
  139.72     550  141.22  548.98   142.2  548.35  142.45  548.01  143.76  546.18
  144.21  545.53  152.58  544.12  152.96     544   159.1     542   160.3  541.63
  160.42  541.64  160.71   541.6  166.61  541.78  183.31     541  207.34  541.97
  242.95  542.07  271.55  541.54  272.28  541.52   283.7  541.43  290.72  541.29
  324.31  540.03  324.48  540.02  341.27  539.29   342.4     540   350.9  545.14
  358.95  540.09  361.69  538.39  368.69     536  368.98  535.89  371.72  534.97
  377.59  534.67  402.73  534.35  411.14  534.37   422.4  534.25  446.56  535.16
  454.56  538.23  458.36  539.54  469.42  534.23  480.31  534.26  523.24  534.87
  531.41  535.09  548.14  534.08  586.72  534.13  612.52  534.44  614.62  534.75
  625.75  535.87  632.96  533.62  681.54  533.26  746.92  532.19  747.51  532.46
  757.46  537.19  766.89  532.11  769.27     532  802.59  531.83  803.09  531.88
  803.66  531.83  868.99  530.56  917.49  530.08  917.79  530.07  940.86   529.8
  964.16  529.68  972.72  529.56  986.64  529.58  996.51  529.46 1012.55  528.95
 1029.96  528.85 1039.86  528.54 1057.85  528.14  1090.7  526.98  1097.3   526.6
 1104.72     526 1119.21  524.99 1124.78  525.18 1127.88  525.18  1132.8  524.91
 1154.15   524.4 1156.65  524.23 1164.26     524  1173.3  523.96 1173.78   523.9
 1175.99  523.82 1184.64  523.77  1185.2  523.75 1212.88  523.78 1215.25  523.82
 1220.21     524 1224.66     524  1239.1  525.19 1244.68  525.47  1263.5  524.94
 1272.46  524.78  1293.1  524.95 1294.12  524.94 1308.26  525.36 1328.42  524.64
 1346.72  524.74 1352.91  524.61 1359.61  524.52 1388.45   523.6 1399.25  524.62
 1399.65  524.67 1419.99  526.66 1421.12  526.79 1425.62   527.2 1427.05  527.36
 1431.58  527.74 1433.99     528 1434.18     528 1439.53  528.61 1440.65   528.7
 1446.05  529.37 1446.47  529.41 1446.82  529.43 1452.99   530.1 1454.67  530.28
 1454.93  530.32  1456.2  530.45 1456.62  530.51 1460.77  530.92 1461.65  531.03
  1470.8     532 1470.92  532.01 1474.97  532.56 1475.56  532.63 1476.91  532.82
 1477.84  532.92  1479.2   533.1 1487.33  534.02  1489.5  534.18 1489.58  534.18
 1512.16  535.23 1513.18  535.27 1526.96   535.9 1527.64  535.94 1529.72  536.09
 1529.82  536.09 1537.45  536.64 1553.94     538 1560.35  538.43 1573.51  539.72
 1573.61  539.72 1583.18  540.65 1594.85   541.6 1599.76  541.89 1599.88   541.9
 1603.14   542.1 1603.26   542.1 1606.26  542.28 1606.65  542.29 1608.55  542.39
 1636.19  543.11  1656.6   543.1 1677.05  542.73 1688.66  542.36  1689.6  542.35
 1693.36  542.24 1693.99  542.24 1703.86  541.98 1703.93  541.97 1717.75  541.66
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BR U #Mann= 5
       0      .1 1419.99     .06 2547.75    .035 2914.25     .06 3028.71     .06
BR U Banks=2547.75,2914.25
BR D #Sta/Elev= 481
       0  565.95   17.02  565.86   17.63  565.85   40.01  565.82   58.27  565.45
   78.96  565.42   79.79  565.41   91.14  565.49  108.87     566     109     566
  109.73  566.03  118.25  566.25   126.5  567.85  127.45     568  127.67  568.05
  131.79  568.01  131.93     568     133     568  136.57  567.79  144.02  566.77
  148.22  566.78  155.39   567.1  156.77  566.05   157.1  565.81  158.73  564.58
  163.12  561.32  164.97     560  165.66  559.52  165.73  559.46  171.19  559.03
   172.4  558.97  173.35  558.96  185.03  559.54  185.11  559.53  202.07  552.31
  202.61     552  204.81  550.79  206.19     550  207.34  549.39  207.52  549.29
  209.12  547.64  209.28  547.47   218.5  546.32   225.4  544.91   225.7  544.86
  240.66     544  241.03     544  242.84  543.91  300.87  541.75  303.39   541.7
  303.74   541.7  311.85  541.35  319.09   541.2  320.06   541.2  342.25  541.62
  345.84  541.59  352.64  541.71   353.8  541.79  360.68  541.93  363.55  541.94
  367.77  541.83  374.28  541.79  393.46   542.4  395.94  542.81  396.97  542.85
  404.37  542.59  404.98  542.54  416.53  542.05  417.42     542  417.64     542
  435.63  541.03  436.74  541.03  438.71     542  442.44     544   442.7  544.15
   446.1  545.99   454.9  541.47  459.72  539.13  464.89  538.92  468.01  538.86
  475.55  538.62  513.31     538  541.08  537.82  541.29  537.86  552.97  540.37
  565.71  538.05  565.74  537.94  566.58  538.03  595.68  538.04  597.12  538.02
  611.58  537.98  616.81  538.03  618.87  537.92  621.78   537.9  630.75  537.61
  649.35  537.24  686.13  536.74   716.1     536  743.37     536  791.71  534.56
  812.01  534.09   812.2  534.08  815.34     534  815.66     534  839.13  533.43
  844.77     536  844.84  536.03  847.16  537.12  848.11  537.55  857.53  534.59
  862.63     534  880.94     534  890.41  534.92  892.72  535.21  907.55     534
  933.71  533.39  964.42  532.93 1021.18  533.16 1023.03  533.23 1027.17  533.07
 1033.25  532.93 1074.28  533.42 1092.92  533.31 1126.07  532.92 1226.79  532.82
 1260.39     532 1276.01  531.28  1281.1  531.14 1296.78  531.03 1383.99  531.21
 1413.34  531.54 1420.73  530.66  1423.5  530.37 1423.77  530.34 1424.31     530
 1427.69     528 1428.26  527.71 1431.24     526 1431.54  525.85 1433.14  525.02
 1435.12  525.48 1444.03   527.4 1444.82  527.58 1445.81  527.79 1467.84   527.1
 1478.66  526.93 1500.98  527.32 1545.37  528.32 1579.68  528.63 1652.94  528.99
 1672.15  528.87 1707.06  529.31 1854.18  530.77 1892.93  530.74 1918.99  530.97
 1932.23  530.84 1956.81  531.13 1958.23  531.16  1971.6  530.93 1976.92   531.1
 1989.07  530.86 1989.68  530.88 1994.82  531.15 2003.93  531.33 2028.97  532.47
 2032.93   532.7 2043.69  534.87 2043.78  534.88  2048.5  535.79 2054.26  535.96
 2054.64  535.98 2055.21     536  2069.1  536.13 2069.71  536.13 2070.93  536.15
  2071.8  536.15 2087.18  536.38 2087.84  536.38 2088.72   536.4 2094.76  536.47
 2095.07  536.47 2108.26  536.72 2108.66  536.72 2108.85  536.73 2109.33  536.73
 2124.03     537 2124.56     537 2124.84  537.01 2129.47  537.09 2139.12   536.8
 2139.26   536.8 2140.43  536.77 2140.72  536.77 2154.51  536.43 2154.71  536.42
 2156.87  536.39 2157.26  536.38 2157.65  536.38 2166.88  536.19  2167.2  536.18
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BR D #Mann= 6
       0      .1 1423.77     .06 2621.75    .035 2710.81    .035 2988.25     .06
 3211.01     .06
BR D Banks=2621.75,2988.25
BC Design=,, 0 ,, 0 ,,,,,,
BC Use User HTab Curves=0
BC User HTab FreeFlow(D)= 0

Type RM Length L Ch R = 1 ,238817  ,83,83,108
BEGIN DESCRIPTION:
This cross section corresponds to cross section 238695.5 of the non-georeferenced CDC model which was the source of this model.
Downstream of Northside Drive.
Ineffective flow in LOB.
Effective flow limit in ROB set at West Fork Levee Loop.
END DESCRIPTION:
XS GIS Cut Line= 3
 2329853.7412212 6972405.5962385  2329079.821977 6970514.0104244
 2328580.2118806 6969446.9087421
#Sta/Elev= 30
       0  565.95  155.39   567.1  165.73  559.46  185.11  559.53  209.28  547.47
  311.85  541.35  436.74  541.03   446.1  545.99  459.72  539.13  513.31     538
  552.97  540.37  839.13  533.43  848.11  537.55  862.63     534  1423.5  530.37
 1433.14  525.02 1445.81  527.79 1989.07  530.86  2428.6   538.8 2493.81  537.73
 2540.43  527.42 2611.66  522.68 2689.84     494 2786.52  490.88 2901.68  496.01
  2979.3  523.34 3092.85  524.07  3140.7  527.53 3175.48  536.49 3222.05  535.66
#Mann= 4 ,-1,0
       0      .1       0  1423.5     .06       0 2611.66    .035       0
  2979.3     .06       0
#XS Ineff= 2 , 0
       0  2497.8     570 3175.48       0     550
Permanent Ineff=
       F       T
Bank Sta=2611.66,2979.3
XS Rating Curve= 0 ,0
Exp/Cntr=0.5,0.3

Type RM Length L Ch R = 1 ,238734  ,329,329,338
BEGIN DESCRIPTION:
This cross section corresponds to cross section 238612.5 of the non-georeferenced CDC model which was the source of this model.
Ineffective flow in LOB.
Effective flow limit in ROB set at West Fork Levee Loop.
END DESCRIPTION:
XS GIS Cut Line= 2
 2329949.4028821 6972383.1899346  2328673.554973 6969424.9456692
#Sta/Elev= 30
       0  551.88   46.36     548   91.64  549.39  148.08  546.25  152.76  548.58
  157.15     546  562.29  538.06 1255.04  533.26 1419.56  531.29 1428.48  528.95
 1478.23  530.46 1578.27  527.73 1891.54  530.17 1982.94  532.12 2009.99  536.26
 2134.18  533.27 2400.19  536.35  2515.6  532.95 2545.69  528.36 2618.16  523.22
 2683.09     496 2702.25  492.98 2757.17  490.31 2902.93  494.55 2917.05     498
 2919.26  501.56  2985.5  524.49 3134.45  526.44 3174.25  535.16 3221.65  534.65
#Mann= 4 ,-1,0
       0      .1       0 1428.48     .06       0 2618.16    .035       0
  2985.5     .06       0
#XS Ineff= 2 , 0
       0 2447.91     570 3174.25       0     550
Permanent Ineff=
       F       T
Bank Sta=2618.16,2985.5
XS Rating Curve= 0 ,0
Exp/Cntr=0.3,0.1

Type RM Length L Ch R = 1 ,238405  ,296,296,313
BEGIN DESCRIPTION:
This cross section corresponds to cross section 238283.8 of the non-georeferenced CDC model which was the source of this model.
Downstream of Sump 28 outfall.
Ineffective flow in LOB.
Effective flow limit in ROB set at West Fork Levee Loop.
END DESCRIPTION:
XS GIS Cut Line= 3
 2330214.2723383 6972279.7705002 2329498.8489508 6970538.9843307
 2329000.3183467 6969352.3298144
#Sta/Elev= 30
       0     564   71.29  565.86   101.5     558  151.49     554  188.22  546.44
  221.91  545.07   435.8  543.64  583.57  538.67  919.98  533.48  1384.3  529.58
 1660.95  525.88  1675.5   523.5 1706.53   527.7 1783.95  531.33 1942.58  527.43
 1978.86  530.31 2305.23  523.26 2606.67   519.4 2662.86     496 2696.84     490
 2732.88   489.6 2830.29   493.1 2876.35     498  2933.5  517.91 2969.95  522.82
 3091.74  525.11  3114.9  533.63 3136.02  534.03 3144.64  537.27 3169.19  536.38
#Mann= 6 ,-1,0
       0      .1       0  1384.3     .06       0 1978.86     .08       0
 2305.23     .06       0 2606.67    .035       0 2969.95     .06       0
#XS Ineff= 2 , 0
       0 2253.32     570 3144.55       0     550
Permanent Ineff=
       F       T
Bank Sta=2606.67,2969.95
XS Rating Curve= 0 ,0
Exp/Cntr=0.5,0.3

Type RM Length L Ch R = 1 ,238109  ,84,84,83
BEGIN DESCRIPTION:
This cross section corresponds to cross section 237987.5 of the non-georeferenced CDC model which was the source of this model.
Upstream of the Union Pacific Railroad.
Ineffective flow in LOB - limit set at Northside Drive.
Effective flow limit in ROB set at West Fork Levee Loop.
END DESCRIPTION:
XS GIS Cut Line= 5
  2330642.738226 6971988.7213785 2329856.2939152 6970715.6645669
 2329722.3982361 6970350.0201539 2329351.7015864 6969414.9695371
 2329312.6522775 6969320.3876277
#Sta/Elev= 30
       0  576.83      83   561.9  445.52  558.54  487.91  533.47  685.12  535.59
   946.7   523.8 1265.24  526.78 1702.81  522.79  1769.2  529.79 1792.98  529.49
 1815.67     524  1887.1     528 1890.76  523.15 1928.79  528.93 1946.17  523.42
 1949.57     528  1957.5  518.81 2012.65     510 2041.03   511.3 2050.05   517.9
 2098.91  519.05 2508.03  521.03  2571.9     494 2594.18  489.55 2645.84  488.02
 2756.74     498 2812.79  518.92 2937.07  527.97 2973.52   536.3 2993.95  536.28
#Mann= 6 ,-1,0
       0      .1       0 1265.24     .06       0  1887.1     .08       0
 2098.91     .06       0 2508.03    .035       0 2812.79     .06       0
#XS Ineff= 2 ,-1
       0 1949.57     580 2973.52 2993.95     550
Permanent Ineff=
       F       T
Bank Sta=2508.03,2812.79
XS Rating Curve= 0 ,0
Exp/Cntr=0.5,0.3

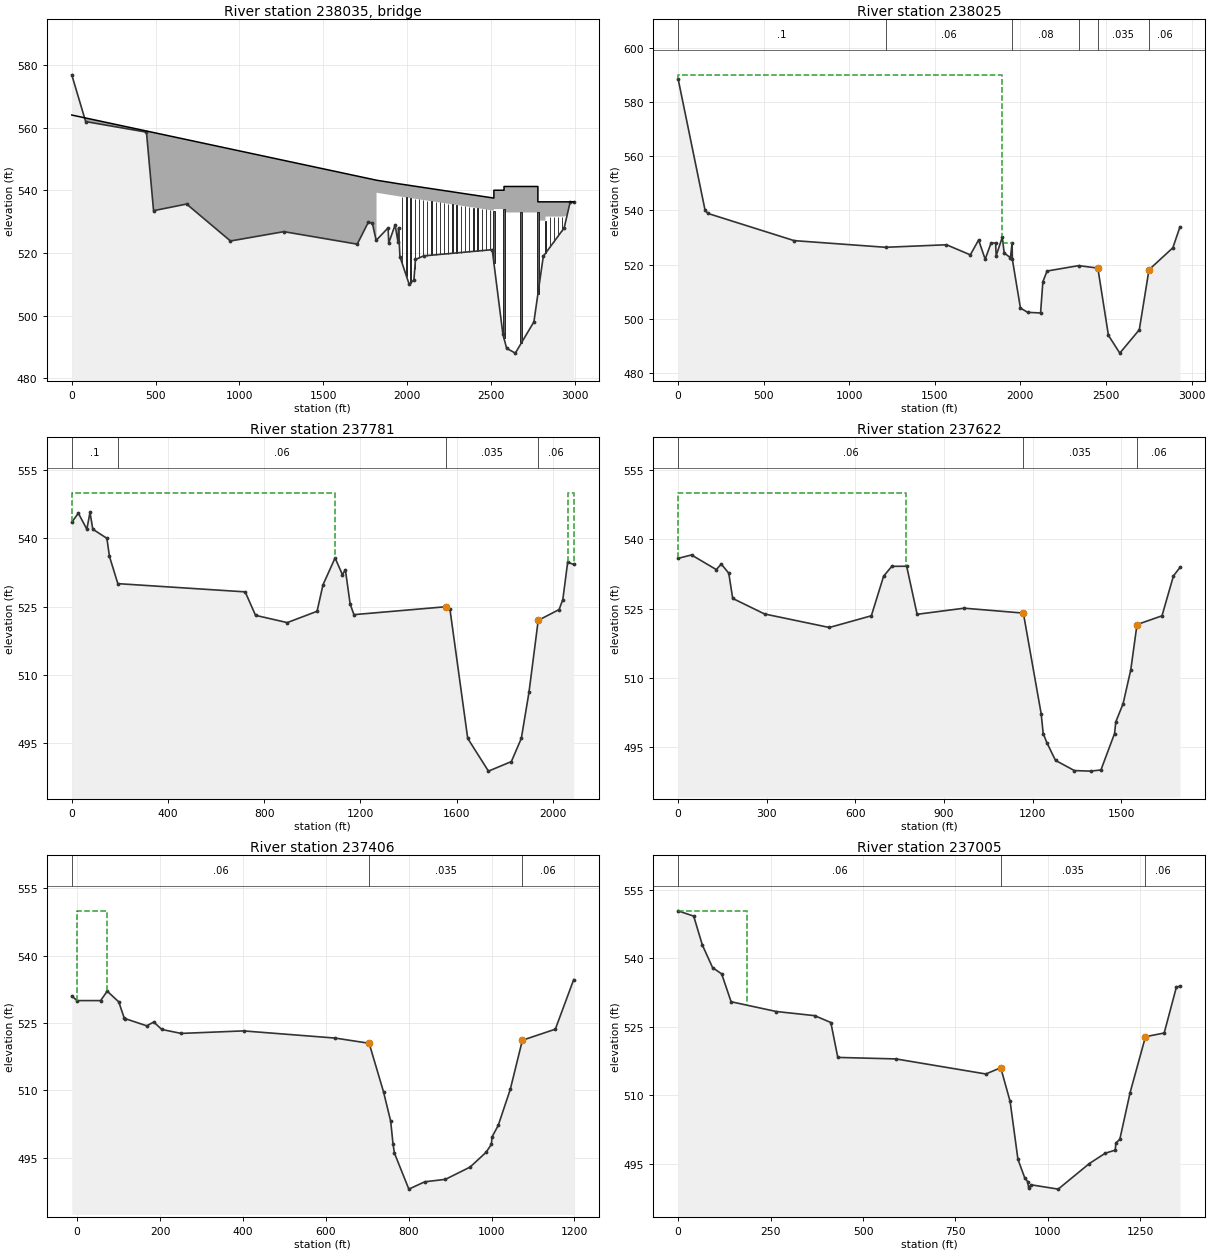
Type RM Length L Ch R = 3 ,238035  ,,,
BEGIN DESCRIPTION:
Union Pacific Railroad
Data from USACE 1949, 1975 survey, TRWD July 2007 field measurements.
END DESCRIPTION:
Node Name=Union Pacific RR
Bridge Culvert--1,0,-1,-1, 0
Deck Dist Width WeirC Skew NumUp NumDn MinLoCord MaxHiCord MaxSubmerge Is_Ogee
39.2,20,2.6,0, 16, 16, , , 0.95, 0, 0,0,,
       0    1818    1818    1946    2518    2518  2578.5  2578.5  2780.5  2780.5
    2826    2826    2826    2955    2955 2993.98
     564   543.2   543.2   542.1   537.5     540     540   541.2   541.2   536.3
   536.3   536.3   536.3   536.3   536.3   536.3
       0       0   539.2   538.1   533.5     534     534   532.9   532.9   530.3
   530.3   530.3   531.6   531.6     450     450
       0    1818    1818    1946    2518    2518  2578.5  2578.5  2780.5  2780.5
    2826    2826    2826    2955    2955 2993.98
     564   543.2   543.2   542.1   537.5     540     540   541.2   541.2   536.3
   536.3   536.3   536.3   536.3   536.3   536.3
       0   539.2   539.2   538.1   533.5     534     534   532.9   532.9   530.3
   530.3   530.3   531.6   531.6     450     450
Pier Skew, UpSta & Num, DnSta & Num=  ,1971, 2 ,1919.06, 2 , 0 , 0 , 0 ,,
       2       2
  487.37   538.1
       2       2
  487.37   538.1
Pier Skew, UpSta & Num, DnSta & Num=  ,1996, 2 ,1944.06, 2 , 0 , 0 , 0 ,,
       2       2
  487.37   538.1
       2       2
  487.37   538.1
Pier Skew, UpSta & Num, DnSta & Num=  ,2021, 2 ,1969.06, 2 , 0 , 0 , 0 ,,
       2       2
  487.37   538.1
       2       2
  487.37   538.1
Pier Skew, UpSta & Num, DnSta & Num=  ,2046, 2 ,1994.06, 2 , 0 , 0 , 0 ,,
       2       2
  487.37   538.1
       2       2
  487.37   538.1
Pier Skew, UpSta & Num, DnSta & Num=  ,2071, 2 ,2019.06, 2 , 0 , 0 , 0 ,,
       2       2
  487.37   538.1
       2       2
  487.37   538.1
Pier Skew, UpSta & Num, DnSta & Num=  ,2096, 2 ,2044.06, 2 , 0 , 0 , 0 ,,
       2       2
  487.37   538.1
       2       2
  487.37   538.1
Pier Skew, UpSta & Num, DnSta & Num=  ,2121, 2 ,2069.06, 2 , 0 , 0 , 0 ,,
       2       2
  487.37   538.1
       2       2
  487.37   538.1
Pier Skew, UpSta & Num, DnSta & Num=  ,2146, 2 ,2094.06, 2 , 0 , 0 , 0 ,,
       2       2
  487.37   538.1
       2       2
  487.37   538.1
Pier Skew, UpSta & Num, DnSta & Num=  ,2171, 2 ,2119.06, 2 , 0 , 0 , 0 ,,
       2       2
  487.37   538.1
       2       2
  487.37   538.1
Pier Skew, UpSta & Num, DnSta & Num=  ,2196, 2 ,2144.06, 2 , 0 , 0 , 0 ,,
       2       2
  487.37   538.1
       2       2
  487.37   538.1
Pier Skew, UpSta & Num, DnSta & Num=  ,2221, 2 ,2169.06, 2 , 0 , 0 , 0 ,,
       2       2
  487.37   538.1
       2       2
  487.37   538.1
Pier Skew, UpSta & Num, DnSta & Num=  ,2246, 2 ,2194.06, 2 , 0 , 0 , 0 ,,
       2       2
  487.37   538.1
       2       2
  487.37   538.1
Pier Skew, UpSta & Num, DnSta & Num=  ,2271, 2 ,2219.06, 2 , 0 , 0 , 0 ,,
       2       2
  487.37   538.1
       2       2
  487.37   538.1
Pier Skew, UpSta & Num, DnSta & Num=  ,2296, 2 ,2244.06, 2 , 0 , 0 , 0 ,,
       2       2
  487.37   538.1
       2       2
  487.37   538.1
Pier Skew, UpSta & Num, DnSta & Num=  ,2321, 2 ,2269.06, 2 , 0 , 0 , 0 ,,
       2       2
  487.37   538.1
       2       2
  487.37   538.1
Pier Skew, UpSta & Num, DnSta & Num=  ,2346, 2 ,2294.06, 2 , 0 , 0 , 0 ,,
       2       2
  487.37   538.1
       2       2
  487.37   538.1
Pier Skew, UpSta & Num, DnSta & Num=  ,2371, 2 ,2319.06, 2 , 0 , 0 , 0 ,,
       2       2
  487.37   538.1
       2       2
  487.37   538.1
Pier Skew, UpSta & Num, DnSta & Num=  ,2396, 2 ,2344.06, 2 , 0 , 0 , 0 ,,
       2       2
  487.37   538.1
       2       2
  487.37   538.1
Pier Skew, UpSta & Num, DnSta & Num=  ,2421, 2 ,2369.06, 2 , 0 , 0 , 0 ,,
       2       2
  487.37   538.1
       2       2
  487.37   538.1
Pier Skew, UpSta & Num, DnSta & Num=  ,2446, 2 ,2394.06, 2 , 0 , 0 , 0 ,,
       2       2
  487.37   538.1
       2       2
  487.37   538.1
Pier Skew, UpSta & Num, DnSta & Num=  ,2471, 2 ,2419.06, 2 , 0 , 0 , 0 ,,
       2       2
  487.37   538.1
       2       2
  487.37   538.1
Pier Skew, UpSta & Num, DnSta & Num=  ,2496, 2 ,2444.06, 2 , 0 , 0 , 0 ,,
       2       2
  487.37   538.1
       2       2
  487.37   538.1
Pier Skew, UpSta & Num, DnSta & Num=  ,2518, 2 ,2466.06, 2 , 0 , 0 , 0 ,,
     9.5       5
     506     535
     9.5       5
     506     535
Pier Skew, UpSta & Num, DnSta & Num=  ,2578, 2 ,2526.06, 2 , 0 , 0 , 0 ,,
    12.5       7
     450     535
    12.5       7
     450     535
Pier Skew, UpSta & Num, DnSta & Num=  ,2682, 2 ,2630.06, 2 , 0 , 0 , 0 ,,
    12.5       7
     450     535
    12.5       7
     450     535
Pier Skew, UpSta & Num, DnSta & Num=  ,2780.5, 2 ,2728.56, 2 , 0 , 0 , 0 ,,
    12.5       7
     450     535
    12.5       7
     450     535
Pier Skew, UpSta & Num, DnSta & Num=  ,2826, 2 ,2776.06, 2 , 0 , 0 , 0 ,,
     4.5       4
     518   535.3
     4.5       4
     518   535.3
Pier Skew, UpSta & Num, DnSta & Num=  ,2852, 4 ,2800.06, 4 , 3 , 3 , 0 ,,
       2       2    2.75    2.75
     500     528     528   535.3
       2       2    2.75    2.75
     500     528     528   535.3
Pier Skew, UpSta & Num, DnSta & Num=  ,2876.5, 4 ,2824.56, 4 , 3 , 3 , 0 ,,
       2       2    2.75    2.75
     500     528     528   535.3
       2       2    2.75    2.75
     500     528     528   535.3
Pier Skew, UpSta & Num, DnSta & Num=  ,2900, 4 ,2848.06, 4 , 3 , 3 , 0 ,,
       2       2    2.75    2.75
     500     528     528   535.3
       2       2    2.75    2.75
     500     528     528   535.3
Pier Skew, UpSta & Num, DnSta & Num=  ,2923, 4 ,2871.06, 4 , 3 , 3 , 0 ,,
       2       2    2.75    2.75
     500     528     528   535.3
       2       2    2.75    2.75
     500     528     528   535.3
BR Coef=-1 , 0 , 0 ,, 0 ,,,0.8,-1,,0,
WSPro=,,,, 1 ,,,, 0 ,,,, 0 ,,,,-1 ,-1 ,-1 , 0 , 0 , 0 , 0 , 0
BC Design=,, 0 ,, 0 ,,22,1971,1919.06,25,2
BC Use User HTab Curves=0
BC User HTab FreeFlow(D)= 0

Type RM Length L Ch R = 1 ,238025  ,244,244,88
BEGIN DESCRIPTION:
This cross section corresponds to cross section 237903.3 of the non-georeferenced CDC model which was the source of this model.
Downstream of the Union Pacific Railroad.
Ineffective flow in LOB - limit set at Northside Drive.
Effective flow limit in ROB set at West Fork Levee Loop.
END DESCRIPTION:
XS GIS Cut Line= 4
 2330760.7049439 6971875.6699999 2329799.0086144 6970314.8131738
 2329430.4429476  6969385.137721 2329392.8709887  6969294.134328
#Sta/Elev= 30
       0  588.62  158.03  540.01  174.56  538.88  677.91  528.86 1212.03   526.4
 1568.07  527.33 1707.31  523.61 1755.63  529.09 1793.98     522 1828.67     528
 1855.01     528 1858.19   523.3 1894.06  530.08 1904.96  524.35  1941.4  522.54
 1951.41     528 1952.87  521.95 1999.91     504 2042.22  502.41 2117.59  502.18
 2131.07  513.72 2155.75  517.65 2340.33  519.64 2452.18  518.73 2513.94  493.94
 2580.42  487.37 2694.37     496 2750.91  518.12 2890.15  526.21 2931.87  533.93
#Mann= 6 ,-1,0
       0      .1       0 1212.03     .06       0 1951.41     .08       0
 2340.33     .06       0 2452.18    .035       0 2750.91     .06       0
#XS Ineff= 2 ,-1
       0 1894.06     590 1894.06  1951.4     528
Permanent Ineff=
       F       F
Bank Sta=2452.18,2750.91
XS Rating Curve= 0 ,0
Exp/Cntr=0.5,0.3

Type RM Length L Ch R = 1 ,237781  ,159,159,72
BEGIN DESCRIPTION:
This cross section corresponds to cross section 237659.6 of the non-georeferenced CDC model which was the source of this model.
Ineffective flow in LOB - limit set at Northside Drive.
Effective flow limit in ROB set at West Fork Levee Loop.
END DESCRIPTION:
XS GIS Cut Line= 3
 2330998.9853389 6970666.9830545 2329859.0641411 6969593.9074122
 2329470.1031089 6969246.7822492
#Sta/Elev= 30
       0  543.53   27.41  545.52   62.72     542   75.84   545.7   87.45     542
  146.03     540  156.84     536  191.57  530.03  721.06  528.22  764.11  523.06
  895.91  521.46  1019.9  523.95 1044.62  529.78  1094.8  535.68 1125.48     532
 1137.67  533.08 1157.52  525.53 1173.25  523.21  1557.2  524.96 1572.23  524.49
 1646.31     496 1732.53   488.8 1827.79   490.9 1869.19     496 1901.03  506.13
 1939.42  521.95 2026.32  524.34 2041.74  526.53 2061.95  534.76 2086.87  534.24
#Mann= 4 ,-1,0
       0      .1       0  191.57     .06       0  1557.2    .035       0
 1939.42     .06       0
#XS Ineff= 2 , 0
       0  1094.8     550 2061.95       0     550
Permanent Ineff=
       F       T
Bank Sta=1557.2,1939.42
XS Rating Curve= 0 ,0
Exp/Cntr=0.3,0.1

Type RM Length L Ch R = 1 ,237622  ,217,217,130
BEGIN DESCRIPTION:
This cross section corresponds to cross section 237501 of the non-georeferenced CDC model which was the source of this model.
Ineffective flow in LOB - limit set at Northside Drive.
Effective flow limit in ROB set at West Fork Levee Loop.
END DESCRIPTION:
XS GIS Cut Line= 3
 2331001.5535894 6970012.7799877 2330374.3443123 6969656.9355291
 2329522.9821572  6969177.691889
#Sta/Elev= 30
       0  535.84   45.53  536.58  129.18  533.43  146.29   534.6  171.53  532.65
   184.9  527.19  292.73  523.83  511.89  520.91  653.97  523.44   695.5     532
  723.18  534.12   773.5  534.14  808.81  523.76  967.92  525.08 1168.26  524.02
 1228.59  502.25 1235.37     498    1248     496 1277.01   492.2 1340.86     490
 1395.67  489.88 1430.69  490.13 1476.81     498 1481.01  500.53 1505.68  504.44
 1531.67  511.76 1552.75  521.54 1637.26  523.43 1676.08  532.06  1698.1  533.88
#Mann= 3 ,-1,0
       0     .06       0 1168.26    .035       0 1552.75     .06       0
#XS Ineff= 2 , 0
       0  770.13     550               0
Permanent Ineff=
       F       F
Bank Sta=1168.26,1552.75
XS Rating Curve= 0 ,0
Exp/Cntr=0.3,0.1

Type RM Length L Ch R = 1 ,237406  ,400,400,413
BEGIN DESCRIPTION:
This cross section corresponds to cross section 237284.1 of the non-georeferenced CDC model which was the source of this model.
Ineffective flow in LOB - limit set at Northside Drive.
Effective flow limit in ROB set at West Fork Levee Loop.
END DESCRIPTION:
XS GIS Cut Line= 3
2330758.343795886969432.26958336 2330746.0312637 6969428.0980667
2329611.154101736969043.59884917
#Sta/Elev= 30
     -13     531       0     530   56.61     530   72.53   532.1   100.4  529.72
  113.18  526.22  116.38  525.97  168.01  524.38  184.88  525.23  204.26  523.57
  250.95  522.69  401.54  523.25  622.94  521.65  704.67  520.49  739.37  509.67
  756.63  503.13  762.35     498  765.77     496  800.48     488   838.8  489.63
  888.72  490.18  948.21  492.91   986.8   496.2  999.76     498  1001.1   499.6
 1016.07  502.18 1045.23  510.22 1074.43  521.17 1153.96  523.63 1198.24  534.67
#Mann= 3 ,-1,0
     -13     .06       0  704.67    .035       0 1074.43     .06       0
#XS Ineff= 2 , 0
       0   72.53     550               0
Permanent Ineff=
       F       F
Bank Sta=704.67,1074.43
XS Rating Curve= 0 ,0
Exp/Cntr=0.3,0.1

Type RM Length L Ch R = 1 ,237005  ,320,320,372
BEGIN DESCRIPTION:
This cross section corresponds to cross section 236883.8 of the non-georeferenced CDC model which was the source of this model.
Ineffective flow in LOB.
Effective flow limit in ROB set at West Fork Levee Loop.
END DESCRIPTION:
XS GIS Cut Line= 2
 2331014.0152632 6969118.5635304 2329737.7838861 6968657.8129535
#Sta/Elev= 30
       0  550.44   42.28  549.28   65.74  542.94   93.31     538  117.89  536.62
  143.42  530.52  265.54  528.38  369.38  527.47  413.03  525.97  431.85  518.32
     589  517.99  832.15  514.69  872.34  516.06  897.73  508.67  918.82     496
   936.9     492  945.01   491.1  947.69  489.79  954.26  490.41 1027.68  489.46
 1111.96  495.07 1155.08  497.34 1181.83     498 1183.55  499.57 1194.24  500.37
  1222.1  510.63 1263.64  522.86 1314.24  523.67 1347.36  533.78 1356.86   533.9
#Mann= 3 ,-1,0
       0     .06       0  872.34    .035       0 1263.64     .06       0
#XS Ineff= 1 ,-1
       0  186.17550.4392
Permanent Ineff=
       F
Bank Sta=872.34,1263.64
XS Rating Curve= 0 ,0
Exp/Cntr=0.3,0.1

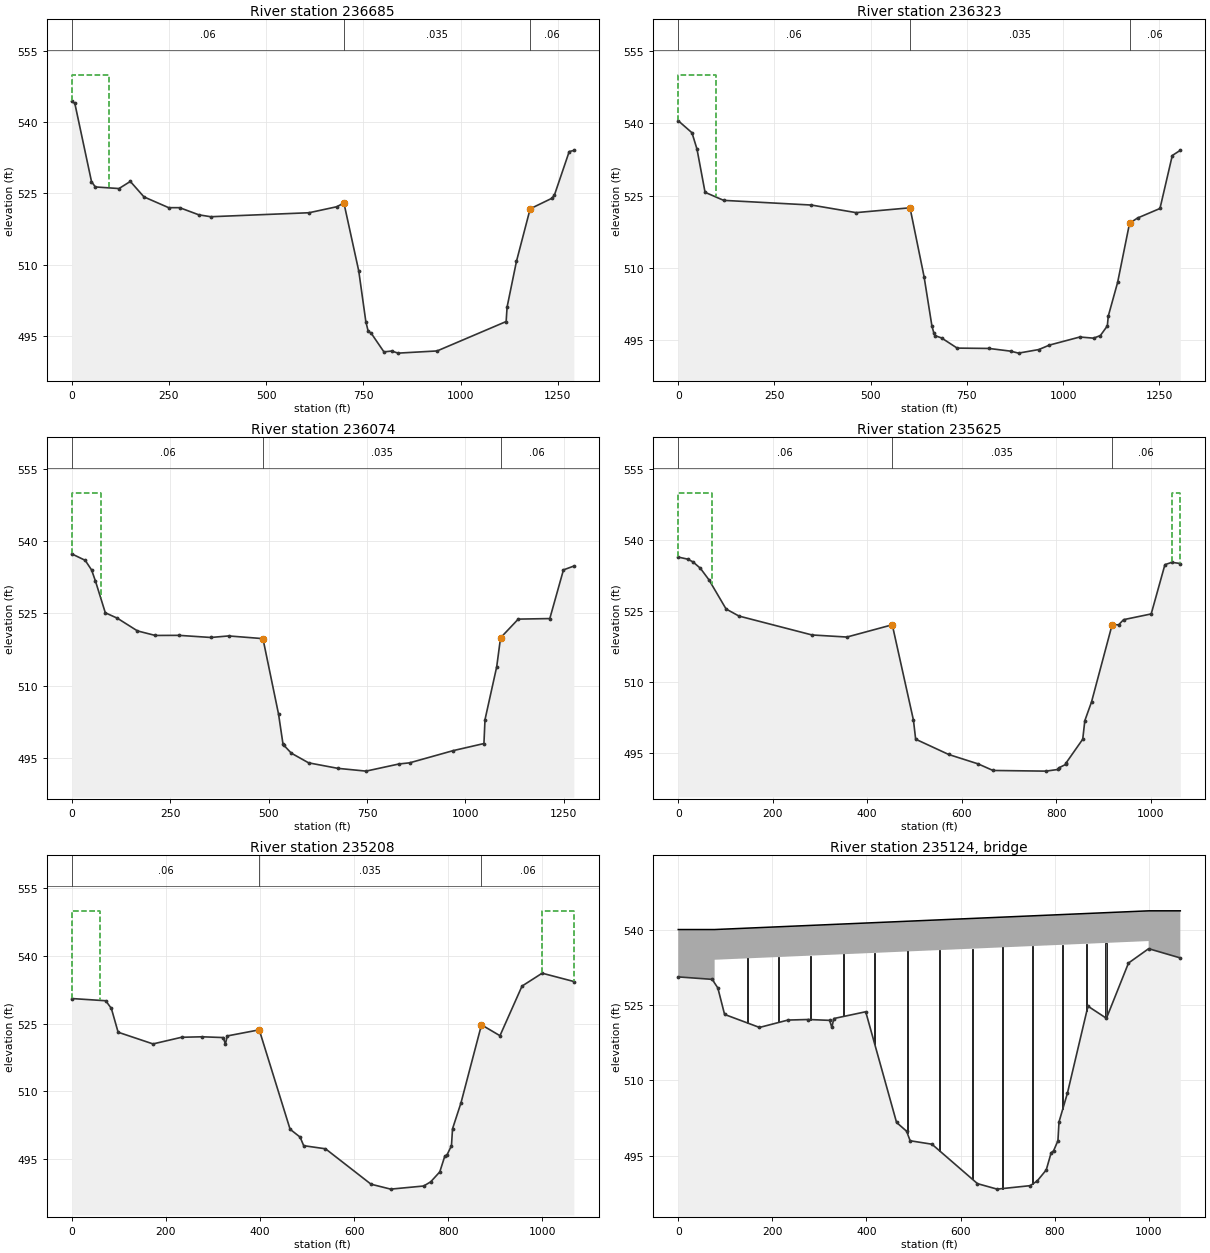
Type RM Length L Ch R = 1 ,236685  ,362,362,420
BEGIN DESCRIPTION:
This cross section corresponds to cross section 236563.3 of the non-georeferenced CDC model which was the source of this model.
Ineffective flow in LOB.
Effective flow limit in ROB set at West Fork Levee Loop.
END DESCRIPTION:
XS GIS Cut Line= 2
  2331000.180079 6968839.4023064 2329816.9359391 6968321.7329142
#Sta/Elev= 30
       0  544.39    7.82     544   50.73  527.51   60.48  526.37  121.48  526.03
  150.64  527.53  185.74  524.27  249.25     522  277.49     522  326.92  520.49
   357.5  520.09  610.29  520.93   681.4  522.19  700.05  522.98  738.23  508.66
  756.42     498  762.34     496  770.53   495.5  803.01   491.6  822.95  491.78
  839.37  491.34  939.77   491.8  1117.4     498 1119.82  501.06  1143.9  510.68
 1179.18  521.76  1234.6  523.96 1241.35   524.6 1279.61  533.83 1291.53  534.06
#Mann= 3 ,-1,0
       0     .06       0  700.05    .035       0 1179.18     .06       0
#XS Ineff= 2 , 0
       0   95.16     550               0
Permanent Ineff=
       F       F
Bank Sta=700.05,1179.18
XS Rating Curve= 0 ,0
Exp/Cntr=0.3,0.1

Type RM Length L Ch R = 1 ,236323  ,249,249,285
BEGIN DESCRIPTION:
This cross section corresponds to cross section 236201.6 of the non-georeferenced CDC model which was the source of this model.
Ineffective flow in LOB.
Effective flow limit in ROB set at West Fork Levee Loop.
END DESCRIPTION:
XS GIS Cut Line= 2
 2331086.4192901 6968552.6300588 2329931.4218874 6967946.9245486
#Sta/Elev= 30
       0  540.49   35.69     538   48.77   534.6   69.69  525.67  118.08     524
  346.03  523.03  461.88  521.46  602.08  522.46  638.51  508.23  658.91     498
  664.04  496.51  666.55     496  684.07   495.5  724.56   493.4  807.19  493.33
  863.39  492.77  883.86  492.36   936.6   493.1  964.33  494.03 1043.21   495.7
  1078.9  495.46 1096.51     496 1114.63     498 1117.01  500.01 1141.34  507.01
 1172.34  519.26 1192.99  520.34 1251.36  522.32 1283.34  533.29 1304.18  534.37
#Mann= 3 ,-1,0
       0     .06       0  602.08    .035       0 1172.34     .06       0
#XS Ineff= 2 , 0
       0   98.84     550               0
Permanent Ineff=
       F       F
Bank Sta=602.08,1172.34
XS Rating Curve= 0 ,0
Exp/Cntr=0.3,0.1

Type RM Length L Ch R = 1 ,236074  ,449,449,1339
BEGIN DESCRIPTION:
This cross section corresponds to cross section 235952.9 of the non-georeferenced CDC model which was the source of this model.
Ineffective flow in LOB.
Effective flow limit in ROB set at West Fork Levee Loop.
END DESCRIPTION:
XS GIS Cut Line= 3
 2331122.2082134 6968335.7960013 2331073.6685245 6968303.8157011
 2330021.7335342 6967691.7099826
#Sta/Elev= 30
       0  537.34   34.09     536   50.36     534   60.26  531.67   85.21  525.12
  115.66     524  166.88  521.36  212.04  520.42   272.3  520.44  353.26     520
   398.4  520.32  485.55  519.76  525.14  504.12  536.28     498  539.06  497.61
  557.74     496  601.54     494   675.5  492.86  747.45  492.28  831.42  493.77
  857.99     494  968.59  496.53 1046.84     498 1049.54  502.96 1079.27  513.92
 1089.03  519.93 1134.04  523.81 1214.13  523.92 1248.78  534.02 1275.19  534.81
#Mann= 3 ,-1,0
       0     .06       0  485.55    .035       0 1089.03     .06       0
#XS Ineff= 2 , 0
       0   73.57     550               0
Permanent Ineff=
       F       F
Bank Sta=485.55,1089.03
XS Rating Curve= 0 ,0
Exp/Cntr=0.3,0.1

Type RM Length L Ch R = 1 ,235625  ,417,417,1094
BEGIN DESCRIPTION:
This cross section corresponds to cross section 235503.9 of the non-georeferenced CDC model which was the source of this model.
Ineffective flow in LOB.
Effective flow limit in ROB set at West Fork Levee Loop.
END DESCRIPTION:
XS GIS Cut Line= 3
 2331104.2959266 6968314.7061672 2331083.4500705 6968268.1859729
  2330626.201783 6967365.5658876
#Sta/Elev= 30
       0  536.44   20.06     536   31.25  535.42   46.81  534.08   64.89  531.66
  101.29  525.48  128.57  523.99  283.19     520  357.01  519.56  453.07  522.15
  497.88  502.03  502.57     498  572.59  494.77  634.74  492.79  666.28   491.4
  778.55  491.26  803.68  491.61  806.65     492  819.87  492.66  821.11     493
  856.26     498  860.68  501.91  874.85  505.86  918.47  522.16  932.19  522.14
  942.78  523.23 1001.18  524.44 1030.24  534.84 1044.92  535.33 1062.81  535.08
#Mann= 3 ,-1,0
       0     .06       0  453.07    .035       0  918.47     .06       0
#XS Ineff= 2 , 0
       0   72.06     550 1044.92       0     550
Permanent Ineff=
       F       T
Bank Sta=453.07,918.47
XS Rating Curve= 0 ,0
Exp/Cntr=0.5,0.3

Type RM Length L Ch R = 1 ,235208  ,150,150,182
BEGIN DESCRIPTION:
This cross section corresponds to cross section 235086.8 of the non-georeferenced CDC model which was the source of this model.
Upstream of IH 35 W.
Ineffective flow in LOB.
Effective flow limit in ROB set at West Fork Levee Loop.
END DESCRIPTION:
XS GIS Cut Line= 4
 2331083.4148091  6968197.247888 2331095.3266898 6968116.7595305
 2331214.0924939 6967220.0777549 2331225.9198509 6967139.9295666
#Sta/Elev= 30
       0  530.58   72.15  530.09   84.16  528.38   98.49  523.12  172.66  520.53
   233.2     522  276.61  522.11  321.74  521.94  326.45  520.52  330.51   522.3
  398.37  523.65  463.93  501.64  485.19   499.9  492.81     498  539.16  497.31
  635.92  489.47  677.63  488.38  747.81  489.07  762.73     490  782.02   492.2
  792.46  495.62  797.57     496  806.84     498   809.1  501.74  827.08  507.49
  870.61  524.76   909.9  522.35  956.79  533.34  999.56  536.19 1066.89  534.35
#Mann= 3 ,-1,0
       0     .06       0  398.37    .035       0  870.61     .06       0
#XS Ineff= 2 , 0
       0      60     550  999.56       0     550
Permanent Ineff=
       F       T
Bank Sta=398.37,870.61
XS Rating Curve= 0 ,0
Exp/Cntr=0.5,0.3

Type RM Length L Ch R = 3 ,235124  ,,,
BEGIN DESCRIPTION:
IH 35 W
Upstream bridge represented.  Bridge length 922.2 feet.
Data from USACE 1975 survey.
END DESCRIPTION:
Node Name=IH 35E
Bridge Culvert--1,0,-1,-1, 0
Deck Dist Width WeirC Skew NumUp NumDn MinLoCord MaxHiCord MaxSubmerge Is_Ogee
17.5,132,2.6,0, 6, 6, , , 0.95, 0, 0,0,,
       0   77.36   77.36  999.56  999.56 1066.89
     540     540     540  543.72  543.72  543.72
     450     450  533.99  537.71     450     450
       0   77.36   77.36  999.56  999.56 1066.89
     540     540     540  543.72  543.72  543.72
     450     450  533.99  537.71     450     450
Pier Skew, UpSta & Num, DnSta & Num=  ,146.36, 2 ,146.36, 2 , 0 , 0 , 0 ,,
     2.5     2.5
     460     539
     2.5     2.5
     460     539
Pier Skew, UpSta & Num, DnSta & Num=  ,213.86, 2 ,213.86, 2 , 0 , 0 , 0 ,,
     2.5     2.5
     460     539
     2.5     2.5
     460     539
Pier Skew, UpSta & Num, DnSta & Num=  ,281.76, 2 ,281.76, 2 , 0 , 0 , 0 ,,
     2.5     2.5
     460     539
     2.5     2.5
     460     539
Pier Skew, UpSta & Num, DnSta & Num=  ,351.66, 2 ,351.66, 2 , 0 , 0 , 0 ,,
     2.5     2.5
     460     539
     2.5     2.5
     460     539
Pier Skew, UpSta & Num, DnSta & Num=  ,417.36, 2 ,417.36, 2 , 0 , 0 , 0 ,,
     2.5     2.5
     460     539
     2.5     2.5
     460     539
Pier Skew, UpSta & Num, DnSta & Num=  ,486.36, 2 ,486.36, 2 , 0 , 0 , 0 ,,
     2.5     2.5
     460     539
     2.5     2.5
     460     539
Pier Skew, UpSta & Num, DnSta & Num=  ,555.61, 2 ,555.61, 2 , 0 , 0 , 0 ,,
     2.5     2.5
     460     539
     2.5     2.5
     460     539
Pier Skew, UpSta & Num, DnSta & Num=  ,624.86, 2 ,624.86, 2 , 0 , 0 , 0 ,,
     2.5     2.5
     460     539
     2.5     2.5
     460     539
Pier Skew, UpSta & Num, DnSta & Num=  ,688.36, 2 ,688.36, 2 , 0 , 0 , 0 ,,
     2.5     2.5
     460     539
     2.5     2.5
     460     539
Pier Skew, UpSta & Num, DnSta & Num=  ,751.96, 2 ,751.96, 2 , 0 , 0 , 0 ,,
     2.5     2.5
     460     539
     2.5     2.5
     460     539
Pier Skew, UpSta & Num, DnSta & Num=  ,817.36, 2 ,817.36, 2 , 0 , 0 , 0 ,,
     2.5     2.5
     460     539
     2.5     2.5
     460     539
Pier Skew, UpSta & Num, DnSta & Num=  ,868.36, 2 ,868.36, 2 , 0 , 0 , 0 ,,
     2.5     2.5
     460     539
     2.5     2.5
     460     539
Pier Skew, UpSta & Num, DnSta & Num=  ,909, 2 ,909, 2 , 0 , 0 , 0 ,,
     2.5     2.5
     460     539
     2.5     2.5
     460     539
Abutment Skew #Up #Dn= , 2 , 2
   77.36   98.49
  533.99  523.12
   77.36   98.49
  533.99  523.12
BR Coef=-1 , 0 , 0 ,, 0 ,,,0.8,-1,,0,
WSPro=,,,, 1 ,,,, 0 ,,,, 0 ,,,,-1 ,-1 ,-1 , 0 , 0 , 0 , 0 , 0
BC Design=,, 0 ,, 0 ,,,,,,
BC Use User HTab Curves=0
BC User HTab FreeFlow(D)= 0