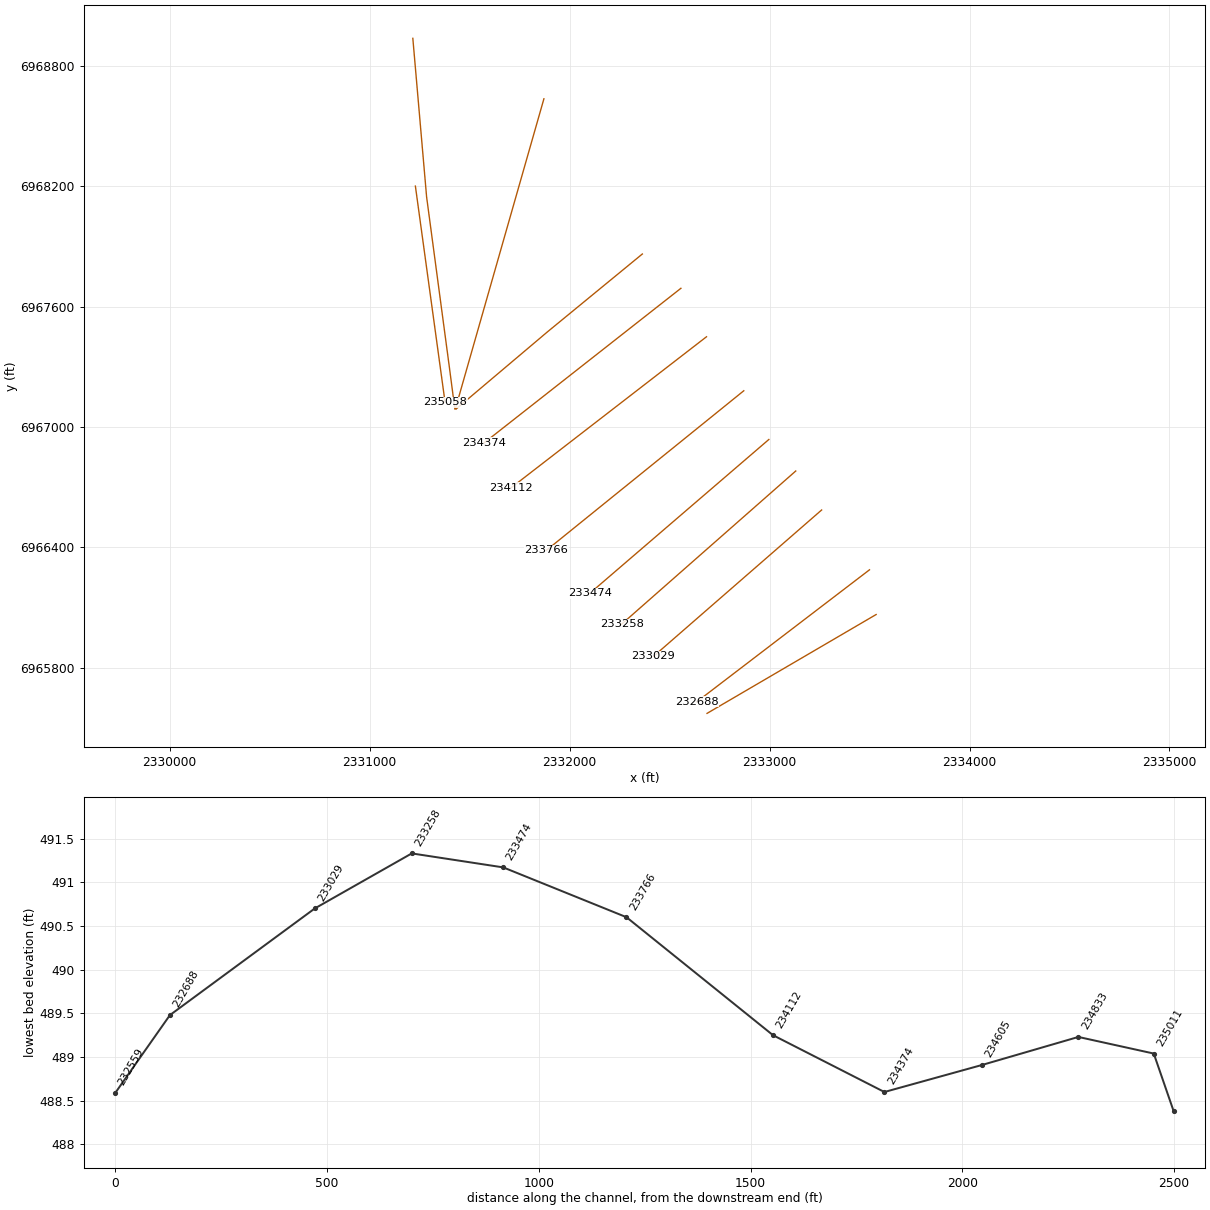
HEC-RAS study CDC_Consolidated_Model.prj: Upper Trinity CDC Consolidated Model

--- CDC_Consolidated_Model.g03 (geometry) --- (continued)

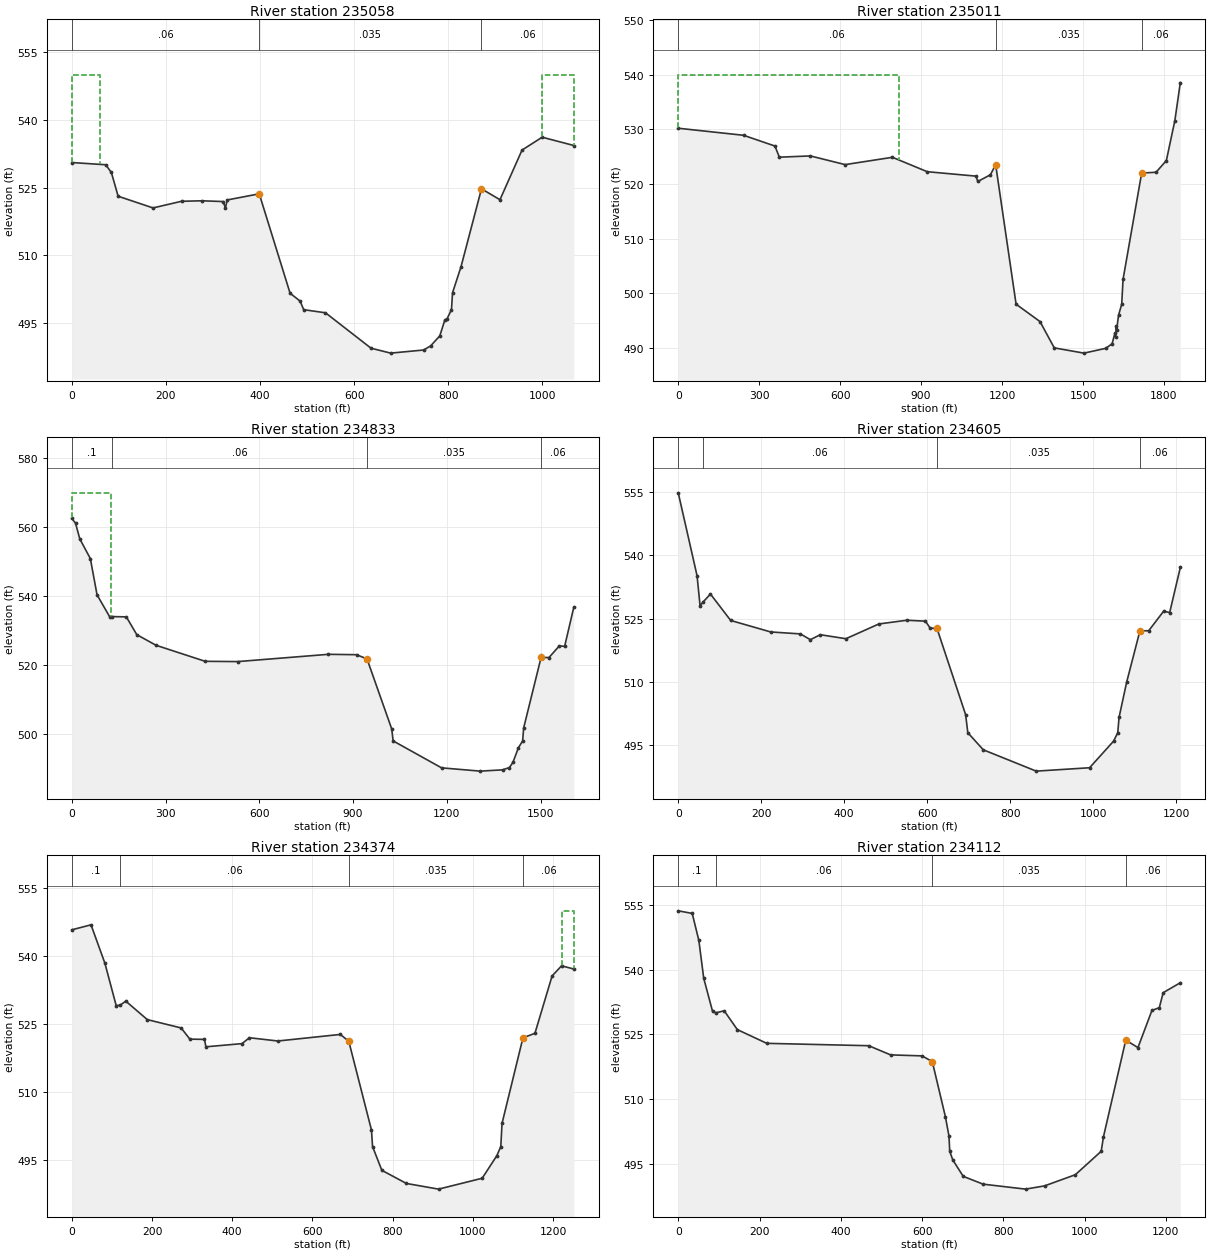
Type RM Length L Ch R = 1 ,235058  ,47,47,47
BEGIN DESCRIPTION:
This cross section corresponds to cross section 234926.2 of the non-georeferenced CDC model which was the source of this model.
Downstream of IH 35 W.
Copy  of cross-section 234926.2
Ineffective flow in LOB.
Effective flow limit in ROB set at West Fork Levee Loop.
END DESCRIPTION:
XS GIS Cut Line= 2
     2331229.195     6968201.438     2331377.632     6967123.313
#Sta/Elev= 30
       0  530.58   72.15  530.09   84.16  528.38   98.49  523.12  172.66  520.53
   233.2     522  276.61  522.11  321.74  521.94  326.45  520.52  330.51   522.3
  398.37  523.65  463.93  501.64  485.19   499.9  492.81     498  539.16  497.31
  635.92  489.47  677.63  488.38  747.81  489.07  762.73     490  782.02   492.2
  792.46  495.62  797.57     496  806.84     498   809.1  501.74  827.08  507.49
  870.61  524.76   909.9  522.35  956.79  533.34  999.56  536.19 1066.89  534.35
#Mann= 3 ,-1,0
       0     .06       0  398.37    .035       0  870.61     .06       0
#XS Ineff= 2 , 0
       0      60     550  999.56       0     550
Permanent Ineff=
       F       T
Bank Sta=398.37,870.61
XS Rating Curve= 0 ,0
Exp/Cntr=0.5,0.3

Type RM Length L Ch R = 1 ,235011  ,178,178,23
BEGIN DESCRIPTION:
This cross section corresponds to cross section 234889.2 of the non-georeferenced CDC model which was the source of this model.
Ineffective flow in LOB.
Effective flow limit in ROB set at West Fork Levee Loop.
END DESCRIPTION:
XS GIS Cut Line= 4
 2331216.4159886 6968938.2483854 2331285.2985397 6968147.5301822
 2331398.2127617  6967304.916491 2331426.5166691 6967090.1397823
#Sta/Elev= 30
       0  530.22  241.96  528.93  358.32  526.96   374.7  524.92  489.53  525.15
  618.54  523.56  793.71   524.9   922.8  522.26 1103.29  521.45 1110.11  520.47
  1156.8   521.7 1176.25  523.55 1251.95     498 1340.55  494.82 1393.46     490
 1503.36  489.04 1584.41  489.92 1607.78  490.76 1618.13   492.7 1620.38  492.02
 1623.69     494 1624.65  493.35  1631.7     496 1643.37     498 1648.32  502.54
 1717.28  522.01  1770.7  522.16 1808.83  524.31 1840.29  531.63 1860.49  538.57
#Mann= 3 ,-1,0
       0     .06       0 1176.25    .035       0 1717.28     .06       0
#XS Ineff= 1 ,-1
       0  819.32     540
Permanent Ineff=
       F
Bank Sta=1176.25,1717.28
XS Rating Curve= 0 ,0
Exp/Cntr=0.3,0.1

Type RM Length L Ch R = 1 ,234833  ,227,227,24
BEGIN DESCRIPTION:
This cross section corresponds to cross section 234711.5 of the non-georeferenced CDC model which was the source of this model.
Ineffective flow in LOB.
Effective flow limit in ROB set at West Fork Levee Loop.
END DESCRIPTION:
XS GIS Cut Line= 2
 2331871.8412788 6968636.6834503   2331429.62136 6967092.3296207
#Sta/Elev= 30
       0  562.55   11.98  561.22   25.63  556.64   59.45  550.91   80.87   540.4
  121.23  534.03  128.67  534.08  174.59     534  207.98  528.84  269.75  525.75
  426.87   521.1  530.85  521.02  821.19  523.13  911.12  523.02  944.65   521.8
 1023.72  501.47 1028.22     498 1183.22  490.18 1306.81  489.23 1378.53   489.6
 1400.35  490.28 1411.61  491.78 1428.99     496 1442.63     498 1445.83  501.75
 1501.56  522.21 1526.85   522.2 1560.24   525.6  1576.9  525.43 1606.42  536.84
#Mann= 4 ,-1,0
       0      .1       0  128.67     .06       0  944.65    .035       0
 1501.56     .06       0
#XS Ineff= 1 ,-1
       0  123.93     570
Permanent Ineff=
       F
Bank Sta=944.65,1501.56
XS Rating Curve= 0 ,0
Exp/Cntr=0.3,0.1

Type RM Length L Ch R = 1 ,234605  ,231,231,217
BEGIN DESCRIPTION:
This cross section corresponds to cross section 234484.1 of the non-georeferenced CDC model which was the source of this model.
Riverside Park in LOB.
Effective flow limit in ROB set at West Fork Levee Loop.
END DESCRIPTION:
XS GIS Cut Line= 3
 2332364.0520498 6967862.7505941 2331889.1915866 6967474.2082914
 2331432.7545712 6967089.6440481
#Sta/Elev= 30
       0  554.74   45.42  535.12   52.64     528   59.19  528.84   77.69   530.8
  126.45  524.55  223.02  521.83  294.53  521.37  318.54     520  342.36  521.18
  404.17  520.23  483.65  523.72   551.1   524.6  596.08  524.38  607.35  522.73
   623.8  522.66  692.85  502.27  698.14     498  735.33  493.96  863.05  488.91
  991.68  489.71 1049.48     496  1059.6     498 1062.76  501.63 1080.97  509.92
 1113.01  522.08 1134.22  522.12 1170.29  526.75 1184.79  526.42 1210.41  537.09
#Mann= 4 ,-1,0
       0      .1       0   59.19     .06       0   623.8    .035       0
 1113.01     .06       0
Bank Sta=623.8,1113.01
XS Rating Curve= 0 ,0
Exp/Cntr=0.3,0.1

Type RM Length L Ch R = 1 ,234374  ,263,263,258
BEGIN DESCRIPTION:
This cross section corresponds to cross section 234252.7 of the non-georeferenced CDC model which was the source of this model.
Riverside Park in LOB.
Effective flow limit in ROB set at West Fork Levee Loop.
Trib in Riverside Park removed from conveyance - original cross-section data removed.
END DESCRIPTION:
XS GIS Cut Line= 2
 2332557.0001198 6967691.7991732 2331571.7371001  6966920.104251
#Sta/Elev= 30
       0  545.81   47.95  546.91   82.48  538.47  110.68   529.1  120.14  529.17
  134.78  530.07  188.28     526  272.64  524.16  294.37  521.69  330.83  521.64
  334.31     520  424.22   520.7  442.86     522  513.62  521.28  669.52  522.73
   690.5  521.22  747.07  501.63  749.73     498   772.9  492.75   834.2  489.85
  914.28   488.6    1023     491 1059.71     496 1069.42     498 1072.51   503.1
 1124.61  521.97 1154.53  522.98 1197.27  535.63 1220.91  537.87  1251.5  537.16
#Mann= 4 ,-1,0
       0      .1       0  120.14     .06       0   690.5    .035       0
 1124.61     .06       0
#XS Ineff= 2 , 0
       0                 1220.91       0     550
Permanent Ineff=
       F       T
Bank Sta=690.5,1124.61
XS Rating Curve= 0 ,0
Exp/Cntr=0.3,0.1

Type RM Length L Ch R = 1 ,234112  ,346,346,358
BEGIN DESCRIPTION:
This cross section corresponds to cross section 233990.2 of the non-georeferenced CDC model which was the source of this model.
Riverside Park in LOB.
Effective flow limit in ROB set at West Fork Levee Loop.
END DESCRIPTION:
XS GIS Cut Line= 2
 2332684.8721876 6967450.0448794 2331706.4220129 6966695.8820169
#Sta/Elev= 30
       0  553.58   34.41  552.98   50.74  546.73   62.67  538.01   84.37  530.37
   92.16     530  113.07  530.47   145.5  526.12  217.84  522.95  468.72   522.4
  522.55  520.28  599.93  520.05  625.11  518.73  657.32     506  666.15  501.52
  668.02     498  675.56     496  701.22   492.2  750.11   490.4  854.63  489.25
   901.4     490  977.09  492.58 1040.75     498 1046.34  501.37 1101.14  523.68
 1131.17  521.97 1165.55  530.55 1183.71   531.2 1193.25  534.66 1235.37  536.96
#Mann= 4 ,-1,0
       0      .1       0   92.16     .06       0  625.11    .035       0
 1101.14     .06       0
Bank Sta=625.11,1101.14
XS Rating Curve= 0 ,0
Exp/Cntr=0.3,0.1

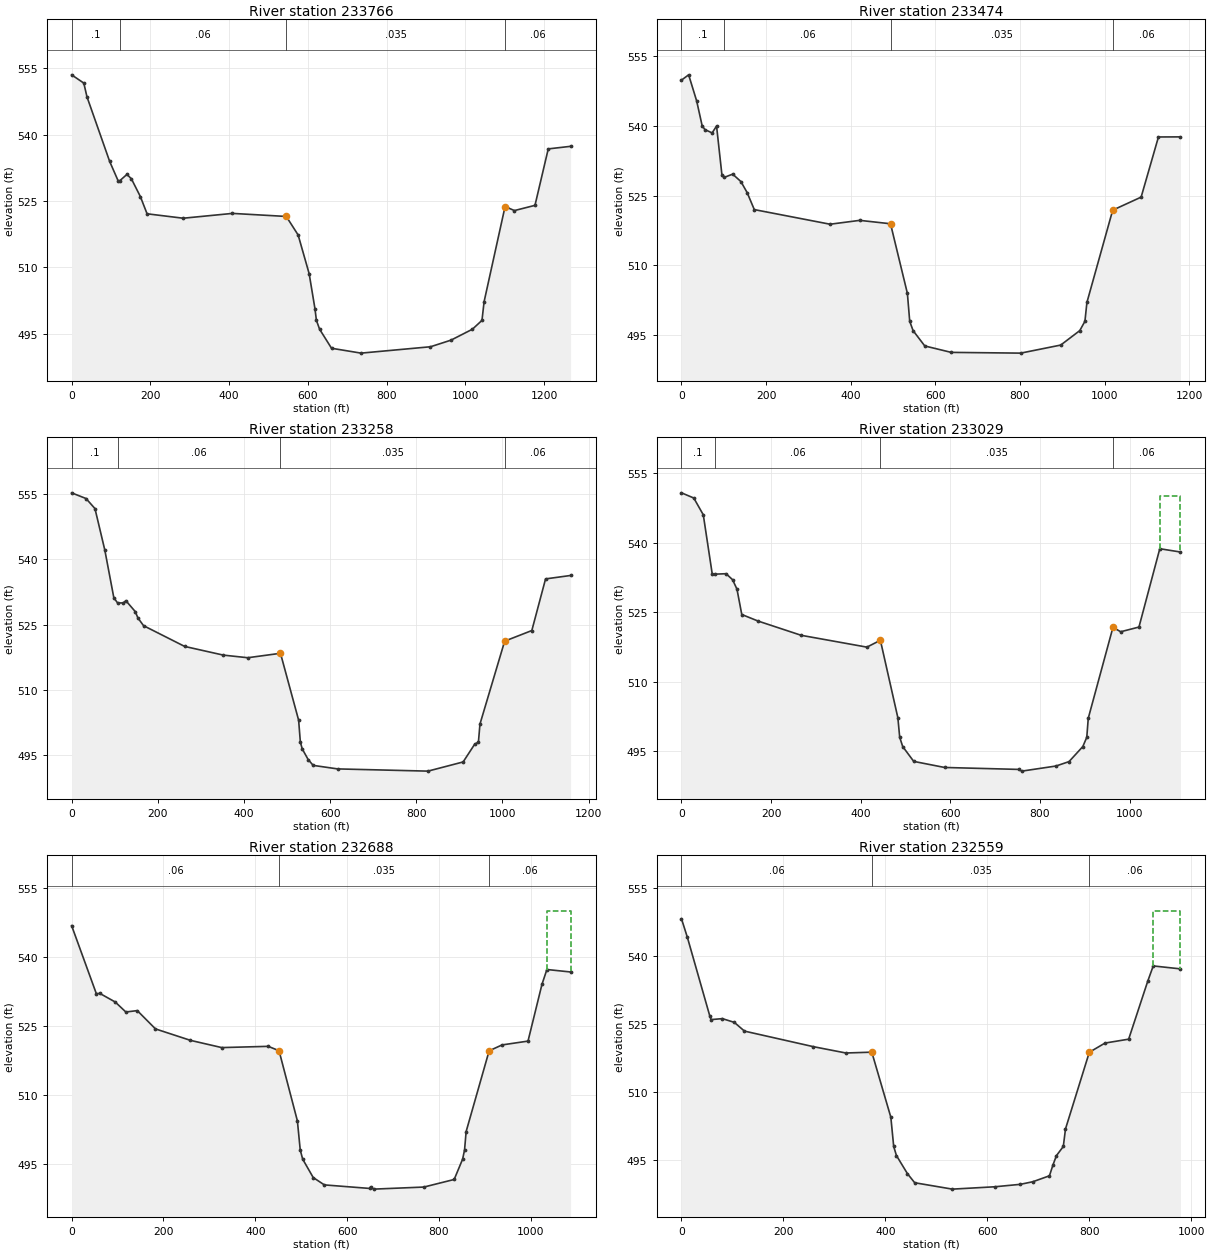
Type RM Length L Ch R = 1 ,233766  ,291,291,311
BEGIN DESCRIPTION:
This cross section corresponds to cross section 233644.6 of the non-georeferenced CDC model which was the source of this model.
Riverside Park in LOB.
Effective flow limit in ROB set at West Fork Levee Loop.
END DESCRIPTION:
XS GIS Cut Line= 2
 2332871.3950291 6967180.7900425 2331884.7011993 6966385.3632718
#Sta/Elev= 30
       0   553.5   30.96  551.63   38.93  548.55   96.63  533.93  118.76  529.42
  122.43  529.57  140.54     531  151.83     530  174.59  525.99  191.66  522.09
  283.42  521.09  408.59  522.18  545.27  521.49  575.36   517.3   603.3  508.57
  618.11  500.62  621.78     498  629.89     496  660.16   491.7  735.13   490.6
  911.51  492.04   963.5  493.53  1017.9     496 1042.28     498 1047.71  502.24
 1100.94  523.73 1124.73  522.82  1176.9     524 1210.62  536.76 1267.39  537.34
#Mann= 4 ,-1,0
       0      .1       0  122.43     .06       0  545.27    .035       0
 1100.94     .06       0
Bank Sta=545.27,1100.94
XS Rating Curve= 0 ,0
Exp/Cntr=0.3,0.1

Type RM Length L Ch R = 1 ,233474  ,216,216,223
BEGIN DESCRIPTION:
This cross section corresponds to cross section 233353.1 of the non-georeferenced CDC model which was the source of this model.
Riverside Park in LOB.
Effective flow limit in ROB set at West Fork Levee Loop.
END DESCRIPTION:
XS GIS Cut Line= 2
 2332996.7072729 6966937.7860421 2332101.1121197 6966170.3895139
#Sta/Elev= 30
       0  549.77   16.94  550.91   35.95  545.28   48.83  539.99   55.34  539.16
   72.47  538.44   82.91  539.92   95.69  529.36  101.43  528.91  121.02  529.59
  140.44     528  155.09  525.65  172.11  521.98  351.23  518.84  421.34  519.67
  494.08  518.94  533.97  503.99  539.46     498  547.44     496  575.06  492.71
  637.59  491.33  801.82  491.17  896.37   492.9  941.35     496  953.58     498
  958.31  502.06 1019.24  521.86 1086.43  524.66 1127.36  537.57  1179.4  537.59
#Mann= 4 ,-1,0
       0      .1       0  101.43     .06       0  494.08    .035       0
 1019.24     .06       0
Bank Sta=494.08,1019.24
XS Rating Curve= 0 ,0
Exp/Cntr=0.3,0.1

Type RM Length L Ch R = 1 ,233258  ,229,229,225
BEGIN DESCRIPTION:
This cross section corresponds to cross section 233136.9 of the non-georeferenced CDC model which was the source of this model.
Riverside Park in LOB.
Effective flow limit in ROB set at West Fork Levee Loop.
END DESCRIPTION:
XS GIS Cut Line= 2
  2333131.140948 6966780.6311734 2332260.5242383 6966016.8603496
#Sta/Elev= 30
       0  555.31   33.43     554   54.18  551.69   77.02  542.17   98.03  531.17
  106.67     530  119.77     530  125.98  530.51  147.78     528  153.82  526.55
  166.98  524.77  262.33     520  352.23     518  408.85   517.4  484.79  518.42
  526.91  503.04   530.9     498  535.39  496.42  548.99     494  560.68  492.65
  617.46  491.84  827.09  491.33  908.72  493.44   935.4   497.5   944.2     498
  947.78  502.15 1005.11  521.21 1068.14  523.65 1100.04  535.52 1158.15  536.31
#Mann= 4 ,-1,0
       0      .1       0  106.67     .06       0  484.79    .035       0
 1005.11     .06       0
Bank Sta=484.79,1005.11
XS Rating Curve= 0 ,0
Exp/Cntr=0.3,0.1

Type RM Length L Ch R = 1 ,233029  ,342,342,305
BEGIN DESCRIPTION:
This cross section corresponds to cross section 232908.1 of the non-georeferenced CDC model which was the source of this model.
Riverside Park in LOB.
Effective flow limit in ROB set at West Fork Levee Loop.
END DESCRIPTION:
XS GIS Cut Line= 2
 2333260.7002492 6966586.3186676 2332419.7240106 6965856.2195258
#Sta/Elev= 30
       0  550.74   27.45  549.62   48.67     546   68.78  533.14   73.95  533.19
    99.6  533.29     114     532  123.84  529.96  134.59  524.49  171.13  523.07
  267.27     520  413.86  517.45  443.93  518.93  482.96  502.21  487.05     498
  493.76     496  518.35   492.8   587.2  491.49  752.93  491.07   759.6   490.7
  835.73   491.8  864.91  492.75  895.75     496   904.6     498  907.86  502.09
  962.99  521.71  980.31  520.77 1021.03  521.78 1067.54  538.68 1113.68  537.97
#Mann= 4 ,-1,0
       0      .1       0   73.95     .06       0  443.93    .035       0
  962.99     .06       0
#XS Ineff= 2 , 0
       0                 1067.54       0     550
Permanent Ineff=
       F       T
Bank Sta=443.93,962.99
XS Rating Curve= 0 ,0
Exp/Cntr=0.3,0.1

Type RM Length L Ch R = 1 ,232688  ,129,129,72
BEGIN DESCRIPTION:
This cross section corresponds to cross section 232566.4 of the non-georeferenced CDC model which was the source of this model.
Riverside Park in LOB.
Effective flow limit in ROB set at West Fork Levee Loop.
END DESCRIPTION:
XS GIS Cut Line= 2
 2333499.9264801 6966287.8844806  2332635.853747 6965629.3559255
#Sta/Elev= 30
       0  546.78   53.77     532   61.63  532.03   94.99  530.17  118.06     528
  142.99   528.3  182.62  524.32  258.82  521.83   326.9  520.26  428.05  520.53
  451.62  519.58  491.57  504.32  497.75     498  503.07     496  526.02     492
  550.27   490.4  650.14  489.62  650.92     490  657.44  489.48  766.94  489.93
  832.92  491.58   851.3     496  855.53     498  858.96     502  909.06  519.56
  937.25  520.84  993.68  521.67 1024.06  534.01 1034.82  537.24 1086.41   536.7
#Mann= 3 ,-1,0
       0     .06       0  451.62    .035       0  909.06     .06       0
#XS Ineff= 2 , 0
       0                 1034.82       0     550
Permanent Ineff=
       F       T
Bank Sta=451.62,909.06
XS Rating Curve= 0 ,0
Exp/Cntr=0.3,0.1

Type RM Length L Ch R = 1 ,232559  ,133,133,77
BEGIN DESCRIPTION:
This cross section corresponds to cross section 232437.7 of the non-georeferenced CDC model which was the source of this model.
Riverside Park in LOB.
Effective flow limit in ROB set at West Fork Levee Loop.
END DESCRIPTION:
XS GIS Cut Line= 2
 2333533.0862232 6966064.9106566 2332687.6096152 6965571.9455244
#Sta/Elev= 30
       0  548.25   11.64  544.12   55.79   526.7    58.1     526   80.16  526.21
  103.58  525.39  123.52  523.46  258.91  520.02  322.39  518.63  373.28  518.81
  410.62  504.46  416.25     498  421.61     496  443.21     492  457.43     490
  531.28  488.59  614.83  489.11  664.68  489.65  689.12  490.22  721.71  491.53
  728.85     494  735.54     496  748.92     498  753.19  501.87  799.92  518.79
  830.73  520.82  877.09  521.68  914.49  534.46   925.3  537.84   978.7  537.19
#Mann= 3 ,-1,0
       0     .06       0  373.28    .035       0  799.92     .06       0
#XS Ineff= 2 , 0
       0                   925.3       0     550
Permanent Ineff=
       F       T
Bank Sta=373.28,799.92
XS Rating Curve= 0 ,0
Exp/Cntr=0.3,0.1