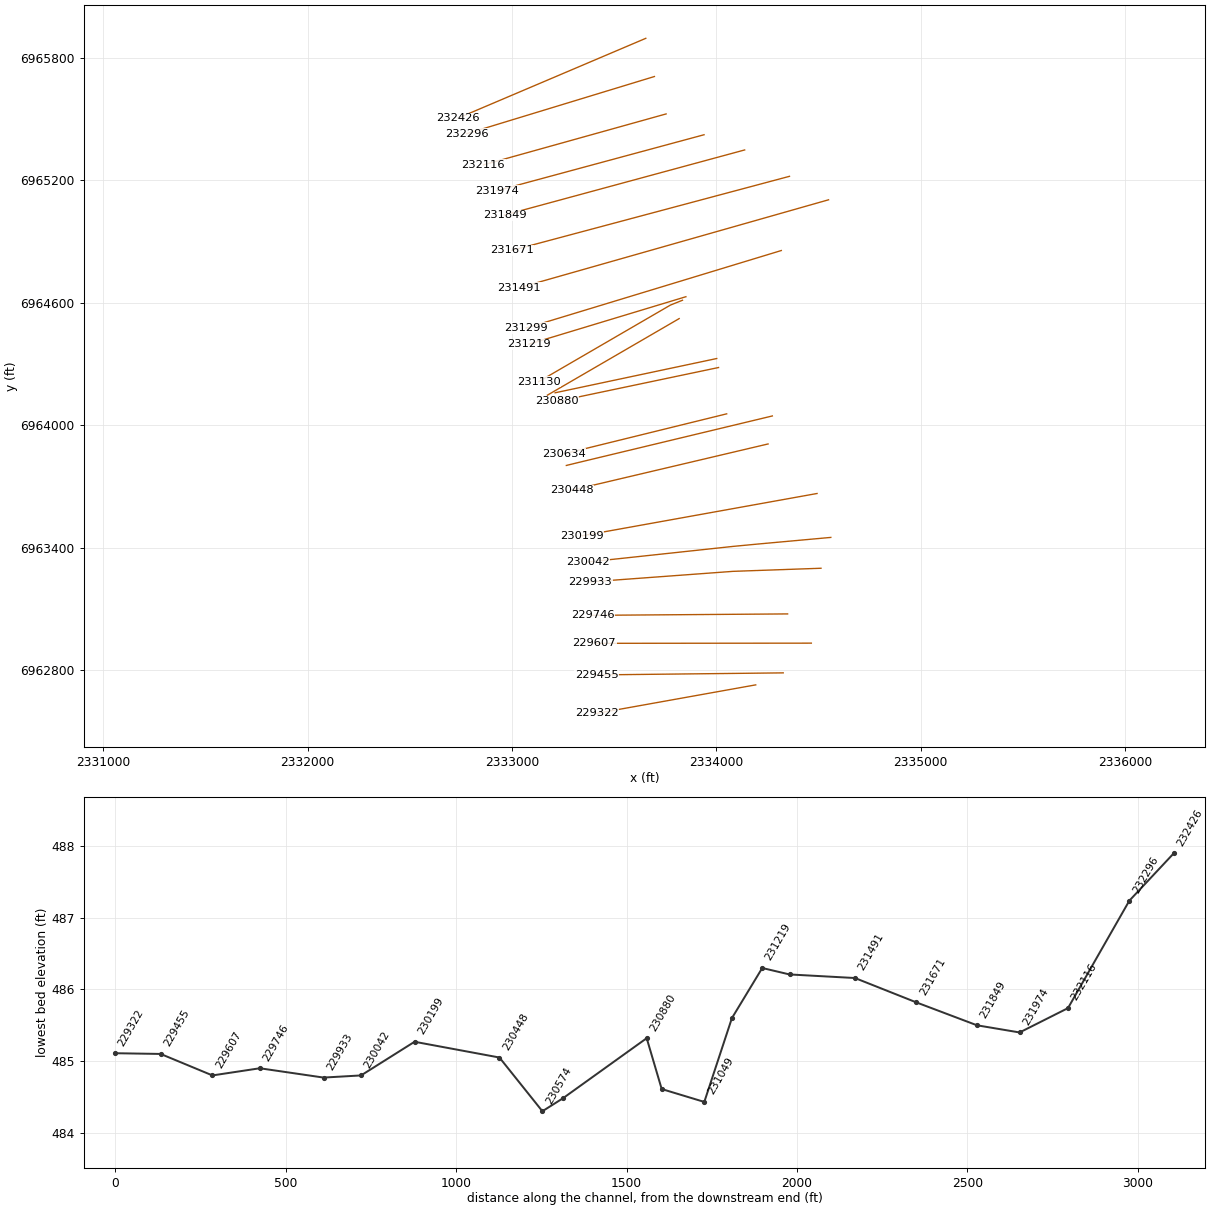
HEC-RAS study CDC_Consolidated_Model.prj: Upper Trinity CDC Consolidated Model

--- CDC_Consolidated_Model.g03 (geometry) --- (continued)

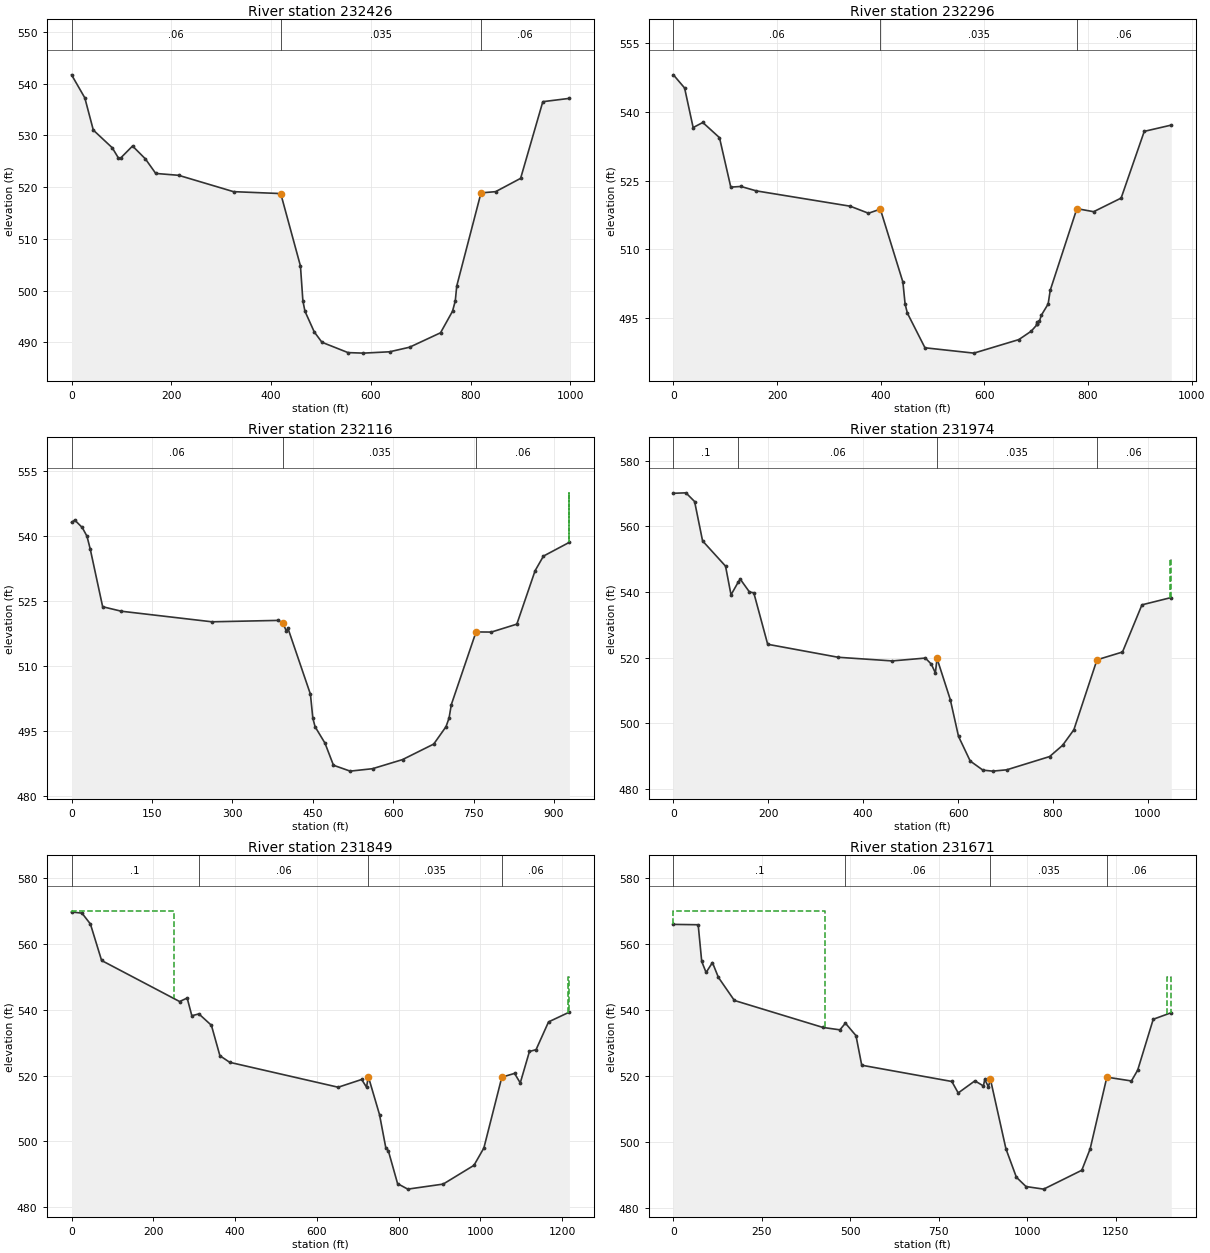
Type RM Length L Ch R = 1 ,232426  ,130,130,83
BEGIN DESCRIPTION:
This cross section corresponds to cross section 232304.4 of the non-georeferenced CDC model which was the source of this model.
Riverside Park in LOB.
Effective flow limit in ROB set at West Fork Levee Loop.
END DESCRIPTION:
XS GIS Cut Line= 2
  2333654.553286 6965896.1174425 2332736.1471003 6965505.3772638
#Sta/Elev= 30
       0  541.69   26.56  537.24   43.61  531.01   81.58  527.59   94.04   525.6
   98.11  525.58  122.27  527.93  147.94  525.45  168.74  522.63  214.59  522.27
  324.65  519.11  419.31  518.74  458.86  504.74  463.74     498  467.87     496
  486.53     492  501.93     490  554.23     488  585.13   487.9   637.6  488.16
   677.5  489.04  739.66  491.83  763.72     496  769.25     498  772.19  500.88
   820.8  518.87  850.18  519.11  900.21  521.68  944.73   536.5  998.07  537.14
#Mann= 3 ,-1,0
       0     .06       0  419.31    .035       0   820.8     .06       0
Bank Sta=419.31,820.8
XS Rating Curve= 0 ,0
Exp/Cntr=0.3,0.1

Type RM Length L Ch R = 1 ,232296  ,180,180,170
BEGIN DESCRIPTION:
This cross section corresponds to cross section 232174.5 of the non-georeferenced CDC model which was the source of this model.
Riverside Park in LOB.
Effective flow limit in ROB set at West Fork Levee Loop.
END DESCRIPTION:
XS GIS Cut Line= 2
 2333696.8969457 6965709.0459746 2332778.0291205 6965428.8047398
#Sta/Elev= 30
       0  548.14   21.61  545.26   38.11   536.6   56.74  537.71   88.93  534.39
  110.75  523.57  130.34  523.71  160.16  522.74  341.22  519.39  376.42  517.85
  399.29  518.75   442.8   502.8  447.06     498  451.43     496  485.41  488.41
  579.83  487.24  666.47   490.2  690.41  492.04  701.91  493.51  701.96     494
  702.08  493.63  706.19   494.2  709.96  495.53  723.08     498  727.13     501
  778.53  518.86  810.86  518.19  863.92  521.17  908.54  535.77  960.65  537.14
#Mann= 3 ,-1,0
       0     .06       0  399.29    .035       0  778.53     .06       0
Bank Sta=399.29,778.53
XS Rating Curve= 0 ,0
Exp/Cntr=0.3,0.1

Type RM Length L Ch R = 1 ,232116  ,142,142,140
BEGIN DESCRIPTION:
This cross section corresponds to cross section 231994.9 of the non-georeferenced CDC model which was the source of this model.
Riverside Park in LOB.
Effective flow limit in ROB set at West Fork Levee Loop.
END DESCRIPTION:
XS GIS Cut Line= 2
 2333754.0962968 6965525.7665363 2332859.6621779 6965275.9831375
#Sta/Elev= 30
       0  543.18    5.92  543.71   19.86     542   28.69     540   34.91  536.98
      58   523.7   92.96  522.66  261.85  520.22  384.63  520.54  394.12     520
  400.81     518  403.59  518.74  445.58  503.49     450     498  454.19     496
  472.72   492.2   488.5   487.1  519.68  485.74  561.35   486.3  617.31   488.4
  675.55  491.99  698.43     496  704.15     498  708.34  501.09  754.45  517.88
  783.01  517.85  830.56  519.68   864.6  532.01  880.19  535.39  928.66  538.58
#Mann= 3 ,-1,0
       0     .06       0  394.12    .035       0  754.45     .06       0
#XS Ineff= 2 , 0
       0                  927.96       0     550
Permanent Ineff=
       F       T
Bank Sta=394.12,754.45
XS Rating Curve= 0 ,0
Exp/Cntr=0.3,0.1

Type RM Length L Ch R = 1 ,231974  ,125,125,125
BEGIN DESCRIPTION:
This cross section corresponds to cross section 231852.5 of the non-georeferenced CDC model which was the source of this model.
Riverside Park in LOB.
Effective flow limit in ROB set at West Fork Levee Loop.
END DESCRIPTION:
XS GIS Cut Line= 2
 2333939.7886798 6965423.7894498 2332926.9656134 6965149.9138102
#Sta/Elev= 30
       0  570.08   26.41  570.22   44.68  567.57   61.49  555.57  109.87  547.88
  121.43  539.13  137.13  543.14  140.96   543.9  160.27     540  169.43  539.75
  198.71  524.06  347.38   520.1  461.18  518.99     531  519.86  543.56     518
  552.08  515.33  555.59  519.73  583.49  507.22  600.82     496  625.49  488.48
  652.31   485.7  672.91   485.4  702.45   485.8  792.82  489.84  820.14  493.26
  843.92     498  892.67  519.33  946.41   521.7  987.41  536.08  1049.2  538.31
#Mann= 4 ,-1,0
       0      .1       0  137.13     .06       0  555.59    .035       0
  892.67     .06       0
#XS Ineff= 2 , 0
       0                 1047.31       0     550
Permanent Ineff=
       F       T
Bank Sta=555.59,892.67
XS Rating Curve= 0 ,0
Exp/Cntr=0.3,0.1

Type RM Length L Ch R = 1 ,231849  ,178,178,176
BEGIN DESCRIPTION:
This cross section corresponds to cross section 231727.8 of the non-georeferenced CDC model which was the source of this model.
Ineffective flow in LOB.
Effective flow limit in ROB set at West Fork Levee Loop.
END DESCRIPTION:
XS GIS Cut Line= 2
 2334138.4505271 6965349.2436801 2332963.0318315 6965030.1437036
#Sta/Elev= 30
       0  569.66   25.54  569.29   46.12     566   73.52  554.92  264.39  542.46
  282.81  543.52  294.22  538.15  311.56   538.7  342.13  535.24  362.92     526
  387.01     524  652.26  516.44  709.69  518.79  721.57  516.46  726.03  519.66
  753.36  508.13  768.82     498  774.84   497.2  797.57  487.17  822.47   485.5
  909.12  487.03  984.47  492.73 1008.68     498 1052.59  519.48 1083.66  520.64
 1097.68  517.75 1120.17   527.3 1136.32  527.84 1166.83  536.27 1217.96  539.26
#Mann= 4 ,-1,0
       0      .1       0  311.56     .06       0  726.03    .035       0
 1052.59     .06       0
#XS Ineff= 2 , 0
       0  249.71     570 1214.01       0     550
Permanent Ineff=
       F       T
Bank Sta=726.03,1052.59
XS Rating Curve= 0 ,0
Exp/Cntr=0.3,0.1

Type RM Length L Ch R = 1 ,231671  ,180,180,188
BEGIN DESCRIPTION:
This cross section corresponds to cross section 231549.6 of the non-georeferenced CDC model which was the source of this model.
Ineffective flow in LOB.
Effective flow limit in ROB set at West Fork Levee Loop.
END DESCRIPTION:
XS GIS Cut Line= 2
 2334358.0441803 6965220.0708286 2332998.6697269 6964856.7544476
#Sta/Elev= 30
       0   565.9   70.03  565.79   80.06  554.68   92.42  551.35  110.38  554.35
  127.12  549.88  172.31  542.89  422.52  534.73  470.55     534  486.15  536.02
     516  532.25  532.28   523.3  786.99  518.38  804.91  514.91  852.11  518.57
  876.16  517.03  879.92  518.99  890.21   516.8  896.14  518.99  939.86     498
  969.36  489.42  996.58   486.6 1046.46  485.82 1154.24  491.53 1177.84     498
 1225.07  519.69 1294.55  518.54 1312.14  521.81 1356.12   537.2 1407.09  539.19
#Mann= 4 ,-1,0
       0      .1       0  486.15     .06       0  896.14    .035       0
 1225.07     .06       0
#XS Ineff= 2 , 0
       0  429.56     570  1395.8       0     550
Permanent Ineff=
       F       T
Bank Sta=896.14,1225.07
XS Rating Curve= 0 ,0
Exp/Cntr=0.3,0.1

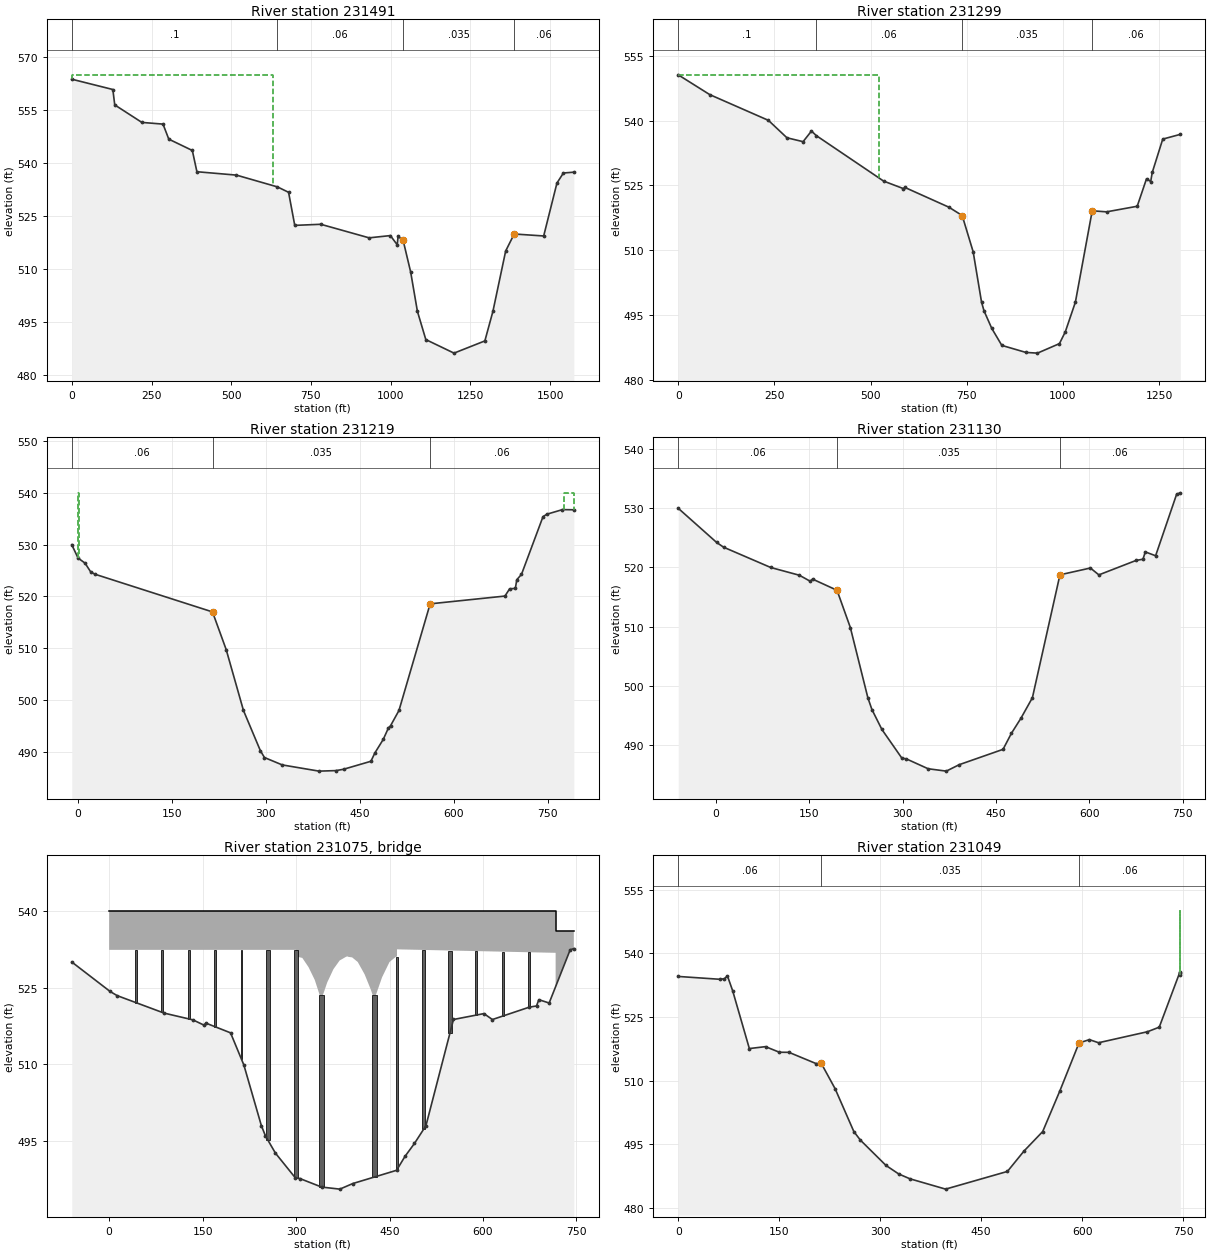
Type RM Length L Ch R = 1 ,231491  ,192,192,202
BEGIN DESCRIPTION:
This cross section corresponds to cross section 231370 of the non-georeferenced CDC model which was the source of this model.
Upstream of Sump 29 outfall.
Ineffective flow in LOB.
Effective flow limit in ROB set at West Fork Levee Loop.
END DESCRIPTION:
XS GIS Cut Line= 2
 2334549.0972078 6965105.0326241 2333034.9116039 6964674.2008501
#Sta/Elev= 30
       0  563.76   128.8  560.84  134.75  556.48   219.8  551.52  286.08  551.04
   304.2  546.78     378  543.57  392.38  537.55  516.32  536.59  644.98  533.25
   679.8  531.72  699.19  522.35  780.88  522.66   932.3  518.82  998.99  519.46
  1020.5  516.85 1023.19   519.2 1038.94  518.12 1062.61  509.15 1083.76     498
 1110.14     490 1198.56  486.16 1295.26  489.62 1320.55     498 1360.53   515.1
 1387.24  519.91 1479.71  519.35  1521.3  534.34 1541.55  537.19 1574.28  537.42
#Mann= 4 ,-1,0
       0      .1       0  644.98     .06       0 1038.94    .035       0
 1387.24     .06       0
#XS Ineff= 1 ,-1
       0  631.83     565
Permanent Ineff=
       F
Bank Sta=1038.94,1387.24
XS Rating Curve= 0 ,0
Exp/Cntr=0.3,0.1

Type RM Length L Ch R = 1 ,231299  ,80,80,79
BEGIN DESCRIPTION:
This cross section corresponds to cross section 231177.9 of the non-georeferenced CDC model which was the source of this model.
Downstream of Sump 29 outfall.
Ineffective flow in LOB.
Effective flow limit in ROB set at West Fork Levee Loop.
END DESCRIPTION:
XS GIS Cut Line= 2
 2334317.8526344 6964856.4275015 2333069.2106022 6964476.6217361
#Sta/Elev= 30
       0  550.58   81.97     546  234.41  540.05  282.54  536.02  324.54  535.12
  346.34  537.58  358.78  536.53  533.88     526  584.84  524.28  589.55  524.52
  703.71  519.96  738.14  518.03  766.65  509.65  788.45     498  794.83     496
  814.97  491.94  841.15     488  903.81  486.37  933.86  486.21  990.97  488.41
 1006.22  491.15 1032.39     498 1076.12  519.13 1113.54  518.89 1193.09  520.18
 1217.34  526.55 1228.15   525.9 1232.17  527.99 1259.45  535.71 1305.13  536.81
#Mann= 4 ,-1,0
       0      .1       0  358.78     .06       0  738.14    .035       0
 1076.12     .06       0
#XS Ineff= 1 ,-1
       0  521.17 550.579
Permanent Ineff=
       F
Bank Sta=738.14,1076.12
XS Rating Curve= 0 ,0
Exp/Cntr=0.3,0.1

Type RM Length L Ch R = 1 ,231219  ,89,89,462
BEGIN DESCRIPTION:
This cross section corresponds to cross section 231097.7 of the non-georeferenced CDC model which was the source of this model.
Ineffective flow in LOB.
Effective flow limit in ROB set at West Fork Levee Loop.
END DESCRIPTION:
XS GIS Cut Line= 3
2333850.933825926964630.12029274 2333841.3628859 6964627.2225165
 2333083.6688247 6964397.8168525
#Sta/Elev= 30
     -10     530       0  527.42    11.2  526.43    20.3  524.73   27.17  524.29
  214.71  517.02  236.56  509.75  264.15     498  291.23  490.22  297.71  488.92
  326.03   487.5  384.69   486.3   411.8   486.4     424  486.66  467.62   488.2
  474.07  489.83  487.28  492.41  495.59  494.63  498.95  495.05  512.42     498
  562.22  518.58  681.65  520.08  689.12  521.48  698.25  521.56  700.58  523.23
  708.07  524.27  742.42   535.4  748.49  535.87  773.47  536.76  791.66  536.73
#Mann= 3 ,-1,0
     -10     .06       0  214.71    .035       0  562.22     .06       0
#XS Ineff= 2 , 0
       0     .84     540  775.35       0     540
Permanent Ineff=
       F       T
Bank Sta=214.71,562.22
XS Rating Curve= 0 ,0
Exp/Cntr=0.5,0.3

Type RM Length L Ch R = 1 ,231130  ,81,81,80
BEGIN DESCRIPTION:
This cross section corresponds to cross section 231008.5 of the non-georeferenced CDC model which was the source of this model.
Upstream of Belknap Street.
Effective flow limit in ROB set at West Fork Levee Loop.
END DESCRIPTION:
XS GIS Cut Line= 4
     2333834.099      6964612.84 2333775.1222195 6964589.1290256
 2333157.0193358 6964229.5288361 2333130.4401888 6964214.0656073
#Sta/Elev= 30
     -60     530     1.5  524.24   12.73  523.43   88.38     520  134.38  518.69
  151.95  517.67  155.57  518.04  194.84  516.15  216.23  509.86  244.34     498
  250.89     496  266.87  492.64  298.89   487.8  306.08  487.67  341.11     486
  370.26   485.6  391.02  486.69  461.34  489.28  474.83     492  489.97  494.52
  508.45     498  552.66  518.76  601.53  519.91  615.11  518.75   674.6  521.18
  685.91   521.4  689.67  522.63  706.21  521.98  739.93  532.37  745.85  532.61
#Mann= 3 ,-1,0
     -60     .06       0  194.84    .035       0  552.66     .06       0
#XS Ineff= 2 , 0
       0       0                       0
Permanent Ineff=
       F       F
Bank Sta=194.84,552.66
XS Rating Curve= 0 ,0
Exp/Cntr=0.5,0.3

Type RM Length L Ch R = 3 ,231075  ,,,
BEGIN DESCRIPTION:
Belknap Street
Data from USACE 1949 survey, USACE 1975 survey, Fort Worth Floodway DPR.
Downstream cross-section represents fill area in LOB.
END DESCRIPTION:
Node Name=Belknap Street
Bridge Culvert--1,0,-1,-1, 0
Deck Dist Width WeirC Skew NumUp NumDn MinLoCord MaxHiCord MaxSubmerge Is_Ogee
19.8,52,2.6,0, 29, 29, , , 0.95, 0, 0,0,,
       0     300     300     310     320     330     338     343     350     360
     370     380     382     384     390     399     410     420     423     428
     438     450     460     462     462     462   716.6   716.6  745.85
     540     540     540     540     540     540     540     540     540     540
     540     540     540     540     540     540     540     540     540     540
     540     540     540     540     540     540     540     536     536
  532.37  532.37  531.07   530.8     529   526.5   523.5   523.5     526   528.6
   530.3     531   531.1     531   530.9     530   527.6   524.6   523.5   523.5
     527     530     531  531.07  531.07  532.47  531.79     450     450
       0     300     300     310     320     330     338     343     350     360
     370     380     382     384     390     399     410     420     423     428
     438     450     460     462     462     462   716.6   716.6  745.95
     540     540     540     540     540     540     540     540     540     540
     540     540     540     540     540     540     540     540     540     540
     540     540     540     540     540     540     540     536     536
  532.37  532.37  531.07   530.8     529   526.5   523.5   523.5     526   528.6
   530.3     531   531.1     531   530.9     530   527.6   524.6   523.5   523.5
     527     530     531  531.07  531.07  532.47  531.79     450     450
Pier Skew, UpSta & Num, DnSta & Num=  ,42.5, 2 ,42.5, 2 , 0 , 0 , 0 ,,
       3       3
     450     539
       3       3
     450     539
Pier Skew, UpSta & Num, DnSta & Num=  ,85, 2 ,85, 2 , 0 , 0 , 0 ,,
       3       3
     450     539
       3       3
     450     539
Pier Skew, UpSta & Num, DnSta & Num=  ,127.5, 2 ,127.5, 2 , 0 , 0 , 0 ,,
       3       3
     450     539
       3       3
     450     539
Pier Skew, UpSta & Num, DnSta & Num=  ,170, 2 ,170, 2 , 0 , 0 , 0 ,,
       3       3
     450     539
       3       3
     450     539
Pier Skew, UpSta & Num, DnSta & Num=  ,212.5, 2 ,212.5, 2 , 0 , 0 , 0 ,,
       3       3
     450     539
       3       3
     450     539
Pier Skew, UpSta & Num, DnSta & Num=  ,255, 4 ,255, 4 , 0 , 0 , 0 ,,
     6.2     6.2       3       3
     450     505     505     539
     6.2     6.2       3       3
     450     505     505     539
Pier Skew, UpSta & Num, DnSta & Num=  ,300, 4 ,300, 4 , 0 , 0 , 0 ,,
     6.2     6.2       3       3
     450     497     497     539
     6.2     6.2       3       3
     450     497     497     539
Pier Skew, UpSta & Num, DnSta & Num=  ,340.5, 2 ,340.5, 2 , 0 , 0 , 0 ,,
       8       5
     450   523.5
       8       5
     450   523.5
Pier Skew, UpSta & Num, DnSta & Num=  ,425.5, 2 ,425.5, 2 , 0 , 0 , 0 ,,
       8       5
     450   523.5
       8       5
     450   523.5
Pier Skew, UpSta & Num, DnSta & Num=  ,462, 2 ,462, 2 , 0 , 0 , 0 ,,
       3       3
     450     539
       3       3
     450     539
Pier Skew, UpSta & Num, DnSta & Num=  ,504.5, 4 ,504.5, 4 , 0 , 0 , 0 ,,
     6.2     6.2       3       3
     450     512     512     539
     6.2     6.2       3       3
     450     512     512     539
Pier Skew, UpSta & Num, DnSta & Num=  ,547, 4 ,547, 4 , 0 , 0 , 0 ,,
     6.2     6.2       3       3
     450     518     518     539
     6.2     6.2       3       3
     450     518     518     539
Pier Skew, UpSta & Num, DnSta & Num=  ,589.5, 2 ,589.5, 2 , 0 , 0 , 0 ,,
       3       3
     450     539
       3       3
     450     539
Pier Skew, UpSta & Num, DnSta & Num=  ,632, 2 ,632, 2 , 0 , 0 , 0 ,,
       3       3
     450     539
       3       3
     450     539
Pier Skew, UpSta & Num, DnSta & Num=  ,674.5, 2 ,674.5, 2 , 0 , 0 , 0 ,,
       3       3
     450     539
       3       3
     450     539
BR Coef=-1 , 0 , 0 ,, 0 ,,,0.8,-1,,0,
WSPro=,,,, 1 ,,,, 0 ,,,, 0 ,,,,-1 ,-1 ,-1 , 0 , 0 , 0 , 0 , 0
BC Design=,, 0 ,, 0 ,,,,,,
BC Use User HTab Curves=0
BC User HTab FreeFlow(D)= 0

Type RM Length L Ch R = 1 ,231049  ,125,125,26
BEGIN DESCRIPTION:
This cross section corresponds to cross section 230927.7 of the non-georeferenced CDC model which was the source of this model.
Downstream of Belknap Street.
Effective flow limit in ROB set at West Fork Levee Loop.
END DESCRIPTION:
XS GIS Cut Line= 3
  2333818.013987 6964522.9608267 2333199.9111032 6964163.3606372
 2333173.2886959 6964147.8722404
#Sta/Elev= 30
       0  534.54   61.87  533.87   68.56     534   73.09  534.67   80.86  531.17
  105.65  517.55  129.65     518  150.27  516.68  164.47  516.66  204.94     514
   212.5  514.06  233.08  508.08  260.87     498  270.48     496  308.73     490
  327.59     488   344.3  486.86  397.22  484.43  489.06   488.6  513.62  493.39
  541.47     498  567.08  507.62  595.43  518.87  610.84  519.65  624.41  518.92
  697.04  521.51  714.61  522.59  744.95  535.43  745.23  535.54   745.9  534.95
#Mann= 3 ,-1,0
       0     .06       0   212.5    .035       0  595.43     .06       0
#XS Ineff= 2 , 0
       0                  745.23       0     550
Permanent Ineff=
       F       T
Bank Sta=212.5,595.43
XS Rating Curve= 0 ,0
Exp/Cntr=0.5,0.3

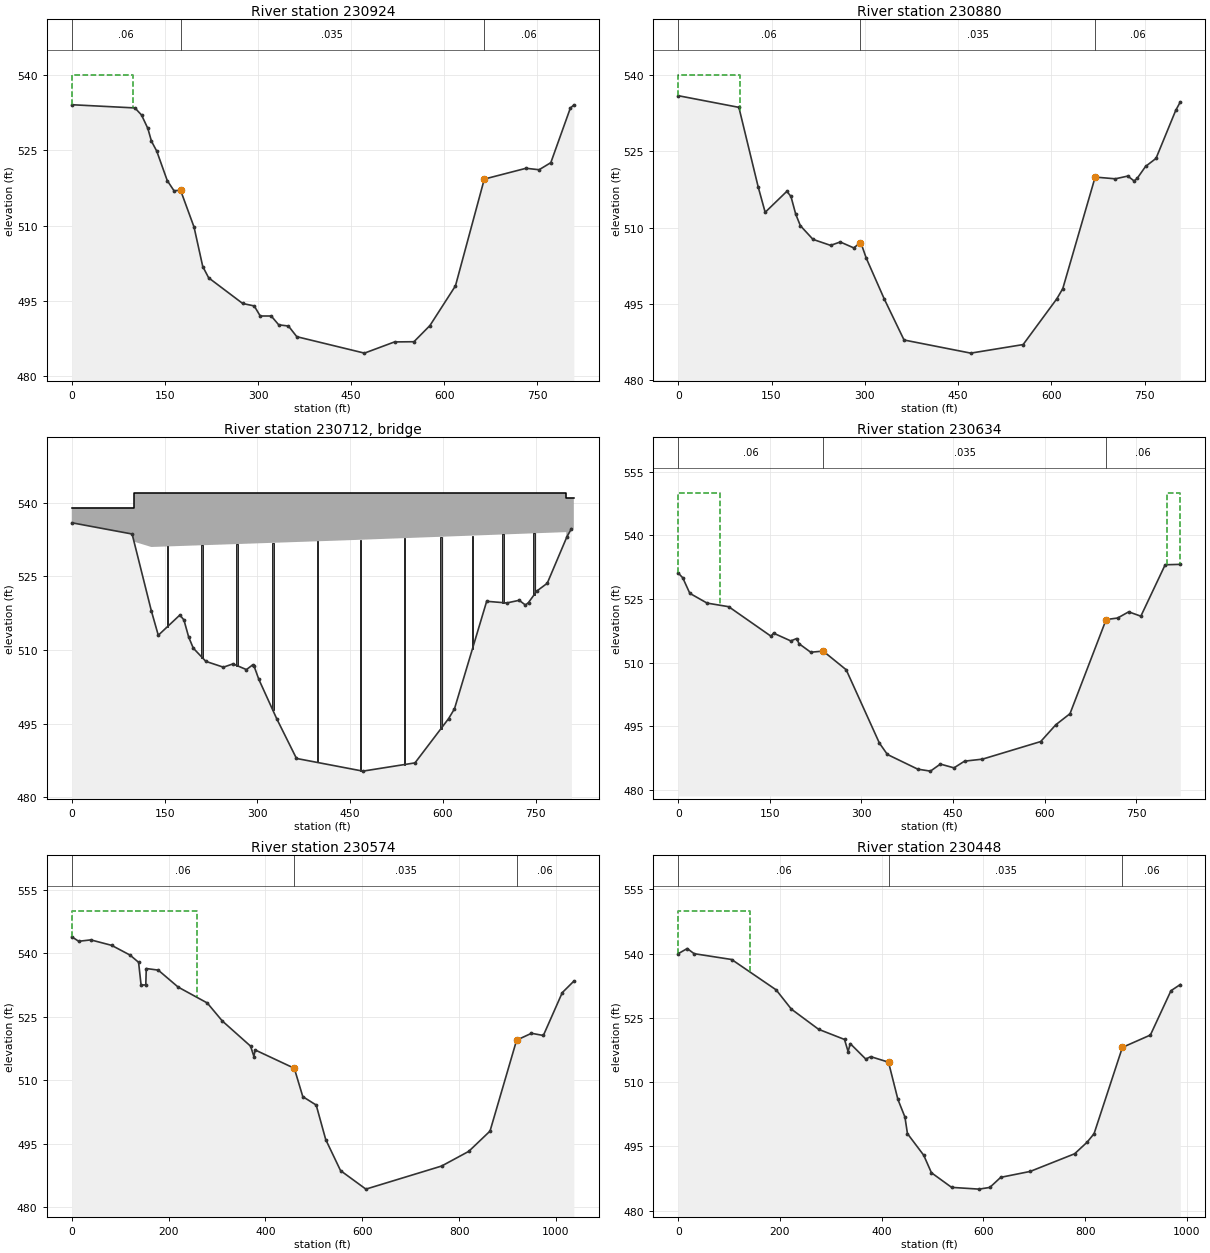
Type RM Length L Ch R = 1 ,230924  ,44,44,43
BEGIN DESCRIPTION:
This cross section corresponds to cross section 230802.3 of the non-georeferenced CDC model which was the source of this model.
Ineffective flow in LOB.
Effective flow limit in ROB set at West Fork Levee Loop.
END DESCRIPTION:
XS GIS Cut Line= 2
 2334001.8821097 6964327.3501299 2333210.8084401  6964159.465805
#Sta/Elev= 30
       0  534.05  101.73  533.41  112.38     532  122.52  529.33  128.36  526.79
  136.92   524.8  153.75  518.96  164.71  516.92  175.17  517.05  196.97  509.69
  210.96  501.85  220.54  499.59  275.31  494.49  293.91     494  303.54     492
  321.26     492   333.3  490.25  349.03     490  362.46  487.88  471.41  484.61
  519.86  486.84  551.16  486.88  576.89   490.1  618.01     498  664.47  519.25
  731.69   521.4  752.74  521.11   771.6  522.52  803.09  533.39  808.69     534
#Mann= 3 ,-1,0
       0     .06       0  175.17    .035       0  664.47     .06       0
#XS Ineff= 1 ,-1
       0    98.5     540
Permanent Ineff=
       F
Bank Sta=175.17,664.47
XS Rating Curve= 0 ,0
Exp/Cntr=0.5,0.3

Type RM Length L Ch R = 1 ,230880  ,246,246,266
BEGIN DESCRIPTION:
This cross section corresponds to cross section 230758.2 of the non-georeferenced CDC model which was the source of this model.
Upstream of SH 121.
Ineffective flow in LOB.
Effective flow limit in ROB set at West Fork Levee Loop.
END DESCRIPTION:
XS GIS Cut Line= 2
 2334010.6965592 6964283.2567515 2333220.5357976 6964117.1720558
#Sta/Elev= 30
       0   535.9   97.52  533.61  128.52     518  139.81  512.99  174.65  517.11
  181.25  516.11  188.96  512.61  196.41  510.36  216.73  507.67  245.02  506.49
  260.54  507.16  282.25     506  292.36  506.96  294.49  506.74  302.32     504
  331.18     496  363.14   487.9  470.44  485.32  554.64     487  608.87     496
  618.43     498  670.49  519.91  702.94  519.57  723.02  520.11  733.18  519.14
  738.09  519.66  751.54     522  768.35  523.58  800.07  533.02  807.43  534.68
#Mann= 3 ,-1,0
       0     .06       0  292.36    .035       0  670.49     .06       0
#XS Ineff= 1 ,-1
       0   98.78     540
Permanent Ineff=
       F
Bank Sta=292.36,670.49
XS Rating Curve= 0 ,0
Exp/Cntr=0.5,0.3

Type RM Length L Ch R = 3 ,230712  ,,,
BEGIN DESCRIPTION:
SH 121
North (west bound) bridge represented.  Bridge length 698.5 feet.  Double bridges - total bridge width set at 156 feet.
Data from USACE 1975 survey.
Note:  Internal bridge cross-sections modified to represent geometry under bridge.
END DESCRIPTION:
Node Name=SH 121
Bridge Culvert--1,0,-1,-1, 0
Deck Dist Width WeirC Skew NumUp NumDn MinLoCord MaxHiCord MaxSubmerge Is_Ogee
15.4,156,2.6,0, 8, 8, , , 0.95, 0, 0,0,,
       0  100.63  100.63  435.85  799.13  799.13  807.43  811.35
     539     539     542     542     542     541     541     541
     470     470  530.85   532.3     534     470     470     470
       0  100.63  100.63  435.85  799.13  799.13  807.43  821.92
     539     539     542     542     542     541     541     541
     470     470  530.85   532.3     534     470     470     470
Pier Skew, UpSta & Num, DnSta & Num=  ,154.78, 2 ,146, 2 , 0 , 0 , 0 ,,
     2.5     2.5
     470     537
     2.5     2.5
     470     537
Pier Skew, UpSta & Num, DnSta & Num=  ,210.78, 2 ,202, 2 , 0 , 0 , 0 ,,
     2.5     2.5
     470     537
     2.5     2.5
     470     537
Pier Skew, UpSta & Num, DnSta & Num=  ,266.78, 2 ,258, 2 , 0 , 0 , 0 ,,
     2.5     2.5
     470     537
     2.5     2.5
     470     537
Pier Skew, UpSta & Num, DnSta & Num=  ,324.78, 2 ,316, 2 , 0 , 0 , 0 ,,
     2.5     2.5
     470     537
     2.5     2.5
     470     537
Pier Skew, UpSta & Num, DnSta & Num=  ,396.78, 2 ,388, 2 , 0 , 0 , 0 ,,
     2.5     2.5
     470     537
     2.5     2.5
     470     537
Pier Skew, UpSta & Num, DnSta & Num=  ,466.78, 2 ,458, 2 , 0 , 0 , 0 ,,
     2.5     2.5
     470     537
     2.5     2.5
     470     537
Pier Skew, UpSta & Num, DnSta & Num=  ,537.78, 2 ,529, 2 , 0 , 0 , 0 ,,
     2.5     2.5
     470     537
     2.5     2.5
     470     537
Pier Skew, UpSta & Num, DnSta & Num=  ,596.78, 2 ,588, 2 , 0 , 0 , 0 ,,
     2.5     2.5
     470     537
     2.5     2.5
     470     537
Pier Skew, UpSta & Num, DnSta & Num=  ,647.28, 2 ,638.5, 2 , 0 , 0 , 0 ,,
     2.5     2.5
     470     537
     2.5     2.5
     470     537
Pier Skew, UpSta & Num, DnSta & Num=  ,696.78, 2 ,688, 2 , 0 , 0 , 0 ,,
     2.5     2.5
     470     537
     2.5     2.5
     470     537
Pier Skew, UpSta & Num, DnSta & Num=  ,747.28, 2 ,738.5, 2 , 0 , 0 , 0 ,,
     2.5     2.5
     470     537
     2.5     2.5
     470     537
BR Coef=-1 , 0 , 0 ,, 0 ,,,0.8,-1,,0,
WSPro=,,,, 1 ,,,, 0 ,,,, 0 ,,,,-1 ,-1 ,-1 , 0 , 0 , 0 , 0 , 0
BR U #Sta/Elev= 202
       0  536.32   95.94  535.62   98.55  535.56  100.63  536.32  105.36  534.01
  146.43  512.57  169.71  515.56  173.29  516.04  183.14  517.15  183.54  517.19
  183.95  517.13  192.17   515.6  228.08  512.53   246.8  510.94  247.54  510.88
  250.64   510.6  251.75  510.58  252.18  510.56  253.25  510.53  253.72  510.52
   268.3  510.08     298  502.68  300.86  501.94  325.45  496.31  336.49  493.82
  340.87  492.83  362.05  488.38  393.54  487.27  393.92  487.23  394.31  487.25
  394.69  487.26  395.25  487.21  395.65   487.2  396.08  487.19  396.53  487.17
  396.96  487.15  397.42   487.1   397.9  487.12   398.4  487.07   398.9  487.05
  399.39  487.07  399.55  487.03  400.09  487.05  400.64  487.03  401.21  487.01
  401.79  487.03  402.36  487.05  402.98  487.06  403.61  487.04  404.24  486.98
  404.91  486.92  405.61  486.98  405.82  486.97  406.55  486.99  407.31  486.97
  408.04  486.99  408.84  486.92  409.66  486.85  410.52  486.78   411.4  486.75
  412.28  486.77  413.23  486.74  414.54  486.65  415.57  486.61  416.65  486.63
  417.71   486.7  418.88  486.67   419.7  486.64   421.3  486.48  422.18  486.68
  423.99  486.69  425.42  486.35  426.94   486.3  428.94  486.24  430.63  486.19
  432.38  486.13  434.25  486.07  438.16  486.09  440.31  486.03  442.62  485.96
  444.91  485.89   447.5  485.73  451.13  485.62  454.12  485.53  456.29  485.46
  460.53  485.33  464.14  485.12  468.01     485  468.02     485   468.8  485.03
  469.57  485.06  469.75  485.08  470.13  485.09  471.34  485.15  472.01  485.18
  472.32  485.17  473.69   485.3  474.26  485.32   474.9  485.37  475.98  485.41
  476.55  485.43  477.27  485.45   478.2  485.49  479.07  485.51  479.57  485.53
  480.74  485.52  481.53   485.5  481.87  485.55   482.2  485.56  483.38  485.59
  484.02  485.61  484.28  485.62  485.56  485.59  487.28  485.62  487.73  485.66
  487.91  485.66  488.26  485.67  489.53  485.69  489.69   485.7  491.67  485.73
  491.84  485.74  491.93  485.74  493.75  485.87  493.82  485.87  493.85  485.87
  495.29   485.9   495.7  485.91  495.71  485.91  497.68  485.94  497.76  485.94
   499.4  485.96  499.51  485.96  501.15  485.99  502.97  486.02  503.18  486.02
  504.45  486.04  506.15  486.07   506.6  486.08  508.05   486.1  509.41  486.12
  510.94  486.14   512.2  486.16  513.41  486.18  514.76   486.2  520.56  486.39
  521.59  486.41  522.96  486.44  524.06  486.46  525.12  486.48  526.29  486.51
  527.27  486.53  528.22  486.55  529.12  486.57  531.28  486.62  532.27  486.64
  532.94   486.7  534.35  486.73  535.22  486.75  536.53  486.78  537.23  486.79
  537.89  486.77  540.72  486.84  541.93  486.87  543.72  486.91   544.2  486.92
  544.73  486.96  546.33     487  546.65  487.01  548.38  487.05  548.76  487.06
  550.55   487.1  550.81  487.11  553.04  487.16  553.22  487.17  553.42  487.16
  555.38  487.31  557.54  487.27  557.57  487.28  557.61  487.27  558.51   487.3
  561.55  488.12  567.26  489.77  571.73  490.98   575.9  492.11  579.72  493.15
  583.83  494.26  587.09  495.14  590.13  495.97  680.66  519.97  687.56  519.92
  711.06  519.72  718.29  519.73  734.21  519.65  740.67  519.63   741.5  519.88
  747.36  521.25   767.9  523.76  770.46  524.11  799.93  538.66  804.06  540.49
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BR U #Mann= 3
       0     .06   268.3    .035  680.66     .06
BR U Banks=268.3,680.66
BR D #Sta/Elev= 202
       0  536.32   95.94  535.62   98.55  535.56  100.63  536.32  105.36  534.01
  146.43  512.57  169.71  515.56  173.29  516.04  183.14  517.15  183.54  517.19
  183.95  517.13  192.17   515.6  228.08  512.53   246.8  510.94  247.54  510.88
  250.64   510.6  251.75  510.58  252.18  510.56  253.25  510.53  253.72  510.52
   268.3  510.08     298  502.68  300.86  501.94  325.45  496.31  336.49  493.82
  340.87  492.83  362.05  488.38  393.54  487.27  393.92  487.23  394.31  487.25
  394.69  487.26  395.25  487.21  395.65   487.2  396.08  487.19  396.53  487.17
  396.96  487.15  397.42   487.1   397.9  487.12   398.4  487.07   398.9  487.05
  399.39  487.07  399.55  487.03  400.09  487.05  400.64  487.03  401.21  487.01
  401.79  487.03  402.36  487.05  402.98  487.06  403.61  487.04  404.24  486.98
  404.91  486.92  405.61  486.98  405.82  486.97  406.55  486.99  407.31  486.97
  408.04  486.99  408.84  486.92  409.66  486.85  410.52  486.78   411.4  486.75
  412.28  486.77  413.23  486.74  414.54  486.65  415.57  486.61  416.65  486.63
  417.71   486.7  418.88  486.67   419.7  486.64   421.3  486.48  422.18  486.68
  423.99  486.69  425.42  486.35  426.94   486.3  428.94  486.24  430.63  486.19
  432.38  486.13  434.25  486.07  438.16  486.09  440.31  486.03  442.62  485.96
  444.91  485.89   447.5  485.73  451.13  485.62  454.12  485.53  456.29  485.46
  460.53  485.33  464.14  485.12  468.01     485  468.02     485   468.8  485.03
  469.57  485.06  469.75  485.08  470.13  485.09  471.34  485.15  472.01  485.18
  472.32  485.17  473.69   485.3  474.26  485.32   474.9  485.37  475.98  485.41
  476.55  485.43  477.27  485.45   478.2  485.49  479.07  485.51  479.57  485.53
  480.74  485.52  481.53   485.5  481.87  485.55   482.2  485.56  483.38  485.59
  484.02  485.61  484.28  485.62  485.56  485.59  487.28  485.62  487.73  485.66
  487.91  485.66  488.26  485.67  489.53  485.69  489.69   485.7  491.67  485.73
  491.84  485.74  491.93  485.74  493.75  485.87  493.82  485.87  493.85  485.87
  495.29   485.9   495.7  485.91  495.71  485.91  497.68  485.94  497.76  485.94
   499.4  485.96  499.51  485.96  501.15  485.99  502.97  486.02  503.18  486.02
  504.45  486.04  506.15  486.07   506.6  486.08  508.05   486.1  509.41  486.12
  510.94  486.14   512.2  486.16  513.41  486.18  514.76   486.2  520.56  486.39
  521.59  486.41  522.96  486.44  524.06  486.46  525.12  486.48  526.29  486.51
  527.27  486.53  528.22  486.55  529.12  486.57  531.28  486.62  532.27  486.64
  532.94   486.7  534.35  486.73  535.22  486.75  536.53  486.78  537.23  486.79
  537.89  486.77  540.72  486.84  541.93  486.87  543.72  486.91   544.2  486.92
  544.73  486.96  546.33     487  546.65  487.01  548.38  487.05  548.76  487.06
  550.55   487.1  550.81  487.11  553.04  487.16  553.22  487.17  553.42  487.16
  555.38  487.31  557.54  487.27  557.57  487.28  557.61  487.27  558.51   487.3
  561.55  488.12  567.26  489.77  571.73  490.98   575.9  492.11  579.72  493.15
  583.83  494.26  587.09  495.14  590.13  495.97  680.66  519.97  687.56  519.92
  711.06  519.72  718.29  519.73  734.21  519.65  740.67  519.63   741.5  519.88
  747.36  521.25   767.9  523.76  770.46  524.11  799.93  538.66  804.06  540.49
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BR D #Mann= 3
       0     .06   268.3    .035  680.66     .06
BR D Banks=268.3,680.66
BC Design=,, 0 ,, 0 ,,,,,,
BC Use User HTab Curves=0
BC User HTab FreeFlow(D)= 0

Type RM Length L Ch R = 1 ,230634  ,60,60,57
BEGIN DESCRIPTION:
This cross section corresponds to cross section 230512.4 of the non-georeferenced CDC model which was the source of this model.
Downstream of SH 121.
Ineffective flow in LOB.
Effective flow limit in ROB set at West Fork Levee Loop.
END DESCRIPTION:
XS GIS Cut Line= 2
 2334050.6056247 6964056.3118685 2333252.5234871 6963859.8154876
#Sta/Elev= 30
       0  531.12    7.38     530   18.95  526.34   47.19  524.04   82.64  523.19
  151.78  516.25  156.05  516.96  184.35  515.13  193.78   515.7  197.83  514.47
  216.88  512.47  237.24  512.74  274.99  508.34  329.28  491.09  342.42   488.4
  392.16  484.94  412.89  484.48  429.13  486.14   451.4  485.25  468.75  486.83
     498   487.3  593.36  491.44  618.13   495.4  641.33     498  700.52  520.17
  719.18  520.52   737.4  521.98  757.33  520.96  797.12  533.06  821.92  533.16
#Mann= 3 ,-1,0
       0     .06       0  237.24    .035       0  700.52     .06       0
#XS Ineff= 2 , 0
       0   68.31     550  800.62       0     550
Permanent Ineff=
       F       T
Bank Sta=237.24,700.52
XS Rating Curve= 0 ,0
Exp/Cntr=0.5,0.3

Type RM Length L Ch R = 1 ,230574  ,126,126,122
BEGIN DESCRIPTION:
This cross section corresponds to cross section 230452.6 of the non-georeferenced CDC model which was the source of this model.
Ineffective flow in LOB.
Effective flow limit in ROB set at West Fork Levee Loop.
END DESCRIPTION:
XS GIS Cut Line= 3
 2334273.9717321 6964045.9358044 2333305.3543102 6963813.1350612
 2333265.7452261 6963803.3957771
#Sta/Elev= 30
       0  543.88   14.29  542.81   39.34  543.14   82.37  541.85  120.39  539.55
  137.99  537.85  143.17   532.5  152.87   532.5  153.89  536.38  178.64     536
  219.68     532  279.83  528.25  310.92     524  369.34  518.05  376.18  515.61
  378.67  517.16   459.6  512.83  477.19  506.13  504.84  504.15  524.52     496
  555.15  488.67  607.49   484.3  763.86  489.75  819.87  493.21  863.84     498
  918.79  519.47  949.51  521.09  973.99  520.57 1013.09  530.69 1036.99   533.4
#Mann= 3 ,-1,0
       0     .06       0   459.6    .035       0  918.79     .06       0
#XS Ineff= 2 , 0
       0  258.28     550               0
Permanent Ineff=
       F       F
Bank Sta=459.6,918.79
XS Rating Curve= 0 ,0
Exp/Cntr=0.3,0.1

Type RM Length L Ch R = 1 ,230448  ,249,249,222
BEGIN DESCRIPTION:
This cross section corresponds to cross section 230326.5 of the non-georeferenced CDC model which was the source of this model.
Ineffective flow in LOB.
Effective flow limit in ROB set at West Fork Levee Loop.
END DESCRIPTION:
XS GIS Cut Line= 2
 2334253.1858982 6963908.7496638 2333292.6916981 6963682.1161702
#Sta/Elev= 30
       0     540    17.7   541.2   31.24     540  105.01  538.64  192.48  531.55
  222.34  527.06  275.92  522.35  326.83  519.98  333.89  517.14  338.11  519.01
  368.65   515.4  378.29  515.97  413.31  514.68  431.83  505.97   445.6  501.87
  450.54     498  482.57  492.95  497.67  488.87  537.36  485.46  591.37  485.05
  612.48  485.45  633.84   487.8  691.78  489.18  779.15   493.3  803.64     496
  817.38     498  873.01  518.13  928.05  521.01  968.52  531.36  986.87   532.8
#Mann= 3 ,-1,0
       0     .06       0  413.31    .035       0  873.01     .06       0
#XS Ineff= 2 , 0
       0  140.91     550               0
Permanent Ineff=
       F       F
Bank Sta=413.31,873.01
XS Rating Curve= 0 ,0
Exp/Cntr=0.3,0.1

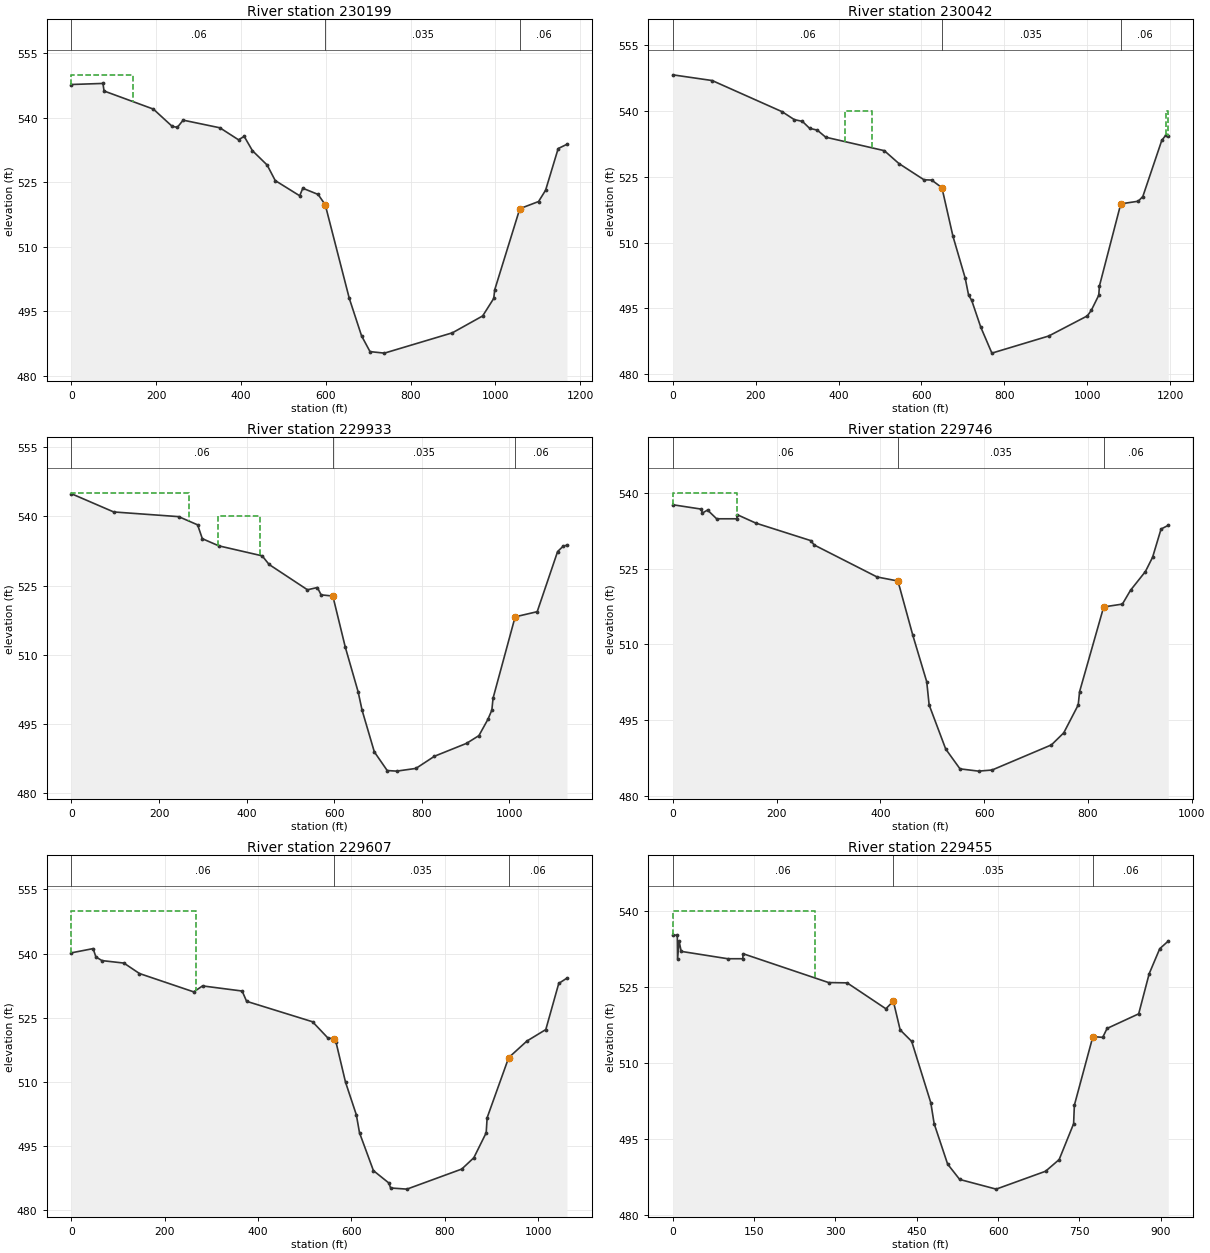
Type RM Length L Ch R = 1 ,230199  ,157,157,124
BEGIN DESCRIPTION:
This cross section corresponds to cross section 230077.8 of the non-georeferenced CDC model which was the source of this model.
Ineffective flow in LOB.
Effective flow limit in ROB set at West Fork Levee Loop.
END DESCRIPTION:
XS GIS Cut Line= 2
 2334492.8010419 6963666.0220508 2333342.3399182 6963458.6617797
#Sta/Elev= 30
       0  547.75   74.31     548   76.92  546.24  193.28  542.03  237.84     538
  249.86  537.79  263.54  539.46  350.21  537.68  394.15  534.89  407.55  535.68
  427.03  532.35  461.67  529.02  480.84   525.4   538.5  521.87  545.79  523.62
  581.93  522.18  598.73  519.78  655.49     498  684.44  489.29  704.39  485.62
  738.35  485.27  898.81     490  970.14  493.92   996.3     498  998.55     500
 1057.79  518.87    1102  520.53 1118.57  523.16 1148.27  532.85    1169  533.85
#Mann= 3 ,-1,0
       0     .06       0  598.73    .035       0 1057.79     .06       0
#XS Ineff= 2 , 0
       0  145.44     550               0
Permanent Ineff=
       F       F
Bank Sta=598.73,1057.79
XS Rating Curve= 0 ,0
Exp/Cntr=0.3,0.1

Type RM Length L Ch R = 1 ,230042  ,110,110,94
BEGIN DESCRIPTION:
This cross section corresponds to cross section 229920.9 of the non-georeferenced CDC model which was the source of this model.
Ineffective flow in LOB.
Effective flow limit in ROB set at West Fork Levee Loop.
END DESCRIPTION:
XS GIS Cut Line= 4
 2334560.2601721 6963450.8613555 2334206.3674077 6963418.6596343
 2334082.2150316 6963406.8449818 2333370.5528199 6963330.2436782
#Sta/Elev= 30
       0  548.21   94.99  546.91  264.01   539.8  293.29     538  312.79  537.61
  330.17  536.02  348.73  535.61  369.03     534  510.44  530.93  545.71     528
  606.17   524.3  624.82  524.23  649.53  522.49  676.12  511.44   705.7  501.89
  713.91     498  721.26  496.85  743.26  490.72  770.11   484.8  907.28   488.7
 1000.54  493.29 1010.25  494.59 1028.05     498 1029.57  500.08 1081.14  518.81
 1123.24  519.41 1134.34  520.48 1180.03  533.26  1189.9  534.47 1195.84  534.38
#Mann= 3 ,-1,0
       0     .06       0  649.53    .035       0 1081.14     .06       0
#XS Ineff= 2 ,-1
  415.71  480.13     540  1189.9 1195.84     540
Permanent Ineff=
       F       T
Bank Sta=649.53,1081.14
XS Rating Curve= 0 ,0
Exp/Cntr=0.3,0.1

Type RM Length L Ch R = 1 ,229933  ,187,187,158
BEGIN DESCRIPTION:
This cross section corresponds to cross section 229811.2 of the non-georeferenced CDC model which was the source of this model.
Ineffective flow in LOB.
Effective flow limit in ROB set at West Fork Levee Loop.
END DESCRIPTION:
XS GIS Cut Line= 3
 2334512.1804375 6963299.7526549 2334081.9806468 6963284.5720917
  2333382.811222 6963232.9480649
#Sta/Elev= 30
       0  544.93   96.48  540.98  244.88  539.96  288.13  538.18  298.87  535.18
  336.47  533.63  435.53  531.46  451.35  529.59  538.92   524.1  561.59  524.59
  570.12     523  596.91  522.74   625.4  511.64   654.7  501.96  663.64     498
  691.68  488.94  721.07   484.9  742.71  484.77  786.63  485.36  829.04     488
  902.15  490.79  930.46  492.47  951.01     496  960.02     498  962.74  500.58
 1013.21  518.23 1063.58  519.35 1110.18  532.39 1123.15  533.58 1131.54  533.76
#Mann= 3 ,-1,0
       0     .06       0  596.91    .035       0 1013.21     .06       0
#XS Ineff= 2 ,-1
       0   269.4 545.126  335.16  430.75     540
Permanent Ineff=
       F       F
Bank Sta=596.91,1013.21
XS Rating Curve= 0 ,0
Exp/Cntr=0.3,0.1

Type RM Length L Ch R = 1 ,229746  ,139,139,138
BEGIN DESCRIPTION:
This cross section corresponds to cross section 229624.6 of the non-georeferenced CDC model which was the source of this model.
Ineffective flow in LOB.
Effective flow limit in ROB set at West Fork Levee Loop.
END DESCRIPTION:
XS GIS Cut Line= 2
 2334348.8005007 6963076.0052833   2333393.84766  6963069.060208
#Sta/Elev= 30
       0  537.64   54.68  536.78   57.11     536   67.04  536.59   84.54  534.86
  123.55  534.86  124.05  535.68  160.21     534  265.91  530.54  272.61  529.67
  393.74  523.34  433.92  522.54  462.54  511.82  489.44  502.59  494.08     498
  526.02  489.27  553.53  485.35  589.25   484.9  615.33  485.12  729.81   490.1
  753.49  492.48  781.35     498  784.02  500.64  830.45  517.41  866.49  517.97
  882.18  520.71  910.87  524.42  924.72  527.25     941  532.83  954.98  533.57
#Mann= 3 ,-1,0
       0     .06       0  433.92    .035       0  830.45     .06       0
#XS Ineff= 2 , 0
       0   123.9     540               0
Permanent Ineff=
       F       F
Bank Sta=433.92,830.45
XS Rating Curve= 0 ,0
Exp/Cntr=0.3,0.1

Type RM Length L Ch R = 1 ,229607  ,152,152,157
BEGIN DESCRIPTION:
This cross section corresponds to cross section 229485.7 of the non-georeferenced CDC model which was the source of this model.
Ineffective flow in LOB.
Effective flow limit in ROB set at West Fork Levee Loop.
END DESCRIPTION:
XS GIS Cut Line= 2
 2334464.9417915 6962932.7723263 2333403.0820057 6962931.9334414
#Sta/Elev= 30
       0  540.16   46.44  541.15   52.44  539.19    65.4  538.34  112.39  537.76
   145.8  535.31   262.1  531.01  280.92  532.41  365.77  531.21  375.38   528.8
  516.67  524.01  549.02  520.27  562.39  519.96  567.02   519.2  587.33  509.85
  610.49  502.22  617.31     498  647.15  489.13  680.02  486.25     684  485.07
  718.92   484.8  836.38   489.5  862.28  492.15  888.77     498  890.81  501.53
     937  515.61   976.1   519.5 1016.49  522.18 1044.25  532.99 1061.86  534.24
#Mann= 3 ,-1,0
       0     .06       0  562.39    .035       0     937     .06       0
#XS Ineff= 2 , 0
       0     266     550               0
Permanent Ineff=
       F       F
Bank Sta=562.39,937
XS Rating Curve= 0 ,0
Exp/Cntr=0.3,0.1

Type RM Length L Ch R = 1 ,229455  ,133,133,244
BEGIN DESCRIPTION:
This cross section corresponds to cross section 229333.6 of the non-georeferenced CDC model which was the source of this model.
Ineffective flow in LOB.
Effective flow limit in ROB set at West Fork Levee Loop.
END DESCRIPTION:
XS GIS Cut Line= 2
  2334327.362849 6962787.1288878 2333413.5064245 6962777.1335694
#Sta/Elev= 30
       0  535.29    8.35  535.14    8.85  530.55    11.7     534   15.51     532
  101.35  530.55  129.14  530.55  129.64  531.54  287.38  525.85  321.55  525.79
  393.05  520.68  406.75  522.19  419.38  516.51  440.66  514.24  475.86  502.15
  482.08     498   506.9  490.04  529.13  487.01  596.44   485.1   687.6  488.63
  712.59  490.93  739.27     498  740.67  501.66  774.79  515.19  792.96  515.04
  800.99   516.8  859.28  519.68  878.66   527.6  898.13  532.53  913.91  534.04
#Mann= 3 ,-1,0
       0     .06       0  406.75    .035       0  774.79     .06       0
#XS Ineff= 1 ,-1
       0  262.59     540
Permanent Ineff=
       F
Bank Sta=406.75,774.79
XS Rating Curve= 0 ,0
Exp/Cntr=0.5,0.3

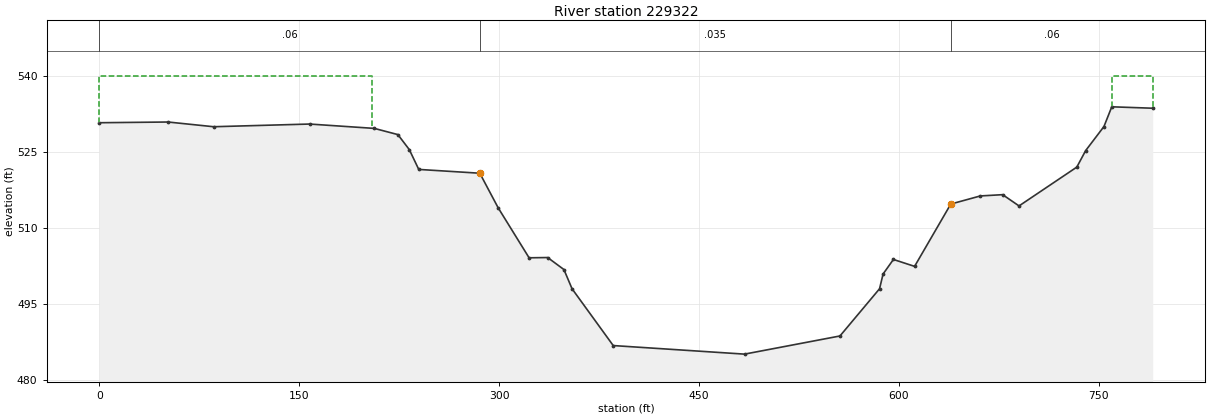
Type RM Length L Ch R = 1 ,229322  ,84,84,83
BEGIN DESCRIPTION:
This cross section corresponds to cross section 229200.2 of the non-georeferenced CDC model which was the source of this model.
Upstream of 4th Street.
Copy of cross-section 229200.2
Ineffective flow in LOB.
Effective flow limit in ROB set at West Fork Levee Loop.
END DESCRIPTION:
XS GIS Cut Line= 4
2334192.718496296962728.40987299  2334181.162228 6962726.3352045
 2333426.0563816 6962590.77290452333414.500113316962588.69823601
#Sta/Elev= 30
       0  530.75   51.59  530.89   85.78  529.96  157.85  530.49  206.42  529.63
  224.07  528.41  232.65  525.45  239.75  521.54  285.57  520.79  299.39  513.95
  322.56  504.11  336.51  504.16  348.71  501.79  354.81     498  385.71   486.8
  484.26  485.11   555.9  488.69   585.6     498  588.27  500.92  596.01  503.78
  611.91  502.42  639.07  514.71  661.27  516.31     678  516.56   690.3  514.34
  733.68     522   740.3  525.25  754.04     530  759.91  533.89  790.66  533.61
#Mann= 3 ,-1,0
       0     .06       0  285.57    .035       0  639.07     .06       0
#XS Ineff= 2 , 0
       0  204.98     540  759.91       0     540
Permanent Ineff=
       F       T
Bank Sta=285.57,639.07
XS Rating Curve= 0 ,0
Exp/Cntr=0.5,0.3