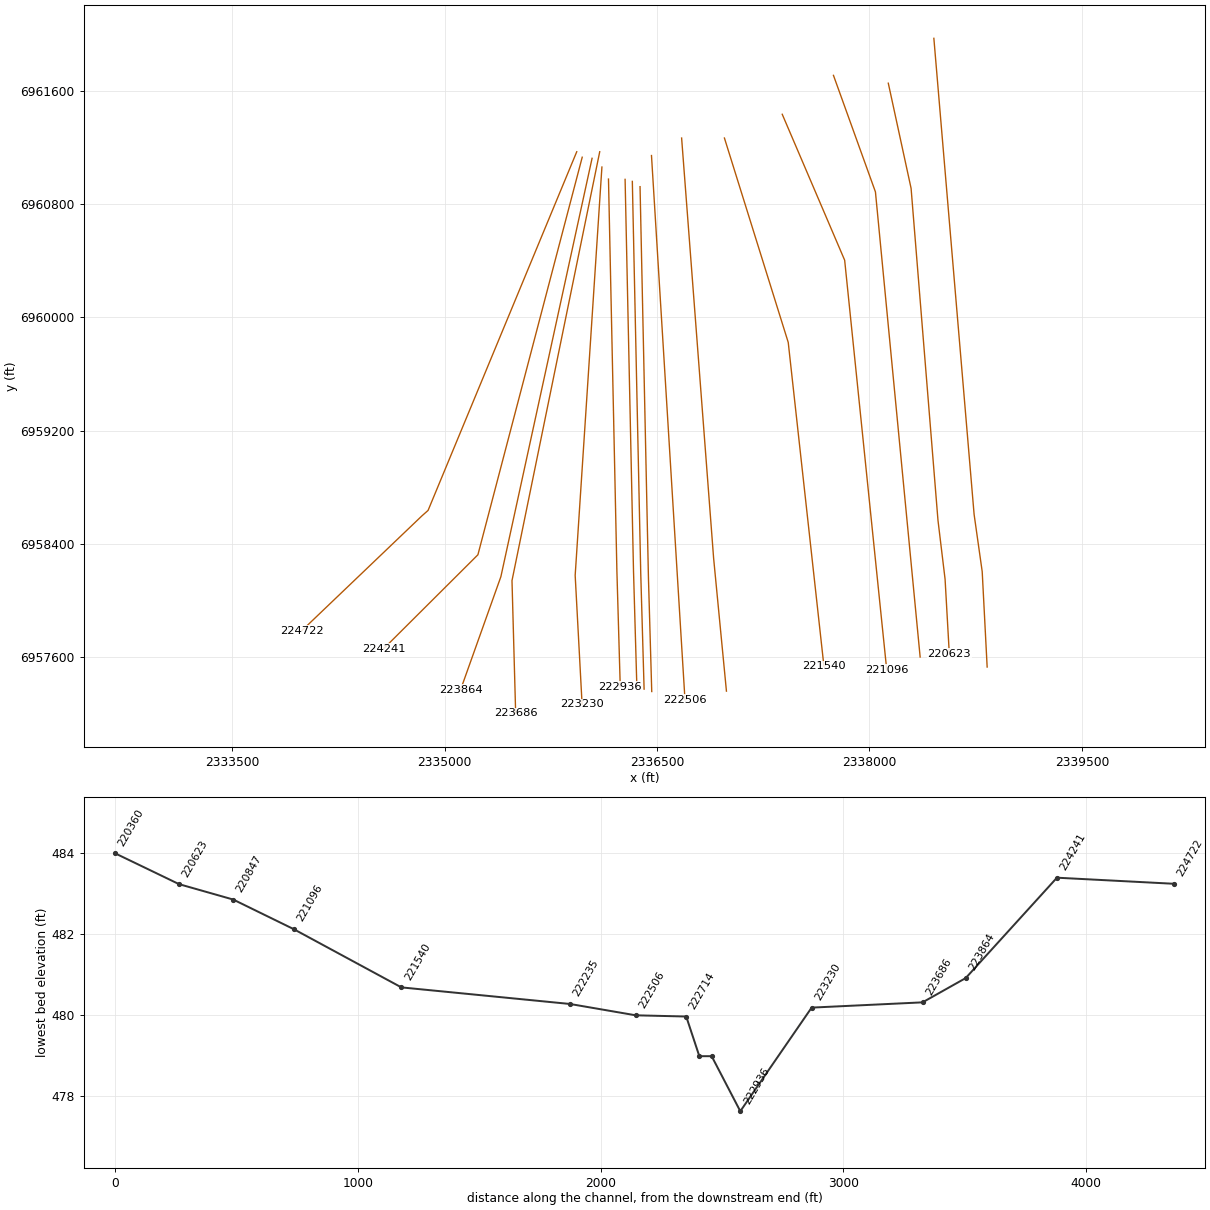
HEC-RAS study CDC_Consolidated_Model.prj: Upper Trinity CDC Consolidated Model

--- CDC_Consolidated_Model.g03 (geometry) --- (continued)

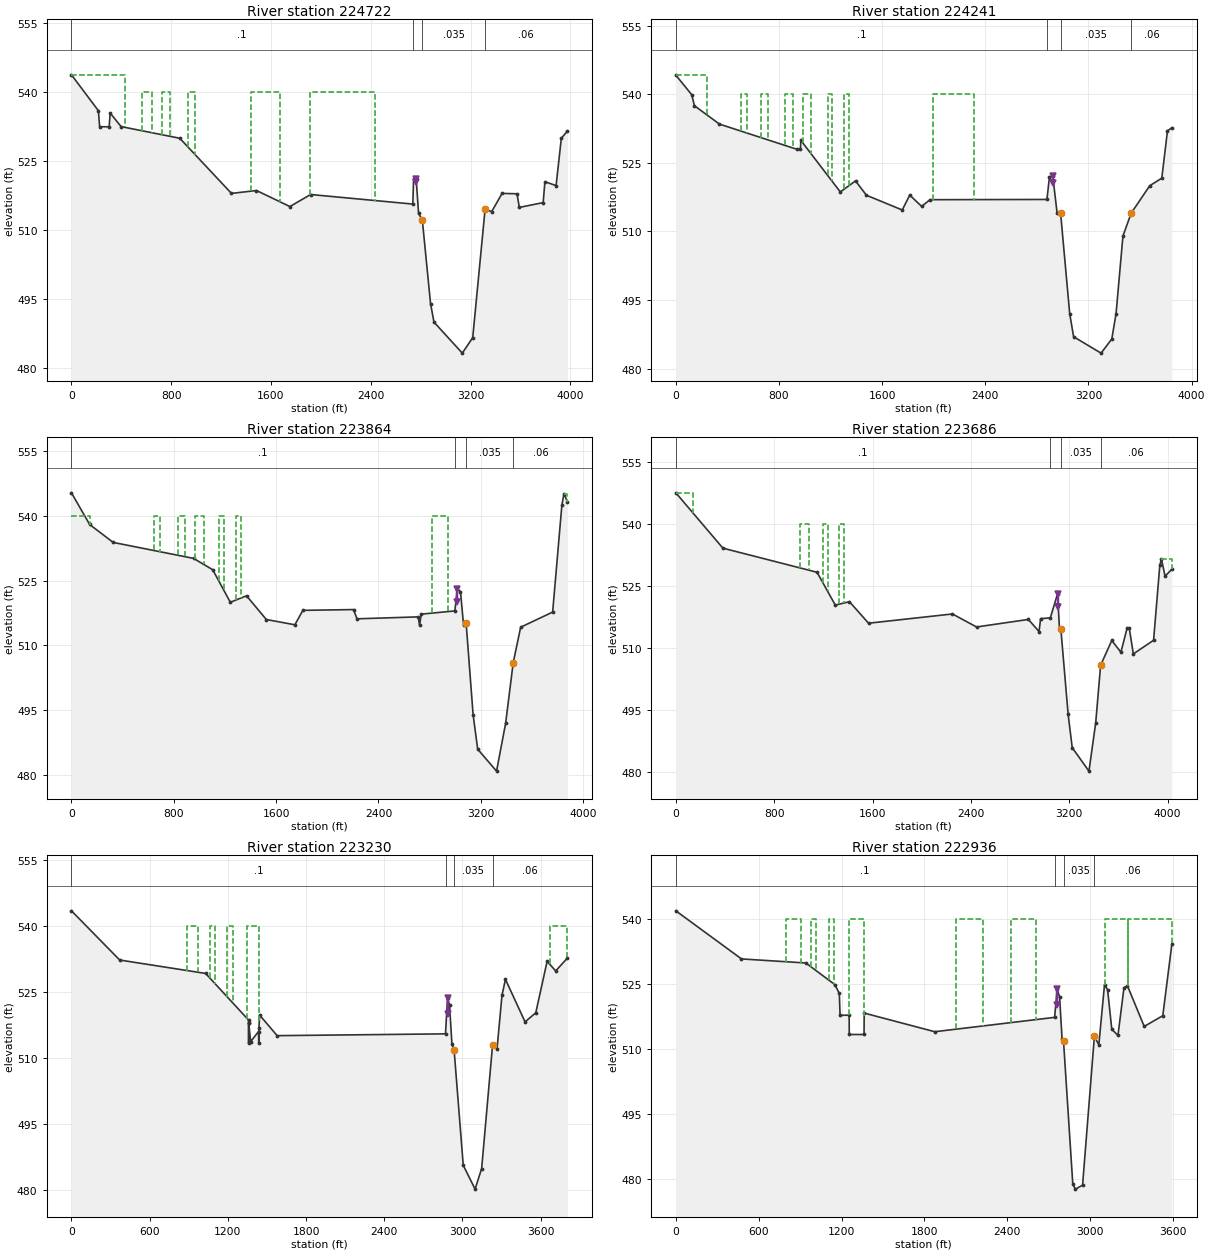
Type RM Length L Ch R = 1 ,224722  ,481,481,779
BEGIN DESCRIPTION:
This cross section corresponds to cross section 224600.2 of the non-georeferenced CDC model which was the source of this model.
Flow confined up to 50-year flood at non-federal levee in LOB.
Ineffective flow in LOB due to structures.
Effective flow set at top of US 287 in ROB.
END DESCRIPTION:
XS GIS Cut Line= 4
 2335932.0128127 6961171.9360164 2334881.8416716 6958635.9885741
 2334837.8977654 6958596.9788046 2333989.8180344  6957785.778638
#Sta/Elev= 30
       0   543.8  215.87     536  225.83   532.5  302.31   532.5  310.21  535.49
  397.92  532.54  868.45     530 1283.05     518 1483.75  518.63 1751.57  515.14
 1917.55  517.76 2737.21  515.68 2743.46  521.13 2763.94  521.24 2783.34  513.66
 2813.57  512.17 2879.52     494 2906.83     490 3133.95  483.25  3217.6  486.62
 3316.61   514.5 3369.88  514.05 3453.02     518 3572.85  517.92 3591.22  514.95
  3782.5     516 3796.42  520.55 3886.08   519.7  3928.2     530 3977.13  531.57
#Mann= 4 ,-1,0
       0      .1       0 2737.21     .06       0 2813.57    .035       0
 3316.61     .06       0
Levee=-1,2763.94,520.5,0,,,Levee 1,
#XS Ineff= 6 ,-1
       0  433.03 543.796 1915.16 2434.15     540    1439 1675.82     540
  934.09  993.45     540  724.94   787.2     540  562.27  643.52     540
Permanent Ineff=
       F       F       F       F       F       F
Bank Sta=2813.57,3316.61
XS Rating Curve= 0 ,0
Exp/Cntr=0.3,0.1

Type RM Length L Ch R = 1 ,224241  ,376,376,1284
BEGIN DESCRIPTION:
This cross section corresponds to cross section 224119.3 of the non-georeferenced CDC model which was the source of this model.
Flow confined up to 50-year flood at non-federal levee in LOB.
Ineffective flow in LOB due to structures.
Effective flow set at top of US 287 in ROB.
END DESCRIPTION:
XS GIS Cut Line= 3
 2335970.6703568 6961133.2784722 2335233.8454865 6958322.3246911
 2334567.8756035  6957658.330874
#Sta/Elev= 30
       0  544.17  123.52  539.89  143.77   537.5   337.9  533.48  935.67     528
  966.04     528  969.03  529.93 1275.24  518.64 1393.23  521.06 1477.96  517.92
 1755.65   514.7 1813.75  517.96 1906.27  515.48 1970.46  516.95 2877.59     517
 2897.52  521.96 2923.35  522.04 2956.63     514 2983.27  514.12 3054.41     492
 3084.63  486.98 3297.42   483.4 3380.73  486.49 3413.66     492 3467.21  509.01
 3531.05     514 3674.79     520 3768.56  521.66 3812.39     532 3846.35  532.68
#Mann= 4 ,-1,0
       0      .1       0 2877.59     .06       0 2983.27    .035       0
 3531.05     .06       0
Levee=-1,2923.35,520.5,0,,,Levee 1,
#XS Ineff= 8 ,-1
       0   245.2 544.253  986.56 1051.48     540 1176.41 1211.24     540
 1305.33 1343.12     540  1995.6 2313.38     540  844.48  910.57     540
  659.95  711.77     540  508.38  554.46     540
Permanent Ineff=
       F       F       F       F       F       F       F       F
Bank Sta=2983.27,3531.05
XS Rating Curve= 0 ,0
Exp/Cntr=0.3,0.1

Type RM Length L Ch R = 1 ,223864  ,178,178,746
BEGIN DESCRIPTION:
This cross section corresponds to cross section 223743.1 of the non-georeferenced CDC model which was the source of this model.
Flow confined up to 50-year flood at non-federal levee in LOB.
Ineffective flow in LOB due to structures.
Effective flow set at top of US 287 in ROB.
END DESCRIPTION:
XS GIS Cut Line= 3
 2336040.2539881 6961125.5468856 2335396.2209912 6958167.8319306
 2335110.9056109 6957366.6040069
#Sta/Elev= 30
       0  545.33   142.1     538   326.5  533.85  954.28  530.16 1104.35  527.53
 1242.03     520 1368.61   521.5 1523.38  516.01 1746.65  514.79 1809.17  518.13
 2205.04  518.31 2232.49  516.17 2710.82  516.62 2721.33  514.68 2734.75  517.25
 2997.38     518 3016.08  523.02 3041.33  522.48 3065.62  514.63 3085.61  515.15
    3140     494 3175.89     486 3323.31  480.92  3394.4     492 3453.72  506.05
 3511.95  514.23 3761.85  517.73 3834.01  542.46 3850.68  545.17 3877.54  543.23
#Mann= 4 ,-1,0
       0      .1       0 2997.38     .06       0 3085.61    .035       0
 3453.72     .06       0
Levee=-1,3016.08,520,0,,,Levee 1,
#XS Ineff= 8 ,-1
 3850.68 3877.54  545.17 1151.83 1190.12     540 1283.83 1324.82     540
       0  144.49     540  835.56  889.65     540  642.83  693.82     540
 2822.17 2942.15     540   968.5 1033.53     540
Permanent Ineff=
       T       F       F       F       F       F       F       F
Bank Sta=3085.61,3453.72
XS Rating Curve= 0 ,0
Exp/Cntr=0.3,0.1

Type RM Length L Ch R = 1 ,223686  ,457,457,734
BEGIN DESCRIPTION:
This cross section corresponds to cross section 223565.1 of the non-georeferenced CDC model which was the source of this model.
Flow confined up to 50-year flood at non-federal levee in LOB.
Ineffective flow in LOB due to structures.
Effective flow set at top of US 287 in ROB.
END DESCRIPTION:
XS GIS Cut Line= 3
 2336094.3745758 6961171.9360164  2335474.620109 6958139.6354928
 2335500.5434811 6957201.0006556
#Sta/Elev= 30
       0  547.47  382.45  534.12 1148.41   528.3 1296.86  520.37 1411.65  521.21
  1567.2  516.01  2249.8  518.24 2445.34   515.1 2867.15  516.92 2953.97     514
 2966.63  517.11 3045.59   517.3 3104.33  523.09 3120.34   514.6 3131.58  514.51
 3190.52     494 3223.86  485.97 3359.85  480.32 3414.87     492 3454.83  505.87
 3545.54  511.85 3619.68     509  3670.7   514.9 3687.82  514.84 3720.69   508.6
 3885.51  511.89 3936.22     530 3949.56  531.47 3978.93  527.37 4033.98  529.02
#Mann= 4 ,-1,0
       0      .1       0 3045.59     .06       0 3131.58    .035       0
 3454.83     .06       0
Levee=-1,3104.33,520,0,,,Levee 1,
#XS Ineff= 5 ,-1
       0  140.92  547.46 1194.86 1233.73     540 1327.46 1370.06     540
 1013.37 1081.98     540 3949.56 4033.98  531.47
Permanent Ineff=
       F       F       F       F       T
Bank Sta=3131.58,3454.83
XS Rating Curve= 0 ,0
Exp/Cntr=0.3,0.1

Type RM Length L Ch R = 1 ,223230  ,294,294,415
BEGIN DESCRIPTION:
This cross section corresponds to cross section 223108.4 of the non-georeferenced CDC model which was the source of this model.
Flow confined up to 50-year flood at non-federal levee in LOB.
Ineffective flow in LOB due to structures.
END DESCRIPTION:
XS GIS Cut Line= 3
 2336109.8376193 6961063.6947114  2335920.930483 6958176.8049269
 2335969.7647085 6957265.5018447
#Sta/Elev= 30
       0  543.44  370.02  532.26 1029.46  529.21 1358.49  518.63 1359.14     518
  1359.5  513.29 1359.82     518 1375.21  513.72 1435.31     516 1437.38  513.29
 1438.38  516.71 1443.71  519.75 1578.21  515.07 2870.01  515.48 2885.46  523.62
 2901.21  521.99 2919.31  513.09 2936.26  511.73 3006.11  485.62 3096.94  480.19
 3147.41  484.87  3231.2  512.97  3265.7  512.13 3303.43  524.23 3329.91  527.86
 3480.47   518.2 3562.77  520.27 3649.78  531.97 3715.39  529.78 3805.67  532.71
#Mann= 4 ,-1,0
       0      .1       0 2870.01     .06       0 2936.26    .035       0
  3231.2     .06       0
Levee=-1,2885.46,520,0,,,Levee 1,
#XS Ineff= 6 ,-1
 1350.23 1441.12     540  886.88  974.43     540 1064.48 1101.55     540
 1194.08 1239.52     540 3670.57 3805.67     540 3329.91 3670.27  527.86
Permanent Ineff=
       F       F       F       F       T       T
Bank Sta=2936.26,3231.2
XS Rating Curve= 0 ,0
Exp/Cntr=0.3,0.1

Type RM Length L Ch R = 1 ,222936  ,118,118,118
BEGIN DESCRIPTION:
This cross section corresponds to cross section 222814.9 of the non-georeferenced CDC model which was the source of this model.
Flow confined up to 50-year flood at non-federal levee in LOB.
Ineffective flow in LOB due to structures.
END DESCRIPTION:
XS GIS Cut Line= 3
   2336156.22675 6960978.6480365 2336215.6287736 6958209.1965671
 2336239.3997726 6957388.6369545
#Sta/Elev= 30
       0  541.81  475.05  530.72  941.21  529.78 1150.93   524.8 1183.43  522.77
 1188.92   517.7 1254.48  517.76 1255.48  513.29 1362.43  513.29 1363.56  518.23
 1874.72  513.93 2742.28  517.24 2760.76  523.79 2778.46   521.9 2796.22  512.24
 2806.72  511.77 2874.02  478.73 2892.96  477.63 2944.74  478.55 3030.21  512.86
 3062.37  510.91 3103.61  524.78 3125.91  523.61 3156.04  514.53 3200.84  513.06
 3244.68  524.12 3269.82   524.5 3390.96  515.15 3525.41  517.62 3590.99  534.07
#Mann= 4 ,-1,0
       0      .1       0 2742.28     .06       0 2806.72    .035       0
 3030.21     .06       0
Levee=-1,2760.76,520,0,,,Levee 1,
#XS Ineff= 8 ,-1
 1254.48 1363.43     540 3271.41 3590.99     540  800.41  903.27     540
  980.25 1013.67     540 1106.15 1141.64     540 2029.58 2220.15     540
 2427.41 2604.02     540 3103.61 3271.41     540
Permanent Ineff=
       F       T       F       F       F       F       F       T
Bank Sta=2806.72,3030.21
XS Rating Curve= 0 ,0
Exp/Cntr=0.5,0.3

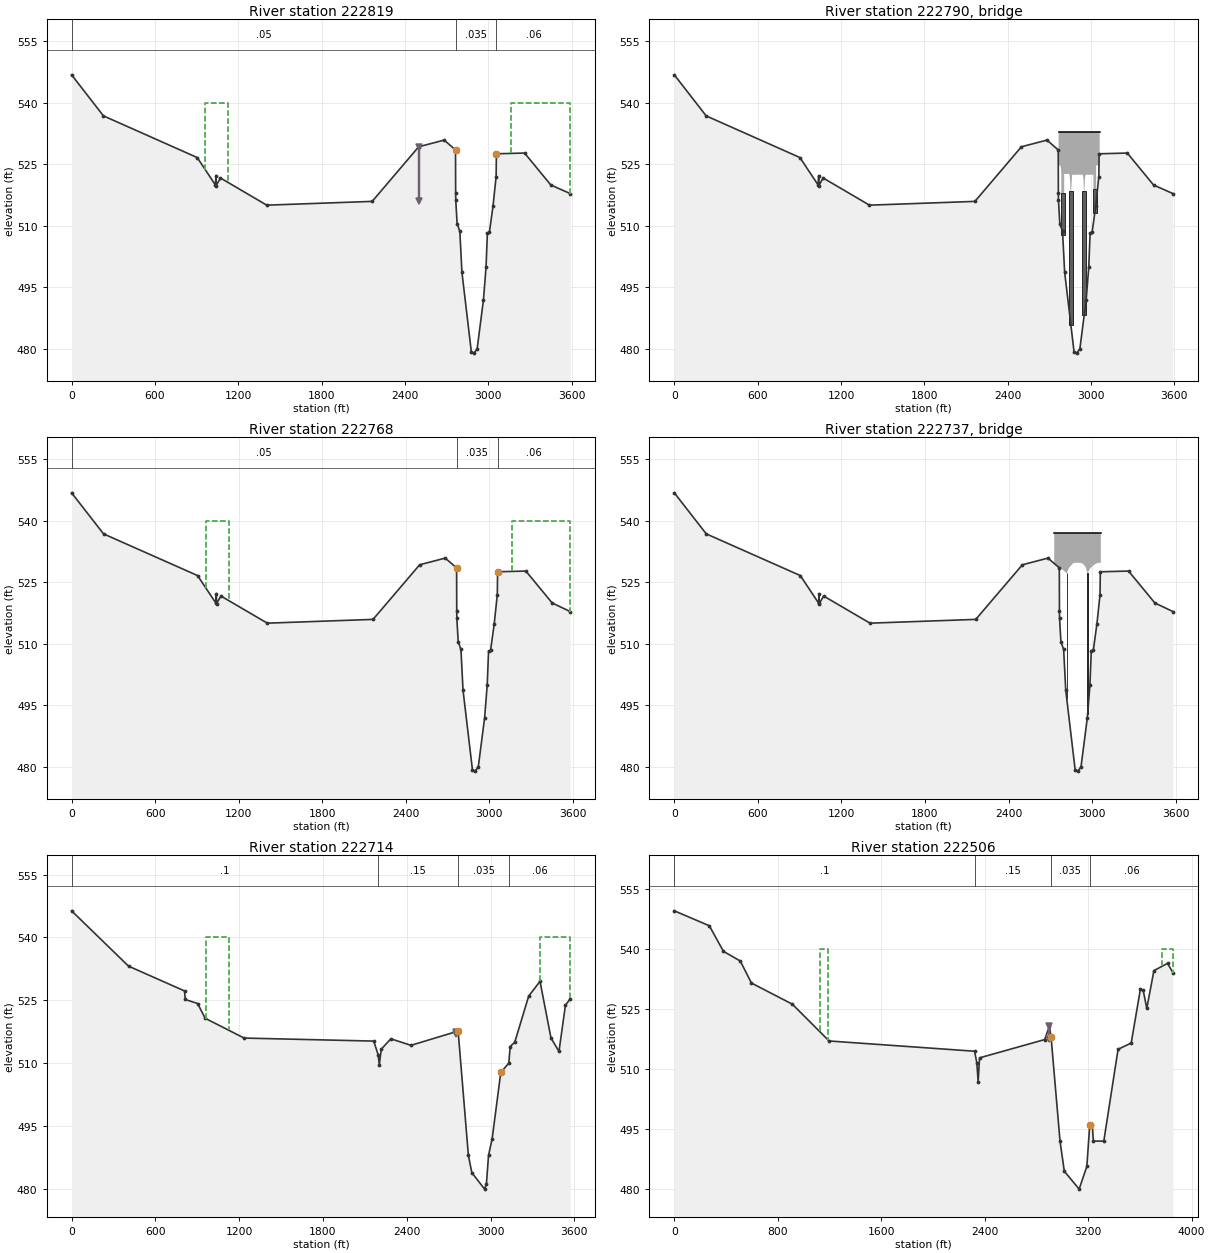
Type RM Length L Ch R = 1 ,222819  ,50.83,50.83,50.83
BEGIN DESCRIPTION:
This cross section corresponds to cross section 222701 of the non-georeferenced CDC model which was the source of this model.
Upstream of Riverside Drive.
Riverside Drive is downstream end of Fort Worth Floodway - a USACE Fort Worth District Federal local flood protection project.
Flooding flows behind the bridge through the road fill opening at the XS limit
END DESCRIPTION:
XS GIS Cut Line= 3
      2336273.61     6960976.591      2336333.01     6958207.235
     2336356.778     6957386.771
#Sta/Elev= 30
       0  546.87  229.28  536.86  904.62  526.69  1035.6     520  1039.7   522.3
  1040.7  519.86 1072.19   521.7 1405.25  515.08 2164.58     516 2499.28  529.32
 2682.95  530.95  2764.5  528.56 2765.52     518 2766.26  516.27 2776.04  510.56
 2795.67  508.67 2810.74  498.71 2878.21  479.35 2896.75  478.99  2920.2     480
 2965.75     492 2984.42     500    2994  508.23  3008.6  508.45 3034.86  514.97
 3056.89  522.05 3059.01  527.61  3261.9  527.79 3450.81     520  3590.8   517.9
#Mann= 3 ,0,0
       0     .05       0  2764.5    .035       0 3059.01     .06       0
Levee=-1,2500,516,0,,,Levee 1,
#XS Ineff= 3 ,-1
  962.85 1127.41     540 3163.84  3590.8     540 1127.41    2500     516
Permanent Ineff=
       F       T       F
Bank Sta=2764.5,3059.01
XS Rating Curve= 0 ,0
Exp/Cntr=0.5,0.3

Type RM Length L Ch R = 3 ,222790  ,,,
BEGIN DESCRIPTION:
Riverside Drive - upstream bridge
Data from bridge plans, USACE 1939 survey.
Note:  Internal bridge cross-sections modified to represent geometry under bridge.
END DESCRIPTION:
Node Name=Riverside Drive
Bridge Culvert--1,0,-1,-1, 0
Deck Dist Width WeirC Skew NumUp NumDn MinLoCord MaxHiCord MaxSubmerge Is_Ogee
1.1,44,2.6,0, 26, 26, , , 0.95, 0, 0,0,,
 2767.02    2779    2784  2786.5  2786.5  2807.5  2807.5  2840.5  2845.5  2849.5
    2853    2858    2860    2865    2942    2947    2949    2953    2955  2957.5
  2962.5  3017.5  3017.5  3037.5  3037.5    3063
     533     533     533     533     533     533     533     533     533     533
     533     533     533     533     533     533     533     533     533     533
     533     533     533     533     533     533
   524.8   524.8   524.2   522.7     518     518   522.7   522.7   522.5     521
   518.5   518.5     520   522.5   522.5     521   518.5   518.5     520   521.8
   522.5   522.5     519     519   524.8   524.8
 2767.02    2779    2784  2786.5  2786.5  2807.5  2807.5  2840.5  2845.5  2849.5
    2853    2858    2860    2865    2942    2947    2949    2953    2955  2957.5
  2962.5  3017.5  3017.5  3037.5  3037.5    3063
     533     533     533     533     533     533     533     533     533     533
     533     533     533     533     533     533     533     533     533     533
     533     533     533     533     533     533
   524.8   524.8   524.2   522.7     518     518   522.7   522.7   522.5     521
   518.5   518.5     520   522.5   522.5     521   518.5   518.5     520   521.8
   522.5   522.5     519     519   524.8   524.8
Pier Skew, UpSta & Num, DnSta & Num=  ,2797, 2 ,2797, 2 , 0 , 0 , 0 ,,
      29      29
     450     520
      29      29
     450     520
Pier Skew, UpSta & Num, DnSta & Num=  ,2855.5, 2 ,2855.5, 2 , 0 , 0 , 0 ,,
      29      29
     450     530
      29      29
     450     530
Pier Skew, UpSta & Num, DnSta & Num=  ,2951.5, 2 ,2951.5, 2 , 0 , 0 , 0 ,,
      29      29
     450     530
      29      29
     450     530
Pier Skew, UpSta & Num, DnSta & Num=  ,3027.5, 2 ,3027.5, 2 , 0 , 0 , 0 ,,
      29      29
     450     520
      29      29
     450     520
BR Coef=-1 , 0 , 0 ,, 0 ,,,0.8,-1,,0,
WSPro=,,,, 1 ,,,, 0 ,,,, 0 ,,,,-1 ,-1 ,-1 , 0 , 0 , 0 , 0 , 0
BR U #Sta/Elev= 494
       0  542.46      14  542.08   16.69     542   27.09     542   27.11  542.06
   28.31  542.06   45.15  541.62   47.67   541.6   53.42  541.45   54.63  541.44
   57.15  541.34   65.74  540.86   85.68  540.24   89.21  540.12   91.79     540
   97.63  539.86  107.74  539.69  111.32  539.69  144.81  538.61  146.59   538.6
  152.69  538.28  166.38  537.96  174.32  537.77  179.43  537.66  180.39  537.65
  182.65  537.58  205.84  537.02   218.6  536.71  219.65  536.68   222.4  536.54
  233.37  536.27  233.87  536.14  235.66  536.11  239.75  535.99  241.35     536
  242.29  535.97  248.14  535.74  252.44  535.62  253.39  535.61  264.34  535.28
  265.72  535.23  290.19   534.5  308.58  534.33   309.1  534.32  336.43  534.07
  341.39  534.03  343.96     534  346.23  533.99  362.72  533.83  389.94  533.58
  391.41  533.54  414.07  533.02  414.72  532.98   438.1  532.42  451.26  532.11
  453.19  532.12  467.64  531.97  469.79  531.94  483.47   531.8  487.22  531.75
  502.97  531.59  505.31  531.59  540.21  531.23  541.94  531.22   543.5  531.14
  575.48  530.82  576.94  530.75  577.99  530.73  581.32  530.74  611.81  530.43
  614.82  530.43  617.09   530.3  638.08  530.03  638.62     530  642.97  529.97
  663.33  529.85   665.6  529.74  667.79  529.69  688.82  529.43   691.1  529.45
  694.64  529.29  705.06  529.15  705.76   529.1  708.55  529.11  712.05  529.07
  715.58  529.37  718.17  529.41   744.7     529   746.5  529.01  748.59  528.96
  752.42  528.38  761.41     528  764.11     528  777.64  528.11  783.77  528.12
  794.22  527.95  797.15  527.95  803.33  527.85   808.7  527.84   835.9  527.42
  841.27   527.4  846.19  527.33  849.58  527.31  876.43   526.9  882.29  526.22
  885.58  526.12  892.39     526  906.44     526  920.08  525.65  921.72  525.63
  931.24   525.1  943.35  524.76  950.62  525.26  951.33  525.28  957.83  524.35
   965.2   524.2  971.64  524.02  974.63     524  980.32     524  981.82  523.94
  990.17  523.94 1004.58  523.79  1013.1  523.77 1014.84  523.75 1017.95   523.6
 1020.16  523.52 1022.44  523.49 1047.87  523.21  1052.5  523.18 1057.83  523.13
 1061.17  523.25 1064.17  523.22 1070.92     523 1073.96  522.98 1077.16  522.94
 1080.46  522.87 1091.86  522.22 1098.06  522.06 1101.64     522 1108.82  521.91
 1111.97  521.75 1115.15  521.62 1116.41  521.58 1132.46  521.16 1135.84   521.1
  1137.6  521.08 1145.18  520.26 1147.34   520.2 1155.74     520 1161.58     520
 1163.27  519.98  1167.3   519.8  1174.8  519.78 1177.06  519.32 1179.11  519.19
  1179.7   519.1 1189.91  519.53 1190.59  519.52 1203.97  519.19 1205.57  519.17
  1208.2  518.93 1208.91   518.9 1210.51  518.95  1211.6  519.01 1220.77  518.78
 1223.82  518.61 1231.11  518.22 1235.43  518.11 1244.99     518 1248.49  517.99
 1260.68  517.97 1262.84  517.96 1265.17  517.97 1270.35  517.95 1275.35  517.96
 1280.25  517.89 1286.25  517.94 1289.78  517.87 1295.95  517.88 1302.34  517.77
 1307.88  517.66 1314.84  517.35 1319.18   517.3 1322.46  517.28 1324.47  517.28
 1327.11   517.3 1330.02  517.29 1331.21  517.26 1336.98  517.05  1349.4  516.92
 1356.44  516.93 1367.79   516.1 1368.56     516 1371.01     516 1378.78  516.06
 1379.82  516.05    1392  516.06 1400.35     516  1404.8     516 1407.55  516.24
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BR U #Mann= 3
       0     .05 2767.02    .035  3071.9    .055
BR U Banks=2811.84,2993.47
BR D #Sta/Elev= 500
       0  542.46      14  542.08   16.69     542   27.09     542   27.11  542.06
   28.31  542.06   45.15  541.62   47.67   541.6   53.42  541.45   54.63  541.44
   57.15  541.34   65.74  540.86   85.68  540.24   89.21  540.12   91.79     540
   97.63  539.86  107.74  539.69  111.32  539.69  144.81  538.61  146.59   538.6
  152.69  538.28  166.38  537.96  174.32  537.77  179.43  537.66  180.39  537.65
  182.65  537.58  205.84  537.02   218.6  536.71  219.65  536.68   222.4  536.54
  232.82  536.29  233.37  536.27  233.87  536.14  235.66  536.11  239.75  535.99
  241.35     536  242.29  535.97  248.14  535.74  252.44  535.62  253.39  535.61
  264.34  535.28  265.72  535.23  290.19   534.5  308.58  534.33   309.1  534.32
  336.43  534.07  341.39  534.03  343.96     534  346.23  533.99  362.72  533.83
  389.94  533.58  391.41  533.54  414.07  533.02  414.72  532.98   438.1  532.42
  451.26  532.11  453.19  532.12  467.64  531.97  469.79  531.94  483.47   531.8
  487.22  531.75  502.97  531.59  505.31  531.59  540.21  531.23  541.94  531.22
   543.5  531.14  575.48  530.82  576.94  530.75  577.99  530.73  581.32  530.74
  611.81  530.43  614.82  530.43  617.09   530.3  631.33  530.14   633.4   530.1
  635.55  530.08  638.08  530.03  638.62     530  642.97  529.97  663.33  529.85
   665.6  529.74  667.79  529.69  688.82  529.43   691.1  529.45  694.64  529.29
  705.06  529.15  705.76   529.1  708.55  529.11  712.05  529.07  715.58  529.37
  718.17  529.41   744.7     529   746.5  529.01  748.59  528.96  752.42  528.38
  761.41     528  764.11     528  777.64  528.11  783.77  528.12  794.22  527.95
  797.15  527.95  803.33  527.85   808.7  527.84   835.9  527.42  841.27   527.4
  846.19  527.33  849.58  527.31  876.43   526.9  882.29  526.22  885.58  526.12
  892.39     526  906.44     526  920.08  525.65  921.72  525.63  931.24   525.1
  943.35  524.76  950.62  525.26  951.33  525.28  957.83  524.35   965.2   524.2
  971.64  524.02  974.63     524  980.32     524  981.82  523.94  990.17  523.94
 1004.58  523.79  1013.1  523.77 1014.84  523.75 1017.95   523.6 1020.16  523.52
 1022.44  523.49 1047.87  523.21  1052.5  523.18 1057.83  523.13 1061.17  523.25
 1064.17  523.22 1070.92     523 1073.96  522.98 1077.16  522.94 1080.46  522.87
 1091.86  522.22 1098.06  522.06 1101.64     522 1108.82  521.91 1111.97  521.75
 1115.15  521.62 1116.41  521.58 1132.46  521.16 1135.84   521.1  1137.6  521.08
 1145.18  520.26 1147.34   520.2 1155.74     520 1161.58     520 1163.27  519.98
  1167.3   519.8  1174.8  519.78 1177.06  519.32 1179.11  519.19  1179.7   519.1
 1189.91  519.53 1190.59  519.52 1203.97  519.19 1205.57  519.17  1208.2  518.93
 1208.91   518.9 1210.51  518.95  1211.6  519.01 1220.77  518.78 1223.82  518.61
 1231.11  518.22 1235.43  518.11 1244.99     518 1248.49  517.99 1260.68  517.97
 1262.84  517.96 1265.17  517.97 1270.35  517.95 1275.35  517.96 1280.25  517.89
 1286.25  517.94 1289.78  517.87 1295.95  517.88 1302.34  517.77 1307.88  517.66
 1314.84  517.35 1319.18   517.3 1322.46  517.28 1324.47  517.28 1327.11   517.3
 1330.02  517.29 1331.21  517.26 1336.98  517.05  1349.4  516.92 1356.44  516.93
 1367.79   516.1 1368.56     516 1371.01     516 1378.78  516.06 1379.82  516.05
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BR D #Mann= 4
       0     .05 2767.02    .035 2993.74     .05  3071.9    .055
BR D Banks=2811.84,2993.47
BC Design=,, 0 ,, 0 ,,,,,,
BC Use User HTab Curves=0
BC User HTab FreeFlow(D)= 0

Type RM Length L Ch R = 1 ,222768  ,54,54,54
BEGIN DESCRIPTION:
This cross section corresponds to cross section 222651.4 of the non-georeferenced CDC model which was the source of this model.
Cross-section located between bridges.
Flooding flows behind the bridge through the road fill opening at the XS limit
END DESCRIPTION:
XS GIS Cut Line= 3
      2336324.69     6960962.268     2336384.156     6958190.635
     2336407.859     6957372.448
#Sta/Elev= 30
       0  546.87  229.28  536.86  904.62  526.69  1035.6     520  1039.7   522.3
  1040.7  519.86 1072.19   521.7 1405.25  515.08 2164.58     516 2499.28  529.32
 2682.95  530.95  2764.5  528.56 2765.52     518 2766.26  516.27 2776.04  510.56
 2795.67  508.67 2810.74  498.71 2878.21  479.35 2896.75  478.99  2920.2     480
 2965.75     492 2984.42     500    2994  508.23  3008.6  508.45 3034.86  514.97
 3056.89  522.05 3059.01  527.61  3261.9  527.79 3450.81     520 3580.75  517.91
#Mann= 3 ,0,0
       0     .05       0  2764.5    .035       0 3059.01     .06       0
#XS Ineff= 3 ,-1
  962.85 1127.41     540 3163.84 3580.75     540 1127.41  2638.9   516.7
Permanent Ineff=
       F       T       F
Bank Sta=2764.5,3059.01
XS Rating Curve= 0 ,0
Exp/Cntr=0.5,0.3

Type RM Length L Ch R = 3 ,222737  ,,,
BEGIN DESCRIPTION:
Riverside Drive - downstream bridge
Data from bridge plans.
Upstream portion of bridge to sta 2766 removed due to influence of upstream bridge.
Note:  Internal bridge cross-sections modified to represent geometry under bridge.
END DESCRIPTION:
Node Name=Riverside Drive
Bridge Culvert--1,0,-1,-1, 0
Deck Dist Width WeirC Skew NumUp NumDn MinLoCord MaxHiCord MaxSubmerge Is_Ogee
4.8,46,2.6,0, 19, 19, , , 0.95, 0, 0,0,,
    2728    2738    2753    2773    2793    2818    2833    2853    2863    2873
    2913    2933    2953    2968    2983    3003    3023    3043    3063
     537     537     537     537     537     537     537     537     537     537
     537     537     537     537     537     537     537     537     537
   528.8   528.8   528.7   528.5     528   527.2   528.5   529.3  529.65   529.8
   529.8   529.6   528.8   527.2   528.3     529   529.5   529.8   529.8
    2728    2738    2753    2773    2793    2818    2833    2853    2863    2873
    2913    2933    2953    2968    2983    3003    3023    3043    3063
     537     537     537     537     537     537     537     537     537     537
     537     537     537     537     537     537     537     537     537
   528.8   528.8   528.7   528.5     528   527.2   528.5   529.3  529.65   529.8
   529.8   529.6   528.8   527.2   528.3     529   529.5   529.8   529.8
Pier Skew, UpSta & Num, DnSta & Num=  ,2818, 2 ,2818, 2 , 0 , 0 , 0 ,,
     3.5     3.5
     450     533
     3.5     3.5
     450     533
Pier Skew, UpSta & Num, DnSta & Num=  ,2968, 2 ,2968, 2 , 0 , 0 , 0 ,,
     3.5     3.5
     450     533
     3.5     3.5
     450     533
BR Coef=-1 , 0 , 0 ,, 0 ,,,0.8,-1,,0,
WSPro=,,,, 1 ,,,, 0 ,,,, 0 ,,,,-1 ,-1 ,-1 , 0 , 0 , 0 , 0 , 0
BR U #Sta/Elev= 438
       0  546.67     4.4  546.56   44.87  545.78   50.29  545.63   55.72  545.48
   61.17  545.32   66.66  545.16   94.48  544.36   95.74  544.28   97.22  544.25
  103.66  543.82     104  543.79   142.4  540.83   144.4  540.71  146.39   540.6
  148.37   540.5  150.34   540.4   153.2  540.28  156.02  540.19  158.81  540.11
  208.41  538.11  210.28  538.15  214.02  537.59  214.22  537.56  214.35  537.56
  228.18  536.93  244.68  536.68   246.5  536.63   251.7  536.51  252.27  536.51
  255.75  536.42  256.65  536.42  258.59  536.37  333.35  534.71  334.28   534.7
   338.5  534.57  339.38  534.56  344.31   534.4  365.16  534.62  368.83  534.66
  375.66   534.7  382.32  534.54  398.51  533.92   406.1  533.75  423.59  533.31
     425  533.27  425.69  533.25  427.09  533.21   450.2  532.16  450.55  532.14
  450.79  532.15  473.03  532.82  483.01  532.56  484.54  532.57  486.91  532.53
  547.21  531.45  555.43  531.36  563.65  531.18  565.13  531.18  567.44  531.16
  591.53  530.72  596.46   530.7  601.36  530.68  645.52   529.8  650.42  529.76
  655.29   529.7  675.92  529.58  677.12  529.62  680.78  529.71  685.19  529.72
  685.53  529.72     687   529.7  695.81  529.41  698.95   529.3  701.88  529.19
  706.46  529.36  719.21  529.72  719.88  529.67  723.56  529.42  728.15  529.14
  729.84  529.17  730.38  529.15  734.48  528.95   787.1  528.15  789.68  528.17
  793.75  528.11  795.66  528.13  799.13  528.07  800.37  528.08  806.51  527.94
  808.68  527.52  812.34  527.19  813.07  527.16  813.76  527.15  814.44  527.15
  820.81   527.1  822.64  527.11  825.62  527.09  860.16  526.63  864.13  526.66
  868.06  526.66  871.36  526.63  897.62  526.82  901.89  526.74   902.4  526.74
  904.76  526.68  913.32  525.58  913.52  525.55  913.65  525.54   933.6   523.8
  942.81  524.41  950.45  524.85  951.76   524.9  953.79  524.97  957.78  524.86
  960.25  524.85  961.86  524.84  970.26  524.69  978.46  524.46  979.11  524.43
  980.03   524.4  980.94  524.38  997.38  523.92   998.3   523.9  999.21  523.87
 1000.12  523.84 1000.63  523.81 1008.83  523.59 1009.33  523.56 1009.84  523.53
 1010.36   523.5  1018.5  523.27 1028.18  522.73 1033.37  522.59 1038.06  522.46
 1038.56  522.44 1039.42  520.24 1039.56  519.86 1042.65  519.86 1064.73  519.86
 1065.29  520.71 1065.73  521.48 1072.14  521.46 1074.04  521.39 1120.85  520.76
 1130.48  520.47 1143.56     520  1144.4  519.96 1154.04  519.51 1159.85  519.39
 1162.63  519.41 1174.42  519.54 1189.08  518.85 1192.84  518.64  1194.5   518.6
 1194.75   518.6 1201.91  518.49 1203.68  518.46 1205.06  518.46 1263.35  517.33
 1265.79  517.38 1311.84  516.98 1311.89  516.98 1312.72  516.97 1314.69  516.96
 1353.55  516.52 1355.36  516.46 1370.25   515.6 1380.23  515.47 1381.65  515.45
  1397.7  514.96 1401.28  515.11 1402.33  515.15 1413.29  515.36 1416.29  515.39
  1427.5  515.56 1431.58  515.57  1437.8  515.64 1443.58  515.64 1448.52  515.69
  1456.1  515.67 1459.68  515.69 1469.17  515.64 1469.58  515.64 1471.28  515.64
  1471.4  515.64  1482.8  515.58 1483.18  515.58 1486.31  515.56 1502.59  515.65
    1514  515.72 1519.89  515.77 1523.39   515.8 1525.59  515.82 1526.99  515.82
 1567.92  515.78 1616.48  515.37 1620.03  515.31  1623.3  515.26  1626.9  515.21
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BR U #Mann= 3
       0     .05 2787.36    .035 3019.18     .05
BR U Banks=2787.36,3019.18
BR D #Sta/Elev= 445
       0  546.67     4.4  546.56   44.87  545.78   50.29  545.63   55.72  545.48
   61.17  545.32   66.66  545.16   94.48  544.36   95.74  544.28   97.22  544.25
  103.66  543.82     104  543.79   142.4  540.83   144.4  540.71  146.39   540.6
  148.37   540.5  150.34   540.4   153.2  540.28  156.02  540.19  158.81  540.11
  208.41  538.11  210.28  538.15  214.02  537.59  214.22  537.56  214.35  537.56
  228.18  536.93  244.68  536.68   246.5  536.63   251.7  536.51  252.27  536.51
  255.75  536.42  256.65  536.42  258.59  536.37  333.35  534.71  334.28   534.7
   338.5  534.57  339.38  534.56  344.31   534.4  365.16  534.62  368.83  534.66
  375.66   534.7  382.32  534.54  398.51  533.92   406.1  533.75  423.59  533.31
     425  533.27  425.69  533.25  427.09  533.21   450.2  532.16  450.55  532.14
  450.79  532.15  473.03  532.82  483.01  532.56  484.54  532.57  486.91  532.53
  547.21  531.45  555.43  531.36  563.65  531.18  565.13  531.18  567.44  531.16
  591.53  530.72  596.46   530.7  601.36  530.68  645.52   529.8  650.42  529.76
  655.29   529.7  675.92  529.58  677.12  529.62  680.78  529.71  685.19  529.72
  685.53  529.72     687   529.7  695.81  529.41  698.95   529.3  701.88  529.19
  706.46  529.36  719.21  529.72  719.88  529.67  723.56  529.42  728.15  529.14
  729.84  529.17  730.38  529.15  734.48  528.95   787.1  528.15  789.68  528.17
  793.75  528.11  795.66  528.13  799.13  528.07  800.37  528.08  806.51  527.94
  808.68  527.52  812.34  527.19  813.07  527.16  813.76  527.15  814.44  527.15
  820.81   527.1  822.64  527.11  825.62  527.09  860.16  526.63  864.13  526.66
  868.06  526.66  871.36  526.63  897.62  526.82  901.89  526.74   902.4  526.74
  904.76  526.68  913.32  525.58  913.52  525.55  913.65  525.54   933.6   523.8
  942.81  524.41  950.45  524.85  951.76   524.9  953.79  524.97  957.78  524.86
  960.25  524.85  961.86  524.84  970.26  524.69  978.46  524.46  979.11  524.43
  980.03   524.4  980.94  524.38  997.38  523.92   998.3   523.9  999.21  523.87
 1000.12  523.84 1000.63  523.81 1008.83  523.59 1009.33  523.56 1009.84  523.53
 1010.36   523.5  1018.5  523.27 1028.18  522.73 1033.37  522.59 1038.06  522.46
 1038.56  522.44 1039.42  520.24 1039.56  519.86 1042.65  519.86 1064.73  519.86
 1065.29  520.71 1065.73  521.48 1072.14  521.46 1074.04  521.39 1120.85  520.76
 1130.48  520.47 1143.56     520  1144.4  519.96 1154.04  519.51 1159.85  519.39
 1162.63  519.41 1174.42  519.54 1189.08  518.85 1192.84  518.64  1194.5   518.6
 1194.75   518.6 1201.91  518.49 1203.68  518.46 1205.06  518.46 1263.35  517.33
 1265.79  517.38 1311.84  516.98 1311.89  516.98 1312.72  516.97 1314.69  516.96
 1353.55  516.52 1355.36  516.46 1370.25   515.6 1380.23  515.47 1381.65  515.45
  1397.7  514.96 1401.28  515.11 1402.33  515.15 1413.29  515.36 1416.29  515.39
  1427.5  515.56 1431.58  515.57  1437.8  515.64 1443.58  515.64 1448.52  515.69
  1456.1  515.67 1459.68  515.69 1469.17  515.64 1469.58  515.64 1471.28  515.64
  1471.4  515.64  1482.8  515.58 1483.18  515.58 1486.31  515.56 1502.59  515.65
    1514  515.72 1519.89  515.77 1523.39   515.8 1525.59  515.82 1526.99  515.82
 1567.92  515.78 1616.48  515.37 1620.03  515.31  1623.3  515.26  1626.9  515.21
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BR D #Mann= 3
       0     .05 2787.36    .035 3019.18     .05
BR D Banks=2787.36,3019.18
BC Design=,, 0 ,, 0 ,,,,,,
BC Use User HTab Curves=0
BC User HTab FreeFlow(D)= 0

Type RM Length L Ch R = 1 ,222714  ,208,208,313
BEGIN DESCRIPTION:
This cross section corresponds to cross section 222551.6 of the non-georeferenced CDC model which was the source of this model.
Downstream of Riverside Drive.
Flow up to 50-year flood confined at non-federal levee in LOB.
Ineffective flow in LOB due to structure.
END DESCRIPTION:
XS GIS Cut Line= 4
     2336379.203     6960925.053     2336438.581     6958156.729
     2336460.789     6957390.128      2336461.79     6957355.543
#Sta/Elev= 30
       0  546.35  407.52  533.16  808.72  527.24  813.42  525.21  902.25  524.24
  956.23  520.73 1235.31     516 2163.34  515.28 2195.08     512 2203.36  509.66
 2217.27  513.36 2285.83  515.82 2430.05  514.27  2767.6  517.67 2841.05     488
  2865.7  483.89 2957.18  479.97 2970.31  481.31 2985.25     488 3011.32     492
 3072.95   507.8 3130.55  510.02 3140.22  513.97 3173.25  515.03 3272.74     526
  3353.9  529.53 3432.49     516 3489.69  512.82 3535.89  523.83 3570.49  525.37
#Mann= 4 ,-1,0
       0      .1       0 2195.08     .15       0  2767.6    .035       0
 3130.55     .06       0
Levee=-1,2750.5,517,0,,,Levee 2,
#XS Ineff= 2 ,-1
  961.13 1127.01     540  3353.9 3570.49     540
Permanent Ineff=
       F       T
Bank Sta=2767.6,3072.95
XS Rating Curve= 0 ,0
Exp/Cntr=0.5,0.3

Type RM Length L Ch R = 1 ,222506  ,271,271,309
BEGIN DESCRIPTION:
This cross section corresponds to cross section 222384.6 of the non-georeferenced CDC model which was the source of this model.
Flow up to 50-year flood confined at non-federal levee in LOB.
Effective flow limit set at IH 30 in ROB.
Ineffective flow in LOB due to structure.
TRWD wetland area adjacent to West Fork river channel.
END DESCRIPTION:
XS GIS Cut Line= 2
 2336459.9999321 6961145.0963657 2336696.6326332 6957296.7880651
#Sta/Elev= 30
       0  549.56  270.64  545.83  379.94  539.43  509.88  537.02  596.43  531.51
  912.37  526.23 1196.86  517.03 2321.44  514.47 2339.22  511.53 2349.15  506.86
 2359.88  512.81 2863.05  517.38 2899.88  520.66 2913.02     518 2982.24     492
 3015.33  484.48  3130.1     480 3189.71   485.7 3211.97  496.05 3231.25   496.1
 3240.17     492 3320.74     492 3431.07  514.95  3532.6  516.52 3603.39  529.93
 3624.99  529.74 3653.15  525.18 3708.14  534.61 3813.28  536.43 3855.58  534.09
#Mann= 4 ,-1,0
       0      .1       0 2321.44     .15       0 2913.02    .035       0
 3211.97     .06       0
Levee=-1,2899.88,517.5,0,,,Levee 2,
#XS Ineff= 2 ,-1
 1123.42 1187.94     540    3774 3855.58     540
Permanent Ineff=
       F       T
Bank Sta=2913.02,3211.97
XS Rating Curve= 0 ,0
Exp/Cntr=0.3,0.1

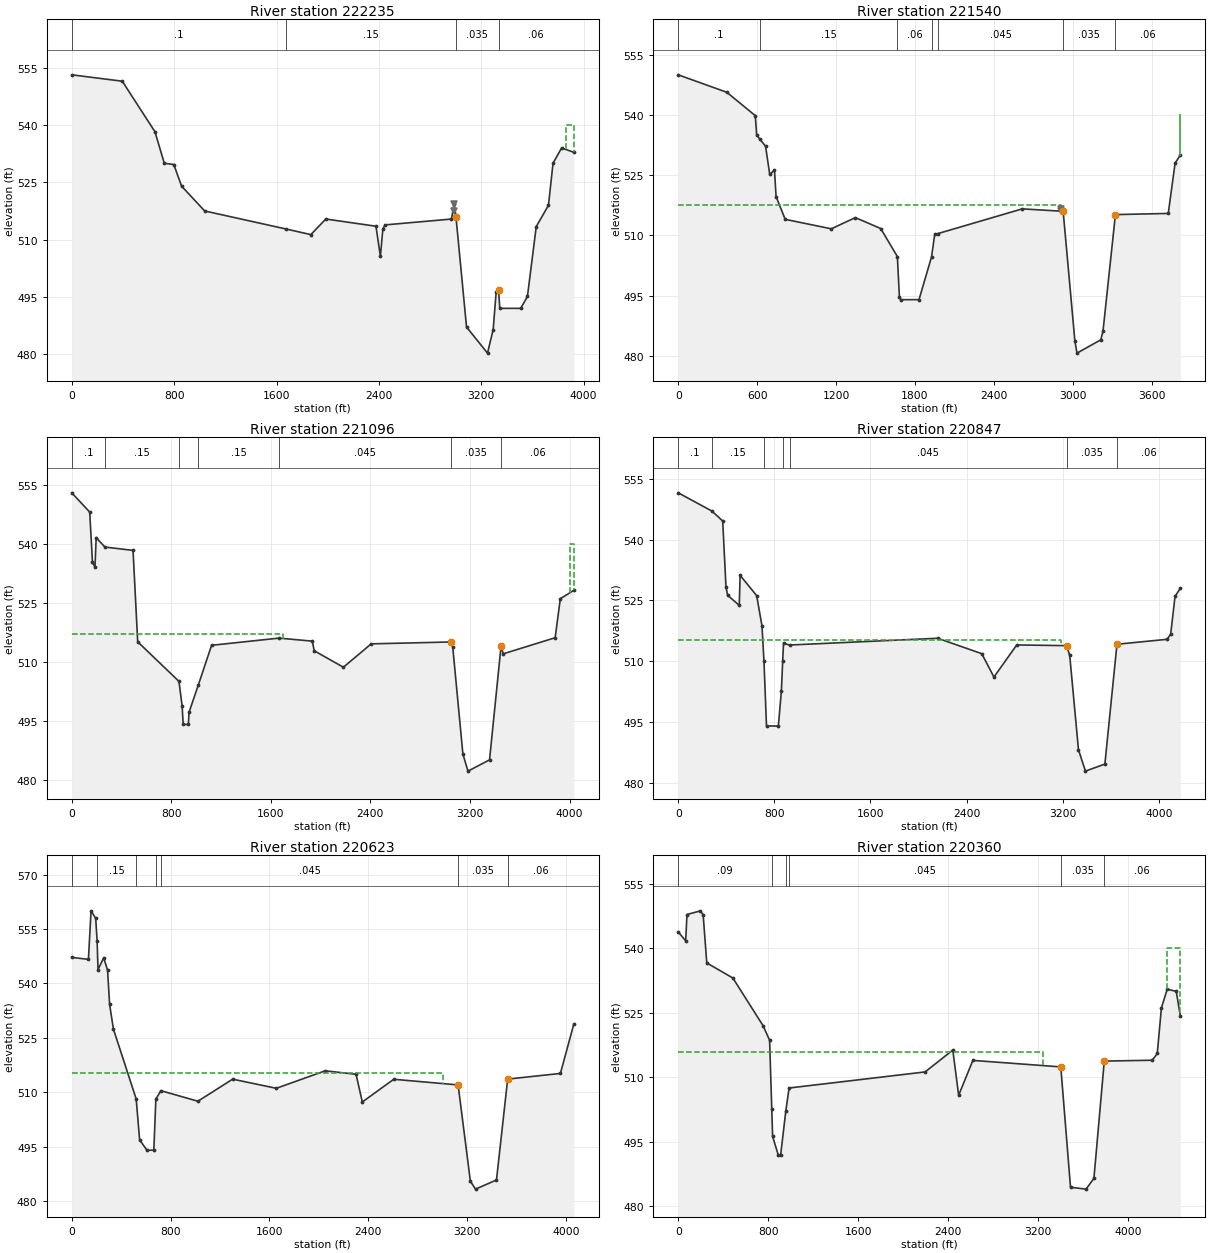
Type RM Length L Ch R = 1 ,222235  ,695,695,740
BEGIN DESCRIPTION:
This cross section corresponds to cross section 222113.5 of the non-georeferenced CDC model which was the source of this model.
Flow up to 50-year flood confined at non-federal levee in LOB.
Effective flow limit set at IH 30 in ROB.
TRWD wetland area adjacent to West Fork river channel.
END DESCRIPTION:
XS GIS Cut Line= 3
 2336672.8499668 6961268.9011834 2336898.9864298 6958297.2619831
 2336989.4820323  6957358.265457
#Sta/Elev= 30
       0  553.14  394.73  551.47  650.25  538.23  722.85     530  797.23  529.66
   858.2     524 1038.52   517.5 1672.62  512.79 1868.23  511.31  1985.3  515.39
 2377.28   513.5  2411.7  505.61 2431.09  512.79 2448.21  513.85 2966.73  515.38
  2988.2  519.23 3002.31     516 3084.92  487.12 3248.85  480.28 3293.23  486.46
 3316.69  496.34  3335.3  496.71 3344.89     492 3508.21     492 3560.85  495.12
 3629.91  513.42 3725.15  518.96 3761.02     530 3828.22     534 3923.58  532.86
#Mann= 4 ,-1,0
       0      .1       0 1672.62     .15       0 3002.31    .035       0
  3335.3     .06       0
Levee=-1,2988.2,517.5,0,,,Levee 2,
#XS Ineff= 2 , 0
       0 3002.31     516    3860       0     540
Permanent Ineff=
       F       T
Bank Sta=3002.31,3335.3
XS Rating Curve= 0 ,0
Exp/Cntr=0.3,0.1

Type RM Length L Ch R = 1 ,221540  ,444,444,434
BEGIN DESCRIPTION:
This cross section corresponds to cross section 221418.5 of the non-georeferenced CDC model which was the source of this model.
Old West Fork oxbow channel in LOB.
Effective flow limit set at sta 2911.76 in LOB for flood events up to 50-year due to upstream left bank levee.  Effective flow limit set at IH 30 in ROB.
END DESCRIPTION:
XS GIS Cut Line= 3
  2336975.244453 6961268.9011834 2337425.9758581 6959823.9823764
2337678.321309366957533.35614034
#Sta/Elev= 30
       0  549.98  369.68  545.63  586.18  539.81  596.49  534.97  619.44     534
  664.24  532.19  695.71  525.19  731.95  526.25  744.04  519.67  813.43     514
 1164.06  511.64 1346.85  514.43 1539.77  511.71 1666.54  504.73 1681.76  494.74
 1691.69     494 1830.76     494 1926.18  504.63 1950.72  510.28 1973.49  510.44
 2616.37  516.61 2927.08     516 3016.09  483.78 3032.21  480.69 3213.24     484
 3229.95   486.1 3324.59  515.18 3726.45  515.47 3778.41     528 3818.07     530
#Mann= 7 ,-1,0
       0      .1       0  619.44     .15       0 1666.54     .06       0
 1926.18     .15       0 1973.49    .045       0 2927.08    .035       0
 3324.59     .06       0
Levee=-1,2911.76,516.5,0,,,Levee 2,
#XS Ineff= 2 , 0
       0 2911.76   517.5 3812.73       0     540
Permanent Ineff=
       F       T
Bank Sta=2927.08,3324.59
XS Rating Curve= 0 ,0
Exp/Cntr=0.3,0.1

Type RM Length L Ch R = 1 ,221096  ,249,249,240
BEGIN DESCRIPTION:
This cross section corresponds to cross section 220974.4 of the non-georeferenced CDC model which was the source of this model.
Old West Fork oxbow channel in LOB.
Effective flow limit set at sta 1700 in LOB for flood events up to 50-year due to upstream left bank levee.  Effective flow limit set at IH 30 in ROB.
END DESCRIPTION:
XS GIS Cut Line= 3
 2337383.6924799 6961436.7445428 2337824.6187451  6960405.084355
2338121.892610446957507.46885995
#Sta/Elev= 30
       0  552.93  144.31  548.03  166.04  535.34  186.54  534.02  196.16  541.53
  266.12  539.14  492.47  538.28  529.82  515.03  861.34  504.97  886.43  498.81
  895.66     494  937.04     494  942.25  497.08  1016.6     504 1123.68  514.14
 1664.99  515.97 1932.84   515.2 1948.17  512.75 2182.85  508.56 2406.23  514.51
 3050.71  514.99 3061.39  513.74 3143.16  486.47  3184.1  482.13 3357.33     485
 3449.56  513.85 3468.07  511.98 3884.61  516.07    3926     526 4034.76  528.13
#Mann= 7 ,-1,0
       0      .1       0  266.12     .15       0  861.34     .06       0
  1016.6     .15       0 1664.99    .045       0 3050.71    .035       0
 3449.56     .06       0
#XS Ineff= 3 ,-1
       0    1700     517    1700 3050.71  514.99    4000 4034.76     540
Permanent Ineff=
       F       F       T
Bank Sta=3050.71,3449.56
XS Rating Curve= 0 ,0
Exp/Cntr=0.3,0.1

Type RM Length L Ch R = 1 ,220847  ,223,223,217
BEGIN DESCRIPTION:
This cross section corresponds to cross section 220725.2 of the non-georeferenced CDC model which was the source of this model.
Old West Fork oxbow channel in LOB.
Effective flow limit set at IH 30 in ROB.
END DESCRIPTION:
XS GIS Cut Line= 3
 2337745.5306034 6961711.9139657 2338042.0377274 6960887.9934983
2338357.832399566957599.53291158
#Sta/Elev= 30
       0  551.58  280.83  547.07  370.15  544.62  397.25  528.42  410.86  526.29
     508  523.79  515.34   531.2  652.96  526.19  697.28  518.69  713.54     510
  734.71     494  833.64     494  858.42  502.61  869.53     510  876.26  514.41
  928.59     514 2159.94  515.67 2526.68  511.86 2627.81  506.09  2817.8  514.02
 3232.57  513.84 3258.76  511.42 3331.43  488.16 3389.39  482.86 3551.28   484.6
 3652.04  514.19 4069.55  515.41 4099.19  516.71  4135.2     526 4179.24     528
#Mann= 7 ,-1,0
       0      .1       0  280.83     .15       0  713.54     .06       0
  869.53     .15       0  928.59    .045       0 3232.57    .035       0
 3652.04     .06       0
#XS Ineff= 2 , 0
       0 3182.81  515.13    4210       0     540
Permanent Ineff=
       F       T
Bank Sta=3232.57,3652.04
XS Rating Curve= 0 ,0
Exp/Cntr=0.3,0.1

Type RM Length L Ch R = 1 ,220623  ,263,263,273
BEGIN DESCRIPTION:
This cross section corresponds to cross section 220501.9 of the non-georeferenced CDC model which was the source of this model.
Old West Fork oxbow channel in LOB.
Effective flow limit set at IH 30 in ROB.
END DESCRIPTION:
XS GIS Cut Line= 5
 2338132.8086802 6961656.5885262 2338293.8914387 6960913.0599658
 2338483.8307496 6958565.8919668 2338533.9909085 6958149.4933953
2338563.964947686957620.33780486
#Sta/Elev= 30
       0   547.2  134.89  546.65  156.12  560.05  193.92  557.94  205.24  551.64
  212.51  543.85   258.5  547.09  289.84  543.66  306.25  534.24   337.2  527.41
  521.62  508.11  549.39  496.85  608.97  493.96  664.44     494  680.83  508.07
  721.48  510.41 1021.24   507.5 1302.46  513.59 1656.29  511.07 2051.33  515.89
 2301.56  514.94  2352.4  507.29  2606.7  513.56 3127.91     512 3227.26  485.42
 3269.12  483.24  3438.7  485.77 3529.28  513.61 3956.26  515.17 4065.03  528.83
#Mann= 7 ,-1,0
       0      .1       0  205.24     .15       0  521.62     .06       0
  680.83     .15       0  721.48    .045       0 3127.91    .035       0
 3529.28     .06       0
#XS Ineff= 2 , 0
       0  3008.3   515.2    4095       0     540
Permanent Ineff=
       F       T
Bank Sta=3127.91,3529.28
XS Rating Curve= 0 ,0
Exp/Cntr=0.3,0.1

Type RM Length L Ch R = 1 ,220360  ,340,340,312
BEGIN DESCRIPTION:
This cross section corresponds to cross section 220239.1 of the non-georeferenced CDC model which was the source of this model.
Upstream of Sycamore Creek (right bank tributary).
Old West Fork oxbow channel in LOB.
Effective flow limit set at IH 30 in ROB.
END DESCRIPTION:
XS GIS Cut Line= 4
  2338454.747461 6961973.7583284 2338738.9602734 6958608.3657827
 2338796.2265175 6958203.2420527 2338831.21113866957528.61673981
#Sta/Elev= 30
       0  543.83   66.26  541.74   77.65  547.87   197.7  548.73  221.52  547.78
   253.7  536.61  485.69   533.1  754.05     522  811.96  518.64  831.08  502.75
  838.75  496.26  888.16     492  910.57     492  956.31  502.24  985.25  507.52
 2194.11  511.26 2440.19  516.35 2492.16  505.83 2618.56  513.94 3399.83  512.43
  3486.3  484.43 3624.18     484 3694.31   486.5 3786.38  513.78 4213.62  513.98
 4257.35  515.56 4293.91  526.13 4345.54  530.49 4426.03     530 4462.05  524.28
#Mann= 6 ,-1,0
       0     .09       0  831.08    .055       0  956.31     .15       0
  985.25    .045       0 3399.83    .035       0 3786.38     .06       0
#XS Ineff= 2 , 0
       0 3242.84  515.78 4345.44       0     540
Permanent Ineff=
       F       T
Bank Sta=3399.83,3786.38
XS Rating Curve= 0 ,0
Exp/Cntr=0.3,0.1