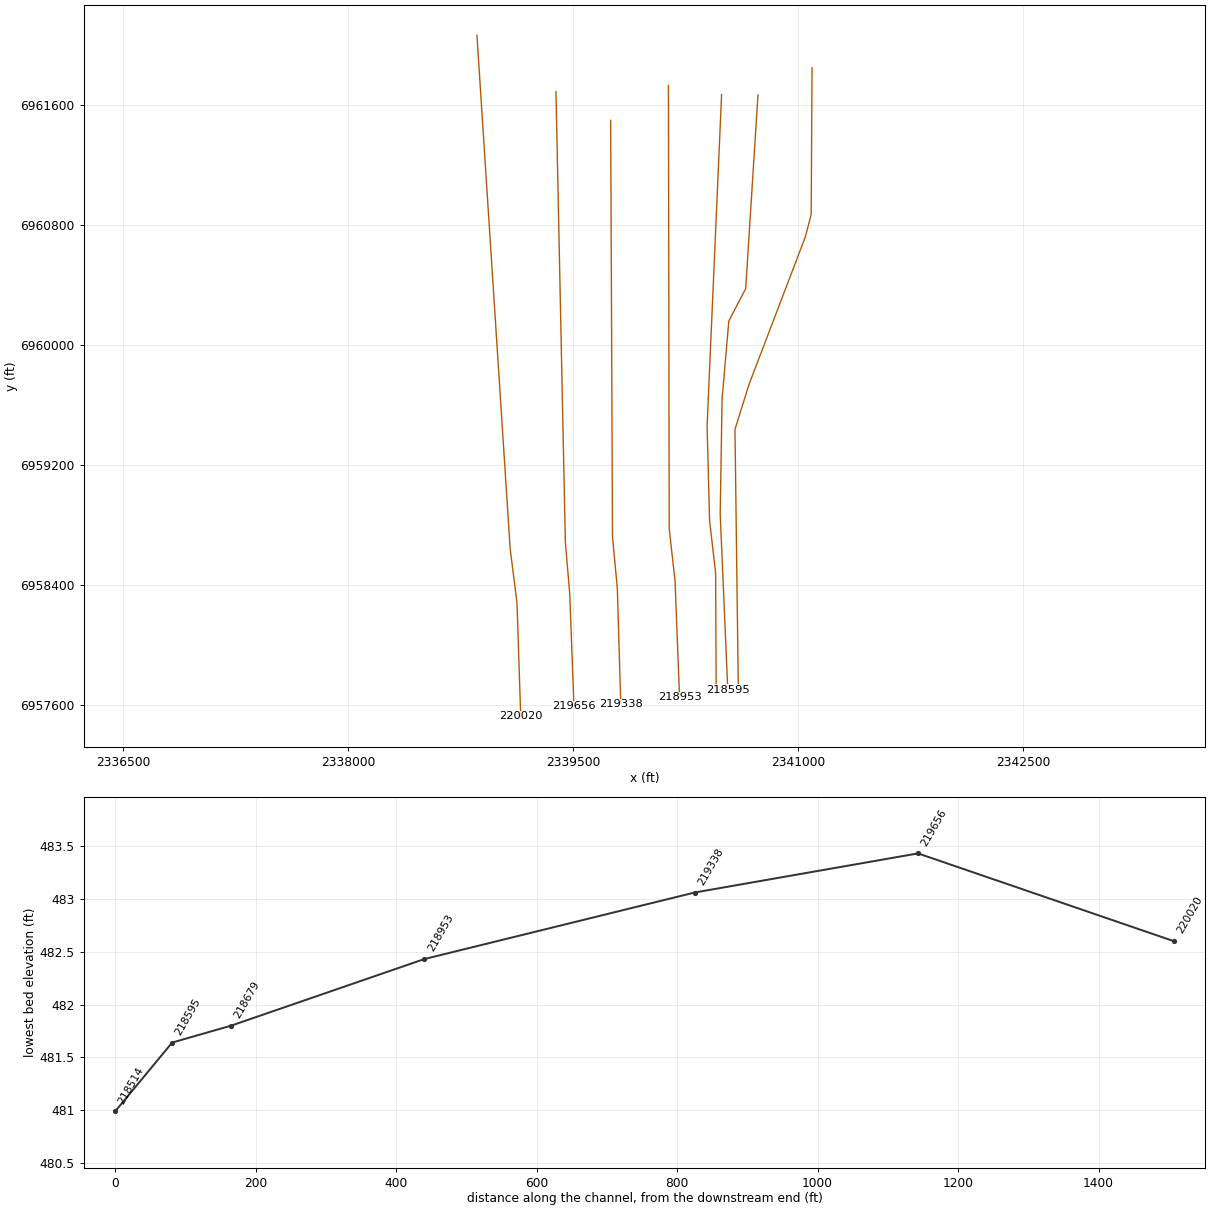
HEC-RAS study CDC_Consolidated_Model.prj: Upper Trinity CDC Consolidated Model

--- CDC_Consolidated_Model.g03 (geometry) --- (continued)

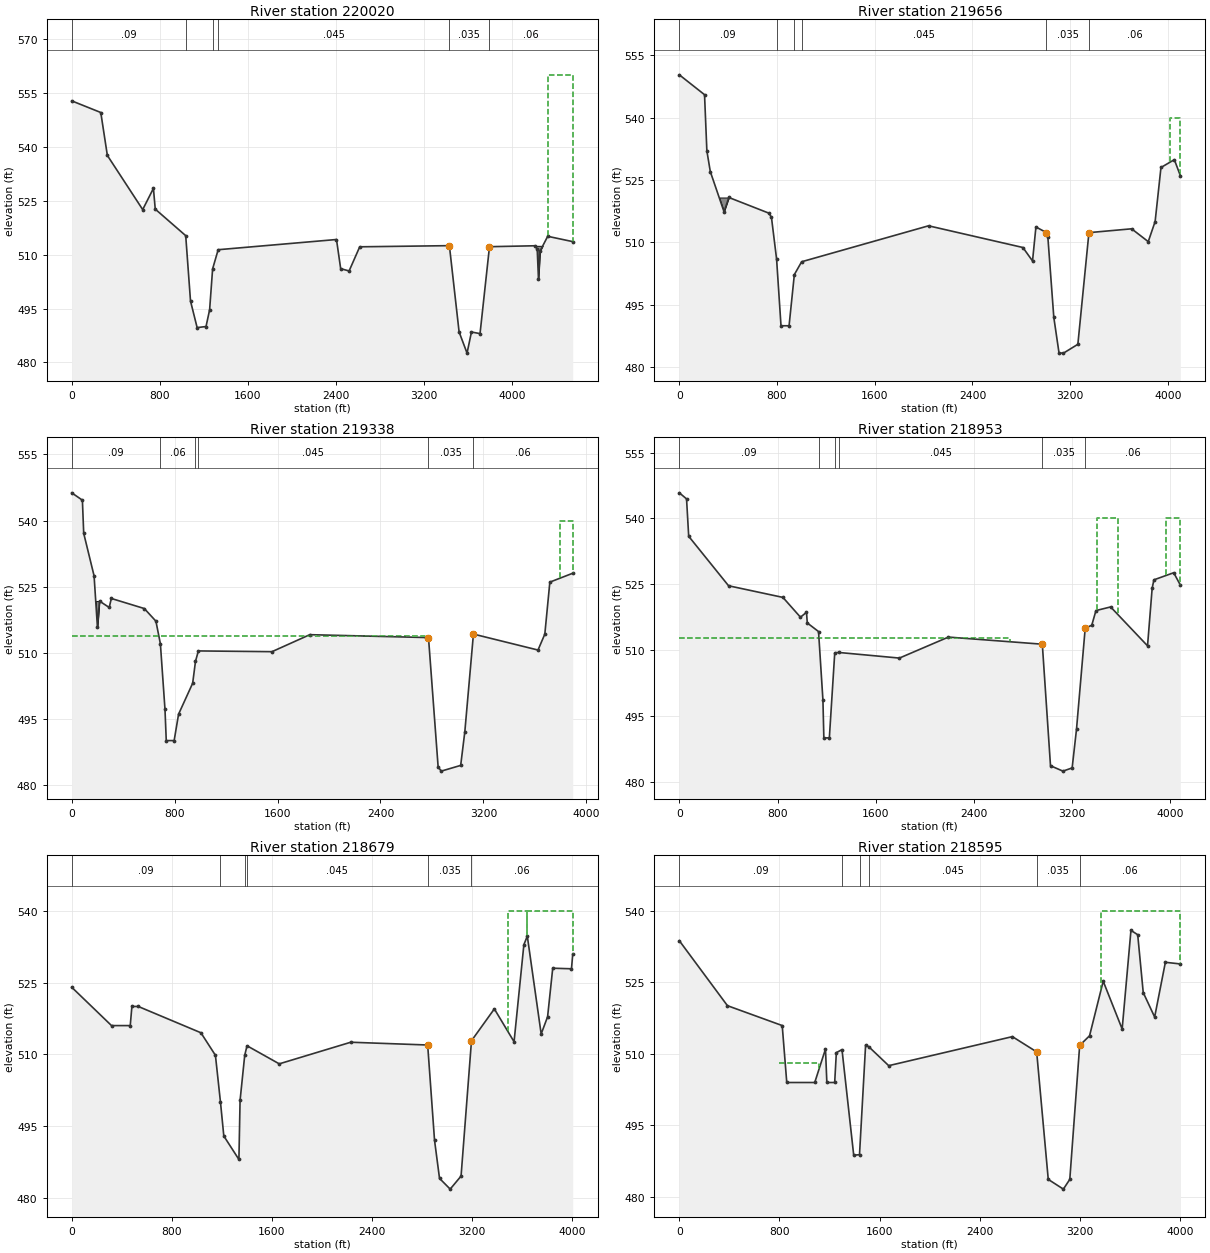
Type RM Length L Ch R = 1 ,220020  ,364,364,316
BEGIN DESCRIPTION:
This cross section corresponds to cross section 219898.8 of the non-georeferenced CDC model which was the source of this model.
Downstream of Sycamore Creek (right bank tributary).
Old West Fork oxbow channel in LOB.
Effective flow limit set at IH 30 in ROB.
Flooding flows behind the bridge through the road fill opening at the XS limit
END DESCRIPTION:
XS GIS Cut Line= 4
 2338858.6612831 6962067.8367254 2339080.2656155 6958643.6094502
 2339125.8056199 6958282.3989024 2339150.5776804 6957525.9882535
#Sta/Elev= 30
       0  552.76  264.14  549.52  323.86  537.58  644.96  522.52  742.41  528.42
  758.95  522.65 1035.78  515.27 1079.34  497.09 1139.47   489.7 1220.36     490
 1253.01  494.66 1280.19  506.03 1330.63  511.36 2405.68   514.2 2443.79  506.09
 2520.34  505.45 2616.83  512.17 3431.51  512.49 3519.75  488.49 3591.96   482.6
 3631.97  488.47 3709.96  488.03 3795.23  512.04 3795.69   512.2    4211  512.46
 4229.58  511.44 4240.99   503.2 4255.12  510.97 4324.83  515.09 4552.28  513.61
#Mann= 6 ,-1,0
       0     .09       0 1035.78     .06       0 1280.19     .15       0
 1330.63    .045       0 3431.51    .035       0 3795.69     .06       0
#XS Ineff= 3 ,-1
    4330 4552.28     560       0 3431.51  512.49 3795.23    4330  512.04
Permanent Ineff=
       T       F       F
#Block Obstruct= 1 ,-1
    4211    4350  512.45
Bank Sta=3431.51,3795.23
XS Rating Curve= 0 ,0
Exp/Cntr=0.3,0.1

Type RM Length L Ch R = 1 ,219656  ,318,318,304
BEGIN DESCRIPTION:
This cross section corresponds to cross section 219535.1 of the non-georeferenced CDC model which was the source of this model.
Old West Fork oxbow channel in LOB.
Effective flow limit set at IH 30 in ROB.
END DESCRIPTION:
XS GIS Cut Line= 4
 2339385.5516684 6961692.9339837 2339448.2301527 6958688.2136007
 2339477.6000701 6958341.2126305 2339505.5307508 6957593.1686628
#Sta/Elev= 30
       0  550.25   206.3  545.48  225.39  531.99  253.53  527.02  365.91  517.38
  405.65   520.8  733.82  517.03  754.38     516  796.26     506  832.37     490
  898.41     490  941.55  502.28 1001.34  505.37 2040.29     514 2813.01  508.79
  2891.7  505.56 2919.57  513.72 3005.26  512.38 3017.11  511.36 3066.05     492
  3108.7  483.47 3145.13  483.43 3262.91  485.55 3353.53  512.36 3703.03  513.28
 3839.18   510.2 3895.56  515.03 3943.35     528 4052.87  529.88 4102.18  526.03
#Mann= 6 ,-1,0
       0     .09       0  796.26     .06       0  941.55     .15       0
 1001.34    .045       0 3005.26    .035       0 3353.53     .06       0
#XS Ineff= 2 ,-1
    4015 4102.18     540       0 3005.26  512.38
Permanent Ineff=
       T       F
#Block Obstruct= 1 ,-1
     300  405.65   520.8
Bank Sta=3005.26,3353.53
XS Rating Curve= 0 ,0
Exp/Cntr=0.3,0.1

Type RM Length L Ch R = 1 ,219338  ,385,385,392
BEGIN DESCRIPTION:
This cross section corresponds to cross section 219217.1 of the non-georeferenced CDC model which was the source of this model.
Old West Fork oxbow channel in LOB.
Effective flow limit set at IH 30 in ROB.
END DESCRIPTION:
XS GIS Cut Line= 4
 2339750.3219351 6961500.4163105 2339762.5861708 6958723.3090924
 2339794.8438954 6958378.6469142 2339817.8154193 6957607.9223295
#Sta/Elev= 30
       0  546.29      83  544.62   93.23  537.09   173.8  527.43  200.01  515.72
  215.98  521.69  291.68  520.24  307.78  522.29  564.21     520  654.48  517.13
  689.22     512  724.96   497.1  734.87     490  796.19     490  830.56     496
  940.17  503.03  962.03     508   984.5  510.37 1556.72   510.2 1850.56  514.06
 2773.18   513.4 2848.12  484.01 2872.19  483.06 3023.33  484.36 3055.51     492
 3122.44   514.2 3624.38  510.57 3677.41  514.19 3716.41     526 3894.37  528.02
#Mann= 6 ,-1,0
       0     .09       0  689.22     .06       0  962.03     .15       0
   984.5    .045       0 2773.18    .035       0 3122.44     .06       0
#XS Ineff= 2 ,-1
    3793 3894.37     540       0 2745.91  513.74
Permanent Ineff=
       T       F
#Block Obstruct= 1 ,-1
     180  215.98  521.69
Bank Sta=2773.18,3122.44
XS Rating Curve= 0 ,0
Exp/Cntr=0.3,0.1

Type RM Length L Ch R = 1 ,218953  ,275,275,278
BEGIN DESCRIPTION:
This cross section corresponds to cross section 218832.1 of the non-georeferenced CDC model which was the source of this model.
Ineffective flow in ROB due to structure.
Old West Fork oxbow channel in LOB.
END DESCRIPTION:
XS GIS Cut Line= 4
 2340135.5893328 6961734.0441416 2340140.7041844 6958777.8354458
 2340179.7789023 6958428.6903993 2340209.6191448 6957654.4895822
#Sta/Elev= 30
       0  545.82   58.75  544.44   76.22  535.92  401.14  524.65  843.91     522
  986.92  517.49 1036.07  518.61 1042.45  516.18 1134.18  514.22 1169.95  498.62
 1177.47     490 1222.27     490 1266.25  509.38 1298.18  509.46 1793.07  508.18
 2192.09  512.96 2957.49  511.34  3024.2  483.66 3125.26  482.43  3200.6  483.16
 3236.17     492 3306.98  515.01 3360.26  515.65 3394.54     519 3514.12  519.83
 3814.82  510.97 3852.51  524.09 3866.72     526 4028.15  527.62 4082.31   524.8
#Mann= 6 ,-1,0
       0     .09       0 1134.18     .06       0 1266.25     .15       0
 1298.18    .045       0 2957.49    .035       0 3306.98     .06       0
#XS Ineff= 3 ,-1
 3399.66 3577.51     540 3968.58 4082.31     540       0 2695.89  512.76
Permanent Ineff=
       F       T       F
Bank Sta=2957.49,3306.98
XS Rating Curve= 0 ,0
Exp/Cntr=0.3,0.1

Type RM Length L Ch R = 1 ,218679  ,84,84,50
BEGIN DESCRIPTION:
This cross section corresponds to cross section 218557.3 of the non-georeferenced CDC model which was the source of this model.
Ineffective flow in ROB due to Beach Street bridge, structure.
Old West Fork oxbow channel in LOB.
END DESCRIPTION:
XS GIS Cut Line= 5
 2340489.9949435  6961672.668904 2340393.3866688 6959464.3117937
 2340409.7360446 6958833.7064004 2340450.2738525 6958480.6670403
  2340453.886334 6957672.4543722
#Sta/Elev= 30
       0  524.02  318.15     516  467.82     516  481.06     520  532.09     520
 1032.66   514.5 1148.67  509.79 1189.06     500 1215.76  492.91 1336.49     488
 1345.74  500.35  1382.8  509.77  1401.3  511.78 1658.91     508 2230.49  512.52
 2845.33  511.94 2900.19     492    2940  484.05 3025.22   481.8 3112.21  484.53
  3195.5  512.83 3378.18  519.49 3535.84  512.62 3614.28  532.92 3641.74  534.71
  3752.5  514.25 3803.83  517.84 3844.93     528 3994.79  527.88 4004.87  530.95
#Mann= 6 ,-1,0
       0     .09       0 1189.06     .06       0  1382.8     .15       0
  1401.3    .045       0 2845.33    .035       0  3195.5     .06       0
#XS Ineff= 3 ,-1
 3487.27 3641.74     540 3641.74 4004.87     540       0 2845.33  511.94
Permanent Ineff=
       F       T       F
Bank Sta=2845.33,3195.5
XS Rating Curve= 0 ,0
Exp/Cntr=0.3,0.1

Type RM Length L Ch R = 1 ,218595  ,81,81,28
BEGIN DESCRIPTION:
This cross section corresponds to cross section 218473.3 of the non-georeferenced CDC model which was the source of this model.
Ineffective flow in ROB due to Beach Street bridge.
Old West Fork oxbow channel in LOB.
END DESCRIPTION:
XS GIS Cut Line= 6
  2340732.605753 6961670.2536259 2340650.7224949 6960379.0185112
 2340538.0875123 6960161.6902751 2340493.2548107 6959642.0695777
 2340480.6574063 6958876.1467697 2340531.2360354 6957704.9890028
#Sta/Elev= 30
       0  533.73  384.22  520.11  821.79  515.94  858.07     504 1081.52     504
 1167.41  511.01 1178.25     504  1240.9     504 1254.13  510.26 1299.24   510.9
 1392.85  488.76 1439.18  488.86 1487.96  511.88 1514.82  511.46  1672.5  507.53
 2660.32  513.62 2854.29  510.42  2946.9  483.68 3067.58  481.64 3118.96  483.69
 3197.85  511.77 3276.79   513.8 3385.79  525.24 3537.21  515.22 3607.49   535.9
 3661.42  534.99 3705.57  522.86 3796.78  517.73  3882.4  529.21 4002.17  528.86
#Mann= 6 ,-1,0
       0     .09       0 1299.24     .06       0 1439.18     .15       0
 1514.82    .045       0 2854.29    .035       0 3197.85     .06       0
#XS Ineff= 3 ,-1
 3365.72 4002.17     540 1299.24    1500   510.9     800 1115.21     508
Permanent Ineff=
       F       F       T
Bank Sta=2854.29,3197.85
XS Rating Curve= 0 ,0
Exp/Cntr=0.3,0.1

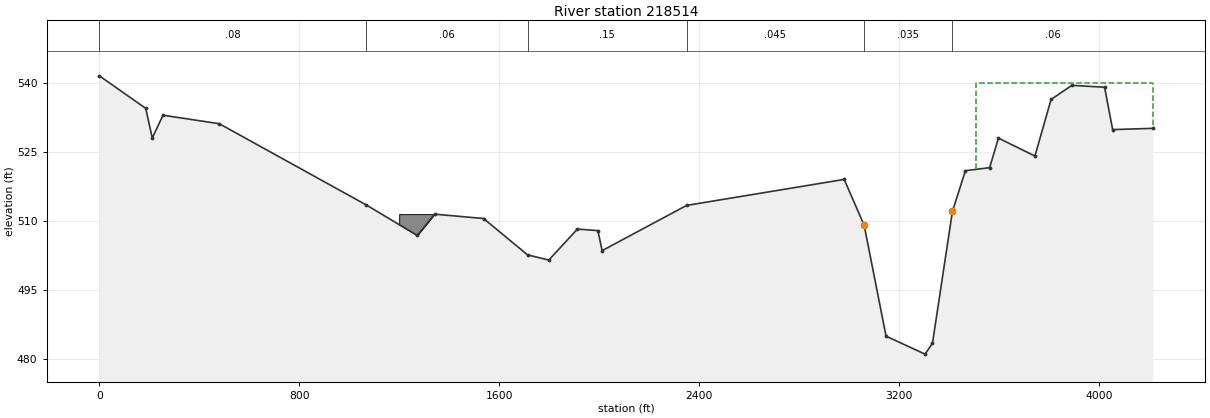
Type RM Length L Ch R = 1 ,218514  ,29,29,29
BEGIN DESCRIPTION:
This cross section corresponds to cross section 218392.7 of the non-georeferenced CDC model which was the source of this model.
Ineffective flow in ROB due to Beach Street bridge.
Old West Fork oxbow channel in LOB.
END DESCRIPTION:
XS GIS Cut Line= 6
 2341092.9657485 6961850.6693696 2341087.4665214 6960872.9194972
  2341047.633942  6960721.470109 2340672.5088718 6959738.7485049
 2340579.2108933 6959439.9268311 2340601.3653113 6957723.4200992
#Sta/Elev= 30
       0  541.55  185.69  534.47  211.84  528.02  254.82  532.98  480.08  531.13
 1068.74  513.44 1272.46  506.82 1341.57  511.45 1537.77   510.5 1713.78  502.59
 1798.89  501.46  1913.3   508.2 1995.25  507.87  2012.3  503.51 2350.39  513.35
 2981.05  519.01 3061.08  509.01 3148.61   484.9 3304.61  480.99 3334.44  483.37
 3414.23  512.04  3466.3  520.91 3563.24  521.57 3598.36     528 3744.46   524.1
 3809.02  536.41 3892.28  539.48 4023.19  539.07 4055.53  529.85 4215.95  530.12
#Mann= 6 ,-1,0
       0     .08       0 1068.74     .06       0 1713.78     .15       0
 2350.39    .045       0 3061.08    .035       0 3414.23     .06       0
#XS Ineff= 1 ,-1
 3508.33 4215.95     540
Permanent Ineff=
       F
#Block Obstruct= 1 ,-1
    1200 1341.57  511.45
Bank Sta=3061.08,3414.23
XS Rating Curve= 0 ,0
Exp/Cntr=0.5,0.3