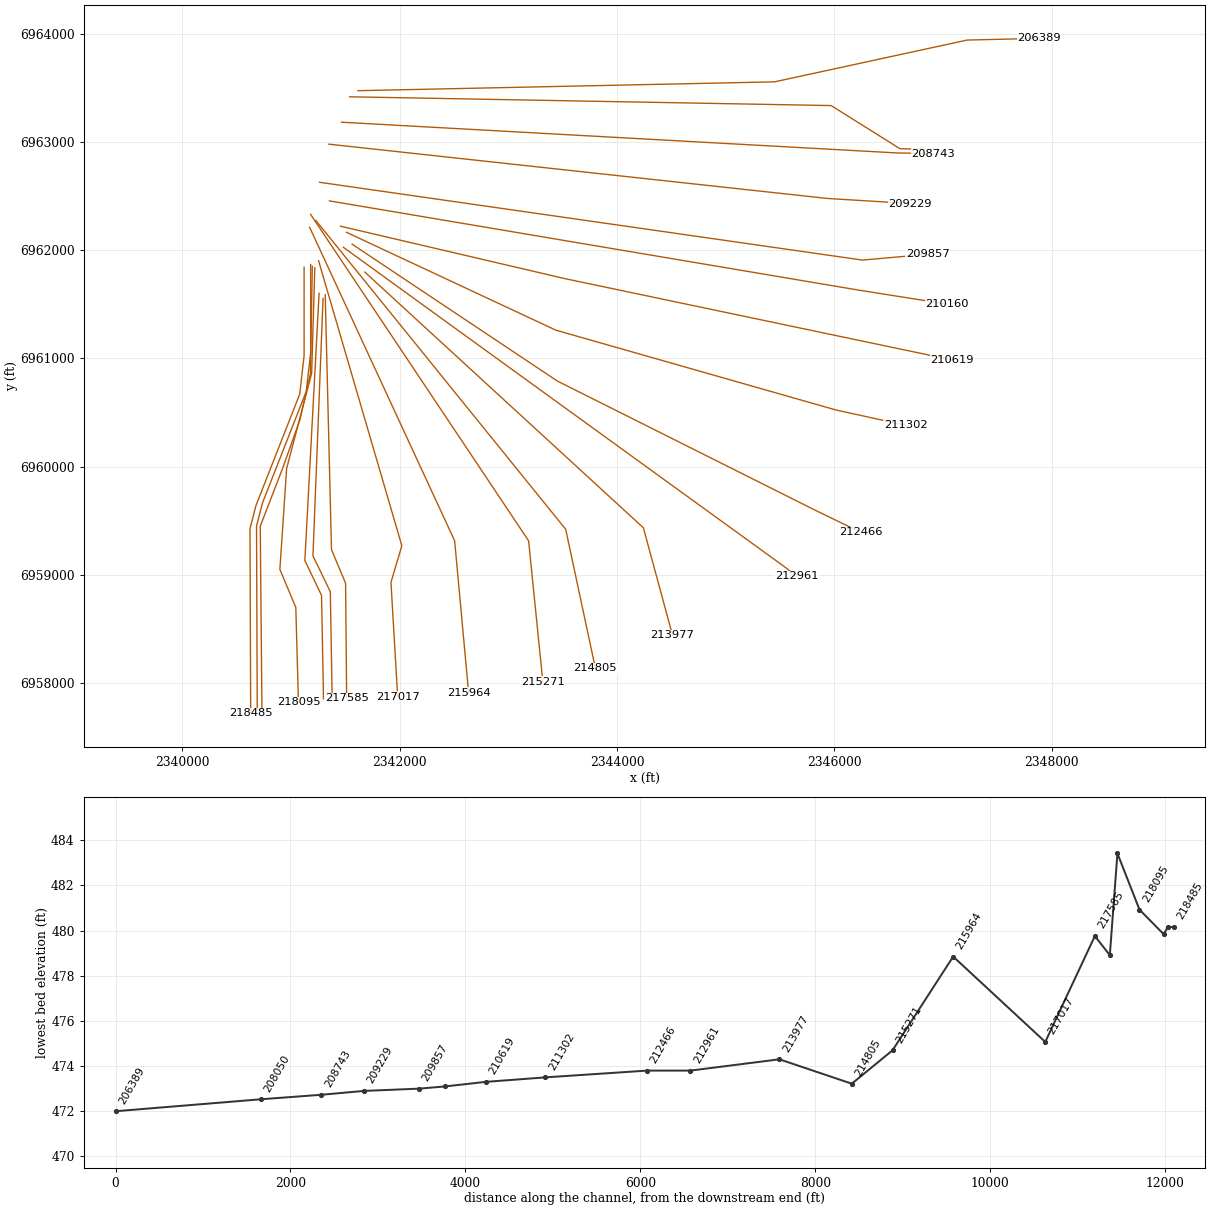
HEC-RAS study CDC_Consolidated_Model.prj: Upper Trinity CDC Consolidated Model

--- CDC_Consolidated_Model.g03 (geometry) --- (continued)

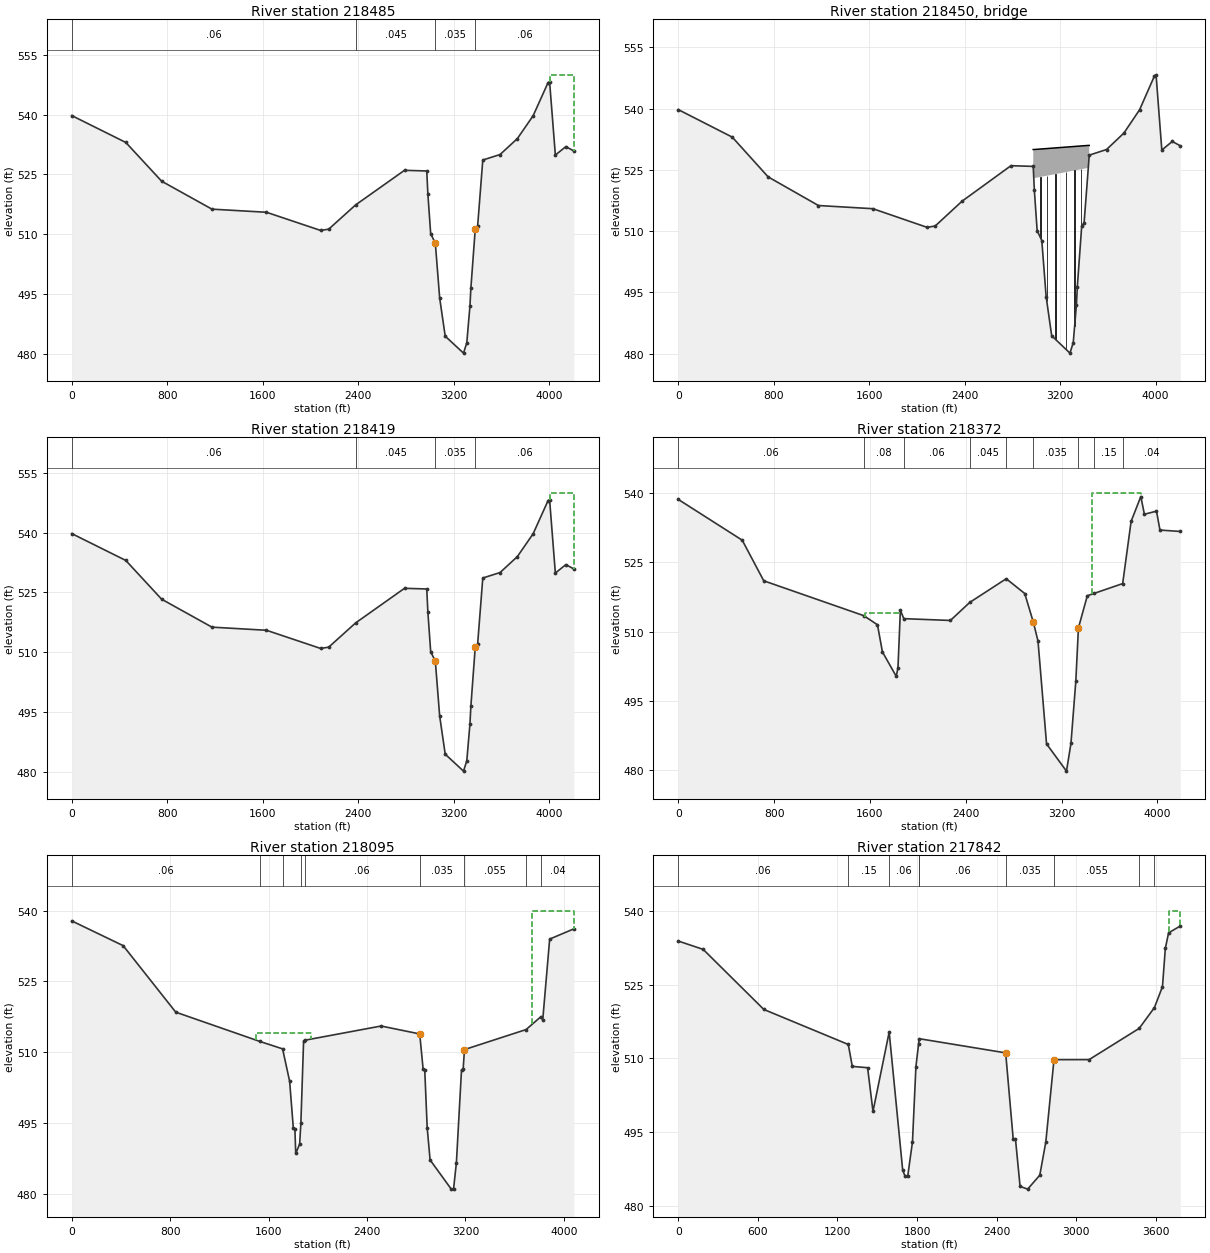
Type RM Length L Ch R = 1 ,218485  ,67,67,67
BEGIN DESCRIPTION:
This cross section corresponds to cross section 218363 of the non-georeferenced CDC model which was the source of this model.
Upstream of Beach Street.
Cross-section generated from points along centrline of Beach Street roadway.
END DESCRIPTION:
XS GIS Cut Line= 6
 2341119.7027942 6961840.9813563 2341119.7027942 6961023.9586464
 2341079.1867654 6960668.8476774 2340676.4099947  6959639.264284
 2340621.5941605 6959424.7678517 2340628.1243955 6957719.9684324
#Sta/Elev= 30
       0  539.77  452.84  533.03  753.35   523.3 1174.86  516.29 1631.55  515.51
 2085.21  510.95 2153.25  511.27 2378.08  517.34 2788.35  526.04 2974.77  525.87
 2984.44     520 3007.66  510.17  3046.8  507.71 3083.02     494 3129.59  484.41
 3282.84  480.16 3310.34  482.75 3336.86     492 3344.51  496.43 3381.33  511.33
 3401.09     512 3444.44  528.62 3589.31     530 3734.17     534 3866.32  539.73
 3990.67     548 4004.26  548.28 4052.54  529.87 4140.35  531.98  4207.5   530.9
#Mann= 4 ,-1,0
       0     .06       0 2378.08    .045       0  3046.8    .035       0
 3381.33     .06       0
#XS Ineff= 2 , 0
       0                 4004.26       0     550
Permanent Ineff=
       F       T
Bank Sta=3046.8,3381.33
XS Rating Curve= 0 ,0
Exp/Cntr=0.5,0.3

Type RM Length L Ch R = 3 ,218450  ,,,
BEGIN DESCRIPTION:
Beach Street
Data from bridge plans, USACE 1975 survey.
Length of bridge 452 feet, minimum low chord elev. 523.  Culvert located at old West Fork oxbow channel not represented due to small size and insignificant impact on flows.
USGS gaging station 08048543 -  Beach Street Gage -   located on downstream side of bridge.  Gage datum elev. 478.70 MSL
END DESCRIPTION:
Node Name=Beach Street
Bridge Culvert--1,0,-1,-1, 0
Deck Dist Width WeirC Skew NumUp NumDn MinLoCord MaxHiCord MaxSubmerge Is_Ogee
1.1,63,2.6,0, 6, 6, , , 0.95, 0, 0,0,,
 2974.77 2974.77 2983.61 3435.61 3435.61 3444.44
     530     530     530     531     531     531
     450     450     523   525.5     450     450
 2974.77 2974.77 2983.61 3435.61 3435.61 3444.44
     530     530     530     531     531     531
     450     450     523   525.5     450     450
Pier Skew, UpSta & Num, DnSta & Num=  ,3036.61, 2 ,3036.61, 2 , 0 , 0 , 0 ,,
       3       3
     450     528
       3       3
     450     528
Pier Skew, UpSta & Num, DnSta & Num=  ,3088.61, 2 ,3088.61, 2 , 0 , 0 , 0 ,,
       3       3
     450     528
       3       3
     450     528
Pier Skew, UpSta & Num, DnSta & Num=  ,3161.61, 2 ,3161.61, 2 , 0 , 0 , 0 ,,
       3       3
     450     528
       3       3
     450     528
Pier Skew, UpSta & Num, DnSta & Num=  ,3251.61, 2 ,3251.61, 2 , 0 , 0 , 0 ,,
       3       3
     450     528
       3       3
     450     528
Pier Skew, UpSta & Num, DnSta & Num=  ,3321.61, 2 ,3321.61, 2 , 0 , 0 , 0 ,,
       3       3
     450     528
       3       3
     450     528
Pier Skew, UpSta & Num, DnSta & Num=  ,3377.61, 2 ,3377.61, 2 , 0 , 0 , 0 ,,
       3       3
     450     528
       3       3
     450     528
BR Coef=-1 , 0 , 0 ,, 0 ,,,0.8,-1,,0,
WSPro=,,,, 1 ,,,, 0 ,,,, 0 ,,,,-1 ,-1 ,-1 , 0 , 0 , 0 , 0 , 0
BC Design=,, 0 ,, 0 ,,,,,,
BC Use User HTab Curves=0
BC User HTab FreeFlow(D)= 0

Type RM Length L Ch R = 1 ,218419  ,47,47,47
BEGIN DESCRIPTION:
This cross section corresponds to cross section 218297 of the non-georeferenced CDC model which was the source of this model.
Downstream of Beach Street.
Cross-section generated from points along centrline of Beach Street roadway.
END DESCRIPTION:
XS GIS Cut Line= 6
 2341180.0614337 6961866.2868327 2341180.0614337 6961049.2641229
  2341139.545405 6960694.1531539 2340736.7686342 6959664.5697604
 2340681.9528001 6959450.0733282  2340688.483035 6957745.2739089
#Sta/Elev= 30
       0  539.77  452.84  533.03  753.35   523.3 1174.86  516.29 1631.55  515.51
 2085.21  510.95 2153.25  511.27 2378.08  517.34 2788.35  526.04 2974.77  525.87
 2984.44     520 3007.66  510.17  3046.8  507.71 3083.02     494 3129.59  484.41
 3282.84  480.16 3310.34  482.75 3336.86     492 3344.51  496.43 3381.33  511.33
 3401.09     512 3444.44  528.62 3589.31     530 3734.17     534 3866.32  539.73
 3990.67     548 4004.26  548.28 4052.54  529.87 4140.35  531.98  4207.5   530.9
#Mann= 4 ,-1,0
       0     .06       0 2378.08    .045       0  3046.8    .035       0
 3381.33     .06       0
#XS Ineff= 2 , 0
       0                 4004.26       0     550
Permanent Ineff=
       F       T
Bank Sta=3046.8,3381.33
XS Rating Curve= 0 ,0
Exp/Cntr=0.5,0.3

Type RM Length L Ch R = 1 ,218372  ,277,277,738
BEGIN DESCRIPTION:
This cross section corresponds to cross section 218250.3 of the non-georeferenced CDC model which was the source of this model.
Ineffective flow in ROB due to Beach Street bridge.
Old West Fork oxbow channel in LOB.
END DESCRIPTION:
XS GIS Cut Line= 6
 2341195.0499155 6961849.8119465 2341178.0685564 6960859.5104318
 2341080.4784064 6960430.1140054 2340924.6108391 6959990.4702451
 2340716.1789835 6959448.9070871   2340731.84128 6957736.5101265
#Sta/Elev= 30
       0  538.58  534.11  529.76  713.89  520.98 1547.19  513.46  1662.9  511.48
 1704.17  505.62 1819.71  500.33 1834.07  502.17 1854.08  514.62 1882.86   512.8
 2271.59  512.41  2433.1  516.31 2737.76  521.43 2892.22  518.23 2964.27     512
 3002.85  507.96 3074.18  485.73 3240.54  479.84 3277.97  485.84 3318.45  499.28
 3340.32   510.8 3414.46  517.75 3473.64  518.28 3709.57  520.38    3780  533.83
 3861.05  539.19 3890.95  535.37  3991.9  536.04 4020.72  531.95 4190.66  531.65
#Mann= 9 ,-1,0
       0     .06       0 1547.19     .08       0 1882.86     .06       0
  2433.1    .045       0 2737.76     .06       0 2964.27    .035       0
 3340.32    .045       0 3473.64     .15       0 3709.57     .04       0
#XS Ineff= 2 ,-1
 1560.34 1854.08     514 3454.52 3861.05     540
Permanent Ineff=
       T       F
Bank Sta=2964.27,3340.32
XS Rating Curve= 0 ,0
Exp/Cntr=0.5,0.3

Type RM Length L Ch R = 1 ,218095  ,252,252,285
BEGIN DESCRIPTION:
This cross section corresponds to cross section 217973.4 of the non-georeferenced CDC model which was the source of this model.
Ineffective flow in ROB due to Beach Street bridge.
Old West Fork oxbow channel in LOB.
END DESCRIPTION:
XS GIS Cut Line= 6
 2341218.3135129 6961837.0169744 2341189.2341134 6960861.1097709
 2340958.6530253 6959981.2964402 2340896.7913874 6959049.5344701
 2341043.3721059 6958699.2899671 2341067.7385303 6957822.2231386
#Sta/Elev= 30
       0  537.86  417.64  532.61  845.23  518.49 1528.41  512.28 1713.74   510.7
 1770.99  503.81 1801.03  493.85  1813.7  493.68 1820.55   488.5 1852.27  490.49
 1862.25  494.86 1884.37  512.32 1892.04  512.52 2514.27  515.55  2828.4  513.87
 2855.96   506.4 2869.07  506.31 2889.04     494 2912.64  487.13 3084.69  480.93
 3103.35  480.94 3126.56  486.55 3168.08  506.23 3181.27  506.36 3192.24  510.55
 3693.07   514.8 3814.69  517.56 3828.32  516.85 3884.65     534 4081.19  536.17
#Mann= 9 ,-1,0
       0     .06       0 1528.41     .15       0 1713.74     .06       0
 1862.25     .15       0 1892.04     .06       0  2828.4    .035       0
 3192.24    .055       0 3693.07     .15       0 3814.69     .04       0
#XS Ineff= 2 ,-1
 3744.83 4081.19     540    1500 1948.62     514
Permanent Ineff=
       F       T
Bank Sta=2828.4,3192.24
XS Rating Curve= 0 ,0
Exp/Cntr=0.3,0.1

Type RM Length L Ch R = 1 ,217842  ,87,87,109
BEGIN DESCRIPTION:
This cross section corresponds to cross section 217720.9 of the non-georeferenced CDC model which was the source of this model.
Upstream of the Beach Street Dam
Ineffective flow in ROB due to Beach Street bridge.
Old West Fork oxbow channel in LOB.
END DESCRIPTION:
XS GIS Cut Line= 4
 2341257.6650071 6961600.1430178 2341126.6147438 6959132.1683299
 2341280.1151285 6958809.9072701 2341298.2227792 6957854.5305144
#Sta/Elev= 30
       0  533.86  188.05  532.16  645.09  519.95 1281.62  512.83  1311.8  508.38
 1427.22   508.1 1467.76  499.21 1589.73  515.35 1691.57  487.29 1710.11     486
 1729.27     486 1765.33  493.02 1791.31   508.3 1811.38  512.94    1817     514
  2467.7  511.12 2524.69  493.54 2541.44  493.67 2576.27  483.98  2633.5  483.42
 2724.94  486.26 2770.29     493 2831.87  509.74 3096.51  509.75 3474.05   516.1
 3589.08  520.34 3649.51  524.59 3670.99  532.35 3695.51  535.52 3783.95  536.92
#Mann= 9 ,-1,0
       0     .06       0 1281.62     .15       0 1589.73     .06       0
 1811.38     .15       0    1817     .06       0  2467.7    .035       0
 2831.87    .055       0 3474.05     .15       0 3589.08     .04       0
#XS Ineff= 3 ,-1
 3701.37 3783.95     540 1589.73    1817     514       0 1589.73  514.89
Permanent Ineff=
       T       T       F
Bank Sta=2467.7,2831.87
XS Rating Curve= 0 ,0
Exp/Cntr=0.3,0.1

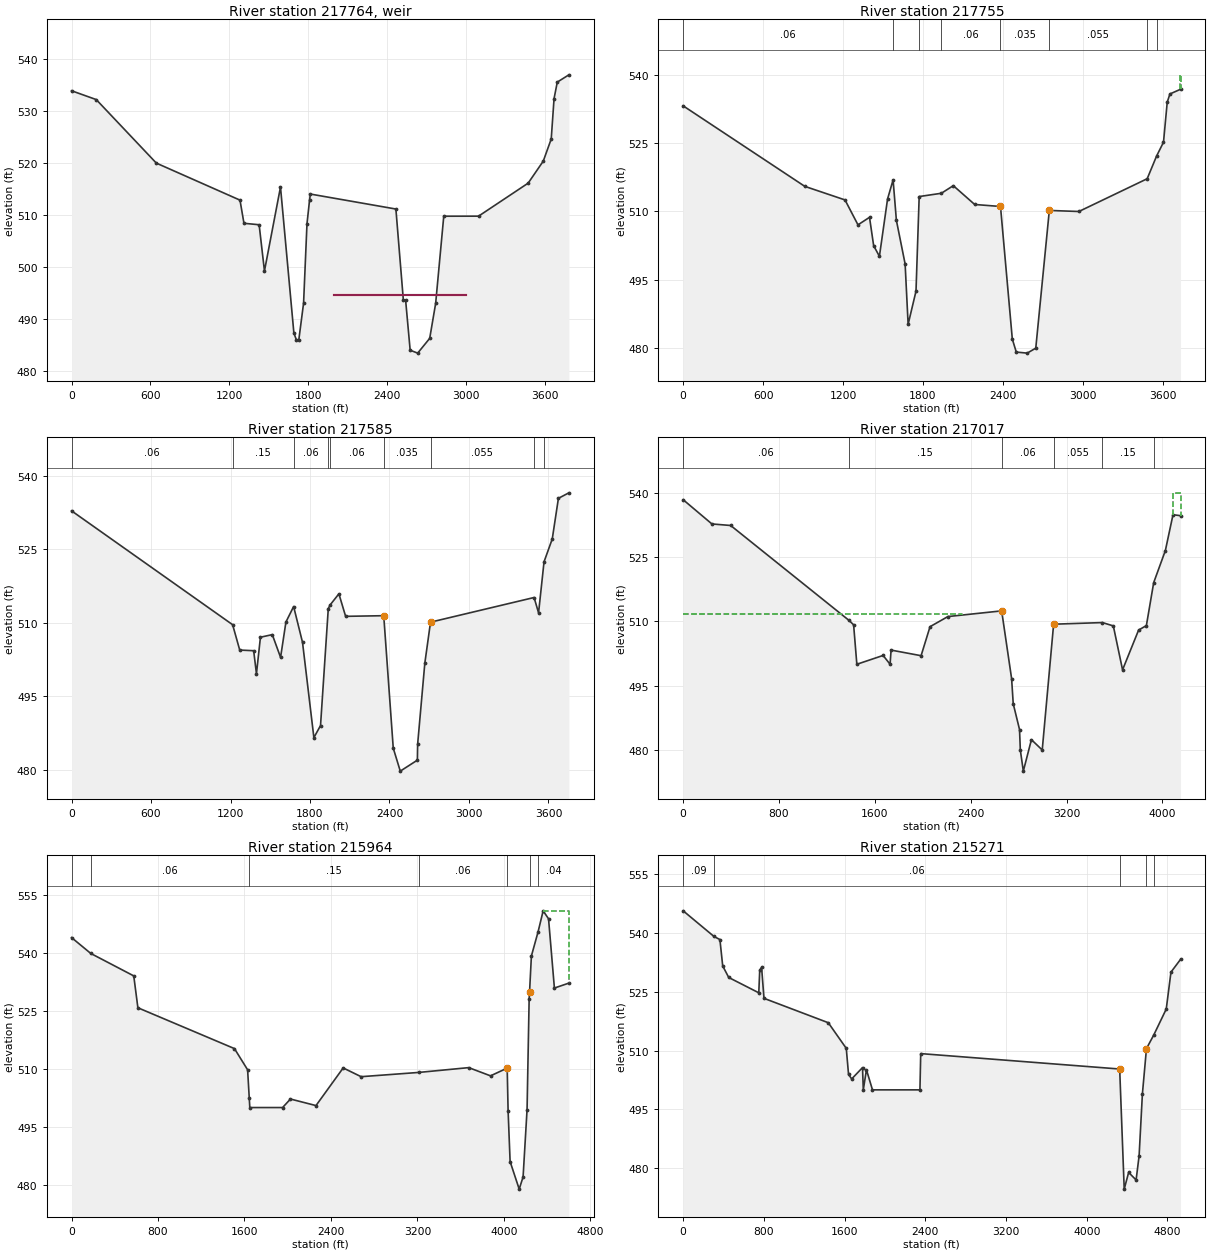
Type RM Length L Ch R = 5 ,217764  ,,,
BEGIN DESCRIPTION:
Beach Street Dam
Constructed by TRWD.  Data from TRWD plans.  Top of dam road surface elevation 494.5
-------------------------------
CDC FW112598-01
-------------------------------
END DESCRIPTION:
Node Name=Beach Street Dam
IW Pilot Flow=0
#Inline Weir SE= 2
    2000   494.5    3000   494.5
IW Dist,WD,Coef,Skew,MaxSub,Min_El,Is_Ogee,SpillHt,DesHd
16.55,17.5,3,0,0.95,, 0 ,,,1.5,3,
Inline Weir Flap Gates= 0
IW Outlet Rating Curve= 0 ,False,,

Type RM Length L Ch R = 1 ,217755  ,171,171,175
BEGIN DESCRIPTION:
This cross section corresponds to cross section 217634.1 of the non-georeferenced CDC model which was the source of this model.
Downstream of the Beach Street Dam
Ineffective flow in ROB due to Beach Street bridge.
Old West Fork oxbow channel in LOB.
END DESCRIPTION:
XS GIS Cut Line= 4
 2341294.1528066 6961553.7038469 2341201.1207148  6959175.256239
 2341360.9047637 6958844.0185531 2341378.1774186 6957857.2271061
#Sta/Elev= 30
       0  533.19  913.08  515.52 1215.29  512.54 1312.67  507.07 1399.25  508.72
 1430.41  502.49 1473.62  500.16 1534.78  512.74 1576.34  516.94 1601.05  508.07
 1666.67  498.49 1689.27  485.24 1748.37  492.51 1772.28  513.28  1938.8     514
 2028.56  515.67 2189.08  511.54 2382.91   511.1 2471.61     482 2501.36  479.14
 2583.39  478.91  2647.8     480 2749.55  510.23 2971.46     510 3484.45  517.19
 3555.02  522.17 3606.94  525.21 3634.96     534 3655.21   535.8 3734.97  536.83
#Mann= 8 ,-1,0
       0     .06       0 1576.34     .06       0 1772.28     .15       0
  1938.8     .06       0 2382.91    .035       0 2749.55    .055       0
 3484.45     .15       0 3555.02     .04       0
#XS Ineff= 3 ,-1
 3732.57 3734.97     540       0 1576.34   515.8 1576.34 1772.28  513.28
Permanent Ineff=
       T       F       T
Bank Sta=2382.91,2749.55
XS Rating Curve= 0 ,0
Exp/Cntr=0.3,0.1

Type RM Length L Ch R = 1 ,217585  ,567,567,542
BEGIN DESCRIPTION:
This cross section corresponds to cross section 217463.3 of the non-georeferenced CDC model which was the source of this model.
Old West Fork oxbow channel in LOB.
END DESCRIPTION:
XS GIS Cut Line= 4
 2341314.0552899 6961586.8746092 2341371.7565978 6959232.7533677
 2341501.4763904 6958921.9498088 2341511.3008464 6957859.0822202
#Sta/Elev= 30
       0  532.85 1216.09  509.62 1269.69  504.45 1374.86  504.32  1395.9  499.62
 1425.96  507.07 1515.48   507.6 1577.98  502.96 1618.42  510.17 1676.54  513.33
 1743.66  506.02 1829.43  486.59 1879.61  489.06 1938.12  512.91 1952.73  513.68
 2018.22  515.92 2069.01  511.33 2356.72  511.46 2428.56  484.45 2481.58  479.76
  2610.7     482 2612.62  485.24 2666.89  501.77  2709.9  510.14 3491.71  515.17
 3525.51  512.04  3566.8  522.45 3628.92  527.12 3675.31   535.4 3754.53  536.52
#Mann= 9 ,-1,0
       0     .06       0 1216.09     .15       0 1676.54     .06       0
 1938.12     .15       0 1952.73     .06       0 2356.72    .035       0
  2709.9    .055       0 3491.71     .15       0  3566.8     .04       0
#XS Ineff= 3 ,-1
       0 1676.54  513.33 1676.54    2000  513.33  2709.9 3754.53  510.14
Permanent Ineff=
       F       T       F
Bank Sta=2356.72,2709.9
XS Rating Curve= 0 ,0
Exp/Cntr=0.3,0.1

Type RM Length L Ch R = 1 ,217017  ,1053,1053,1624
BEGIN DESCRIPTION:
This cross section corresponds to cross section 216896 of the non-georeferenced CDC model which was the source of this model.
Located at the old West Fork oxbow channel/modified West Fork river channel confluence.
Effective flow limit set at IH 30 in ROB.
Channel reach length modified to account for reduced effective length for high flows and to better compute volume.
END DESCRIPTION:
XS GIS Cut Line= 4
 2341253.0913925 6961901.0522459 2342019.2238245 6959268.5181783
 2341919.0967963 6958930.0216941 2341980.7879606 6957875.7279476
#Sta/Elev= 30
       0  538.39  239.69  532.74  396.54  532.38 1384.31  510.23  1422.4  509.21
 1449.35     500 1668.52  502.06 1726.75     500 1735.08  503.31 1985.47     502
 2060.22  508.77 2209.14  511.13 2657.96  512.46 2740.98  496.65 2754.44   490.8
 2807.02  484.78 2813.64     480 2838.72  475.07 2906.29  482.41 2996.48     480
 3091.63  509.35 3499.16  509.73 3589.82  508.95  3666.9   498.7 3800.96  507.99
 3865.66  509.02  3926.7  519.05 4024.03  526.52 4087.84  534.89 4150.84  534.67
#Mann= 6 ,-1,0
       0     .06       0 1384.31     .15       0 2657.96     .06       0
 3091.63    .055       0 3499.16     .15       0  3926.7     .04       0
#XS Ineff= 4 ,-1
 4087.84 4150.84     540 3091.63 4087.84  509.35    2325 2657.96  509.35
       0    2325   511.8
Permanent Ineff=
       T       F       F       F
Bank Sta=2657.96,3091.63
XS Rating Curve= 0 ,0
Exp/Cntr=0.3,0.1

Type RM Length L Ch R = 1 ,215964  ,693,693,867
BEGIN DESCRIPTION:
This cross section corresponds to cross section 215842 of the non-georeferenced CDC model which was the source of this model.
Effective flow limit set at IH 30 in ROB.
END DESCRIPTION:
XS GIS Cut Line= 3
 2341170.3212836 6962210.9598793  2342505.236492 6959314.2812891
 2342633.9740205 6957908.2398916
#Sta/Elev= 30
       0  544.07  178.07  539.95   575.7  534.13  613.81  525.87 1507.33  515.28
 1629.06  509.78 1644.08  502.48  1649.3     500 1952.46     500 2025.34  502.21
 2261.55  500.51  2513.1  510.27 2679.11     508 3210.57   509.1 3674.65  510.35
 3876.17  508.22 4030.44  510.22 4038.86  499.16 4057.44     486 4141.53  478.85
  4177.5     482 4214.31  499.49 4233.61  528.22 4237.44     530 4254.42  539.29
 4316.57  545.59 4363.11     551 4413.05  548.93 4467.18  530.98  4601.4  532.26
#Mann= 7 ,-1,0
       0     .09       0  178.07     .06       0 1644.08     .15       0
 3210.57     .06       0 4030.44    .066       0 4237.44     .15       0
 4316.57     .04       0
#XS Ineff= 2 , 0
       0 4030.44   509.7 4363.11       0     551
Permanent Ineff=
       F       T
Bank Sta=4030.44,4237.44
XS Rating Curve= 0 ,0
Exp/Cntr=0.3,0.1

Type RM Length L Ch R = 1 ,215271  ,466,466,741
BEGIN DESCRIPTION:
This cross section corresponds to cross section 215148.4 of the non-georeferenced CDC model which was the source of this model.
END DESCRIPTION:
XS GIS Cut Line= 3
 2341179.0462832 6962330.4915824 2343185.7814011 6959314.2812891
 2343316.6554869 6958014.2659492
#Sta/Elev= 30
       0  545.63  305.62  539.09  364.06  538.31  391.84  531.58  451.61  528.64
  749.37  524.74  758.73  530.51  777.24  531.22  800.72  523.33 1438.23  517.11
 1616.36  510.58 1639.06  503.92 1670.14  502.79 1777.45  505.68  1785.1     500
 1816.35  505.13 1876.16     500 2346.48     500 2354.31  509.24 4326.11  505.31
 4371.08   474.7 4414.87  478.96 4488.89  477.03 4518.69  483.19 4551.33  498.98
 4591.66  510.52 4664.25     514  4787.7   520.6 4834.38     530 4929.37  533.26
#Mann= 5 ,-1,0
       0     .09       0  305.62     .06       0 4326.11    .066       0
 4591.66     .15       0 4664.25     .04       0
#XS Ineff= 2 , 0
       0 4326.11  505.31               0
Permanent Ineff=
       F       F
Bank Sta=4326.11,4591.66
XS Rating Curve= 0 ,0
Exp/Cntr=0.3,0.1

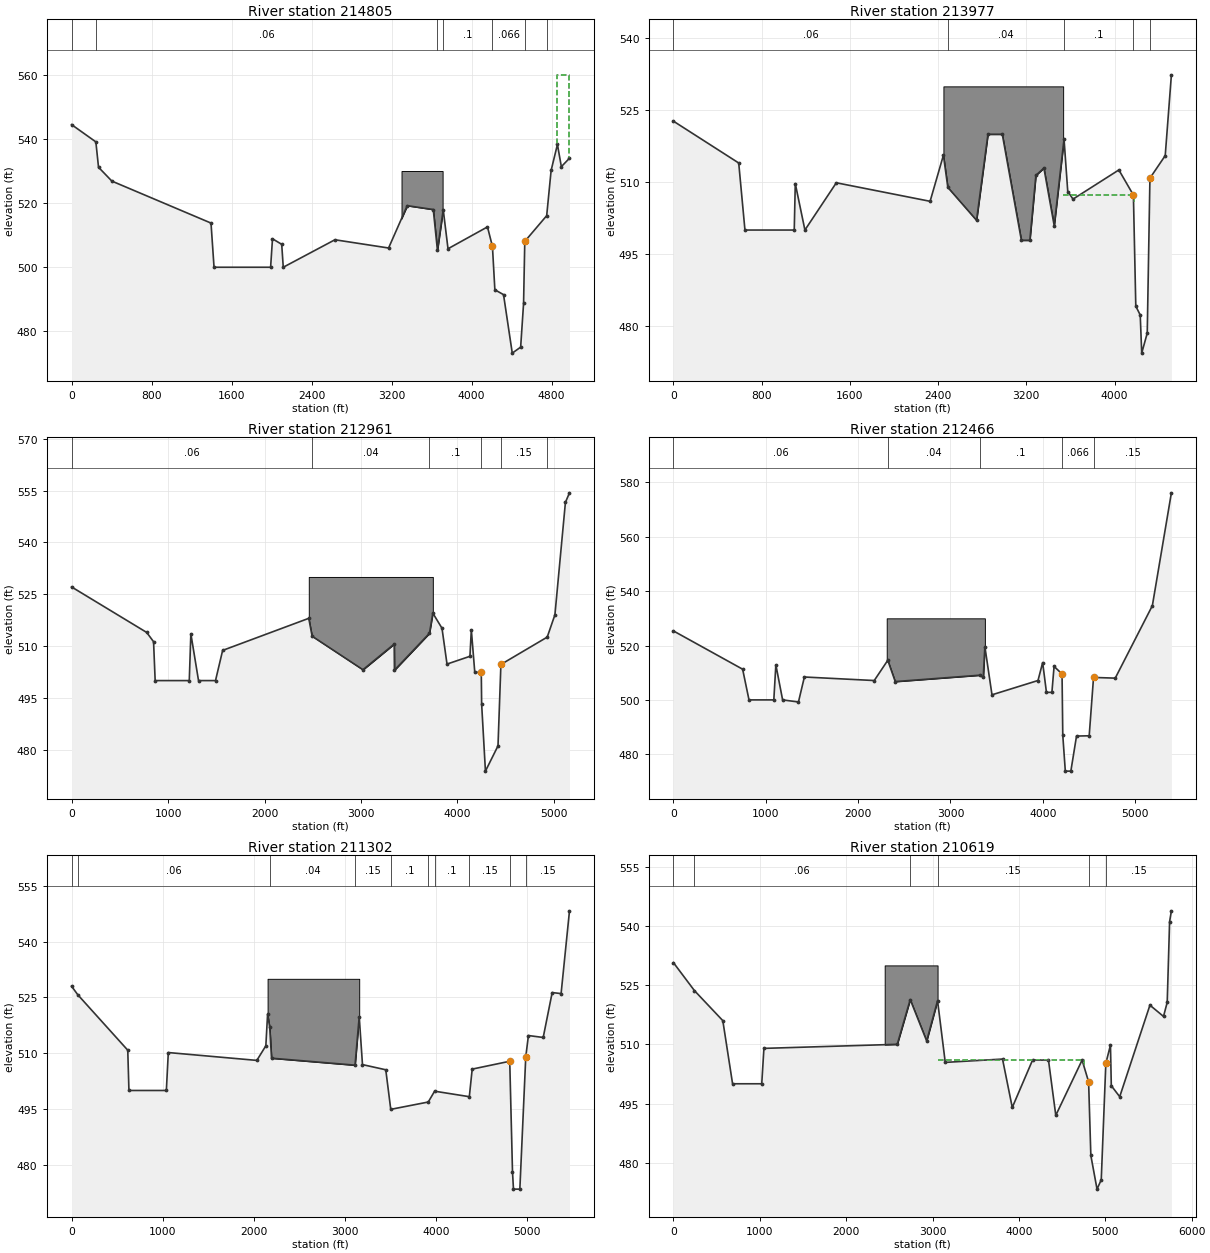
Type RM Length L Ch R = 1 ,214805  ,828,828,1382
BEGIN DESCRIPTION:
This cross section corresponds to cross section 214682.5 of the non-georeferenced CDC model which was the source of this model.
Abandoned sewage treatment plant in LOB - leveed plant blocked for conveyance and storage per CDC Model procedure.
END DESCRIPTION:
XS GIS Cut Line= 3
 2341227.4318329 6962273.2475063 2343527.2944227 6959420.6329964
 2343800.8091512 6958135.2655388
#Sta/Elev= 30
       0  544.48  242.95  539.09  269.56  531.18  402.99  526.86 1394.26  513.77
  1424.5     500 1990.16     500 2008.95  508.87 2101.15  507.15 2116.56     500
 2633.23  508.57  3169.6     506  3356.3   519.2 3616.44     518 3658.13  505.27
 3715.88  517.98 3763.77  505.77 4158.37  512.58 4208.01  506.49 4232.29  492.97
  4318.9  491.46 4406.24  473.22 4490.18  475.09 4519.26  488.71 4531.43  508.06
 4750.39  516.08 4794.87  530.22 4857.87  538.29 4896.91  531.36  4978.4     534
#Mann= 7 ,-1,0
       0     .09       0  242.95     .06       0 3658.13     .04       0
 3715.88      .1       0 4208.01    .066       0 4531.43     .15       0
 4750.39    .035       0
#XS Ineff= 3 ,-1
       0 3298.86  506.49 3709.71 4208.01  506.49 4857.87  4978.4     560
Permanent Ineff=
       F       F       T
#Block Obstruct= 1 ,-1
 3298.86 3709.71     530
Bank Sta=4208.01,4531.43
XS Rating Curve= 0 ,0
Exp/Cntr=0.3,0.1

Type RM Length L Ch R = 1 ,213977  ,1017,1017,2678
BEGIN DESCRIPTION:
This cross section corresponds to cross section 213855 of the non-georeferenced CDC model which was the source of this model.
Abandoned sewage treatment plant in LOB - leveed plant blocked for conveyance and storage per CDC Model procedure.
Channel data estimated from USACE 1975 survey.
END DESCRIPTION:
XS GIS Cut Line= 3
 2341678.0955673 6961796.9975873 2344242.1831846 6959434.2782615
 2344510.6739376 6958440.8620738
#Sta/Elev= 30
       0  522.73   591.8     514   648.3     500 1095.38     500 1104.76   509.7
 1192.13     500 1476.98  509.87 2327.41     506 2448.23  515.62 2488.18  508.91
 2748.65  502.03  2852.1     520 2982.02     520 3155.34  497.86 3232.14  497.86
 3286.71  511.41 3359.31  512.95 3453.01  500.91 3542.15  518.99 3575.82  508.04
 3623.71  506.46 4039.34  512.55 4171.19   507.3 4192.94   484.1 4233.06  482.26
  4246.6   474.3 4296.72  478.48 4321.12  510.83  4459.8  515.54 4515.75  532.41
#Mann= 5 ,-1,0
       0     .06       0 2488.18     .04       0 3542.15      .1       0
 4171.19    .066       0 4321.12    .035       0
#XS Ineff= 2 ,-1
       0 2448.23  507.27 3534.12 4172.55  507.27
Permanent Ineff=
       F       F
#Block Obstruct= 1 ,-1
 2448.23 3534.12     530
Bank Sta=4171.19,4321.12
XS Rating Curve= 0 ,0
Exp/Cntr=0.3,0.1

Type RM Length L Ch R = 1 ,212961  ,495,495,883
BEGIN DESCRIPTION:
This cross section corresponds to cross section 212838.3 of the non-georeferenced CDC model which was the source of this model.
Abandoned sewage treatment plant in LOB - leveed plant blocked for conveyance and storage per CDC Model procedure.
Channel data estimated from USACE 1975 survey.
END DESCRIPTION:
XS GIS Cut Line= 3
 2341481.0248919 6962025.5784969 2345544.3637317 6959071.8156737
 2345653.0846959 6958987.1708755
#Sta/Elev= 30
       0  527.11  779.13  513.93  849.99  511.25  866.52     500  1220.2     500
  1236.5  513.56 1316.04     500 1492.07     500 1565.95  508.74 2458.77  518.02
 2493.41  512.85 3020.44  503.14 3344.24  510.57 3346.61  503.01 3709.93   513.7
 3744.61  519.53 3839.72  515.15 3891.68  504.78 4129.51  507.03 4143.67  514.72
 4179.67  502.36 4246.93  502.39 4250.64  493.22    4290   473.8 4420.25  481.11
 4450.35  504.67 4930.57  512.59 5010.27  519.05  5119.1  551.58 5161.28  554.34
#Mann= 6 ,-1,0
       0     .06       0 2493.41     .04       0 3709.93      .1       0
 4246.93    .066       0 4450.35     .15       0 4930.57    .035       0
#XS Ineff= 2 ,-1
       0 2458.77   507.8 3744.61 4143.67  514.72
Permanent Ineff=
       F       F
#Block Obstruct= 1 ,-1
 2458.77 3744.61     530
Bank Sta=4246.93,4450.35
XS Rating Curve= 0 ,0
Exp/Cntr=0.3,0.1

Type RM Length L Ch R = 1 ,212466  ,1164,1164,1705
BEGIN DESCRIPTION:
This cross section corresponds to cross section 212348.6 of the non-georeferenced CDC model which was the source of this model.
Abandoned sewage treatment plant in LOB - leveed plant blocked for conveyance and storage per CDC Model procedure.
Channel data estimated from USACE 1975 survey.
END DESCRIPTION:
XS GIS Cut Line= 4
 2341561.0009215 6962054.6607484 2343450.1350292 6960790.1569073
 2345826.2791066 6959595.3726873 2346240.3543129 6959393.7880306
#Sta/Elev= 30
       0  525.36  749.14  511.29  818.16     500 1087.04     500 1109.02  512.89
  1182.3     500 1353.86  499.23 1417.98  508.42 2174.81  507.12 2321.34  514.57
 2402.16  506.73 3321.28  509.09 3355.62  508.24 3373.04   519.6 3450.09  501.87
 3948.55  507.13 3998.93  513.72 4040.05  502.77 4099.16  502.78 4122.66  512.31
    4209  509.54 4216.88  487.03  4244.4   473.8  4304.4   473.8 4365.76   486.7
 4503.05   486.8 4550.15  508.26  4785.2     508 5187.22  534.65 5393.43  576.16
#Mann= 5 ,-1,0
       0     .06       0 2321.34     .04       0 3321.28      .1       0
    4209    .066       0 4550.15     .15       0
#XS Ineff= 2 ,-1
       0 2309.83   507.8 3373.04    4209   507.8
Permanent Ineff=
       F       F
#Block Obstruct= 1 ,-1
 2309.83 3373.04     530
Bank Sta=4209,4550.15
XS Rating Curve= 0 ,0
Exp/Cntr=0.3,0.1

Type RM Length L Ch R = 1 ,211302  ,683,683,778
BEGIN DESCRIPTION:
This cross section corresponds to cross section 211182.5 of the non-georeferenced CDC model which was the source of this model.
Abandoned sewage treatment plant in LOB - leveed plant blocked for conveyance and storage per CDC Model procedure.
Channel data estimated from USACE 1975 survey.
END DESCRIPTION:
XS GIS Cut Line= 4
 2341510.1070138 6962163.7187703 2343436.7106666 6961260.0159518
  2346014.283317 6960522.6882172 2346657.4812251 6960381.2802729
#Sta/Elev= 30
       0  528.01    69.1  525.69  617.08  510.82  630.02     500  1040.9     500
 1062.32  510.19 2034.28  508.08 2133.37     512 2152.36  520.43 2175.58  517.05
  2195.8  508.67 3112.83   506.8 3158.62  519.83 3194.44  506.95 3450.14  505.56
 3504.95  494.93 3916.82   496.9 3986.47  499.81 4367.62  498.33 4399.21  505.74
 4811.42  507.85 4841.74  478.14  4852.5   473.5  4922.5   473.5 4987.33  509.01
  5016.5  514.76 5178.91  514.24  5277.4   526.3 5375.34  526.03 5467.54  548.26
#Mann= 10 ,-1,0
       0     .09       0    69.1     .06       0 2175.58     .04       0
 3112.83     .15       0 3504.95      .1       0 3916.82     .15       0
 3986.47      .1       0 4367.62     .15       0 4811.42    .066       0
 4987.33     .15       0
#XS Ineff= 2 ,-1
       0 2152.36  507.85 3158.62 4811.42  507.85
Permanent Ineff=
       F       F
#Block Obstruct= 1 ,-1
 2152.36 3158.62     530
Bank Sta=4811.42,4987.33
XS Rating Curve= 0 ,0
Exp/Cntr=0.3,0.1

Type RM Length L Ch R = 1 ,210619  ,460,460,510
BEGIN DESCRIPTION:
This cross section corresponds to cross section 210502.6 of the non-georeferenced CDC model which was the source of this model.
Channel data estimated from USACE 1975 survey.
Abandoned sewage treatment plant in LOB - leveed plant blocked for conveyance and storage per CDC Model procedure.
END DESCRIPTION:
XS GIS Cut Line= 3
 2341454.8007606 6962220.4300358 2343520.8376922 6961735.8041017
 2347085.7676613 6960984.6257467
#Sta/Elev= 30
       0  530.69  242.43  523.62  571.38     516  684.43     500 1022.18     500
 1047.34  508.97 2591.09     510 2741.27  521.34 2931.66  510.86 3057.89  521.06
 3146.92  505.42 3810.08  506.26 3922.84     494 4157.85     506 4342.17     506
 4426.79     492 4731.47     506 4806.77   500.5 4832.63  481.83  4904.3   473.3
 4953.13  475.66 5006.34  505.19 5059.77   509.8 5069.52  499.51 5166.95  496.72
 5516.78  519.92 5673.95  517.07 5716.91  520.63 5744.46  541.07 5765.34  543.83
#Mann= 6 ,-1,0
       0     .09       0  242.43     .06       0 2741.27     .04       0
 3057.89     .15       0 4806.77    .066       0 5006.34     .15       0
#XS Ineff= 3 ,-1
       0 2445.58     506 3057.89 4752.77     506 5006.34 5765.34  505.19
Permanent Ineff=
       F       F       F
#Block Obstruct= 1 ,-1
 2445.58 3057.89     530
Bank Sta=4806.77,5006.34
XS Rating Curve= 0 ,0
Exp/Cntr=0.3,0.1

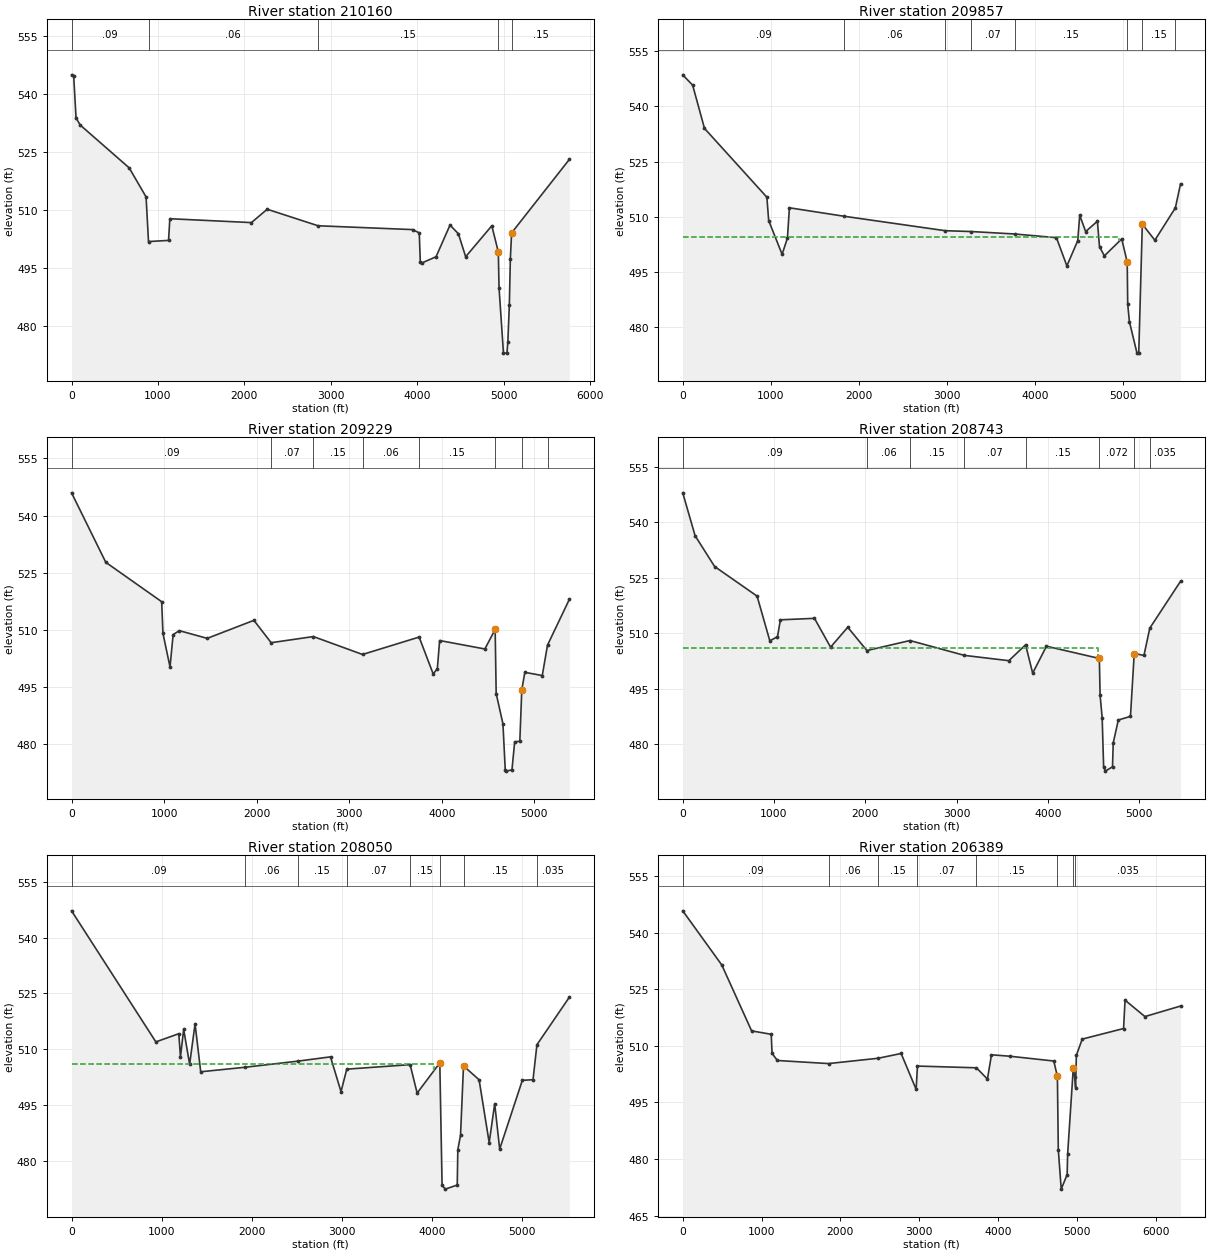
Type RM Length L Ch R = 1 ,210160  ,303,303,378
BEGIN DESCRIPTION:
This cross section corresponds to cross section 210038.7 of the non-georeferenced CDC model which was the source of this model.
Channel data estimated from USACE 1975 survey.
END DESCRIPTION:
XS GIS Cut Line= 3
 2341352.7741526 6962454.2407855 2346229.4630691  6961628.956012
 2347035.4406234  6961501.198647
#Sta/Elev= 30
       0  544.99   24.97  544.59   52.05  533.84  101.09     532  667.01  520.96
  862.66  513.45  890.74  501.92 1122.66  502.22 1137.71  507.82 2082.08  506.82
 2264.48  510.27 2853.38     506 3947.32  505.01 4024.75  504.16 4036.74  496.71
 4051.45  496.35 4219.21     498 4380.81  506.18 4477.54  503.94 4561.88     498
 4864.49     506 4939.94  499.23 4948.07  490.04  4999.5   473.1  5039.5   473.1
 5049.88  475.92 5067.43  485.49 5079.05  497.46 5093.82  504.16 5762.07  523.14
#Mann= 5 ,-1,0
       0     .09       0  890.74     .06       0 2853.38     .15       0
 4939.94    .066       0 5093.82     .15       0
#XS Ineff= 2 , 0
       0 4864.49     506               0
Permanent Ineff=
       F       F
Bank Sta=4939.94,5093.82
XS Rating Curve= 0 ,0
Exp/Cntr=0.3,0.1

Type RM Length L Ch R = 1 ,209857  ,628,628,651
BEGIN DESCRIPTION:
This cross section corresponds to cross section 209734 of the non-georeferenced CDC model which was the source of this model.
Channel data estimated from USACE 1975 survey.
END DESCRIPTION:
XS GIS Cut Line= 3
 2341261.9374736 6962626.0030896 2346258.7714086  6961907.385302
 2346859.3999414 6961960.9960956
#Sta/Elev= 30
       0  548.54  112.49  545.73  246.99     534  955.32  515.32  975.59  508.99
 1128.16  499.82 1188.73  504.23    1211  512.45 1829.92  510.16 2979.58  506.23
  3276.8     506 3767.81  505.34 4242.46  504.34 4361.12  496.68 4484.57  503.55
 4506.78  510.44 4574.09     506 4707.55   508.8  4731.6  501.86 4786.92  499.41
 4983.64     504 5046.06  497.71 5051.63  486.28 5071.02  481.54    5157     473
    5177     473 5217.43     508 5359.87  503.65 5592.62  512.42 5651.26  518.94
#Mann= 8 ,-1,0
       0     .09       0 1829.92     .06       0 2979.58     .15       0
  3276.8     .07       0 3767.81     .15       0 5046.06    .066       0
 5217.43     .15       0 5592.62    .035       0
#XS Ineff= 2 , 0
       0  4956.3  504.53 5217.43       0     508
Permanent Ineff=
       F       F
Bank Sta=5046.06,5217.43
XS Rating Curve= 0 ,0
Exp/Cntr=0.3,0.1

Type RM Length L Ch R = 1 ,209229  ,486,486,530
BEGIN DESCRIPTION:
This cross section corresponds to cross section 209098.0 of the non-georeferenced CDC model which was the source of this model.
Channel data estimated from USACE 1975 survey.
END DESCRIPTION:
XS GIS Cut Line= 3
 2341347.3306697 6962978.2497158 2345937.2120771 6962476.5650288
 2346696.4286447 6962430.1366958
#Sta/Elev= 30
       0  545.97  369.96  527.72  973.81  517.38  987.36  509.06 1063.67  500.26
 1097.46  508.75 1164.57  509.78 1465.75  507.76  1969.9  512.49 2156.27  506.62
 2612.57  508.23 3143.47  503.53 3754.96   508.1 3906.85  498.42  3951.7  499.79
 3976.51  507.19 4465.25  504.97 4576.29  510.11 4587.36  493.27  4660.5  485.32
  4685.5  473.19    4697   472.9 4757.99  473.24 4787.19   480.6  4842.9  480.74
 4863.99  494.24 4896.89  498.84 5085.34     498 5141.84  505.98 5377.86     518
#Mann= 8 ,-1,0
       0     .09       0 2156.27     .07       0 2612.57     .15       0
 3143.47     .06       0 3754.96     .15       0 4576.29    .066       0
 4863.99     .15       0 5141.84    .035       0
#XS Ineff= 2 , 0
       0 4576.29     506               0
Permanent Ineff=
       F       F
Bank Sta=4576.29,4863.99
XS Rating Curve= 0 ,0
Exp/Cntr=0.3,0.1

Type RM Length L Ch R = 1 ,208743  ,692,692,173
BEGIN DESCRIPTION:
This cross section corresponds to cross section 208638.1 of the non-georeferenced CDC model which was the source of this model.
Channel data estimated from USACE 1975 survey.
END DESCRIPTION:
XS GIS Cut Line= 3
 2341464.7461685 6963181.0585404 2346581.7108619 6962896.8389868
 2346910.5357426 6962891.7143396
#Sta/Elev= 30
       0   547.9  135.48  536.32  349.21     528   814.6     520  954.12  507.93
 1038.05  509.04 1070.13   513.6 1443.14     514 1619.64  506.21 1807.98  511.59
 2017.54   505.3 2489.48     508  3086.7  503.99 3572.74  502.56 3756.41  506.85
  3833.9  499.19  3984.9  506.47 4564.42  503.16 4572.47  493.24 4595.26  487.17
  4611.3  473.89 4629.93  472.73 4708.56  473.91  4716.2  480.33 4772.24  486.54
 4905.18  487.52 4946.55   504.5 5052.88  503.98 5117.16  511.36 5453.71     524
#Mann= 8 ,-1,0
       0     .09       0 2017.54     .06       0 2489.48     .15       0
  3086.7     .07       0 3756.41     .15       0 4564.42    .072       0
 4946.55     .15       0 5117.16    .035       0
#XS Ineff= 2 , 0
       0 4547.46  505.93               0
Permanent Ineff=
       F       F
Bank Sta=4564.42,4946.55
XS Rating Curve= 0 ,0
Exp/Cntr=0.3,0.1

Type RM Length L Ch R = 1 ,208050  ,1662,1662,6820
BEGIN DESCRIPTION:
This cross section corresponds to cross section 207998 of the non-georeferenced CDC model which was the source of this model.
Channel data estimated from USACE 1975 survey.
Channel reach length modified to account for reduced effective length for high flows and to better compute volume.
END DESCRIPTION:
XS GIS Cut Line= 4
 2341539.4652637 6963415.8896677 2345970.4812343 6963334.7668638
 2346603.8079802 6962936.0056178 2346946.9932305 6962930.3497104
#Sta/Elev= 30
       0  547.16  935.39  512.01  1189.9  514.21 1208.41     508  1243.9  515.38
 1310.05     506 1370.41  516.85 1433.04     504 1928.76  505.22 2507.67  506.84
 2873.18     508 2989.85  498.67 3053.73   504.7 3756.69  505.91 3834.42  498.29
 4086.03  506.38 4111.16  473.65  4145.3  472.53 4279.44  473.62 4285.87  483.08
 4315.92  486.97 4348.92  505.56 4521.96  501.86 4633.87  485.01 4695.14  495.43
 4750.32  483.27 5001.94  501.71 5120.27  501.87 5163.76  511.25  5523.4     524
#Mann= 8 ,-1,0
       0     .09       0 1928.76     .06       0 2507.67     .15       0
 3053.73     .07       0 3756.69     .15       0 4086.03    .072       0
 4348.92     .15       0 5163.76    .035       0
#XS Ineff= 2 , 0
       0 4017.66     506 4348.92       0  505.56
Permanent Ineff=
       F       F
Bank Sta=4086.03,4348.92
XS Rating Curve= 0 ,0
Exp/Cntr=0.5,0.3

Type RM Length L Ch R = 1 ,206389  ,230,230,138
BEGIN DESCRIPTION:
This cross section corresponds to cross section 206448.3 of the non-georeferenced CDC model which was the source of this model.
Upstream of East 1st Street.
Channel data estimated from USACE 1975 survey.
---------------------------------------------------------------------
CDC FW070700-01 Dyer Addition
Located in LOB.
Cross-sections 206448.3 - 209088.06
---------------------------------------------------------------------
END DESCRIPTION:
XS GIS Cut Line= 4
 2341614.8601598  6963472.279432 2345449.1497094 6963553.9425653
 2347221.6992953  6963939.931137 2347885.2533845 6963955.9284139
#Sta/Elev= 30
       0  545.86  495.22  531.49  873.42     514 1122.44  513.09  1132.8  508.03
 1200.06  506.14 1848.69  505.32 2477.39  506.73 2769.83     508 2960.08  498.47
 2976.68  504.66 3724.65   504.2 3864.07  501.21 3915.52  507.65 4150.01  507.27
 4705.57     506 4751.54  501.92 4762.99   482.5    4800     472 4875.04  475.87
 4881.39  481.32  4952.9  504.12 4971.28  501.78 4982.15  498.97 4992.12  507.53
 5066.66  511.82  5590.6  514.62 5609.65  522.14 5861.49   517.8 6312.99  520.59
#Mann= 8 ,-1,0
       0     .09       0 1848.69     .06       0 2477.39     .15       0
 2976.68     .07       0 3724.65     .15       0 4751.54    .066       0
  4952.9     .15       0 4971.28    .035       0
#XS Ineff= 2 , 0
       0                 6312.99       0
Permanent Ineff=
       F       F
Bank Sta=4751.54,4952.9
XS Rating Curve= 0 ,0
Exp/Cntr=0.5,0.3