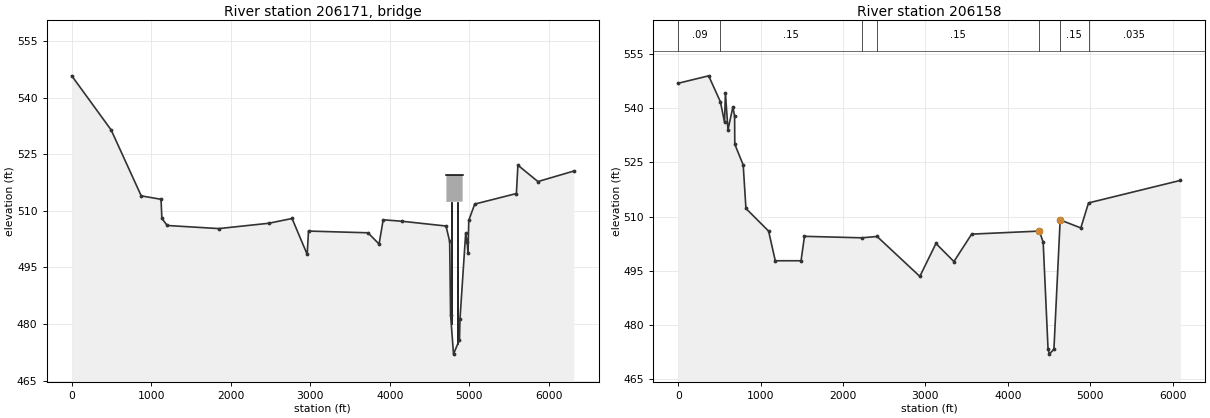
HEC-RAS study CDC_Consolidated_Model.prj: Upper Trinity CDC Consolidated Model

--- CDC_Consolidated_Model.g03 (geometry) --- (continued)

Type RM Length L Ch R = 3 ,206171  ,,,
BEGIN DESCRIPTION:
East 1st Street
Data from USACE 1975 survey.
Note:  Internal bridge cross-sections modified to represent geometry under bridge.
END DESCRIPTION:
Node Name=East 1st Street
Bridge Culvert--1,0,-1,-1, 0
Deck Dist Width WeirC Skew NumUp NumDn MinLoCord MaxHiCord MaxSubmerge Is_Ogee
110.3,25,2.6,0, 2, 2, , , 0.95, 0, 0,0,,
 4711.04 4914.96
   519.5   519.5
  512.38  512.48
 4711.04 4914.96
   519.5   519.5
  512.38  512.48
Pier Skew, UpSta & Num, DnSta & Num=  ,4772.04, 2 ,4772.04, 2 , 0 , 0 , 0 ,,
       6       6
     450     515
       6       6
     450     515
Pier Skew, UpSta & Num, DnSta & Num=  ,4852.04, 2 ,4852.04, 2 , 0 , 0 , 0 ,,
       6       6
     450     515
       6       6
     450     515
BR Coef=-1 , 0 , 0 ,, 0 ,,,0.8,-1,,0,
WSPro=,,,, 1 ,,,, 0 ,,,, 0 ,,,,-1 ,-1 ,-1 , 0 , 0 , 0 , 0 , 0
BR U #Sta/Elev= 492
       0  548.23     .68  548.22   26.63   547.6   27.12   547.6   52.94  546.99
   53.64  546.98   80.06  546.35  105.64  545.75  162.76     544  171.86  543.86
  211.57  542.72  231.62     542  238.86  541.94  254.87  541.48  270.84  541.01
  301.83  540.12  348.43  538.63  360.89  538.22   364.2  538.08  364.98   538.1
  393.81  537.18  396.27  537.09  401.23  537.12  401.85  536.89   423.5  536.11
  426.57  535.99  471.45  534.37  478.54  534.06  480.08  534.02  521.09   532.3
  526.97  531.96  530.23  531.92   542.2  531.41  543.35  531.34  571.34  530.16
  574.93  529.98  588.42  529.39  600.27  528.86  611.35  528.39  619.77  528.05
  625.98  527.69  629.29  527.53  653.23  526.46  659.35  526.18  662.23     526
  675.29  525.33  676.51  525.35  696.28  524.38  708.11  523.81  713.31  523.51
   718.9  523.28  729.93  522.75  744.06     522  759.93  521.24  766.58  520.91
   767.2  520.93  775.99  520.49  784.52     520  817.55  518.52  821.63  518.31
  873.18  516.03  875.77  515.95  880.24  515.73  880.66  515.66  887.62  515.32
  894.53  514.96  894.88  515.05  907.57  514.48  911.05  514.48  913.81  514.38
  944.92  513.38   975.2  512.43  983.79  512.15  992.43  511.97  996.47  511.75
 1008.81  511.36    1014  511.31 1056.69  509.98 1059.18  510.13  1072.4     510
  1080.1  509.75  1106.4  509.28  1119.5  509.04 1123.71  509.41 1125.76  509.94
 1127.82  509.32 1132.46  508.04 1134.21     508 1135.66  507.66  1142.1  507.51
 1145.23  507.48 1157.49  507.47 1181.85  506.99 1194.92  506.98 1222.42  506.45
 1236.26  506.44  1248.7  506.35 1252.43  506.08 1259.65   505.9 1267.88  505.89
 1271.51   505.6 1277.21  505.72  1286.3  505.66 1291.02  505.68 1292.98  505.64
 1298.38  505.61 1302.78  505.51 1308.31  505.48 1312.57  505.39 1318.34  505.36
 1322.47  505.28 1336.45   505.2 1350.87   505.1 1364.84  505.02 1365.34  504.99
 1372.72  504.95 1406.64  504.74 1420.29  504.64 1438.49  504.56  1467.8  504.46
 1483.46  504.38 1507.54  504.38 1518.44   504.4  1529.6   504.4 1540.82  504.42
 1566.07  504.43 1577.53  504.45  1598.2  504.45 1599.99  504.46 1618.06  504.46
 1644.37  504.48 1664.86  504.48 1686.21   504.5 1702.13   504.5 1703.67  504.51
 1721.45  504.51 1729.55  504.52 1750.18  504.69 1769.61  504.84 1816.08  505.23
 1826.01   505.3 1835.91  505.39  1869.8  505.66 1890.25  505.83 1899.43  505.89
 1911.13  506.03  1921.1  506.08 1925.48  506.07 1928.99     506 1937.39  506.07
 1937.53  506.44 1963.88   506.8 1971.65   506.9 2017.44  506.92 2043.85  506.94
 2054.01  506.94 2117.31  506.98  2143.9  507.02 2170.31  507.07 2187.23  507.09
 2194.71  507.11 2218.62  507.15 2236.69  507.15 2238.36  507.16 2256.36  507.16
 2258.73  507.17 2277.34  507.17 2284.32  507.18 2312.38  507.18 2313.98  507.19
 2334.23  507.19 2387.86  507.25 2396.26  507.25 2407.53  507.27 2416.05  507.27
 2446.08  507.31 2453.59  507.31 2478.63  507.35 2488.36  507.44 2493.46  507.46
 2511.34  507.62 2517.63  507.66 2522.86  507.72 2544.98   507.9 2557.96  507.97
 2568.12  507.99 2598.98     508 2609.65  508.01  2628.1  508.01 2676.41  508.04
 2706.41  508.05 2726.55  508.07 2745.67  508.08 2752.97  508.11 2770.37  508.13
 2779.42  508.15 2785.39  507.98 2789.73  507.97  2812.7  508.02 2827.69  508.06
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BR U #Mann= 3
       0     .06 4711.04    .055 4914.96     .06
BR U Banks=4711.04,4914.96
BR D #Sta/Elev= 492
       0  548.23     .68  548.22   26.63   547.6   27.12   547.6   52.94  546.99
   53.64  546.98   80.06  546.35  105.64  545.75  162.76     544  171.86  543.86
  211.57  542.72  231.62     542  238.86  541.94  254.87  541.48  270.84  541.01
  301.83  540.12  348.43  538.63  360.89  538.22   364.2  538.08  364.98   538.1
  393.81  537.18  396.27  537.09  401.23  537.12  401.85  536.89   423.5  536.11
  426.57  535.99  471.45  534.37  478.54  534.06  480.08  534.02  521.09   532.3
  526.97  531.96  530.23  531.92   542.2  531.41  543.35  531.34  571.34  530.16
  574.93  529.98  588.42  529.39  600.27  528.86  611.35  528.39  619.77  528.05
  625.98  527.69  629.29  527.53  653.23  526.46  659.35  526.18  662.23     526
  675.29  525.33  676.51  525.35  696.28  524.38  708.11  523.81  713.31  523.51
   718.9  523.28  729.93  522.75  744.06     522  759.93  521.24  766.58  520.91
   767.2  520.93  775.99  520.49  784.52     520  817.55  518.52  821.63  518.31
  873.18  516.03  875.77  515.95  880.24  515.73  880.66  515.66  887.62  515.32
  894.53  514.96  894.88  515.05  907.57  514.48  911.05  514.48  913.81  514.38
  944.92  513.38   975.2  512.43  983.79  512.15  992.43  511.97  996.47  511.75
 1008.81  511.36    1014  511.31 1056.69  509.98 1059.18  510.13  1072.4     510
  1080.1  509.75  1106.4  509.28  1119.5  509.04 1123.71  509.41 1125.76  509.94
 1127.82  509.32 1132.46  508.04 1134.21     508 1135.66  507.66  1142.1  507.51
 1145.23  507.48 1157.49  507.47 1181.85  506.99 1194.92  506.98 1222.42  506.45
 1236.26  506.44  1248.7  506.35 1252.43  506.08 1259.65   505.9 1267.88  505.89
 1271.51   505.6 1277.21  505.72  1286.3  505.66 1291.02  505.68 1292.98  505.64
 1298.38  505.61 1302.78  505.51 1308.31  505.48 1312.57  505.39 1318.34  505.36
 1322.47  505.28 1336.45   505.2 1350.87   505.1 1364.84  505.02 1365.34  504.99
 1372.72  504.95 1406.64  504.74 1420.29  504.64 1438.49  504.56  1467.8  504.46
 1483.46  504.38 1507.54  504.38 1518.44   504.4  1529.6   504.4 1540.82  504.42
 1566.07  504.43 1577.53  504.45  1598.2  504.45 1599.99  504.46 1618.06  504.46
 1644.37  504.48 1664.86  504.48 1686.21   504.5 1702.13   504.5 1703.67  504.51
 1721.45  504.51 1729.55  504.52 1750.18  504.69 1769.61  504.84 1816.08  505.23
 1826.01   505.3 1835.91  505.39  1869.8  505.66 1890.25  505.83 1899.43  505.89
 1911.13  506.03  1921.1  506.08 1925.48  506.07 1928.99     506 1937.39  506.07
 1937.53  506.44 1963.88   506.8 1971.65   506.9 2017.44  506.92 2043.85  506.94
 2054.01  506.94 2117.31  506.98  2143.9  507.02 2170.31  507.07 2187.23  507.09
 2194.71  507.11 2218.62  507.15 2236.69  507.15 2238.36  507.16 2256.36  507.16
 2258.73  507.17 2277.34  507.17 2284.32  507.18 2312.38  507.18 2313.98  507.19
 2334.23  507.19 2387.86  507.25 2396.26  507.25 2407.53  507.27 2416.05  507.27
 2446.08  507.31 2453.59  507.31 2478.63  507.35 2488.36  507.44 2493.46  507.46
 2511.34  507.62 2517.63  507.66 2522.86  507.72 2544.98   507.9 2557.96  507.97
 2568.12  507.99 2598.98     508 2609.65  508.01  2628.1  508.01 2676.41  508.04
 2706.41  508.05 2726.55  508.07 2745.67  508.08 2752.97  508.11 2770.37  508.13
 2779.42  508.15 2785.39  507.98 2789.73  507.97  2812.7  508.02 2827.69  508.06
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BR D #Mann= 3
       0     .06 4711.04    .055 4914.96     .06
BR D Banks=4711.04,4914.96
BC Design=,, 0 ,, 0 ,,,,,,
BC Use User HTab Curves=0
BC User HTab FreeFlow(D)= 0

Type RM Length L Ch R = 1 ,206158  ,0,0,0
BEGIN DESCRIPTION:
This cross section corresponds to cross section 206218.0 of the non-georeferenced CDC model which was the source of this model.
Downstream of East 1st Street.
Central City model begins here.
********************************************** Rating curve as downstream condition developed from the current Upper Trinity River CDC Model.
**********************************************
Channel data estimated from USACE 1975 survey.
END DESCRIPTION:
XS GIS Cut Line= 6
     2341904.096     6963632.544     2343430.684     6963683.607
     2344852.789     6963698.881     2345465.415      6963790.52
     2347058.227     6964146.116     2347947.115     6964085.101
#Sta/Elev= 30
       0  546.85  369.23   548.9  512.04  541.71  562.18  536.03  572.53  544.23
  603.81  533.98  663.08  540.28  684.12  537.77  686.41     530  788.51  524.26
  821.63  512.25 1096.67     506  1177.8   497.8 1490.48   497.8  1532.1  504.55
 2227.97  504.14 2413.28  504.51 2932.16  493.48 3128.06  502.57 3345.99  497.58
 3560.99  505.16 4383.29     506 4429.29  502.89 4488.22  473.47 4503.96     472
 4559.71  473.37 4635.51  509.09 4886.06  506.87 4979.55  513.78 6093.63     520
#Mann= 7 ,-1,0
       0     .09       0  512.04     .15       0 2227.97     .06       0
 2413.28     .15       0 4383.29    .066       0 4635.51     .15       0
 4979.55    .035       0
#XS Ineff= 2 , 0
       0                 6093.63       0
Permanent Ineff=
       F       F
Bank Sta=4383.29,4635.51
XS Rating Curve= 0 ,0
Exp/Cntr=0.5,0.3
Stream Node=Clear Fork      ,cf              , 0 , 0 ,Upstream end
Stream Node=Clear Fork      ,cf              , 0 , 1 ,Downstream end
Stream Node=West Fork       ,wf4             , 0 , 0 ,Upstream end
Stream Node=West Fork       ,wf4             , 0 , 1 ,Downstream end
Stream Node=West Fork       ,wf3             , 0 , 0 ,Upstream end
Stream Node=West Fork       ,wf3             , 0 , 1 ,Downstream end
LCMann Table=0

--- CDC_Consolidated_Model.g04 (geometry) ---

Geom Title=Exist: 1%+ AEP [WF/EF/TRMS]
Program Version=6.60
BEGIN GEOM DESCRIPTION:
Existing: Geometry file for use with 1%+ AEP peak flows for the WF/EF/TRMS
END GEOM DESCRIPTION:

Junct Name=ef-wf
Junct Desc=, 0 , 0 , 0 ,0
Up River,Reach=Elm Fork        ,ef3 ds
Up River,Reach=West Fork       ,wf
Dn River,Reach=Main Stem       ,ms
Junc L&A=3030,20
Junc L&A=1494,0

Junct Name=J2
Junct Desc=, 0 , 0 ,-1 ,0
Up River,Reach=Elm Fork        ,ef3
Dn River,Reach=Elm Fork        ,PGBT split west
Dn River,Reach=Elm Fork        ,PGBT split east
Junc L&A=741,0
Junc L&A=370,0

Junct Name=J1
Junct Desc=, 0 , 0 ,-1 ,0
Up River,Reach=Elm Fork        ,PGBT split west
Up River,Reach=Elm Fork        ,PGBT split east
Dn River,Reach=Elm Fork        ,ef3 ds
Junc L&A=1067,0
Junc L&A=1067,0

River Reach=Elm Fork        ,ef3
Reach XY= 30
      2443507.86      7054781.77      2443915.37      7053909.89
      2443712.82      7053314.17      2443133.27      7052713.75
      2443336.18      7052124.19       2443690.1      7052046.36
      2444983.67      7052568.29      2445822.43      7052571.42
      2446558.92      7052244.63      2446983.77      7051618.15
      2446833.53      7051182.86      2445539.52      7051137.95
      2445258.66      7050815.85      2446648.28      7050138.14
      2446851.94      7049721.91      2446747.18      7049390.79
      2445718.34      7049007.95      2445520.89      7048288.45
      2444349.09      7048317.26      2443701.18      7047191.54
      2443845.71      7046976.55      2446154.44      7046114.48
      2446441.34      7045466.69      2446602.22      7043949.82
      2448092.76      7043729.22      2448101.07      7043184.86
      2447026.42      7042543.32      2447988.56      7041959.85
      2447709.25      7040463.12      2447850.52      7040050.17

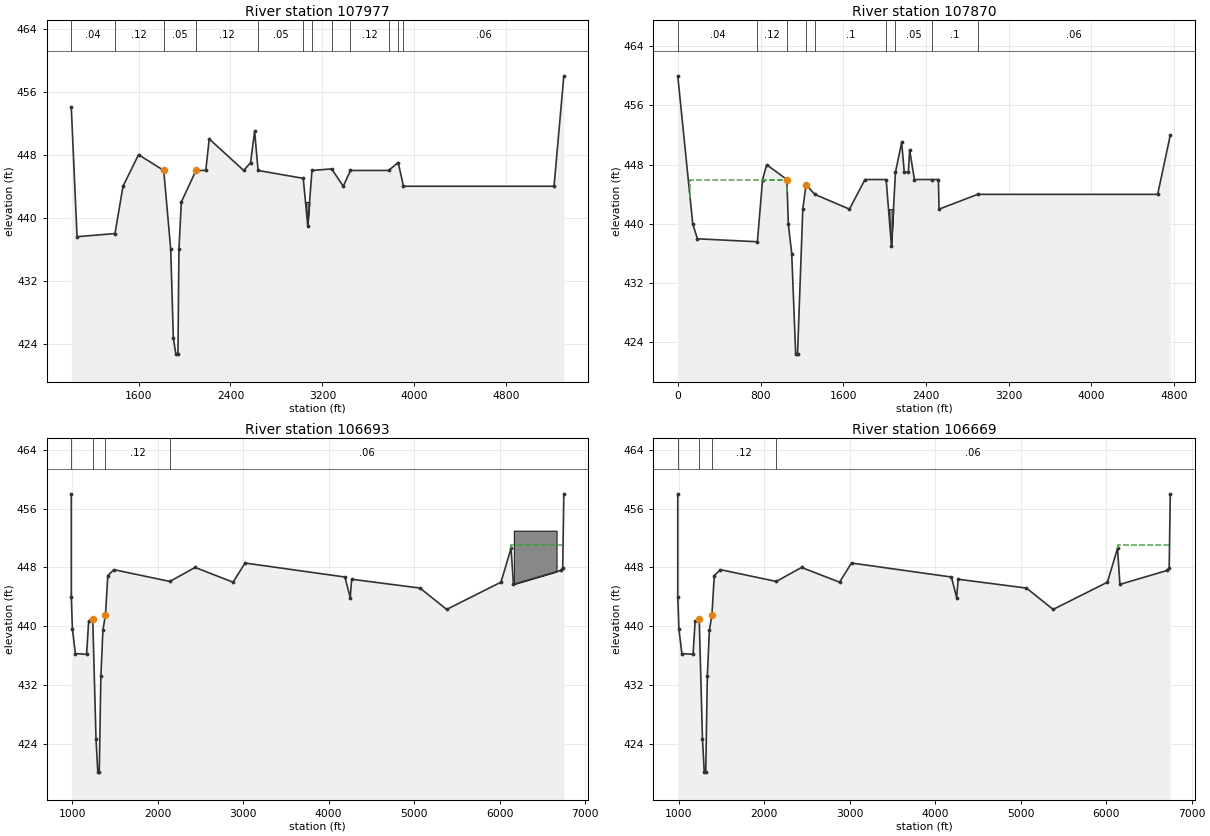
Type RM Length L Ch R = 1 ,107977  ,37,107,201
BEGIN DESCRIPTION:
This cross section corresponds to cross section 107964 of the non-georeferenced CDC model which was the source of this model.
FIS SECTION RECODED BY OEI, Added dense shrubs b/w fairways, mounds b/s 6 & 8
END DESCRIPTION:
XS GIS Cut Line= 6
2445808.357103357046657.124288962445775.275148517046645.97208031
2445068.484895417046738.446960972444833.605115837046686.63210396
2442716.03290743 7046775.21001082441539.11334527 7046806.0485318
#Sta/Elev= 30
    1015     454    1065   437.6    1395     438    1465     444    1600     448
  1819.3     446    1880     436    1903   424.7    1925  422.71    1943  422.71
  1951.5     436  1972.4     442    2100     446    2185     446    2215     450
    2515     446    2575     447    2610     451    2640     446    3033     445
    3072     439    3109     446    3280   446.2    3381     444    3444     446
    3775     446    3859     447    3905     444    5215     444    5300     458
#Mann= 12 ,-1,0
    1015     .04       0    1395     .12       0  1819.3     .05       0
    2100     .12       0    2640     .05       0    3033     .09       0
    3109     .12       0    3280     .05       0    3444     .12       0
    3775     .05       0    3859      .1       0    3905     .06       0
#XS Ineff= 2 ,-1
    1015  1819.3     446    2100    5300     446
Permanent Ineff=
       F       F
#Block Obstruct= 1 ,-1
    3033    3109     442
Bank Sta=1819.3,2100
XS Rating Curve= 0 ,0
Exp/Cntr=0.3,0.1

Type RM Length L Ch R = 1 ,107870  ,759,1177,557
BEGIN DESCRIPTION:
This cross section corresponds to cross section 107820 of the non-georeferenced CDC model which was the source of this model.
NEW SECTION ADDED BY OEI
----------------------------------------
CDC LEW050102-01 Vista Ridge Golf Center
Cross-section 107820 - 109670
Located in ROB.
----------------------------------------
END DESCRIPTION:
XS GIS Cut Line= 6
2446120.972947937046749.88591446 2445827.42858757046622.02593397
2445390.500983697046619.73591229 2445120.92442317046650.20566763
2444876.301224687046604.346507392441393.439424017046715.47030088
#Sta/Elev= 30
       0     460     145     440     190     438     770   437.6     820     446
     860     448    1055     446    1069     440    1102     436    1140  422.43
    1158  422.43    1209     442    1240   445.3    1325     444    1660     442
    1810     446    2015     446    2066     437    2105     447    2165     451
    2190     447    2230     447    2242     450    2288     446    2460     446
    2520     446    2526     442    2900     444    4640     444    4762     452
#Mann= 9 ,-1,0
       0     .04       0     770     .12       0    1055     .05       0
    1240     .05       0    1325      .1       0    2015     .09       0
    2105     .05       0    2460      .1       0    2900     .06       0
#XS Ineff= 2 ,-1
     120    1060     446    1240    4762   445.3
Permanent Ineff=
       F       F
#Block Obstruct= 1 ,-1
    2015    2105     442
Bank Sta=1055,1240
XS Rating Curve= 0 ,0
Exp/Cntr=0.3,0.1

Type RM Length L Ch R = 1 ,106693  ,24,24,24
BEGIN DESCRIPTION:
This cross section corresponds to cross section 106700 of the non-georeferenced CDC model which was the source of this model.
Water tank section DS Copied section
END DESCRIPTION:
XS GIS Cut Line= 5
2446254.662969267046465.101050972445876.386822917045960.52594464
2445562.02557501 7045963.65257882445240.248987597045964.12501881
2440747.161517087045998.48026505
#Sta/Elev= 30
     990     458     990     444    1003   439.7    1038   436.3    1169   436.2
    1193   440.7    1241     441    1279   424.7    1300   420.2    1317   420.2
    1336   433.2    1360   439.5    1390   441.6    1417   446.9    1489   447.7
    2142   446.1    2438     448    2882     446    3022   448.6    4190   446.7
    4252   443.9    4269   446.4    5068   445.2    5380   442.3    6015     446
    6133   450.6    6161   445.7    6716   447.6    6737   447.9    6750     458
#Mann= 4 ,-1,0
     990     .06       0    1241     .05       0    1390     .12       0
    2142     .06       0
#XS Ineff= 3 ,-1
     200    1241     441    1390    1500   441.6    6133    6750     451
Permanent Ineff=
       F       F       F
#Block Obstruct= 1 ,-1
    6165    6665     453
Bank Sta=1241,1390
XS Rating Curve= 0 ,0
Exp/Cntr=0.3,0.1

Type RM Length L Ch R = 1 ,106669  ,850,721,560
BEGIN DESCRIPTION:
This cross section corresponds to cross section 106657 of the non-georeferenced CDC model which was the source of this model.
Water tank section DS
-------------------------------------------------
CDC LEW052401-1 Water Storage Tank
Cross-section 106657 - 107964
Project located in far ROB west of Gun Club road.
-------------------------------------------------
END DESCRIPTION:
XS GIS Cut Line= 3
2446264.197070937046450.406198472445896.118082677045935.09522122
2440769.508913347045970.63287979
#Sta/Elev= 30
     990     458     990     444    1003   439.7    1038   436.3    1169   436.2
    1193   440.7    1241     441    1279   424.7    1300   420.2    1317   420.2
    1336   433.2    1360   439.5    1390   441.6    1417   446.9    1489   447.7
    2142   446.1    2438     448    2882     446    3022   448.6    4190   446.7
    4252   443.9    4269   446.4    5068   445.2    5380   442.3    6015     446
    6133   450.6    6161   445.7    6716   447.6    6737   447.9    6750     458
#Mann= 4 ,-1,0
     990     .06       0    1241     .05       0    1390     .12       0
    2142     .06       0
#XS Ineff= 3 ,-1
     200    1241     441    1390    1500   441.6    6133    6750     451
Permanent Ineff=
       F       F       F
Bank Sta=1241,1390
XS Rating Curve= 0 ,0
Exp/Cntr=0.3,0.1