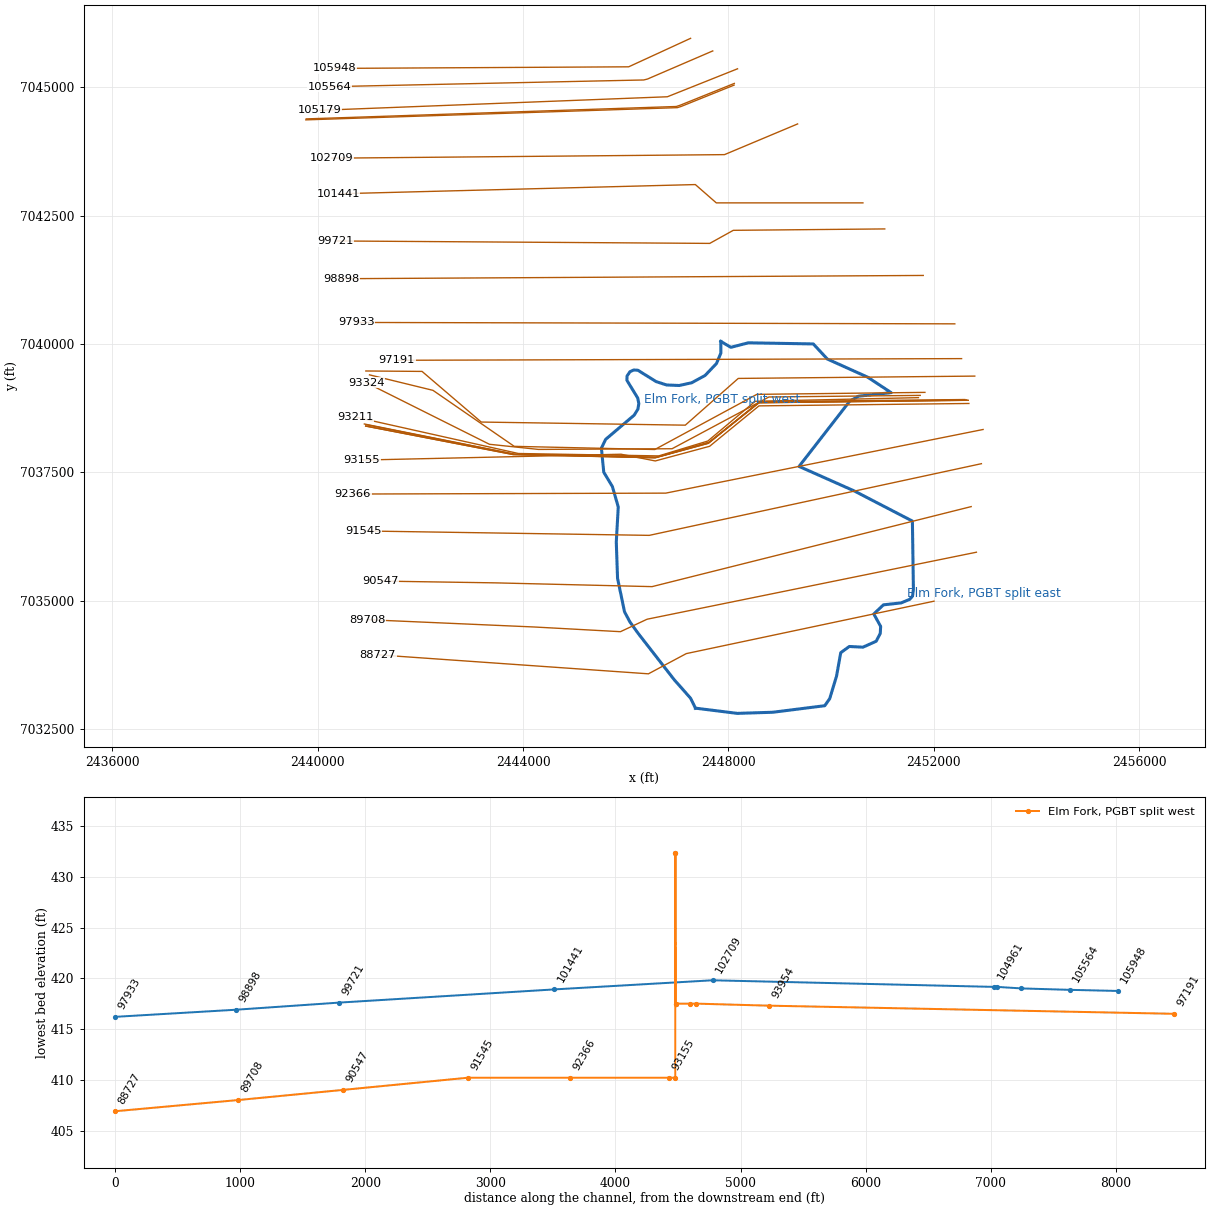
HEC-RAS study CDC_Consolidated_Model.prj: Upper Trinity CDC Consolidated Model

--- CDC_Consolidated_Model.g04 (geometry) --- (continued)

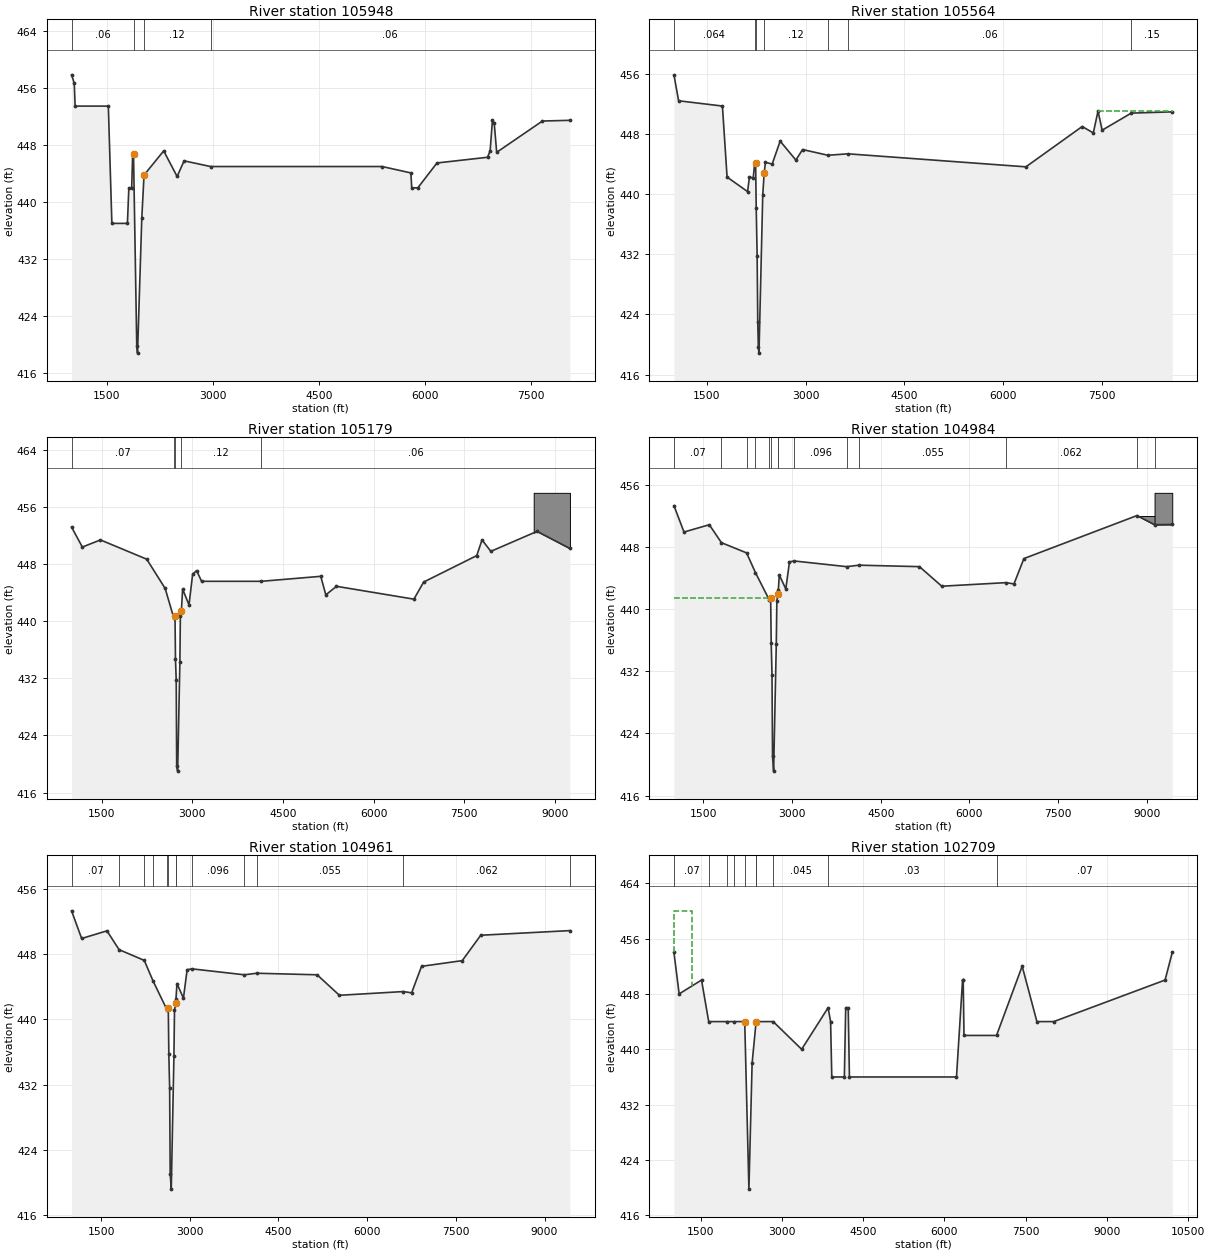
Type RM Length L Ch R = 1 ,105948  ,434,384,385
BEGIN DESCRIPTION:
This cross section corresponds to cross section 105936 of the non-georeferenced CDC model which was the source of this model.
END DESCRIPTION:
XS GIS Cut Line= 3
2447261.761020667045957.092224462446056.025899357045402.07004055
2440333.456307777045370.96642822
#Sta/Elev= 30
    1000   457.9    1038   456.7    1050   453.5    1520   453.5    1570     437
    1790     437    1810     442    1850     442    1864   446.7    1876   446.8
    1922   419.8    1933  418.75    1993   437.7    2025   443.8    2303   447.2
    2493   443.6    2592   445.8    2966     445    5393     445    5800   444.1
    5812     442    5898     442    6169   445.5    6884   446.3    6921   447.2
    6954   451.5    6979   451.1    7014     447    7661   451.4    8050   451.5
#Mann= 4 ,-1,0
    1000     .06       0    1876     .05       0    2025     .12       0
    2966     .06       0
#XS Ineff= 3 ,-1
    1000    1876   446.8    2025    6954   443.8    6954    8050   451.5
Permanent Ineff=
       F       F       F
Bank Sta=1876,2025
XS Rating Curve= 0 ,0
Exp/Cntr=0.3,0.1

Type RM Length L Ch R = 1 ,105564  ,436,385,385
BEGIN DESCRIPTION:
This cross section corresponds to cross section 105600 of the non-georeferenced CDC model which was the source of this model.
Interpolated cross-section.
END DESCRIPTION:
XS GIS Cut Line= 4
2447693.509501017045711.683266462446421.248922177045163.56658055
2446349.58863243 7045145.66602582440235.841673587045014.70926672
#Sta/Elev= 30
    1000  455.85 1070.85   452.4 1736.83   451.7 1807.68  442.26 2119.41  440.33
 2147.74   442.3 2204.43  442.12 2226.05     444 2241.27  444.18 2250.61   438.1
  2264.6  431.82 2273.93  423.04 2282.69  419.61 2292.59  418.86 2349.85  439.89
 2371.49   442.8 2390.77  444.23    2493  443.99 2614.51  447.04  2853.3  444.52
 2955.22  445.92 3340.26  445.16 3646.38  445.35 6349.51  443.62 7205.06  448.98
  7373.9  448.13 7445.97  451.04 7507.74  448.49 7950.43  450.76 8574.32  450.93
#Mann= 7 ,-1,0
    1000    .064       0 2226.05    .072       0 2241.27     .05       0
 2371.49     .12       0 3340.26    .066       0 3646.38     .06       0
 7950.43     .15       0
#XS Ineff= 3 ,-1
    1000 2241.27  444.18 2371.49 7445.97   442.8 7445.97 8574.32  451.04
Permanent Ineff=
       F       F       F
#Block Obstruct= 2 , 0
       0                    7950       0     458
Bank Sta=2241.27,2371.49
XS Rating Curve= 0 ,0
Exp/Cntr=0.3,0.1

Type RM Length L Ch R = 1 ,105179  ,132,195,97
BEGIN DESCRIPTION:
This cross section corresponds to cross section 105167 of the non-georeferenced CDC model which was the source of this model.
END DESCRIPTION:
XS GIS Cut Line= 3
2448176.333010447045363.731206462446809.859037347044818.43997422
2440036.274159347044554.02285214
#Sta/Elev= 30
    1000   453.2    1178   450.4    1478   451.4    2244   448.7    2549   444.6
    2691   440.5    2712   440.8    2720   434.7    2732   431.8    2740   419.7
    2756     419    2793   434.3    2801   440.8    2818   441.5    2838   444.5
    2944   442.3    3004   446.6    3070   447.1    3152   445.6    4140   445.6
    5125   446.3    5209   443.7    5385   444.9    6667   443.1    6829   445.5
    7707   449.2    7795   451.4    7941   449.8    8706   452.6    9250   450.2
#Mann= 5 ,-1,0
    1000     .07       0    2691      .1       0    2712     .05       0
    2818     .12       0    4140     .06       0
#Block Obstruct= 1 ,-1
    8650    9250     458
Bank Sta=2712,2818
XS Rating Curve= 0 ,0
Exp/Cntr=0.3,0.1

Type RM Length L Ch R = 1 ,104984  ,23,23,23
BEGIN DESCRIPTION:
This cross section corresponds to cross section 104750 of the non-georeferenced CDC model which was the source of this model.
Copy of cross-section 104700.
-------------------------------------
CDC COP070199-01 Windsor Estates
Cross-section 104750 - 105600
Located in ROB west of Denton Creek.
------------------------------------
END DESCRIPTION:
XS GIS Cut Line= 4
2448113.084121177045078.379086882447057.470746857044653.08531804
2446982.141501167044628.758923132439775.045022997044387.18558738
#Sta/Elev= 30
 1001.58  453.35 1171.64  449.95 1599.66  450.89 1804.88  448.58 2230.58  447.26
 2380.82  444.71 2617.17  441.16 2637.23   441.4 2646.37   435.7 2660.08  431.59
 2669.21  421.07 2687.48  419.15 2732.44  435.47 2742.16  441.12 2762.81  441.97
 2767.32   442.5 2783.54  444.41 2893.42  442.62 2955.61  446.11  3036.4  446.22
 3923.04  445.49 4133.14  445.68 5154.15  445.49 5531.46  442.97 6614.39  443.43
 6752.52  443.27 6920.44  446.53 8832.78  452.07    9130   450.9 9429.95  450.92
#Mann= 14 ,-1,0
 1001.58     .07       0 1804.88    .076       0 2230.58    .089       0
 2380.82    .096       0 2617.17    .091       0 2637.23     .05       0
 2762.81    .106       0 2767.32    .116       0  3036.4    .096       0
 3923.04    .062       0 4133.14    .055       0 6614.39    .062       0
 8832.78    .025       0    9130     .15       0
#XS Ineff= 2 , 0
       02637.235441.4023 2762.81       0  441.97
Permanent Ineff=
       F       F
#Block Obstruct= 2 ,-1
    8830    9130     452    9130  9429.5     455
Bank Sta=2637.23,2762.81
XS Rating Curve= 0 ,0
Exp/Cntr=0.3,0.1

Type RM Length L Ch R = 1 ,104961  ,1362,2252,998
BEGIN DESCRIPTION:
This cross section corresponds to cross section 104700 of the non-georeferenced CDC model which was the source of this model.
Interpolated cross-section.
END DESCRIPTION:
XS GIS Cut Line= 4
2448109.035572837045045.457892882447078.592751837044629.84028579
2447002.81534433 7044606.01553032439768.890507767044368.21974605
#Sta/Elev= 30
 1001.58  453.35 1171.64  449.95 1599.66  450.89 1804.88  448.58 2230.58  447.26
 2380.82  444.71 2617.17  441.16 2637.23   441.4 2646.37   435.7 2660.08  431.59
 2669.21  421.07 2687.48  419.15 2732.44  435.47 2742.16  441.12 2762.81  441.97
 2767.32   442.5 2783.54  444.41 2893.42  442.62 2955.61  446.11  3036.4  446.22
 3923.04  445.49 4133.14  445.68 5154.15  445.49 5531.46  442.97 6614.39  443.43
 6752.52  443.27 6920.44  446.53 7608.72  447.23 7921.76  450.35 9429.95  450.92
#Mann= 13 ,-1,0
 1001.58     .07       0 1804.88    .076       0 2230.58    .089       0
 2380.82    .096       0 2617.17    .091       0 2637.23     .05       0
 2762.81    .106       0 2767.32    .116       0  3036.4    .096       0
 3923.04    .062       0 4133.14    .055       0 6614.39    .062       0
 9429.95    .062       0
Bank Sta=2637.23,2762.81
XS Rating Curve= 0 ,0
Exp/Cntr=0.3,0.1

Type RM Length L Ch R = 1 ,102709  ,907,1268,605
BEGIN DESCRIPTION:
This cross section corresponds to cross section 102686 of the non-georeferenced CDC model which was the source of this model.
pond 1650-1990, forest 2110-2260,2530-2840
----------------------------------------------------------
XS 102709 to 97192 retored  to  to 1991 topo  to remove CAR 062309-01
END DESCRIPTION:
XS GIS Cut Line= 3
 2449346.20501457044288.79208338 2447922.35189117043690.69715096
2440269.43379802 7043621.4781293
#Sta/Elev= 30
  1008.4     454  1104.3     448  1517.4     450    1650     444    1990     444
    2110     444  2314.8     444    2392   419.8  2451.2     438  2524.8     444
    2530     444    2840     444  3365.7     440  3853.3     446  3899.7     444
  3921.7     436  4153.8     436  4178.4     446  4224.8     446  4247.2     436
  6223.3     436  6335.2     450  6347.4     450  6361.7     442  6962.2     442
  7435.4     452  7707.4     444  8018.6     444   10073     450   10206     454
#Mann= 10 ,-1,0
  1008.4     .07       0    1650     .04       0    1990     .07       0
    2110      .1       0  2314.8     .05       0  2524.8    .045       0
    2530      .1       0    2840    .045       0  3853.3     .03       0
  6962.2     .07       0
#XS Ineff= 2 , 0
       0    1350     460               0
Permanent Ineff=
       F       F
Bank Sta=2314.8,2524.8
XS Rating Curve= 0 ,0
Exp/Cntr=0.3,0.1

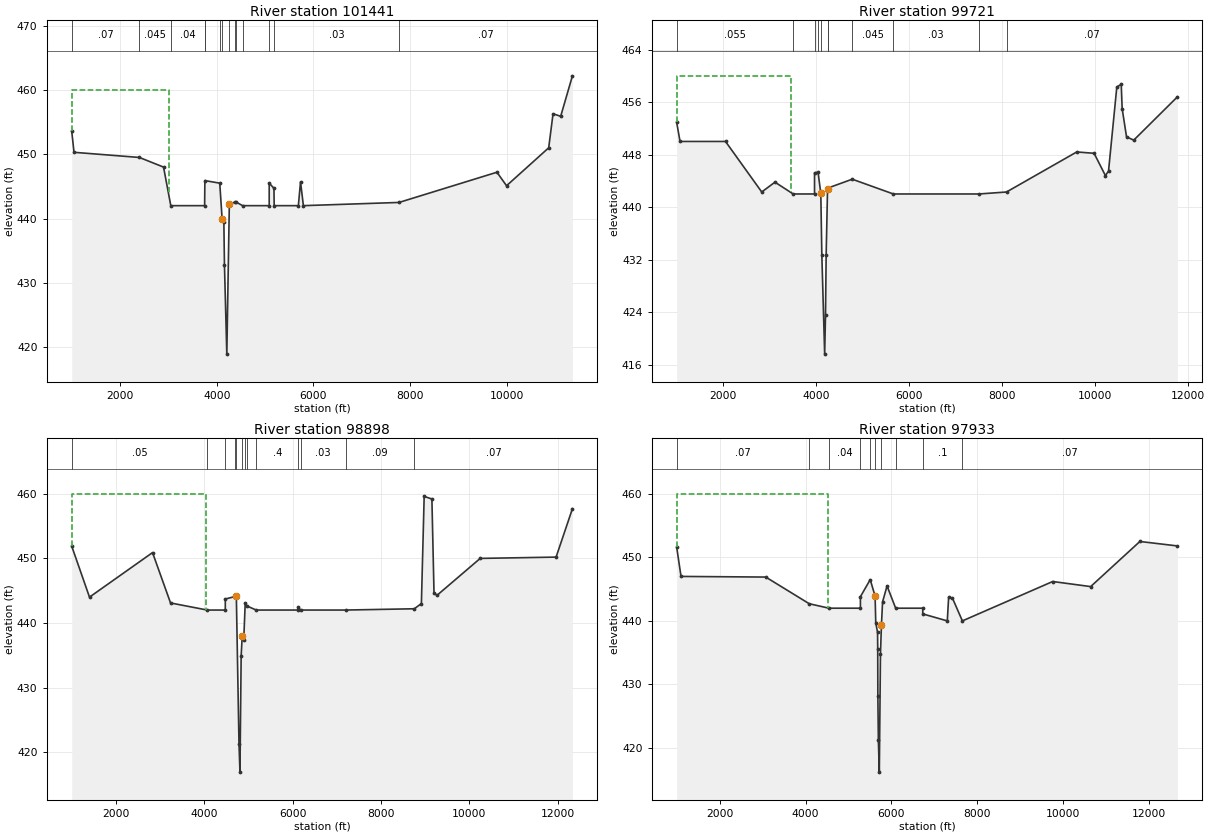
Type RM Length L Ch R = 1 ,101441  ,930,1720,870
BEGIN DESCRIPTION:
This cross section corresponds to cross section 101428 of the non-georeferenced CDC model which was the source of this model.
END DESCRIPTION:
XS GIS Cut Line= 4
2450618.600107497042750.521209812447762.271830687042750.52120981
2447354.618118447043107.218002962440395.945027927042927.45786379
#Sta/Elev= 30
    1000   453.6    1048   450.3    2400   449.5    2900     448    3050     442
    3750     442    3755   445.9    4063   445.5    4111     440    4148   439.4
    4160   432.8    4209   418.9    4261   442.2    4387   442.6    4390   442.6
    4537     442    5086     442    5086   445.5    5184   444.7    5189     442
    5689     442    5734   445.7    5793     442    7772   442.5    9797   447.2
    9996   445.1   10868     451   10958   456.3   11116   455.9   11359   462.2
#Mann= 14 ,-1,0
    1000     .07       0    2400    .045       0    3050     .04       0
    3750      .1       0    3755      .1       0    4063      .1       0
    4111     .05       0    4261      .1       0    4387    .045       0
    4390      .1       0    4537     .04       0    5086    .045       0
    5189     .03       0    7772     .07       0
#XS Ineff= 2 , 0
       0    3008     460               0
Permanent Ineff=
       F       F
Bank Sta=4111,4261
XS Rating Curve= 0 ,0
Exp/Cntr=0.3,0.1

Type RM Length L Ch R = 1 ,99721   ,899,823,899
BEGIN DESCRIPTION:
This cross section corresponds to cross section 99708 of the non-georeferenced CDC model which was the source of this model.
END DESCRIPTION:
XS GIS Cut Line= 4
2451043.622879517042242.79223838 2448093.4909845 7042215.4750358
2447634.88002509 7041960.69208082440342.924792777042008.16147405
#Sta/Elev= 30
    1000   452.9    1072     450    2050     450    2829   442.3    3113   443.8
    3505     442    3964     442    3964  445.23    4040   445.3    4099   442.1
    4121   432.7    4182   417.6    4200   423.5    4214   432.7    4244   442.8
    4250   442.9    4775  444.25    5659     442    7500     442    8092   442.3
    9602   448.4    9975   448.2   10219   444.8   10286   445.5   10464   458.3
   10559   458.7   10579     455   10673   450.7   10828   450.2   11767   456.8
#Mann= 11 ,-1,0
    1000    .055       0    3505     .04       0    3964      .1       0
    4040    .055       0    4099     .05       0    4244    .045       0
    4250      .1       0    4775    .045       0    5659     .03       0
    7500     .09       0    8092     .07       0
#XS Ineff= 2 , 0
       0    3453     460               0
Permanent Ineff=
       F       F
Bank Sta=4099,4244
XS Rating Curve= 0 ,0
Exp/Cntr=0.3,0.1

Type RM Length L Ch R = 1 ,98898   ,920,965,900
BEGIN DESCRIPTION:
This cross section corresponds to cross section 98884 of the non-georeferenced CDC model which was the source of this model.
END DESCRIPTION:
XS GIS Cut Line= 2
2451793.58496225 7041336.08112532440455.763149777041272.52350964
#Sta/Elev= 30
    1000   451.9    1403     444    2830   450.9    3238   443.1    4070     442
    4478     442    4478  443.71    4700   444.1    4728   444.1    4788   421.3
    4810   416.9    4837   434.9    4861     438    4895   437.3    4929   443.1
    4960  442.65    5179     442    6130     442    6130   442.4    6184     442
    7200     442    8757   442.2    8918     443    8981   459.6    9156   459.2
    9204   444.6    9275   444.3   10250     450   11968   450.2   12338   457.7
#Mann= 13 ,-1,0
    1000     .05       0    4070     .04       0    4478      .1       0
    4700     .05       0    4728    .045       0    4861      .1       0
    4929    .045       0    4960      .1       0    5179      .4       0
    6130    .045       0    6184     .03       0    7200     .09       0
    8757     .07       0
#XS Ineff= 2 , 0
       0    4030     460               0
Permanent Ineff=
       F       F
Bank Sta=4728,4861
XS Rating Curve= 0 ,0
Exp/Cntr=0.3,0.1

Type RM Length L Ch R = 1 ,97933   ,701,742,701
BEGIN DESCRIPTION:
This cross section corresponds to cross section 97919 of the non-georeferenced CDC model which was the source of this model.
END DESCRIPTION:
XS GIS Cut Line= 2
2452408.071922247040392.980977392440749.103770437040420.18794397
#Sta/Elev= 30
    1000   451.6    1101     447    3074   446.9    4087   442.7    4547     442
    5278     442    5278  443.81    5506   446.5    5620   443.9    5635   439.7
    5677   438.2    5681   435.5    5684   428.2    5696   421.2    5718   416.2
    5745   434.8    5767   439.3    5794     443    5898   445.5    6099     442
    6730     442    6730   441.1    7301     440    7332   443.7    7420   443.6
    7652     440    9755   446.2   10639   445.4   11785   452.5   12659   451.8
#Mann= 10 ,-1,0
    1000     .07       0    4087     .05       0    4547     .04       0
    5278      .1       0    5506      .1       0    5620     .05       0
    5767      .1       0    6099     .04       0    6730      .1       0
    7652     .07       0
#XS Ineff= 2 , 0
       0    4517     460               0
Permanent Ineff=
       F       F
Bank Sta=5620,5767
XS Rating Curve= 0 ,0
Exp/Cntr=0.3,0.1

River Reach=Elm Fork        ,PGBT split west
Reach XY= 30
      2447850.52      7040050.17      2447851.28      7039823.18
       2447765.5      7039618.88      2447543.86      7039386.42
      2447283.34      7039244.82      2447041.73      7039191.65
      2446794.53      7039201.31      2446590.32      7039267.69
      2446235.77      7039488.35      2446154.21      7039493.36
      2446079.96      7039459.22       2446023.8      7039374.59
      2446021.19      7039292.91      2446232.21      7038946.89
       2446253.3       7038838.4      2446235.52      7038729.33
      2446162.43      7038612.58      2445606.85      7038140.69
       2445524.8      7037970.04       2445570.8       7037501.1
      2445738.38      7037223.01      2445853.15       7036823.6
       2445814.6      7036141.12      2445839.38      7035433.75
       2445974.7      7034782.32      2446080.86      7034582.01
      2446241.32      7034359.76      2446941.68      7033458.66
      2447261.03       7033097.4      2447356.93      7032903.31

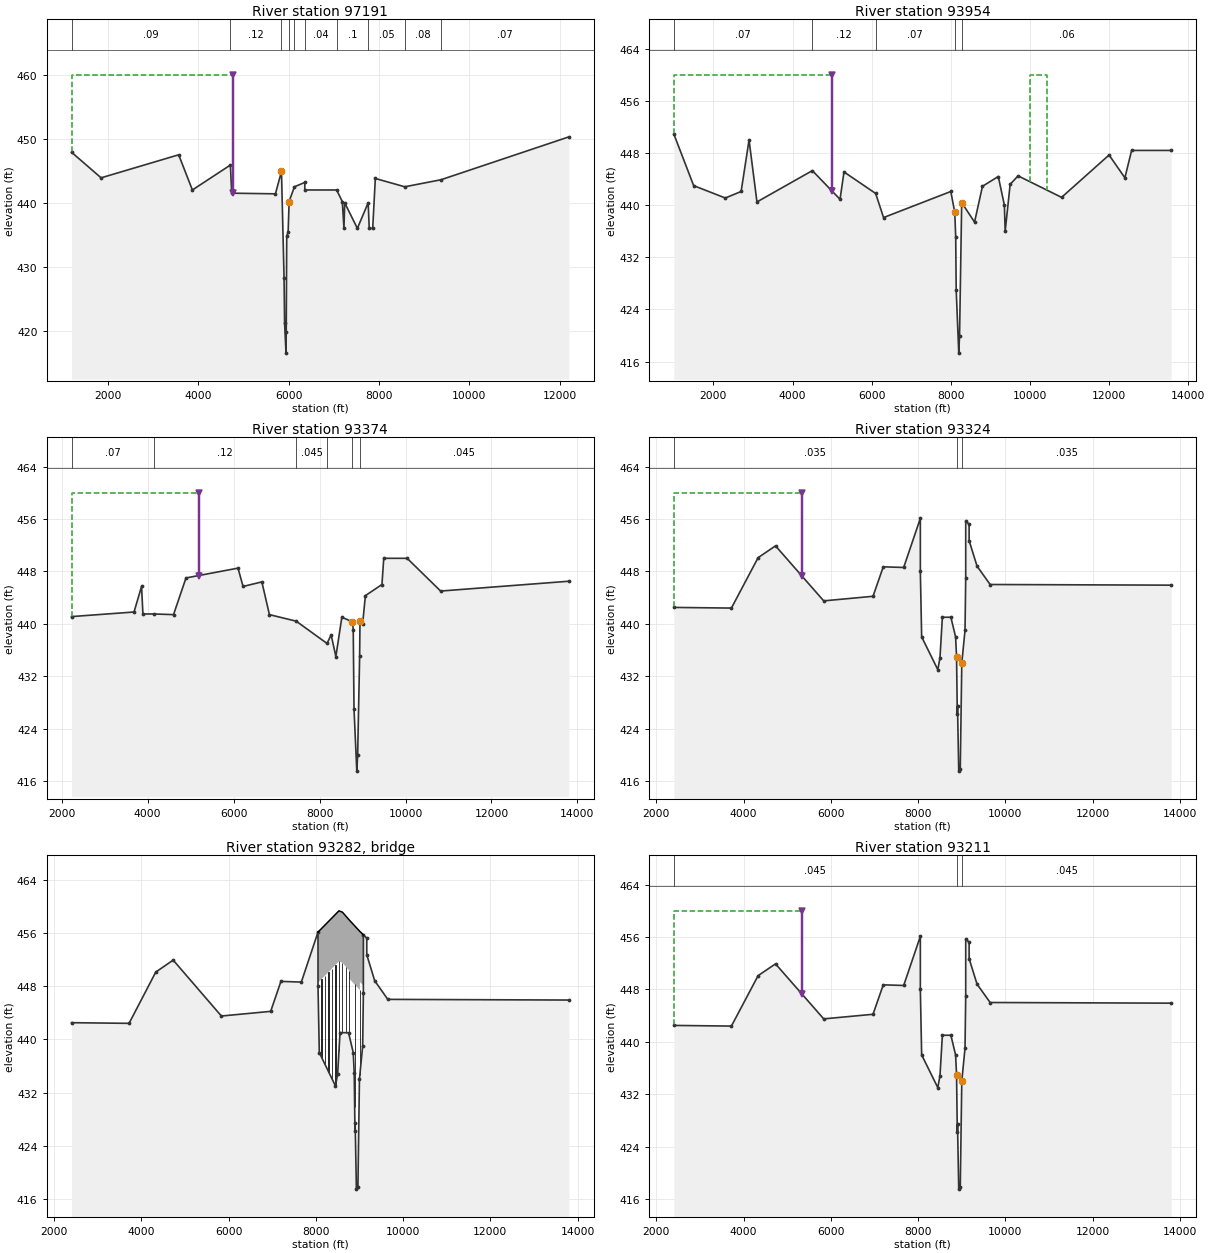
Type RM Length L Ch R = 1 ,97191   ,2199,3237,1350
BEGIN DESCRIPTION:
This cross section corresponds to cross section 97178 of the non-georeferenced CDC model which was the source of this model.
END DESCRIPTION:
XS GIS Cut Line= 2
2452539.652695837039715.174918292441539.700942527039682.66481271
#Sta/Elev= 30
    1200   447.9    1854   443.9    3570   447.5    3873     442    4714   445.9
    4743   441.5    5710   441.4    5844   444.9    5901   428.2    5913   421.2
    5944   416.5    5949   419.8    5960   434.8    5991   435.4    6013   440.2
    6130   442.5    6360  443.18    6360     442 7064.45     442    7189   440.2
  7225.9     436  7241.9     440  7522.7     436  7761.2     440  7785.3     436
  7861.8     436  7919.6   443.8    8571   442.5    9372   443.6   12200   450.3
#Mann= 10 ,-1,0
    1200     .09       0    4714     .12       0    5844     .05       0
    6013    .045       0    6130      .1       0    6360     .04       0
 7064.45      .1       0  7761.2     .05       0    8571     .08       0
    9372     .07       0
Levee=-1,4780,460,0,,,,
#XS Ineff= 2 , 0
       0    4780     460               0
Permanent Ineff=
       F       F
Bank Sta=5844,6013
XS Rating Curve= 0 ,0
Exp/Cntr=0.3,0.1

Type RM Length L Ch R = 1 ,93954   ,649,580,459
BEGIN DESCRIPTION:
This cross section corresponds to cross section 93940 of the non-georeferenced CDC model which was the source of this model.
--------------------------------------------
CDC CAR062309-1 WTP Pre-Sedimentation Basins
Cross-section 93940 - 105167
--------------------------------------------
Bridge blocked ROB as part of the project for SPF only.
No other impacts to 100-year or SPF conveyance models.
--------------------------------------------
CDC Cop 050812-01 River Oaks Assisted Living and Memory Care
Cross-section 93359 - 93940
Located in ROB.
--------------------------------------------
END DESCRIPTION:
XS GIS Cut Line= 6
  2452796.764058     7039374.541 2448190.2778644     7039329.194
 2447158.7989563     7038418.323 2443184.5719966     7038479.048
 2442031.7429374     7039465.8252440936.74876567 7039474.2485852
#Sta/Elev= 30
    1000   450.9    1500     443    2300   441.1    2700   442.1    2900     450
    3100   440.5    4500   445.3    5200   440.9    5300   445.1    6100   441.8
    6300   438.1    8000   442.1    8100   438.9    8124   435.1    8136     427
    8201   417.3    8221     420    8275   440.4    8600   437.4    8800   442.9
    9200   444.4    9354     440    9374     436    9500   443.2    9700   444.5
   10800   441.2   12000   447.7   12400   444.2   12570   448.4   13570   448.4
#Mann= 5 ,-1,0
    1000     .07       0    4500     .12       0    6100     .07       0
    8100     .05       0    8275     .06       0
Levee=-1,5000,460,0,,,,
#XS Ineff= 2 ,-1
    1000    5000     460   10000   10426     460
Permanent Ineff=
       F       F
Bank Sta=8100,8275
XS Rating Curve= 0 ,0
Exp/Cntr=0.3,0.1

Type RM Length L Ch R = 1 ,93374   ,50,50,50
BEGIN DESCRIPTION:
This cross section corresponds to cross section 93359 of the non-georeferenced CDC model which was the source of this model.
END DESCRIPTION:
XS GIS Cut Line= 6
2451825.857535517039057.255302382448551.367037277039018.65006463
2446565.057033517037943.830035812443827.059884857038005.64520088
2442244.274008427039096.973070712441008.350427037039398.64766707
#Sta/Elev= 30
    2230   441.1    3684   441.8    3859   445.7    3891   441.5    4146   441.5
    4603   441.4    4893     447    6103   448.5    6221   445.7    6658   446.4
    6834   441.4    7457   440.4    8174     437    8270   438.3    8380     435
    8519     441    8766   440.3    8784   439.1    8802     427    8867   417.5
    8887     420    8933   435.1    8941   440.4    9002     440    9067   444.3
    9452     446    9494     450   10038     450   10817     445   13800   446.5
#Mann= 6 ,-1,0
    2230     .07       0    4146     .12       0    7457    .045       0
    8174    .035       0    8766     .05       0    8941    .045       0
Levee=-1,5190,460,0,,,,
#XS Ineff= 2 , 0
       0    5190     460               0
Permanent Ineff=
       F       F
Bank Sta=8766,8941
XS Rating Curve= 0 ,0
Exp/Cntr=0.3,0.1

Type RM Length L Ch R = 1 ,93324   ,113,113,113
BEGIN DESCRIPTION:
This cross section corresponds to cross section 93297 of the non-georeferenced CDC model which was the source of this model.
Upstream bounding cross-section for Sandy Lake Road bridge
END DESCRIPTION:
XS GIS Cut Line= 6
2451734.592626187038998.613031222448786.985660497038967.59209588
2446901.668565017037959.034729792444298.008746097037945.72931021
2443344.115968857038045.839674292440940.74752348 7039248.2781476
#Sta/Elev= 30
    2400   442.5    3719   442.4    4331   450.1    4730   451.9    5835   443.5
    6965   444.2    7200   448.7    7668   448.6    8050   456.1    8050     448
    8080     438    8450     433    8500   434.8    8555     441    8750     441
    8858     438    8880     435    8897   426.3    8902   427.4    8930   417.5
    8965   417.8    9000     434    9074     439    9090     447    9090   455.7
    9168   455.2    9168   452.7    9350   448.8    9650     446   13800   445.9
#Mann= 3 ,0,0
    2400    .035       0    8880     .03       0    9000    .035       0
Levee=-1,5329,460,0,,,,
#XS Ineff= 2 , 0
       0    5329     460               0
Permanent Ineff=
       F       F
Bank Sta=8880,9000
XS Rating Curve= 0 ,0
Exp/Cntr=0.3,0.1

Type RM Length L Ch R = 3 ,93282   ,,,
BEGIN DESCRIPTION:
Sandy Lake Road
Note:  Bridge and roadway modeled from plans dated Dec. 1996 and stamped Dec. 1997.
END DESCRIPTION:
Node Name=Sandy Lake Road
Bridge Culvert--1,0,-1,-1, 0
Deck Dist Width WeirC Skew NumUp NumDn MinLoCord MaxHiCord MaxSubmerge Is_Ogee
1,83,2.6,0, 8, 8, , , 0.95, 0, ,,,
    8050    8530    8610    8770    8770    9010    9010    9090
   456.1   459.3   459.1   457.9   457.9   456.2   456.2   455.7
   448.5   451.7   451.5   450.3   449.1   447.4   448.6   448.1
    8050    8530    8610    8770    8770    9010    9010    9090
   456.1   459.3   459.1   457.9   457.9   456.2   456.2   455.7
   448.5   451.7   451.5   450.3   449.1   447.4   448.6   448.1
Pier Skew, UpSta & Num, DnSta & Num=  ,8130, 2 ,8130, 2 , 0 , 0 , 0 ,,
     2.5     2.5
     425     452
     2.5     2.5
     425     452
Pier Skew, UpSta & Num, DnSta & Num=  ,8210, 2 ,8210, 2 , 0 , 0 , 0 ,,
     2.5     2.5
     425     452
     2.5     2.5
     425     452
Pier Skew, UpSta & Num, DnSta & Num=  ,8290, 2 ,8290, 2 , 0 , 0 , 0 ,,
     2.5     2.5
     425     452
     2.5     2.5
     425     452
Pier Skew, UpSta & Num, DnSta & Num=  ,8370, 2 ,8370, 2 , 0 , 0 , 0 ,,
     2.5     2.5
     425     452
     2.5     2.5
     425     452
Pier Skew, UpSta & Num, DnSta & Num=  ,8450, 2 ,8450, 2 , 0 , 0 , 0 ,,
     2.5     2.5
     425     452
     2.5     2.5
     425     452
Pier Skew, UpSta & Num, DnSta & Num=  ,8530, 2 ,8530, 2 , 0 , 0 , 0 ,,
     2.5     2.5
     425     453
     2.5     2.5
     425     453
Pier Skew, UpSta & Num, DnSta & Num=  ,8610, 2 ,8610, 2 , 0 , 0 , 0 ,,
     2.5     2.5
     425     453
     2.5     2.5
     425     453
Pier Skew, UpSta & Num, DnSta & Num=  ,8690, 2 ,8690, 2 , 0 , 0 , 0 ,,
     2.5     2.5
     425     452
     2.5     2.5
     425     452
Pier Skew, UpSta & Num, DnSta & Num=  ,8770, 2 ,8770, 2 , 0 , 0 , 0 ,,
       3       3
     425     452
       3       3
     425     452
Pier Skew, UpSta & Num, DnSta & Num=  ,8890, 2 ,8890, 2 , 0 , 0 , 0 ,,
       3       3
     425     452
       3       3
     425     452
Pier Skew, UpSta & Num, DnSta & Num=  ,9010, 2 ,9010, 2 , 0 , 0 , 0 ,,
       3       3
     425     452
       3       3
     425     452
BR Coef= 1 , 0 , 0 ,1.05, 0 ,,,0.8,-1,0.5,1,
WSPro=,,,, 1 ,,,, 0 ,,,, 0 ,,,,-1 ,-1 ,-1 , 0 , 0 , 0 , 0 , 0
BC Design=,, 0 ,, 0 ,,,,,,
BC HTab HWMax=456.1
BC Use User HTab Curves=0
BC User HTab FreeFlow(D)= 0

Type RM Length L Ch R = 1 ,93211   ,2,3,4
BEGIN DESCRIPTION:
This cross section corresponds to cross section 93212 of the non-georeferenced CDC model which was the source of this model.
Downstream bounding cross-section for Sandy Lake Road bridge
END DESCRIPTION:
XS GIS Cut Line= 6
2451700.19735375 7038954.69809282448520.069527697038883.64377296
2447597.799390587038109.242434642446642.141196947037819.29157096
2443907.252637837037866.266214552440736.861069247038575.79107872
#Sta/Elev= 30
    2400   442.5    3719   442.4    4331   450.1    4730   451.9    5835   443.5
    6965   444.2    7200   448.7    7668   448.6    8050   456.1    8050     448
    8080     438    8450     433    8500   434.8    8555     441    8750     441
    8858     438    8880     435    8897   426.3    8902   427.4    8930   417.5
    8965   417.8    9000     434    9074     439    9090     447    9090   455.7
    9168   455.2    9168   452.7    9350   448.8    9650     446   13800   445.9
#Mann= 3 ,0,0
    2400    .045       0    8880     .05       0    9000    .045       0
Levee=-1,5329,460,0,,,,
#XS Ineff= 2 , 0
       0    5329     460               0
Permanent Ineff=
       F       F
Bank Sta=8880,9000
XS Rating Curve= 0 ,0
Exp/Cntr=0.3,0.1

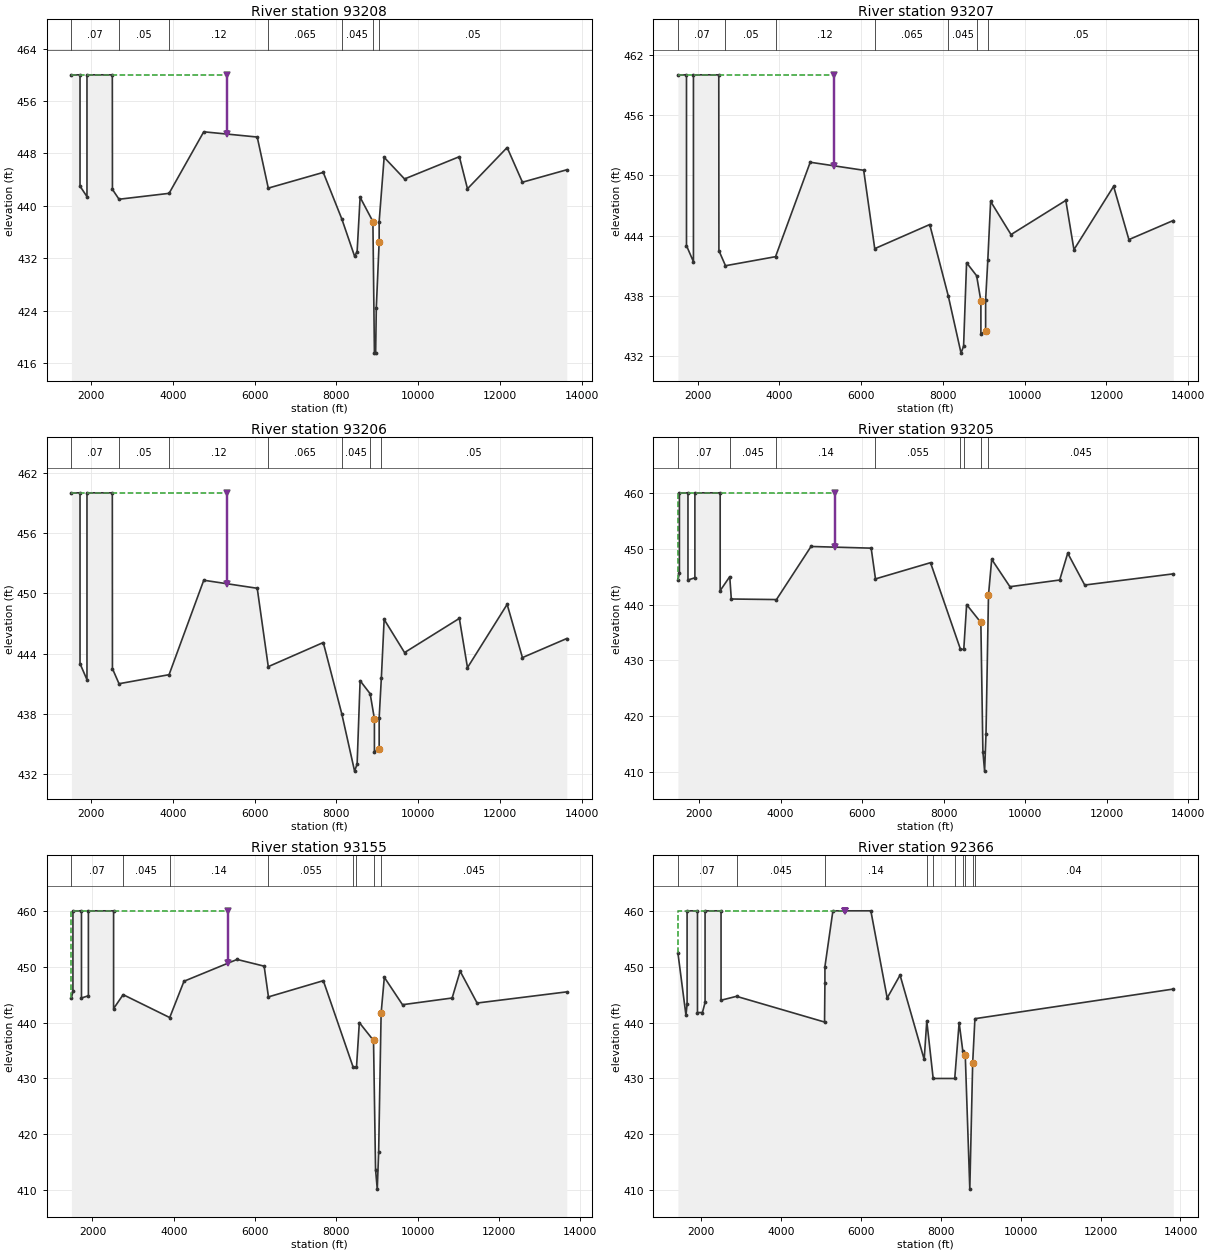
Type RM Length L Ch R = 1 ,93208   ,1,1,1
BEGIN DESCRIPTION:
This cross section corresponds to cross section 93197 of the non-georeferenced CDC model which was the source of this model.
END DESCRIPTION:
XS GIS Cut Line= 6
2452600.490828757038917.960305382448624.117547937038876.03912938
2447622.075260677038085.549240542446594.051726167037793.92941697
2443835.875484027037852.248854132440907.53596965  7038441.053893
#Sta/Elev= 30
    1520     460    1730     460    1730     443    1900   441.4    1900     460
    2520     460    2523   442.5    2684     441    3908   441.9    4756   451.3
    6064   450.5    6334   442.7    7679   445.1    8132     438    8445   432.3
    8507     433    8580   441.3    8893   437.6    8930   417.5    8960   417.5
    8976   424.4    9046   434.5    9046   437.6    9168   447.4    9667   444.1
   11007   447.5   11206   442.6   12176   448.9   12550   443.6   13635   445.5
#Mann= 7 ,-1,0
    1520     .07       0    2684     .05       0    3908     .12       0
    6334    .065       0    8132    .045       0    8893     .05       0
    9046     .05       0
Levee=-1,5329,460,0,,,,
#XS Ineff= 2 , 0
       0    5329     460               0
Permanent Ineff=
       F       F
Bank Sta=8893,9046
XS Rating Curve= 0 ,0
Exp/Cntr=0.3,0.1

Type RM Length L Ch R = 1 ,93207   ,1,1,1
BEGIN DESCRIPTION:
This cross section corresponds to cross section 93196 of the non-georeferenced CDC model which was the source of this model.
END DESCRIPTION:
XS GIS Cut Line= 6
2452641.390353267038908.900284132448592.968660097038861.20648189
2447619.803611677038082.320244392446590.514987837037792.19451229
2443830.769195027037851.319065972440941.944247077038428.13162729
#Sta/Elev= 30
    1520     460    1730     460    1730     443    1900   441.4    1900     460
    2520     460    2523   442.5    2684     441    3908   441.9    4756   451.3
    6064   450.5    6334   442.7    7679   445.1    8132     438    8445   432.3
    8507     433    8580   441.3    8826     440    8930   437.5    8930   434.2
    9046   434.5    9046   437.6    9100   441.6    9168   447.4    9667   444.1
   11007   447.5   11206   442.6   12176   448.9   12550   443.6   13635   445.5
#Mann= 7 ,-1,0
    1520     .07       0    2684     .05       0    3908     .12       0
    6334    .065       0    8132    .045       0    8826     .02       0
    9100     .05       0
Levee=-1,5329,460,0,,,,
#XS Ineff= 2 , 0
       0    5329     460               0
Permanent Ineff=
       F       F
Bank Sta=8930,9046
XS Rating Curve= 0 ,0
Exp/Cntr=0.3,0.1

Type RM Length L Ch R = 1 ,93206   ,1,1,1
BEGIN DESCRIPTION:
This cross section corresponds to cross section 93191 of the non-georeferenced CDC model which was the source of this model.
END DESCRIPTION:
XS GIS Cut Line= 6
2452633.708610097038904.114532552448582.513956587038855.67696539
2447608.631061857038066.236943222446572.952030847037783.50916222
2443805.37685734 7037846.64322232440933.827626397038401.55917062
#Sta/Elev= 30
    1520     460    1730     460    1730     443    1900   441.4    1900     460
    2520     460    2523   442.5    2684     441    3908   441.9    4756   451.3
    6064   450.5    6334   442.7    7679   445.1    8132     438    8445   432.3
    8507     433    8580   441.3    8826     440    8930   437.5    8930   434.2
    9046   434.5    9046   437.6    9100   441.6    9168   447.4    9667   444.1
   11007   447.5   11206   442.6   12176   448.9   12550   443.6   13635   445.5
#Mann= 7 ,-1,0
    1520     .07       0    2684     .05       0    3908     .12       0
    6334    .065       0    8132    .045       0    8826     .02       0
    9100     .05       0
Levee=-1,5329,460,0,,,,
#XS Ineff= 2 , 0
       0    5329     460               0
Permanent Ineff=
       F       F
Bank Sta=8930,9046
XS Rating Curve= 0 ,0
Exp/Cntr=0.3,0.1

Type RM Length L Ch R = 1 ,93205   ,50,50,50
BEGIN DESCRIPTION:
This cross section corresponds to cross section 93190 of the non-georeferenced CDC model which was the source of this model.
END DESCRIPTION:
XS GIS Cut Line= 6
   2452670.74636   7038903.30167     2448582.553     7038854.674
      2447608.67     7038065.234     2446572.991     7037782.506
     2443805.416     7037845.6412440933.865646337038400.55714905
#Sta/Elev= 30
    1483   444.4    1520   445.6    1520     460    1730     460    1730   444.4
    1900   444.8    1900     460    2520     460    2520   442.5    2755     445
    2793     441    3901   440.9    4749   450.4    6224   450.1    6330   444.6
    7680   447.5    8415     432    8496     432    8566     440    8915   436.8
    8965   413.7    9007   410.2    9041   416.8    9102   441.7    9181   448.1
    9628   443.2   10849   444.4   11046   449.2   11463   443.5   13635   445.5
#Mann= 8 ,-1,0
    1483     .07       0    2755    .045       0    3901     .14       0
    6330    .055       0    8415    .035       0    8496     .12       0
    8915     .05       0    9102    .045       0
Levee=-1,5329,460,0,,,,
#XS Ineff= 2 , 0
       0    5329     460               0
Permanent Ineff=
       F       F
Bank Sta=8915,9102
XS Rating Curve= 0 ,0
Exp/Cntr=0.3,0.1

Type RM Length L Ch R = 1 ,93155   ,759,789,739
BEGIN DESCRIPTION:
This cross section corresponds to cross section 93141 of the non-georeferenced CDC model which was the source of this model.
END DESCRIPTION:
XS GIS Cut Line= 6
 2452682.0648126 7038840.95028882448594.03788367 7038794.2240043
2447632.440069357038006.71606489  2446574.4408737037721.01223996
2445907.796865087037851.96014079 2440858.56340847037737.79077835
#Sta/Elev= 30
    1483   444.4    1520   445.6    1520     460    1730     460    1730   444.4
    1900   444.8    1900     460    2520     460    2520   442.5    2755     445
    3901   440.9    4252   447.4    5558   451.3    6224   450.1    6330   444.6
    7680   447.5    8415     432    8496     432    8566     440    8915   436.8
    8965   413.7    9007   410.2    9041   416.8    9102   441.7    9181   448.1
    9628   443.2   10849   444.4   11046   449.2   11463   443.5   13670   445.5
#Mann= 8 ,-1,0
    1483     .07       0    2755    .045       0    3901     .14       0
    6330    .055       0    8415    .035       0    8496     .12       0
    8915     .05       0    9102    .045       0
Levee=-1,5329,460,0,,,,
#XS Ineff= 2 , 0
       0    5329     460               0
Permanent Ineff=
       F       F
Bank Sta=8915,9102
XS Rating Curve= 0 ,0
Exp/Cntr=0.3,0.1

Type RM Length L Ch R = 1 ,92366   ,820,821,820
BEGIN DESCRIPTION:
This cross section corresponds to cross section 92351 of the non-georeferenced CDC model which was the source of this model.
END DESCRIPTION:
XS GIS Cut Line= 4
2452958.679744937038334.056289462446778.237053337037093.70312713
2441681.935894257037078.872448132440681.94012853 7037075.9623736
#Sta/Elev= 30
    1420   452.5    1622   441.3    1650   443.3    1650     460    1910     460
    1910   441.8    2034   441.8    2100   443.6    2100     460    2500     460
    2500     444    2887   444.7    5091   440.1    5100     447    5100     450
    5300     460    6250     460    6659   444.4    6981   448.5    7585   433.4
    7650   440.3    7810     430    8350     430    8460     440    8550     435
    8613   434.2    8727   410.2    8799   432.8    8855   440.7   13820     446
#Mann= 10 ,-1,0
    1420     .07       0    2887    .045       0    5100     .14       0
    7650     .05       0    7810     .03       0    8350     .05       0
    8550     .14       0    8613     .05       0    8799     .14       0
    8855     .04       0
Levee=-1,5608,460,0,,,,
#XS Ineff= 2 , 0
       0    5608     460               0
Permanent Ineff=
       F       F
Bank Sta=8613,8799
XS Rating Curve= 0 ,0
Exp/Cntr=0.3,0.1

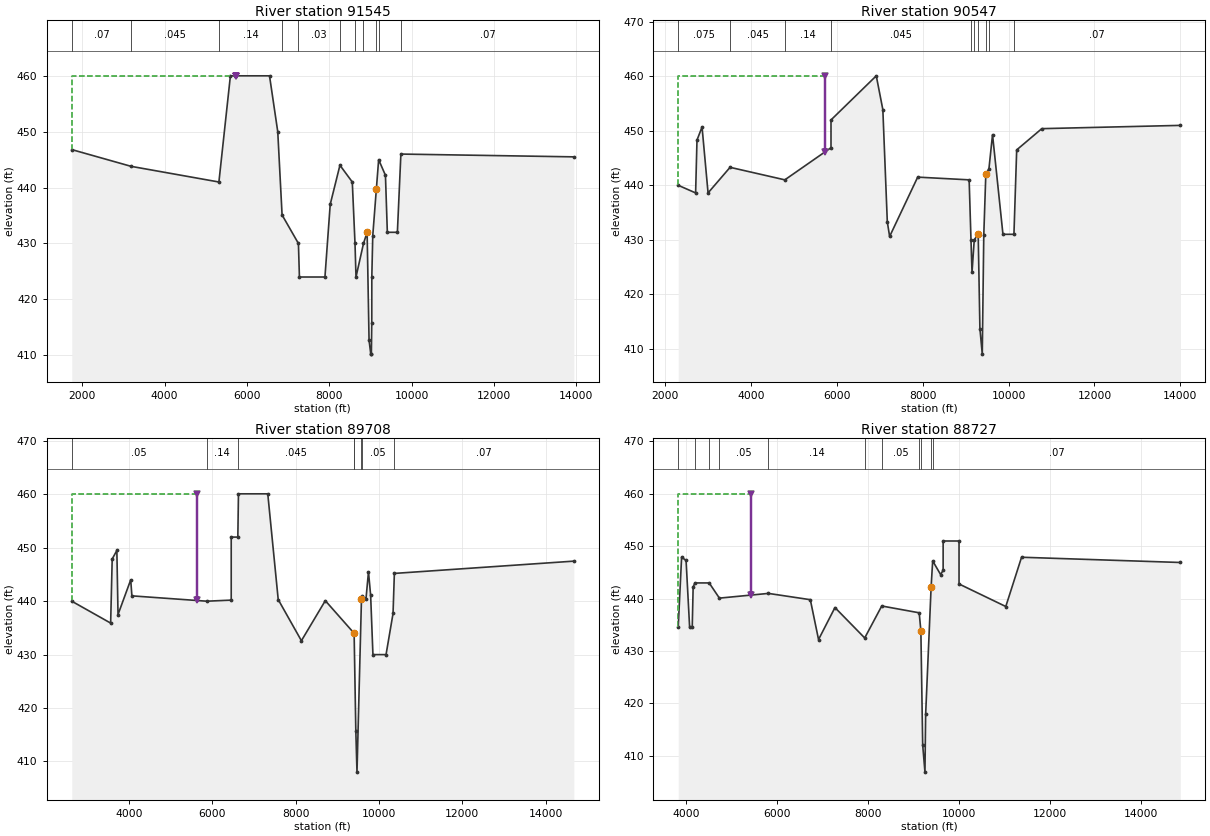
Type RM Length L Ch R = 1 ,91545   ,1000,998,1000
BEGIN DESCRIPTION:
This cross section corresponds to cross section 91530 of the non-georeferenced CDC model which was the source of this model.
END DESCRIPTION:
XS GIS Cut Line= 4
2452926.00067642 7037667.63373782446457.170110177036270.74315888
2441883.650057767036341.302400962440883.769044657036356.72834108
#Sta/Elev= 30
    1748   446.8    3190   443.8    5321     441    5600     460    6550     460
    6750     450    6855   435.1    7252     430    7276     424    7896     424
    8024     437    8260     444    8560     441    8626     430    8650     424
    8832     430    8920     432    8967   412.7    9009   410.2    9023   410.2
    9033   415.8    9034     424    9057   431.4    9145   439.8    9200     445
    9365   442.2    9411     432    9655     432    9740     446   13940   445.5
#Mann= 11 ,-1,0
    1748     .07       0    3190    .045       0    5321     .14       0
    6855    .035       0    7252     .03       0    8260    .045       0
    8626     .03       0    8832     .05       0    9145     .14       0
    9200    .035       0    9740     .07       0
Levee=-1,5730,460,0,,,,
#XS Ineff= 2 , 0
       0    5730     460               0
Permanent Ineff=
       F       F
Bank Sta=8920,9145
XS Rating Curve= 0 ,0
Exp/Cntr=0.3,0.1

Type RM Length L Ch R = 1 ,90547   ,651,839,951
BEGIN DESCRIPTION:
This cross section corresponds to cross section 90532 of the non-georeferenced CDC model which was the source of this model.
END DESCRIPTION:
XS GIS Cut Line= 5
2452726.779946277036831.144925222446511.170002167035271.50893688
2443460.91166702 7035345.00649332442720.441363197035356.46742839
2441220.621005267035379.68151771
#Sta/Elev= 30
    2300     440    2705   438.6    2737   448.3    2855   450.7    2995   438.6
    3508   443.3    4784     441    5860   446.9    5860     452    6915   460.1
    7068   453.9    7172   433.3    7226   430.6    7880   441.5    9079     441
    9122     430    9146     424    9198     430    9290     431    9330   413.7
    9385     409    9420   430.8    9468   442.1    9540     443    9624   449.3
    9867     431   10123     431   10187   446.5   10772   450.4   14000     451
#Mann= 10 ,-1,0
    2300    .075       0    3508    .045       0    4784     .14       0
    5860    .045       0    9122     .03       0    9198    .045       0
    9290     .05       0    9468     .14       0    9540    .035       0
   10123     .07       0
Levee=-1,5720,460,0,,,,
#XS Ineff= 2 , 0
       0    5720     460               0
Permanent Ineff=
       F       F
Bank Sta=9290,9468
XS Rating Curve= 0 ,0
Exp/Cntr=0.3,0.1

Type RM Length L Ch R = 1 ,89708   ,799,981,999
BEGIN DESCRIPTION:
This cross section corresponds to cross section 89694 of the non-georeferenced CDC model which was the source of this model.
END DESCRIPTION:
XS GIS Cut Line= 6
2452828.585188847035942.362582042446415.268947247034636.62405179
2445895.703057267034393.601243882444214.567311917034485.10959105
2443457.398878757034518.245679632440959.789463927034627.54897753
#Sta/Elev= 30
    2620     440    3554   435.9    3591   447.9    3703   449.5    3731   437.5
    4036     444    4064     441    5860     440    6450   440.2    6450     452
    6609     452    6624   460.1    7328   460.1    7579   440.3    8136   432.6
    8710   440.1    9390   434.1    9402   434.1    9443   415.7    9471     408
    9579   440.5    9592   440.9    9688   440.5    9747   445.5    9799   441.1
    9854     430   10169     430   10337   437.7   10369   445.2   14680   447.5
#Mann= 8 ,-1,0
    2620     .05       0    5860     .14       0    6609    .045       0
    9390     .14       0    9402     .05       0    9579     .14       0
    9592     .05       0   10369     .07       0
Levee=-1,5621,460,0,,,,
#XS Ineff= 2 , 0
       0    5621     460               0
Permanent Ineff=
       F       F
Bank Sta=9402,9579
XS Rating Curve= 0 ,0
Exp/Cntr=0.3,0.1

Type RM Length L Ch R = 1 ,88727   ,1150,1067,950
BEGIN DESCRIPTION:
This cross section corresponds to cross section 88712 of the non-georeferenced CDC model which was the source of this model.
OEI Updated Ground Data and manning's n values  for proposed conditions on West Tracts
-------------------
END DESCRIPTION:
XS GIS Cut Line= 5
2452003.022207417034988.043296472447177.857973257033966.21692805
2446440.408988837033572.352230222444164.230142277033732.23708105
2441171.60391302 7033942.4470999
#Sta/Elev= 30
    3820   434.6    3894   447.9  3992.5   447.3    4071   434.5    4128   434.5
    4148   442.2  4185.7     443 4500.86     443    4726   440.1    5804     441
    6727   439.8    6908   432.2    7269   438.3    7924   432.5    8299   438.6
    9123   437.3    9160   433.9    9200   412.1    9250   406.9    9265   417.9
    9386   442.3    9420   447.2    9594   444.6    9650   445.4    9650     451
   10000     451   10000   442.8   11029   438.5   11376   447.9   14870   446.9
#Mann= 11 ,-1,0
    3820     .08       0  4185.7     .02       0 4500.86     .08       0
    4726     .05       0    5804     .14       0    7924     .07       0
    8299     .05       0    9123     .12       0    9160     .05       0
    9386     .12       0    9420     .07       0
Levee=-1,5432,460,0,,,,
#XS Ineff= 2 , 0
       0    5432     460               0
Permanent Ineff=
       F       F
Bank Sta=9160,9386
XS Rating Curve= 0 ,0
Exp/Cntr=0.3,0.1

River Reach=Elm Fork        ,PGBT split east
Reach XY= 30
      2447850.52      7040050.17      2448046.24      7039935.45
      2448387.09      7040023.41      2449651.56      7040001.42
      2449924.88      7039707.44      2450709.71      7039354.02
      2451168.18      7039051.97      2450533.58      7038983.11
      2450359.03      7038883.33      2449374.49      7037614.65
      2450454.81      7037133.85      2451581.78      7036549.12
      2451601.55      7035215.06      2451584.45      7035087.75
      2451531.25      7035025.05      2451364.04      7034954.75
      2451018.24      7034916.79      2450829.87      7034738.84
      2450963.55      7034496.21      2450955.74      7034358.19
      2450875.93      7034206.43      2450618.79      7034091.55
      2450352.95      7034104.98      2450186.47      7033984.14
      2450104.06      7033526.54      2449971.54      7033089.05
      2449875.18      7032951.03      2448864.61      7032823.42
      2448171.55      7032801.49      2447356.93      7032903.31