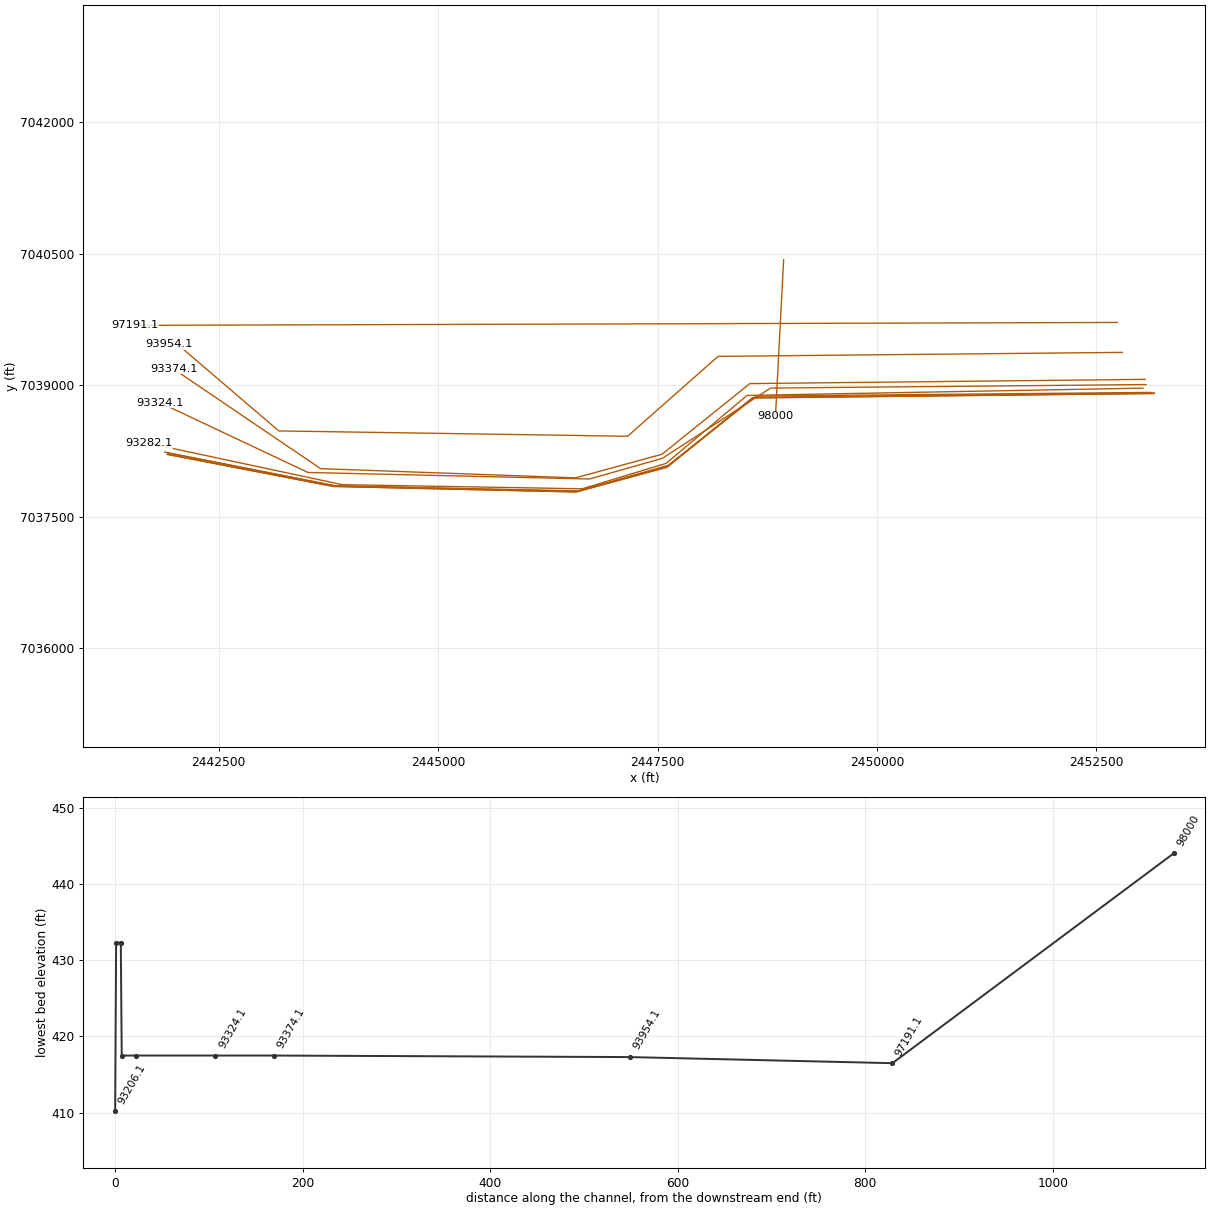
HEC-RAS study CDC_Consolidated_Model.prj: Upper Trinity CDC Consolidated Model

--- CDC_Consolidated_Model.g04 (geometry) --- (continued)

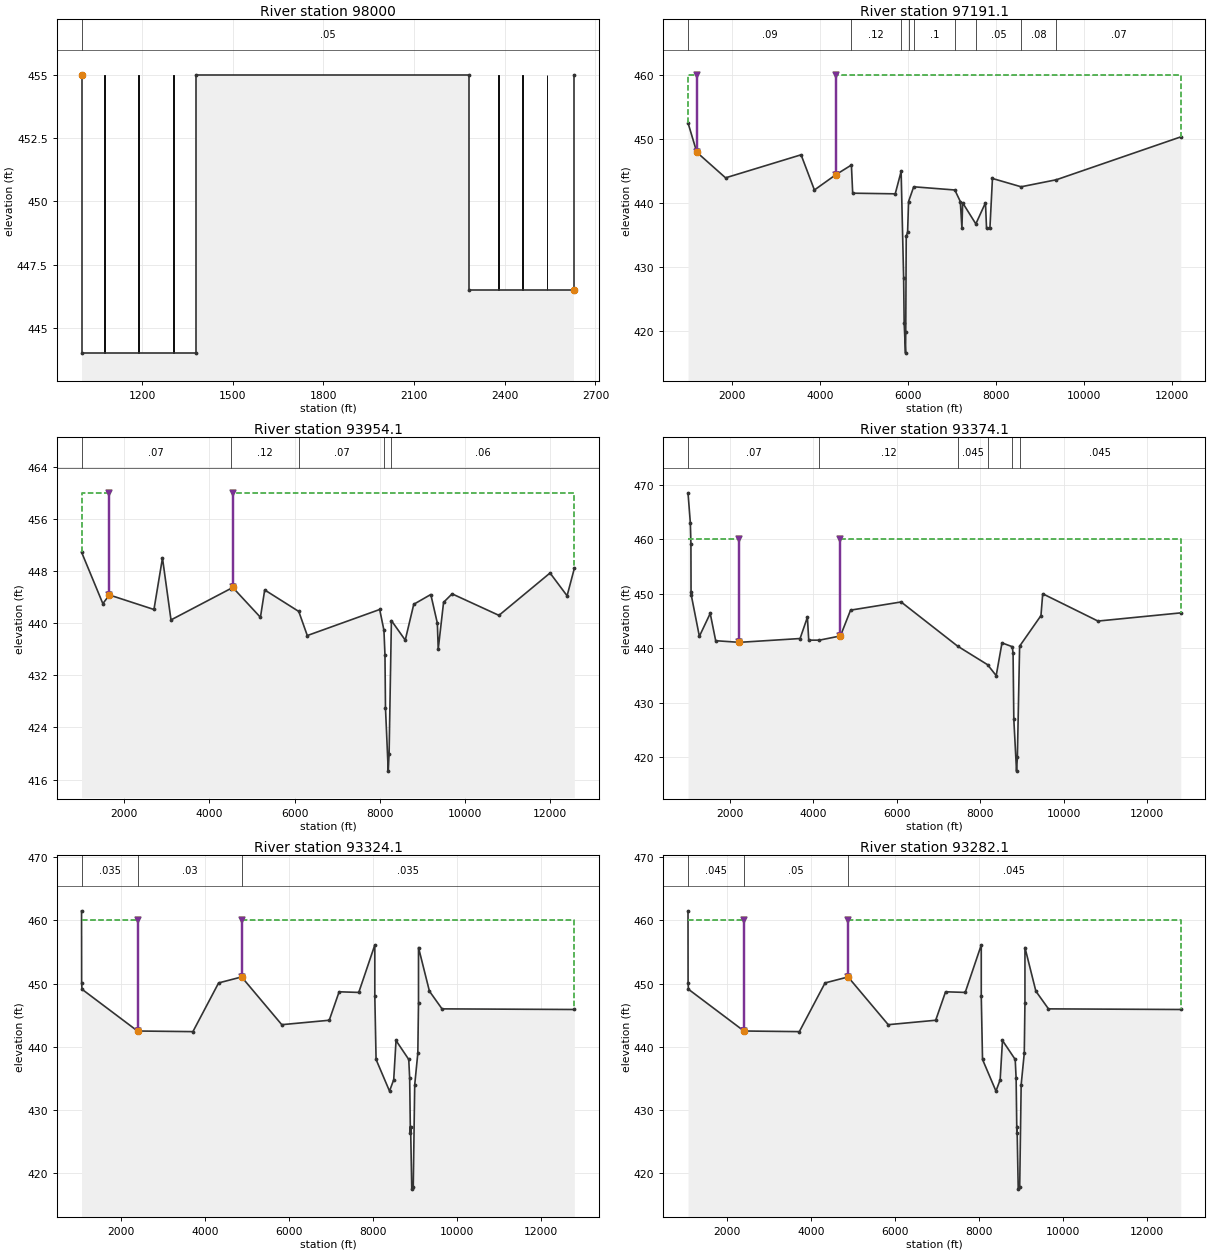
Type RM Length L Ch R = 1 ,98000   ,300,300,300
BEGIN DESCRIPTION:
This cross section corresponds to cross section 98000 of the non-georeferenced CDC model which was the source of this model.
At PGBT West Face of DWU Crossing,
380' +/- bridge opening
END DESCRIPTION:
XS GIS Cut Line= 2
2448936.862001187040430.24205771 2448843.40123017038643.49431889
#Sta/Elev= 8
    1000     455    1000     444    1380     444    1380     455    2280     455
    2280   446.5    2630   446.5    2630     455
#Mann= 1 ,-1,0
    1000     .05       0
#Block Obstruct= 6 ,-1
    1073    1076     455    1188    1191     455    1303    1306     455
    2378    2381     455    2458    2461     455    2538    2541     455
Bank Sta=1000,2630
XS Rating Curve= 0 ,0
Exp/Cntr=0.3,0.1

Type RM Length L Ch R = 1 ,97191.1 ,2200,280,1350
BEGIN DESCRIPTION:
This cross section corresponds to cross section 97178 of the non-georeferenced CDC model which was the source of this model.
END DESCRIPTION:
XS GIS Cut Line= 2
2452739.651967767039715.766124472441539.700942527039682.66481271
#Sta/Elev= 30
    1000   452.5    1200   447.9    1854   443.9    3570   447.5    3873     442
    4360444.3889    4714   445.9    4743   441.5    5710   441.4    5844   444.9
    5901   428.2    5913   421.2    5944   416.5    5949   419.8    5960   434.8
    5991   435.4    6013   440.2    6130   442.5 7064.45     442    7189   440.2
  7225.9     436  7241.9     440  7541.9   436.7  7761.2     440  7785.3     436
  7861.8     436  7919.6   443.8    8571   442.5    9372   443.6   12200   450.3
#Mann= 9 ,-1,0
    1000     .09       0    4714     .12       0    5844     .05       0
    6013    .045       0    6130      .1       0 7064.45      .1       0
  7541.9     .05       0    8571     .08       0    9372     .07       0
Levee=-1,1200,460,-1,4360,460,,
#XS Ineff= 2 , 0
       0    1200     460    4360       0     460
Permanent Ineff=
       T       T
Bank Sta=1200,4360
XS Rating Curve= 0 ,0
Exp/Cntr=0.3,0.1

Type RM Length L Ch R = 1 ,93954.1 ,650,380,460
BEGIN DESCRIPTION:
This cross section corresponds to cross section 93940 of the non-georeferenced CDC model which was the source of this model.
END DESCRIPTION:
XS GIS Cut Line= 6
2452796.764058267039374.541085142448190.277864437039329.19406296
2447158.79895625 7038418.3231813 2443184.57199667038479.04812546
2442031.742937427039465.825023292441936.719177347039466.55632105
#Sta/Elev= 30
    1000   450.9    1500     443    1654 444.328    2700   442.1    2900     450
    3100   440.5    4500   445.3    4550445.4833    5200   440.9    5300   445.1
    6100   441.8    6300   438.1    8000   442.1    8100   438.9    8124   435.1
    8136     427    8201   417.3    8221     420    8275   440.4    8600   437.4
    8800   442.9    9200   444.4    9354     440    9374     436    9500   443.2
    9700   444.5   10800   441.2   12000   447.7   12400   444.2   12570   448.4
#Mann= 5 ,-1,0
    1000     .07       0    4500     .12       0    6100     .07       0
    8100     .05       0    8275     .06       0
Levee=-1,1654,460,-1,4550,460,,
#XS Ineff= 2 , 0
       0    1654     460    4550       0     460
Permanent Ineff=
       T       T
Bank Sta=1654,4550
XS Rating Curve= 0 ,0
Exp/Cntr=0.3,0.1

Type RM Length L Ch R = 1 ,93374.1 ,62,62,62
BEGIN DESCRIPTION:
This cross section corresponds to cross section 93359 of the non-georeferenced CDC model which was the source of this model.
--------------------------------------------
CDC Cop 050812-01 River Oaks Assisted Living and Memory Care
Cross-section 93359 - 93940
Located in ROB.
--------------------------------------------
END DESCRIPTION:
XS GIS Cut Line= 6
2453055.818986337039066.976083472448551.367037277039018.65006463
2447550.309000027038212.535207052446565.057033517037943.83003581
 2443660.83088667038049.009943542441985.526494417039186.21665864
#Sta/Elev= 30
    1000   468.5    1056     463    1070   459.2    1073   450.4    1080   449.7
    1272   442.2    1532   446.4    1663   441.4    2230   441.1    3684   441.8
    3859   445.7    3891   441.5    4146   441.5    4650442.2752    4893     447
    6103   448.5    7457   440.4    8174     437    8380     435    8519     441
    8766   440.3    8784   439.1    8802     427    8867   417.5    8887     420
    8941   440.4    9452     446    9494     450   10817     445   12800   446.5
#Mann= 6 ,-1,0
    1000     .07       0    4146     .12       0    7457    .045       0
    8174    .035       0    8766     .05       0    8941    .045       0
Levee=-1,2230,460,-1,4650,460,,
#XS Ineff= 2 , 0
       0    2230     460    4650       0     460
Permanent Ineff=
       T       T
Bank Sta=2230,4650
XS Rating Curve= 0 ,0
Exp/Cntr=0.3,0.1

Type RM Length L Ch R = 1 ,93324.1 ,85,85,85
BEGIN DESCRIPTION:
This cross section corresponds to cross section 93297 of the non-georeferenced CDC model which was the source of this model.
Upstream bounding cross-section for Sandy Lake Road bridge
END DESCRIPTION:
XS GIS Cut Line= 6
2453066.561747017039007.696674472448786.985660497038967.59209588
2447555.995668417038166.889629052446724.131518517037930.82809331
 2443517.29180367038005.28102839 2441834.59635017038799.91001655
#Sta/Elev= 30
    1068   461.5    1070   450.1    1079   449.1    2400   442.5    3719   442.4
    4331   450.1    4879451.0464    5835   443.5    6965   444.2    7200   448.7
    7668   448.6    8050   456.1    8050     448    8080     438    8400     433
    8500   434.8    8555     441    8858     438    8880     435    8897   426.3
    8902   427.4    8930   417.5    8965   417.8    9000     434    9074     439
    9090     447    9090   455.7    9350   448.8    9650     446   12800   445.9
#Mann= 3 ,0,0
    1068    .035       0    2400     .03       0    4879    .035       0
Levee=-1,2400,460,-1,4879,460,,
#XS Ineff= 2 , 0
       0    2400     460    4879       0     460
Permanent Ineff=
       T       T
Bank Sta=2400,4879
XS Rating Curve= 0 ,0
Exp/Cntr=0.3,0.1

Type RM Length L Ch R = 1 ,93282.1 ,10,15,20
BEGIN DESCRIPTION:
This cross section corresponds to cross section 93212 of the non-georeferenced CDC model which was the source of this model.
Downstream bounding cross-section for Sandy Lake Road bridge
END DESCRIPTION:
XS GIS Cut Line= 6
2453032.140556017038966.992687632448520.069527697038883.64377296
2447597.799390587038109.242434642446642.141196947037819.29157096
2443907.252637837037866.266214552441707.816747997038336.53299055
#Sta/Elev= 30
    1068   461.5    1070   450.1    1079   449.1    2400   442.5    3719   442.4
    4331   450.1    4879451.0464    5835   443.5    6965   444.2    7200   448.7
    7668   448.6    8050   456.1    8050     448    8080     438    8400     433
    8500   434.8    8555     441    8858     438    8880     435    8897   426.3
    8902   427.4    8930   417.5    8965   417.8    9000     434    9074     439
    9090     447    9090   455.7    9350   448.8    9650     446   12800   445.9
#Mann= 3 ,0,0
    1068    .045       0    2400     .05       0    4879    .045       0
Levee=-1,2400,460,-1,4879,460,,
#XS Ineff= 2 , 0
       0    2400     460    4879       0     460
Permanent Ineff=
       T       T
Bank Sta=2400,4879
XS Rating Curve= 0 ,0
Exp/Cntr=0.3,0.1

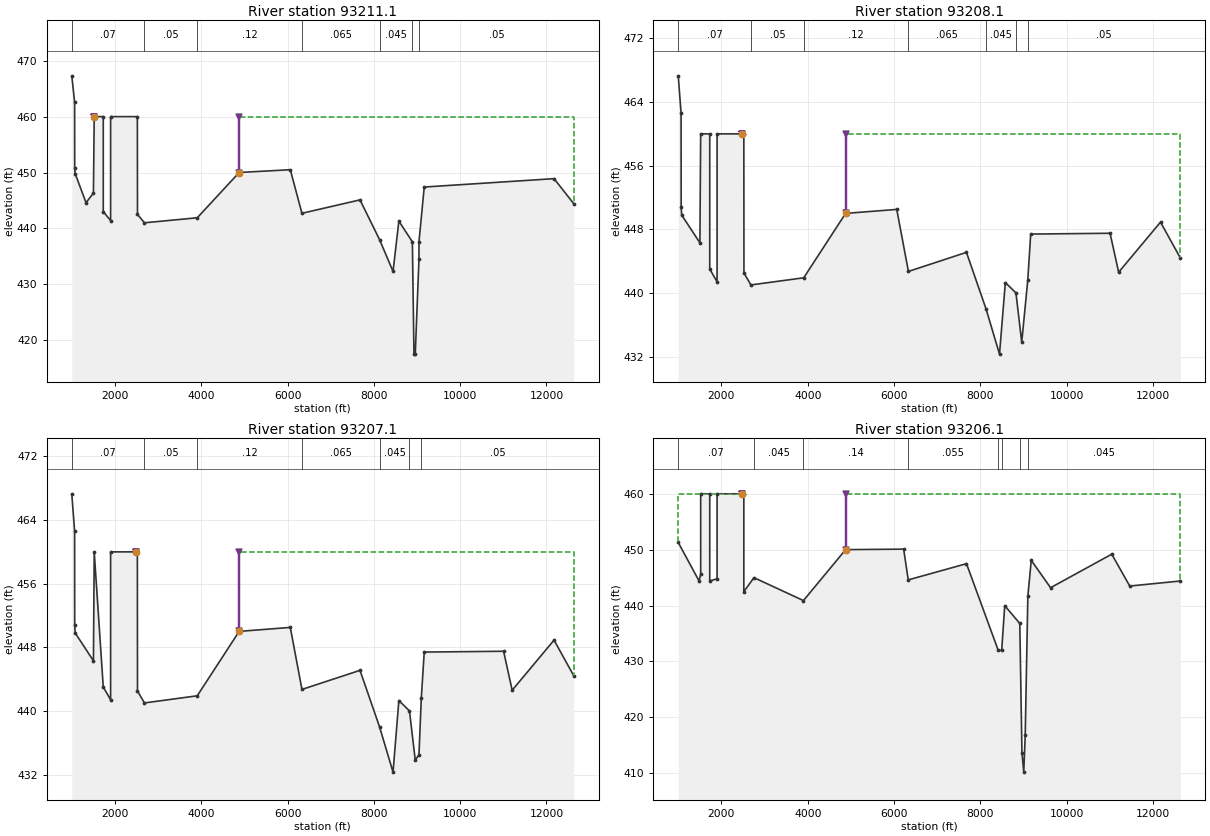
Type RM Length L Ch R = 1 ,93211.1 ,1,1,1
BEGIN DESCRIPTION:
This cross section corresponds to cross section 93197 of the non-georeferenced CDC model which was the source of this model.
END DESCRIPTION:
XS GIS Cut Line= 6
2453120.484211337038918.043310462448624.117547937038876.03912938
2447622.075260677038085.549240542446594.051726167037793.92941697
2443835.875484027037852.24885413 2441886.55884467038237.30353022
#Sta/Elev= 30
    1000   467.3    1066   462.6    1068   450.8    1079   449.8    1330   444.6
    1502   446.3    1520     460    1730     460    1730     443    1900   441.4
    1900     460    2520     460    2523   442.5    2684     441    3908   441.9
    4879450.0003    6064   450.5    6334   442.7    7679   445.1    8132     438
    8445   432.3    8580   441.3    8893   437.6    8930   417.5    8960   417.5
    9046   434.5    9046   437.6    9168   447.4   12176   448.9   12635   444.4
#Mann= 7 ,-1,0
    1000     .07       0    2684     .05       0    3908     .12       0
    6334    .065       0    8132    .045       0    8893     .05       0
    9046     .05       0
Levee=-1,1520,460,-1,4879,460,,
#XS Ineff= 2 , 0
       0    1520     460    4879       0     460
Permanent Ineff=
       T       T
Bank Sta=1520,4879
XS Rating Curve= 0 ,0
Exp/Cntr=0.3,0.1

Type RM Length L Ch R = 1 ,93208.1 ,5,5,5
BEGIN DESCRIPTION:
This cross section corresponds to cross section 93196 of the non-georeferenced CDC model which was the source of this model.
END DESCRIPTION:
XS GIS Cut Line= 6
2453161.383407747038911.607299722448592.968660097038861.20648189
2447619.803611677038082.320244392446590.514987837037792.19451229
2443830.769195027037851.319065972441921.452803677038226.72940439
#Sta/Elev= 30
    1000   467.3    1066   462.6    1068   450.8    1079   449.8    1502   446.3
    1520     460    1730     460    1730     443    1900   441.4    1900     460
    2480     460    2520     460    2523   442.5    2684     441    3908   441.9
    4879450.0003    6064   450.5    6334   442.7    7679   445.1    8132     438
    8445   432.3    8580   441.3    8826     440    8960   433.8    9100   441.6
    9168   447.4   11007   447.5   11206   442.6   12176   448.9   12635   444.4
#Mann= 7 ,-1,0
    1000     .07       0    2684     .05       0    3908     .12       0
    6334    .065       0    8132    .045       0    8826     .02       0
    9100     .05       0
Levee=-1,2480,460,-1,4879,460,,
#XS Ineff= 2 , 0
       0    2480     460    4879       0     460
Permanent Ineff=
       T       T
Bank Sta=2480,4879
XS Rating Curve= 0 ,0
Exp/Cntr=0.3,0.1

Type RM Length L Ch R = 1 ,93207.1 ,1,1,1
BEGIN DESCRIPTION:
This cross section corresponds to cross section 93191 of the non-georeferenced CDC model which was the source of this model.
END DESCRIPTION:
XS GIS Cut Line= 6
 2453153.70166467038906.782834312448582.513956587038855.67696539
2447608.631061857038066.236943222446572.952030847037783.50916222
2443805.37685734 7037846.64322232441915.66278902 7038211.8235943
#Sta/Elev= 30
    1000   467.3    1066   462.6    1068   450.8    1079   449.8    1502   446.3
    1520     460    1730     443    1900   441.4    1900     460    2480     460
    2520     460    2523   442.5    2684     441    3908   441.9    4879450.0003
    6064   450.5    6334   442.7    7679   445.1    8132     438    8445   432.3
    8580   441.3    8826     440    8960   433.8    9046   434.5    9100   441.6
    9168   447.4   11007   447.5   11206   442.6   12176   448.9   12635   444.4
#Mann= 7 ,-1,0
    1000     .07       0    2684     .05       0    3908     .12       0
    6334    .065       0    8132    .045       0    8826     .02       0
    9100     .05       0
Levee=-1,2480,460,-1,4879,460,,
#XS Ineff= 2 , 0
       0    2480     460    4879       0     460
Permanent Ineff=
       T       T
Bank Sta=2480,4879
XS Rating Curve= 0 ,0
Exp/Cntr=0.3,0.1

Type RM Length L Ch R = 1 ,93206.1 ,49,49,49
BEGIN DESCRIPTION:
This cross section corresponds to cross section 93190 of the non-georeferenced CDC model which was the source of this model.
END DESCRIPTION:
XS GIS Cut Line= 6
      2453153.74      7038905.78 2448582.5139566 7038855.6769654
 2447608.6310619 7038066.2369432 2446572.9520308 7037783.5091622
 2443805.3768573 7037846.6432223  2441915.662789 7038211.8232662
#Sta/Elev= 30
    1000   451.3    1483   444.4    1520   445.6    1520     460    1730     460
    1730   444.4    1900   444.8    1900     460    2480     460    2520     460
    2520   442.5    2755     445    3901   440.9    4879450.0134    6224   450.1
    6330   444.6    7680   447.5    8415     432    8496     432    8566     440
    8915   436.8    8965   413.7    9007   410.2    9041   416.8    9102   441.7
    9181   448.1    9628   443.2   11046   449.2   11463   443.5   12635   444.4
#Mann= 8 ,-1,0
    1000     .07       0    2755    .045       0    3901     .14       0
    6330    .055       0    8415    .035       0    8496     .12       0
    8915     .05       0    9102    .045       0
Levee=-1,2480,460,-1,4879,460,,
#XS Ineff= 2 , 0
       0    2480     460    4879       0     460
Permanent Ineff=
       T       T
Bank Sta=2480,4879
XS Rating Curve= 0 ,0
Exp/Cntr=0.3,0.1