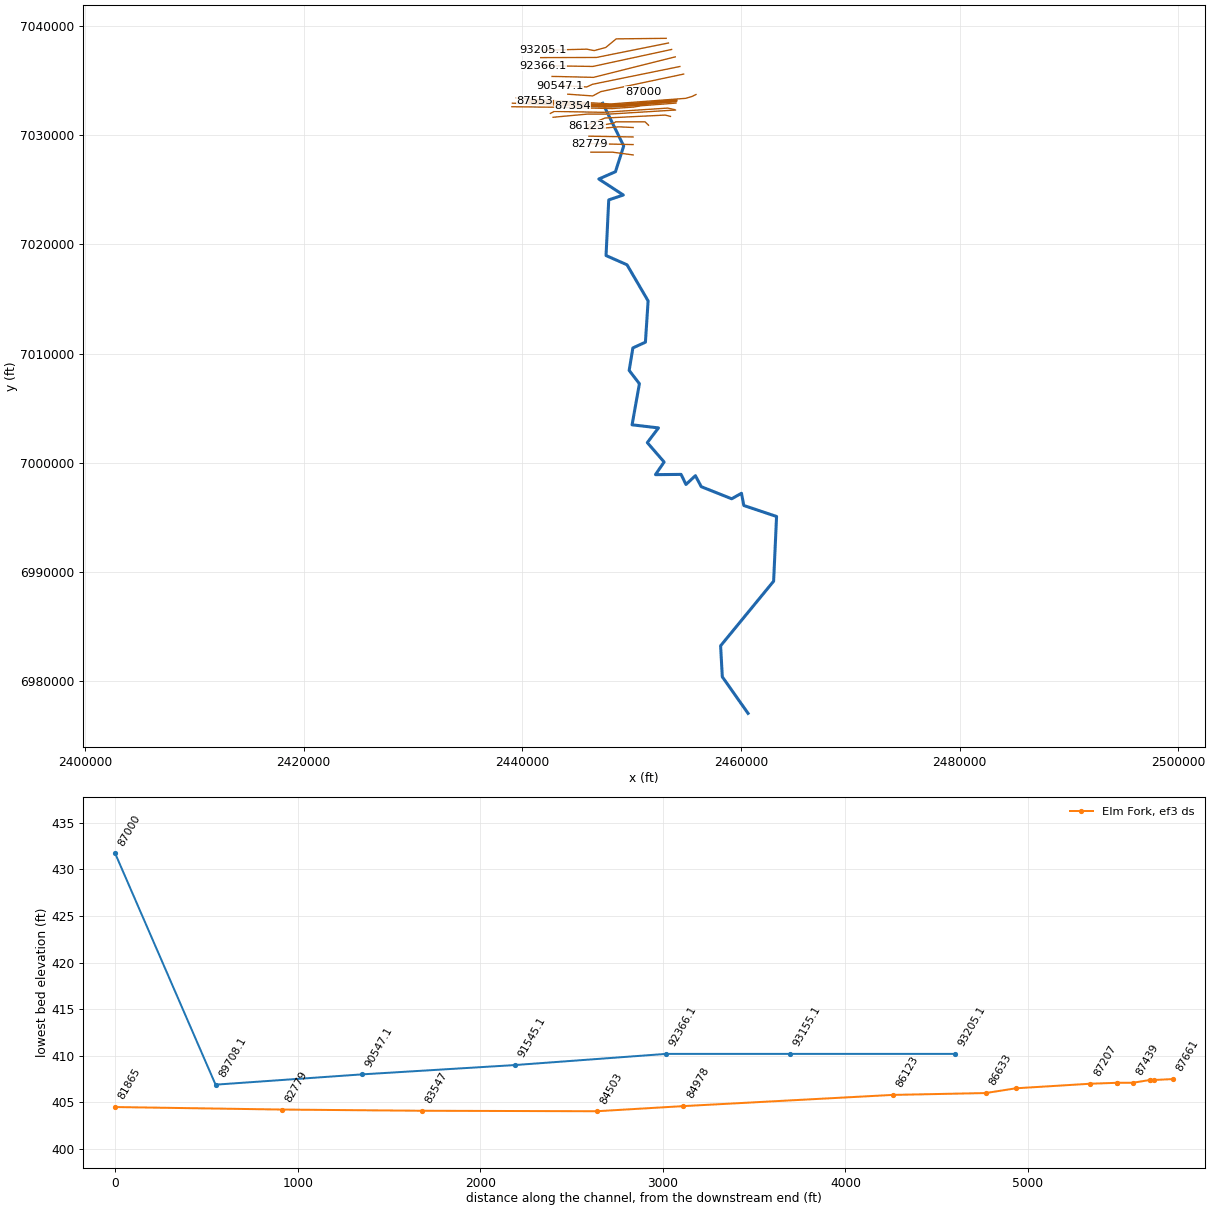
HEC-RAS study CDC_Consolidated_Model.prj: Upper Trinity CDC Consolidated Model

--- CDC_Consolidated_Model.g04 (geometry) --- (continued)

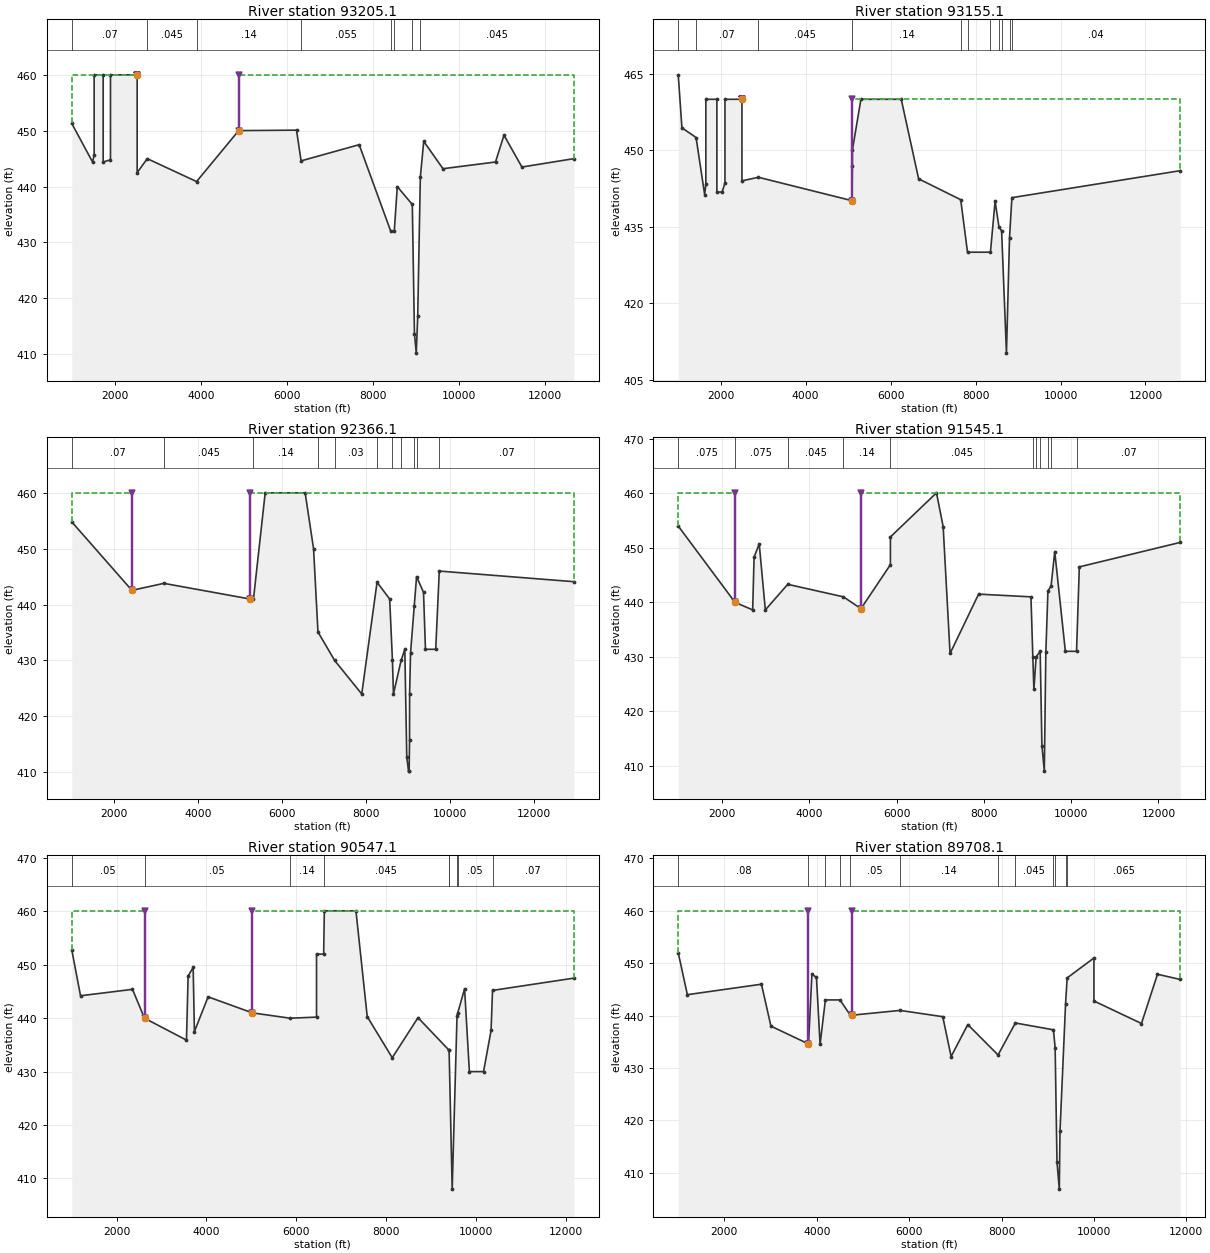
Type RM Length L Ch R = 1 ,93205.1 ,760,900,740
BEGIN DESCRIPTION:
This cross section corresponds to cross section 93141 of the non-georeferenced CDC model which was the source of this model.
END DESCRIPTION:
XS GIS Cut Line= 6
2453165.058925337038843.361045142448594.03788367 7038794.2240043
2447632.440069357038006.71606489  2446574.4408737037721.01223996
2445907.796865087037851.960140792441858.408966517037755.36518963
#Sta/Elev= 30
    1000   451.3    1483   444.4    1520   445.6    1520     460    1730     460
    1730   444.4    1900   444.8    1900     460    2520     460    2520   442.5
    2755     445    3901   440.9    4879450.0134    6224   450.1    6330   444.6
    7680   447.5    8415     432    8496     432    8566     440    8915   436.8
    8965   413.7    9007   410.2    9041   416.8    9102   441.7    9181   448.1
    9628   443.2   10849   444.4   11046   449.2   11463   443.5   12670     445
#Mann= 8 ,-1,0
    1000     .07       0    2755    .045       0    3901     .14       0
    6330    .055       0    8415    .035       0    8496     .12       0
    8915     .05       0    9102    .045       0
Levee=-1,2520,460,-1,4879,460,,
#XS Ineff= 2 , 0
       0    2520     460    4879       0     460
Permanent Ineff=
       T       T
Bank Sta=2520,4879
XS Rating Curve= 0 ,0
Exp/Cntr=0.3,0.1

Type RM Length L Ch R = 1 ,93155.1 ,820,680,820
BEGIN DESCRIPTION:
This cross section corresponds to cross section 92351 of the non-georeferenced CDC model which was the source of this model.
END DESCRIPTION:
XS GIS Cut Line= 3
2453370.468947597038416.698184552446778.237053337037093.70312713
2441681.935894257037078.87244813
#Sta/Elev= 30
    1000   464.8    1087   454.4    1420   452.5    1622   441.3    1650   443.3
    1650     460    1910     460    1910   441.8    2034   441.8    2100   443.6
    2100     460    2500     460    2500     444    2887   444.7    5090440.1099
    5100     447    5100     450    5300     460    6250     460    6659   444.4
    7650   440.3    7810     430    8350     430    8460     440    8550     435
    8613   434.2    8727   410.2    8799   432.8    8855   440.7   12820     446
#Mann= 11 ,-1,0
    1000    .045       0    1420     .07       0    2887    .045       0
    5100     .14       0    7650     .05       0    7810     .03       0
    8350     .05       0    8550     .14       0    8613     .05       0
    8799     .14       0    8855     .04       0
Levee=-1,2500,460,-1,5090,460,,
#XS Ineff= 2 , 0
       0    2500     460    5090       0     460
Permanent Ineff=
       T       T
Bank Sta=2500,5090
XS Rating Curve= 0 ,0
Exp/Cntr=0.3,0.1

Type RM Length L Ch R = 1 ,92366.1 ,1000,830,1000
BEGIN DESCRIPTION:
This cross section corresponds to cross section 91530 of the non-georeferenced CDC model which was the source of this model.
END DESCRIPTION:
XS GIS Cut Line= 3
2453657.147836187037825.518920722446457.170110177036270.74315888
2441883.650057767036341.30240096
#Sta/Elev= 30
    1000   454.8    2430 442.549    3190   443.8    5240     441    5321     441
    5600     460    6550     460    6750     450    6855   435.1    7252     430
    7896     424    8260     444    8560     441    8626     430    8650     424
    8832     430    8920     432    8967   412.7    9009   410.2    9023   410.2
    9033   415.8    9034     424    9057   431.4    9145   439.8    9200     445
    9365   442.2    9411     432    9655     432    9740     446   12940   444.1
#Mann= 11 ,-1,0
    1000     .07       0    3190    .045       0    5321     .14       0
    6855    .035       0    7252     .03       0    8260    .045       0
    8626     .03       0    8832     .05       0    9145     .14       0
    9200    .035       0    9740     .07       0
Levee=-1,2430,460,-1,5240,460,,
#XS Ineff= 2 , 0
       0    2430     460    5240       0     460
Permanent Ineff=
       T       T
Bank Sta=2430,5240
XS Rating Curve= 0 ,0
Exp/Cntr=0.3,0.1

Type RM Length L Ch R = 1 ,91545.1 ,650,838,950
BEGIN DESCRIPTION:
This cross section corresponds to cross section 90532 of the non-georeferenced CDC model which was the source of this model.
END DESCRIPTION:
XS GIS Cut Line= 4
2453987.691138337037147.536024722446511.170002167035271.50893688
2443460.91166702 7035345.00649332442720.441363197035356.46742839
#Sta/Elev= 30
    1000     454    2300     440    2705   438.6    2737   448.3    2855   450.7
    2995   438.6    3508   443.3    4784     441    5185438.8321    5860   446.9
    5860     452    6915   460.1    7068   453.9    7226   430.6    7880   441.5
    9079     441    9122     430    9146     424    9198     430    9290     431
    9330   413.7    9385     409    9420   430.8    9468   442.1    9540     443
    9624   449.3    9867     431   10123     431   10187   446.5   12500     451
#Mann= 11 ,-1,0
    1000    .075       0    2300    .075       0    3508    .045       0
    4784     .14       0    5860    .045       0    9122     .03       0
    9198    .045       0    9290     .05       0    9468     .14       0
    9540    .035       0   10123     .07       0
Levee=-1,2300,460,-1,5185,460,,
#XS Ineff= 2 , 0
       0    2300     460    5185       0     460
Permanent Ineff=
       T       T
Bank Sta=2300,5185
XS Rating Curve= 0 ,0
Exp/Cntr=0.3,0.1

Type RM Length L Ch R = 1 ,90547.1 ,800,800,1000
BEGIN DESCRIPTION:
This cross section corresponds to cross section 89694 of the non-georeferenced CDC model which was the source of this model.
--------------------------------------------
CDC CAR040507-1 Western Extrusions
Cross-section 89694-91530
Located in LOB within ineffective flow area.
--------------------------------------------
END DESCRIPTION:
XS GIS Cut Line= 5
2454416.018037597036265.561082632446415.268947247034636.62405179
2445895.703057267034393.601243882444214.567311917034485.10959105
2443457.398878757034518.24567963
#Sta/Elev= 30
    1000   452.8    1195   444.2    2352   445.4    2620     440    3554   435.9
    3591   447.9    3703   449.5    3731   437.5    4036     444    5020     441
    5860     440    6450   440.2    6450     452    6609     452    6624   460.1
    7328   460.1    7579   440.3    8136   432.6    8710   440.1    9390   434.1
    9402   434.1    9471     408    9579   440.5    9592   440.9    9747   445.5
    9854     430   10169     430   10337   437.7   10369   445.2   12180   447.5
#Mann= 9 ,-1,0
    1000     .05       0    2620     .05       0    5860     .14       0
    6609    .045       0    9390     .14       0    9402     .05       0
    9579     .14       0    9592     .05       0   10369     .07       0
Levee=-1,2620,460,-1,5020,460,,
#XS Ineff= 2 , 0
       0    2620     460    5020       0     460
Permanent Ineff=
       T       T
Bank Sta=2620,5020
XS Rating Curve= 0 ,0
Exp/Cntr=0.3,0.1

Type RM Length L Ch R = 1 ,89708.1 ,1150,550,950
BEGIN DESCRIPTION:
This cross section corresponds to cross section 88712 of the non-georeferenced CDC model which was the source of this model.
OEI Updated Ground Data and manning's n values  for proposed conditions on West Tracts
------------------
END DESCRIPTION:
XS GIS Cut Line= 4
2454761.838868267035572.279004632447177.857973257033966.21692805
2446440.408988837033572.352230222444164.230142277033732.23708105
#Sta/Elev= 30
    1000     452 1197.54     444 2801.35     446 3006.98     438    3820   434.6
    3894   447.9  3992.5   447.3    4071   434.5  4185.7     443 4500.86     443
    4726   440.1    4770440.0958    5804     441    6727   439.8    6908   432.2
    7269   438.3    7924   432.5    8299   438.6    9123   437.3    9160   433.9
    9200   412.1    9250   406.9    9265   417.9    9386   442.3    9420   447.2
   10000     451   10000   442.8   11029   438.5   11376   447.9   11870   446.9
#Mann= 12 ,-1,0
    1000     .08       0    3820     .08       0  4185.7     .02       0
 4500.86     .08       0    4726     .05       0    5804     .14       0
    7924     .07       0    8299    .045       0    9123     .12       0
    9160     .05       0    9386     .12       0    9420    .065       0
Levee=-1,3820,460,-1,4770,460,,
#XS Ineff= 2 , 0
       0    3820     460    4770       0     460
Permanent Ineff=
       T       T
Bank Sta=3820,4770
XS Rating Curve= 0 ,0
Exp/Cntr=0.3,0.1

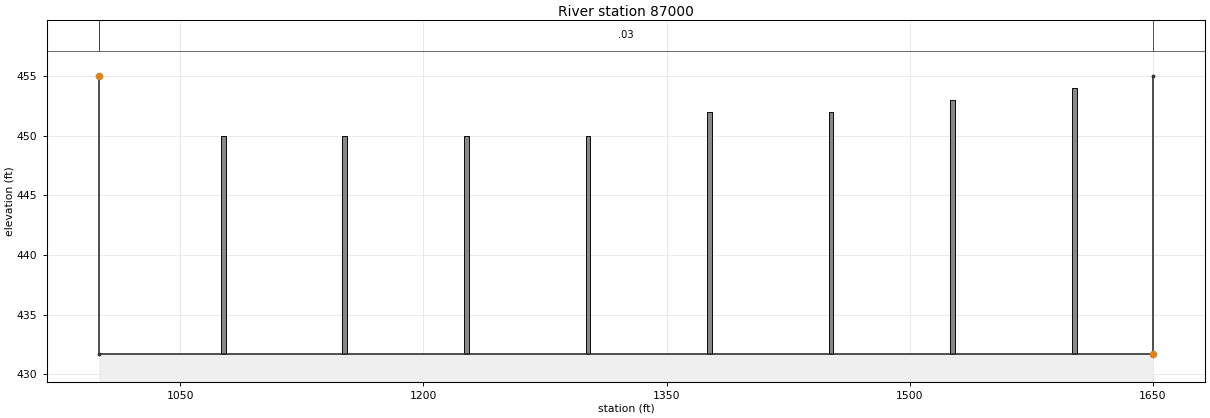
Type RM Length L Ch R = 1 ,87000   ,,,
BEGIN DESCRIPTION:
This cross section corresponds to cross section 87000 of the non-georeferenced CDC model which was the source of this model.
PGBT, West Face of Bridge Structure Approximated
END DESCRIPTION:
XS GIS Cut Line= 2
2450736.60840169 7034400.27806782451049.781003687033963.45840338
#Sta/Elev= 4
    1000     455    1000   431.7    1650   431.7    1650     455
#Mann= 3 ,0,0
    1000    .055       0    1000     .03       0    1650    .055       0
#Block Obstruct= 8 ,-1
    1075    1078     450    1150    1153     450    1225    1228     450
    1300    1303     450    1375    1378     452    1450    1453     452
    1525    1528     453    1600    1603     454
#XS Lid=3
    1000  452.62  448.27    1180  454.09  448.61    1650  457.92   453.7
Bank Sta=1000,1650
XS Rating Curve= 0 ,0
Exp/Cntr=0.3,0.1

River Reach=Elm Fork        ,ef3 ds
Reach XY= 30
      2447356.93      7032903.31      2449276.42      7028990.09
      2448521.48      7026637.83      2447000.53      7025969.64
       2449243.1      7024505.45      2447907.61      7024057.09
      2447661.34       7018966.6      2449579.68      7018119.64
      2451509.59      7014814.57      2451262.61      7011037.61
       2450116.3      7010513.16      2449776.69      7008454.84
      2450712.67      7007237.43      2450043.63      7003476.24
      2452456.92      7003195.07      2451436.24      7001846.74
      2452973.76      7000073.06      2452181.75      6998915.55
      2454526.25      6998940.04      2454971.66       6998016.3
      2455835.87      6998821.28      2456369.33      6997815.18
      2459151.98      6996708.01      2460049.87      6997211.53
      2460262.81      6996093.07      2463259.53      6995089.58
      2462990.63      6989165.68      2458140.49       6983253.5
      2458296.43      6980416.59       2460651.9      6977070.51

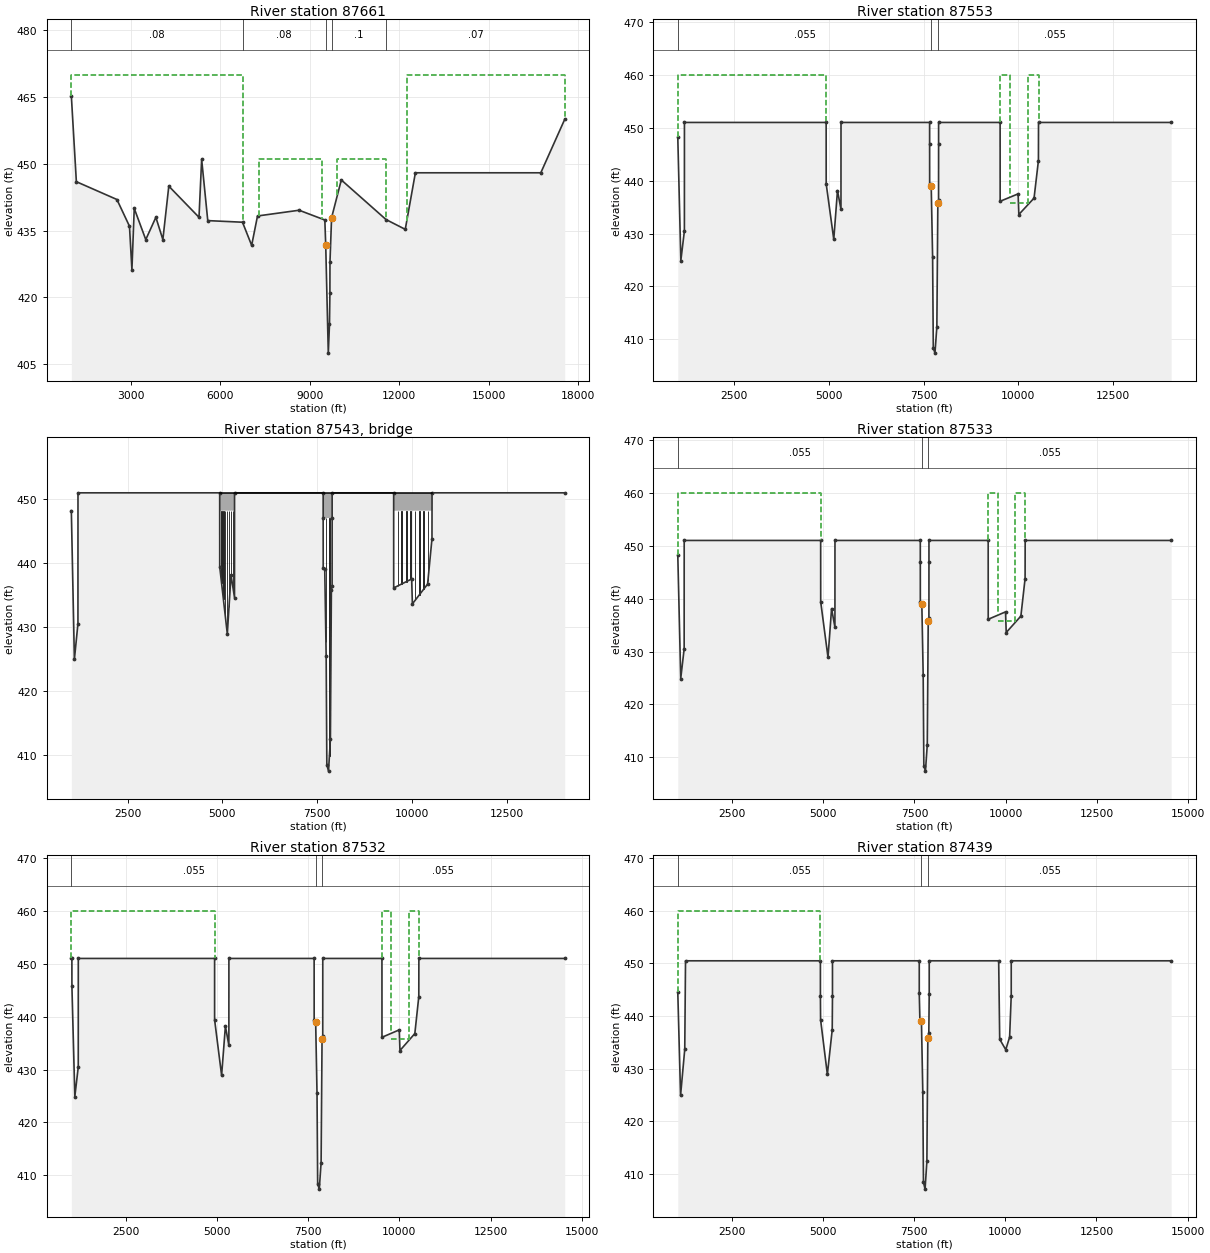
Type RM Length L Ch R = 1 ,87661   ,108,108,108
BEGIN DESCRIPTION:
This cross section corresponds to cross section 87645 of the non-georeferenced CDC model which was the source of this model.
Luna Road Extension USACE Permit Number 199300443
Cross-section 8764 - 90532
Located in LOB.
***************************************
CDC CAR171221-01 Valwood Crossing
In LOB between cross-sections 87541 - 88712.
This project supercedes previous two CDC projects listed below.
CDC PROJECTS: CAR032511-1 AND CAR032511-2 PROPOSED LUNA ROAD LP and #2 LP
************************
END DESCRIPTION:
XS GIS Cut Line= 6
2455887.09514791 7033701.99403132455520.128034097033523.18992697
  2454945.8729497033352.136135222448091.474912437032838.97213531
2439726.696366437033333.714256052439450.78484476 7033400.9532948
#Sta/Elev= 30
    1000  465.29 1168.59     446 2528.56     442 2949.73     436 3031.52  426.22
 3109.47     440 3496.07     433  3834.8     438  4069.4     433  4268.4     445
 5281.31     438  5370.2     451 5575.21  437.26    6740   436.9    7047   431.7
    7243   438.3 8639.04  439.59    9501   437.4    9531   431.7    9617   407.5
    9657     414    9671   421.1    9673   427.9    9727   437.910053.13  446.39
11552.79   437.5   12198   435.312537.56     448 16743.4     448 17544.8     460
#Mann= 5 ,-1,0
    1000     .08       0    6740     .08       0    9531     .05       0
    9727      .1       011552.79     .07       0
#XS Ineff= 4 ,-1
    1000 6740.01     470    7280    9420     451    9920   11560     451
 12249.9 17544.8     470
Permanent Ineff=
       F       F       F       F
Bank Sta=9531,9727
XS Rating Curve= 0 ,0
Exp/Cntr=0.3,0.1

Type RM Length L Ch R = 1 ,87553   ,20,20,20
BEGIN DESCRIPTION:
This cross section corresponds to cross section 87541 of the non-georeferenced CDC model which was the source of this model.
-------------------------------------------------------------------------
CDC PROJECTS: CAR032511-1 AND CAR032511-2 PROPOSED LUNA ROAD LP and #2 LP
CROSS-SECTION 87541 - 89694
-------------------------------------------------------------------------
END DESCRIPTION:
XS GIS Cut Line= 6
2454102.120371437033203.139057892451323.501912927032973.65756147
2449224.330586347032814.517131722447823.491196427032749.33812821
 2446156.59164317032832.145377292441112.34216543 7033123.6423869
#Sta/Elev= 30
  1015.6   448.2    1096   424.9    1190   430.5    1191     451    4930     451
    4931   439.4    5131   428.9    5229  438.12    5321   434.6    5322     451
    7660     451    7660     447    7661   439.3    7702     439    7739   425.5
    7757   408.4    7801   407.4    7851   412.4    7877   435.8    7896   436.4
    7897     447    7897     451    9520     451    9521   436.1    9995   437.5
   10014   433.6 10415.5   436.7   10531   443.8   10533     451   14033     451
#Mann= 3 ,0,0
  1015.6    .055       0    7702     .05       0    7877    .055       0
#XS Ineff= 6 ,-1
    1000    4930     460    4930    7702     439    7877    9520   435.8
    9520    9778     460    9778   10268   435.8   10268   10533     460
Permanent Ineff=
       F       F       F       F       F       F
Bank Sta=7702,7877
XS Rating Curve= 0 ,0
Exp/Cntr=0.5,0.3

Type RM Length L Ch R = 3 ,87543   ,,,
BEGIN DESCRIPTION:
Southern Pacific Railroad
END DESCRIPTION:
Node Name=Southern Pacific
Bridge Culvert--1,0,-1,-1, 0
Deck Dist Width WeirC Skew NumUp NumDn MinLoCord MaxHiCord MaxSubmerge Is_Ogee
1,18,2.6,0, 46, 46, , , 0.95, 0, ,,,
    4930    4930    4974    4984    5023    5033    5072    5082    5121    5131
    5170    5180    5219    5229    5268    5278    5322    5322    7660    7660
    7729    7737    7820    7828    7897    7897    9520    9520  9624.5  9641.5
  9737.5  9754.5  9850.5  9867.5  9963.5  9980.5 10076.5 10093.5 10189.5 10206.5
 10302.5 10319.5 10415.5 10432.5   10533   10533
     451     451     451     451     451     451     451     451     451     451
     451     451     451     451     451     451     451     451     451     451
     451     451     451     451     451     451     451     451     451     451
     451     451     451     451     451     451     451     451     451     451
     451     451     451     451     451     451
     451   448.2   448.2   448.2   448.2   448.2   448.2   448.2   448.2   448.2
   448.2   448.2   448.2   448.2   448.2   448.2   448.2     451     451     447
     447     447     447     447     447     451     451   448.2   448.2   448.2
   448.2   448.2   448.2   448.2   448.2   448.2   448.2   448.2   448.2   448.2
   448.2   448.2   448.2   448.2   448.2     451
    4930    4930    4974    4984    5023    5033    5072    5082    5121    5131
    5170    5180    5219    5229    5268    5278    5322    5322    7660    7660
    7729    7737    7820    7828    7897    7897    9520    9520  9624.5  9641.5
  9737.5  9754.5  9850.5  9867.5  9963.5  9980.5 10076.5 10093.5 10189.5 10206.5
 10302.5 10319.5 10415.5 10432.5   10533   10533
     451     451     451     451     451     451     451     451     451     451
     451     451     451     451     451     451     451     451     451     451
     451     451     451     451     451     451     451     451     451     451
     451     451     451     451     451     451     451     451     451     451
     451     451     451     451     451     451
     451   448.2   448.2   448.2   448.2   448.2   448.2   448.2   448.2   448.2
   448.2   448.2   448.2   448.2   448.2   448.2   448.2     451     451     447
     447     447     447     447     447     451     451   448.2   448.2   448.2
   448.2   448.2   448.2   448.2   448.2   448.2   448.2   448.2   448.2   448.2
   448.2   448.2   448.2   448.2   448.2     451
Pier Skew, UpSta & Num, DnSta & Num=  ,4979, 2 ,4979, 2 , 0 , 0 , 0 ,,
      10      10
     420     450
      10      10
     420     450
Pier Skew, UpSta & Num, DnSta & Num=  ,5028, 2 ,5028, 2 , 0 , 0 , 0 ,,
      10      10
     420     450
      10      10
     420     450
Pier Skew, UpSta & Num, DnSta & Num=  ,5077, 2 ,5077, 2 , 0 , 0 , 0 ,,
      10      10
     420     450
      10      10
     420     450
Pier Skew, UpSta & Num, DnSta & Num=  ,5126, 2 ,5126, 2 , 0 , 0 , 0 ,,
      10      10
     420     450
      10      10
     420     450
Pier Skew, UpSta & Num, DnSta & Num=  ,5175, 2 ,5175, 2 , 0 , 0 , 0 ,,
      10      10
     420     450
      10      10
     420     450
Pier Skew, UpSta & Num, DnSta & Num=  ,5224, 2 ,5224, 2 , 0 , 0 , 0 ,,
      10      10
     420     450
      10      10
     420     450
Pier Skew, UpSta & Num, DnSta & Num=  ,5273, 2 ,5273, 2 , 0 , 0 , 0 ,,
      10      10
     420     450
      10      10
     420     450
Pier Skew, UpSta & Num, DnSta & Num=  ,7733, 2 ,7733, 2 , 0 , 0 , 0 ,,
       8       8
     420     450
       8       8
     420     450
Pier Skew, UpSta & Num, DnSta & Num=  ,7824, 2 ,7824, 2 , 0 , 0 , 0 ,,
       8       8
     420     450
       8       8
     420     450
Pier Skew, UpSta & Num, DnSta & Num=  ,9633, 2 ,9633, 2 , 0 , 0 , 0 ,,
      17      17
     420     450
      17      17
     420     450
Pier Skew, UpSta & Num, DnSta & Num=  ,9729, 2 ,9729, 2 , 0 , 0 , 0 ,,
      17      17
     420     450
      17      17
     420     450
Pier Skew, UpSta & Num, DnSta & Num=  ,9859, 2 ,9859, 2 , 0 , 0 , 0 ,,
      17      17
     420     450
      17      17
     420     450
Pier Skew, UpSta & Num, DnSta & Num=  ,9972, 2 ,9972, 2 , 0 , 0 , 0 ,,
      17      17
     420     450
      17      17
     420     450
Pier Skew, UpSta & Num, DnSta & Num=  ,10085, 2 ,10085, 2 , 0 , 0 , 0 ,,
      17      17
     420     450
      17      17
     420     450
Pier Skew, UpSta & Num, DnSta & Num=  ,10198, 2 ,10198, 2 , 0 , 0 , 0 ,,
      17      17
     420     450
      17      17
     420     450
Pier Skew, UpSta & Num, DnSta & Num=  ,10311, 2 ,10311, 2 , 0 , 0 , 0 ,,
      17      17
     420     450
      17      17
     420     450
Pier Skew, UpSta & Num, DnSta & Num=  ,10424, 2 ,10424, 2 , 0 , 0 , 0 ,,
      17      17
     420     450
      17      17
     420     450
BR Coef= 1 , 0 , 0 ,1.05, 0 ,,,0.8,-1,0.5,1,
WSPro=,,,, 1 ,,,, 0 ,,,, 0 ,,,,-1 ,-1 ,-1 , 0 , 0 , 0 , 0 , 0
BC Design=,, 0 ,, 0 ,,,,,,
BC HTab HWMax=451
BC Use User HTab Curves=0
BC User HTab FreeFlow(D)= 0

Type RM Length L Ch R = 1 ,87533   ,1,1,1
BEGIN DESCRIPTION:
This cross section corresponds to cross section 87522 of the non-georeferenced CDC model which was the source of this model.
END DESCRIPTION:
XS GIS Cut Line= 6
2454120.089167517033189.222747132451256.687085937032950.51850013
2449170.19257125 7032792.92695182447774.69765884 7032732.9585678
2446114.146846097032813.27960138 2440630.59999147033120.73640699
#Sta/Elev= 30
  1015.6   448.2    1096   424.9    1190   430.5    1191     451    4930     451
    4931   439.4    5131   428.9    5229  438.12    5321   434.6    5322     451
    7660     451    7660     447    7661   439.3    7702     439    7739   425.5
    7757   408.4    7801   407.4    7851   412.4    7877   435.8    7896   436.4
    7897     447    7897     451    9520     451    9521   436.1    9995   437.5
   10014   433.6 10415.5   436.7   10531   443.8   10533     451   14533     451
#Mann= 3 ,0,0
  1015.6    .055       0    7702     .05       0    7877    .055       0
#XS Ineff= 6 ,-1
    1000    4930     460    4930    7702     439    7877    9520   435.8
    9520    9778     460    9778   10268   435.8   10268   10533     460
Permanent Ineff=
       F       F       F       F       F       F
Bank Sta=7702,7877
XS Rating Curve= 0 ,0
Exp/Cntr=0.5,0.3

Type RM Length L Ch R = 1 ,87532   ,120,93,70
BEGIN DESCRIPTION:
This cross section corresponds to cross section 87521 of the non-georeferenced CDC model which was the source of this model.
END DESCRIPTION:
XS GIS Cut Line= 6
2454132.295179847033189.360870212451253.417079337032949.31935555
2449167.344807927032791.790799222447772.13106292 7032732.0963648
2446111.913910937032812.286493142440627.212328417033119.31093543
#Sta/Elev= 30
    1000     451    1015     451    1016   445.7    1096   424.9    1190   430.5
    1191     451    4930     451    4930   439.4    5122   428.9    5226   438.2
    5321   434.6    5322     451    7660     451    7661   439.3    7702     439
    7739   425.5    7757   408.4    7801   407.4    7851   412.4    7877   435.8
    7896   436.4    7897     451    9520     451    9521   436.1    9995   437.5
   10014   433.6   10422   436.8   10531   443.8   10533     451   14533     451
#Mann= 3 ,0,0
    1000    .055       0    7702     .05       0    7877    .055       0
#XS Ineff= 6 ,-1
    1000    4930     460    4930    7702     439    7877    9520   435.8
    9520    9778     460    9778   10268   435.8   10268   10533     460
Permanent Ineff=
       F       F       F       F       F       F
Bank Sta=7702,7877
XS Rating Curve= 0 ,0
Exp/Cntr=0.5,0.3

Type RM Length L Ch R = 1 ,87439   ,85,85,85
BEGIN DESCRIPTION:
This cross section corresponds to cross section 87428 of the non-georeferenced CDC model which was the source of this model.
END DESCRIPTION:
XS GIS Cut Line= 6
  2454099.7762167033113.246849212451670.286324357032924.21146613
2450948.477072427032837.734276882448898.740358267032685.89796638
2447533.458640017032651.919687882440595.786211237032971.39049108
#Sta/Elev= 30
    1020   444.5    1096   424.9    1211   433.7    1232   450.5    4931   450.5
    4931  443.78    4936   439.3    5122   428.9    5255   437.4    5262  443.78
    5262   450.5    7642   450.5    7642  444.29    7659   439.3    7702     439
    7739   425.5    7757   408.4    7801   407.1    7851   412.4    7877   435.8
    7904   436.8    7915  444.18    7915   450.5    9820   450.5    9848   435.6
   10014   433.6   10120     436   10164   443.9   10164   450.5   14550   450.5
#Mann= 3 ,0,0
    1020    .055       0    7702     .05       0    7877    .055       0
#XS Ineff= 2 , 0
       0    4931     460               0
Permanent Ineff=
       F       F
Bank Sta=7702,7877
XS Rating Curve= 0 ,0
Exp/Cntr=0.5,0.3

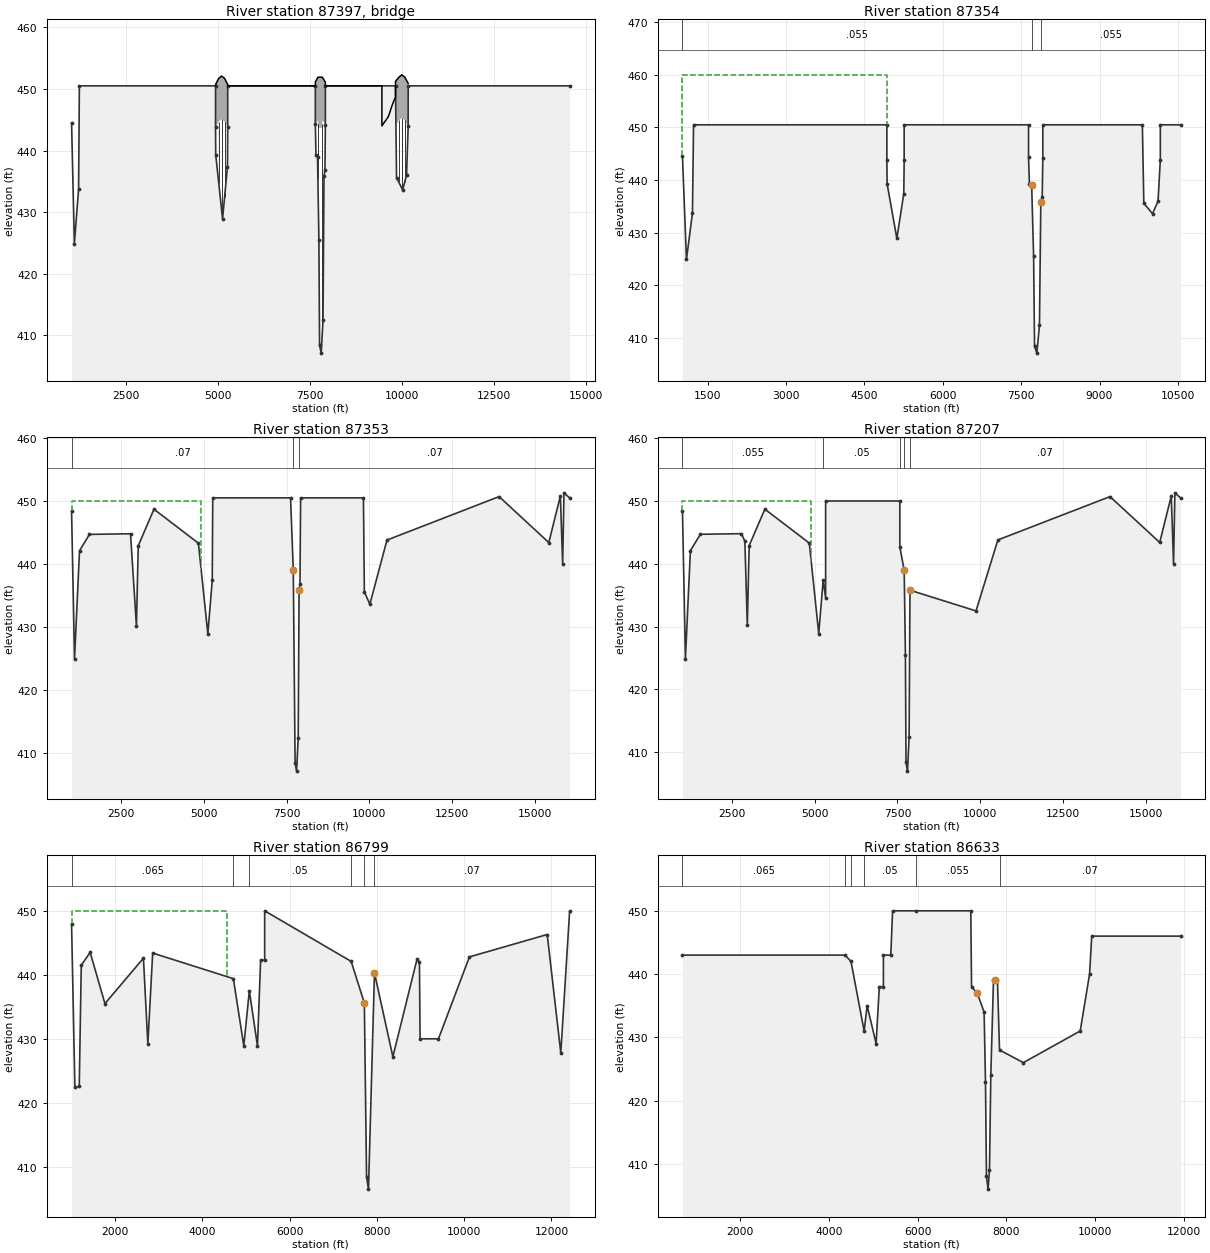
Type RM Length L Ch R = 3 ,87397   ,,,
BEGIN DESCRIPTION:
Belt Line Road
END DESCRIPTION:
Node Name=Belt Line Road
Bridge Culvert--1,0,-1,-1, 0
Deck Dist Width WeirC Skew NumUp NumDn MinLoCord MaxHiCord MaxSubmerge Is_Ogee
0.5,84,2.6,0, 38, 38, , , 0.95, 0, ,,,
    4931    4931  5015.8  5018.3  5095.8  5098.3  5175.8  5178.3    5262    5262
    5369    7520    7642    7642  7710.8  7713.3  7830.8  7833.3    7915    7915
    8024    9450    9451    9508    9593    9639    9720    9791    9820    9820
    9830  9910.8  9913.3  9990.8  9993.3 10070.8 10073.3   10164
   450.5   450.7  451.69  451.71  452.09  452.09  451.71  451.69   450.7   450.5
   450.5   450.5   450.5   451.1  451.89   451.9   451.9  451.89   451.1   450.5
   450.5   450.5     444   444.5   445.2   445.7   447.2   448.3   448.6   451.2
   451.3  451.89  451.91  452.29  452.29  451.91  451.89   450.9
   450.5  443.78  444.69  444.71  445.09  445.09  444.71  444.69  443.78   450.5
   450.5   450.5   450.5  444.29  444.89   443.7   443.7  444.89  444.29   450.5
   450.5   450.5     444   444.5   445.2   445.7   447.2   448.3   448.6   443.9
     444  444.89  444.91  445.29  445.29  444.91  444.89   443.9
    4931    4931  5015.8  5018.3  5095.8  5098.3  5175.8  5178.3    5262    5262
    5369    7520    7642    7642  7710.8  7713.3  7830.8  7833.3    7915    7915
    8024    9450    9451    9508    9593    9639    9720    9791    9820    9820
    9830  9910.8  9913.3  9990.8  9993.3 10070.8 10073.3   10164
   450.5   450.7  451.69  451.71  452.09  452.09  451.71  451.69   450.7   450.5
   450.5   450.5   450.5   451.1  451.89   451.9   451.9  451.89   451.1   450.5
   450.5   450.5     444   444.5   445.2   445.7   447.2   448.3   448.6   451.2
   451.3  451.89  451.91  452.29  452.29  451.91  451.89   450.9
   450.5  443.78  444.69  444.71  445.09  445.09  444.71  444.69  443.78   450.5
   450.5   450.5   450.5  444.29  444.89   443.7   443.7  444.89  444.29   450.5
   450.5   450.5     444   444.5   445.2   445.7   447.2   448.3   448.6   443.9
     444  444.89  444.91  445.29  445.29  444.91  444.89   443.9
Pier Skew, UpSta & Num, DnSta & Num=  ,5017.05, 2 ,5017.05, 2 , 0 , 0 , 0 ,,
     2.5     2.5
     430     450
     2.5     2.5
     430     450
Pier Skew, UpSta & Num, DnSta & Num=  ,5097.05, 2 ,5097.05, 2 , 0 , 0 , 0 ,,
     2.5     2.5
     430     450
     2.5     2.5
     430     450
Pier Skew, UpSta & Num, DnSta & Num=  ,5177.05, 2 ,5177.05, 2 , 0 , 0 , 0 ,,
     2.5     2.5
     430     450
     2.5     2.5
     430     450
Pier Skew, UpSta & Num, DnSta & Num=  ,7712.05, 2 ,7712.05, 2 , 0 , 0 , 0 ,,
     2.5     2.5
     410     450
     2.5     2.5
     410     450
Pier Skew, UpSta & Num, DnSta & Num=  ,7832.05, 2 ,7832.05, 2 , 0 , 0 , 0 ,,
     2.5     2.5
     410     450
     2.5     2.5
     410     450
Pier Skew, UpSta & Num, DnSta & Num=  ,9912.05, 2 ,9912.05, 2 , 0 , 0 , 0 ,,
     2.5     2.5
     410     450
     2.5     2.5
     410     450
Pier Skew, UpSta & Num, DnSta & Num=  ,9992.05, 2 ,9992.05, 2 , 0 , 0 , 0 ,,
     2.5     2.5
     410     450
     2.5     2.5
     410     450
Pier Skew, UpSta & Num, DnSta & Num=  ,10072.05, 2 ,10072.05, 2 , 0 , 0 , 0 ,,
     2.5     2.5
     410     450
     2.5     2.5
     410     450
BR Coef= 1 , 0 , 0 ,1.05, 0 ,,,0.8,-1,0.5,1,
WSPro=,,,, 1 ,,,, 0 ,,,, 0 ,,,,-1 ,-1 ,-1 , 0 , 0 , 0 , 0 , 0
BC Design=,, 0 ,, 0 ,,,,,,
BC HTab HWMax=450.5
BC Use User HTab Curves=0
BC User HTab FreeFlow(D)= 0

Type RM Length L Ch R = 1 ,87354   ,1,1,1
BEGIN DESCRIPTION:
This cross section corresponds to cross section 87339 of the non-georeferenced CDC model which was the source of this model.
END DESCRIPTION:
XS GIS Cut Line= 6
2454096.437968087033066.68066938 2451360.00446467032828.53350788
2450655.638419247032730.874910552448644.077809847032584.72428422
2447305.792756777032575.173778382444591.557699687032674.81465521
#Sta/Elev= 30
    1020   444.5    1096   424.9    1211   433.7    1232   450.5    4931   450.5
    4931  443.78    4936   439.3    5122   428.9    5255   437.4    5262  443.78
    5262   450.5    7642   450.5    7642  444.29    7659   439.3    7702     439
    7739   425.5    7757   408.4    7801   407.1    7851   412.4    7877   435.8
    7904   436.8    7915  444.18    7915   450.5    9820   450.5    9848   435.6
   10014   433.6   10120     436   10164   443.9   10164   450.5   10550   450.5
#Mann= 3 ,0,0
    1020    .055       0    7702     .05       0    7877    .055       0
#XS Ineff= 2 , 0
       0    4931     460               0
Permanent Ineff=
       F       F
Bank Sta=7702,7877
XS Rating Curve= 0 ,0
Exp/Cntr=0.5,0.3

Type RM Length L Ch R = 1 ,87353   ,99,146,258
BEGIN DESCRIPTION:
This cross section corresponds to cross section 87338 of the non-georeferenced CDC model which was the source of this model.
END DESCRIPTION:
XS GIS Cut Line= 6
  2454105.186966 7033067.3151826 2451356.5897733 7032827.4649405
 2450652.3930189 7032729.6787187 2448100.9394604 7032577.6547446
 2445703.8589528 7032630.5614629 2439097.1060902 7032909.7754714
#Sta/Elev= 30
    1007   448.4    1096   424.9    1247   442.1    1548   444.7    2787   444.8
    2965   430.2    3021   442.9    3495   448.7    4837   443.3    5122   428.9
    5255   437.4    5270   450.5    7620   450.5    7702     439    7757   408.4
    7801   407.1    7851   412.4    7877   435.8    7904   436.8    7924   450.5
    9820   450.5    9848   435.6   10014   433.6   10531   443.8   13917   450.7
   15418   443.4   15767   450.8   15836     440   15876   451.3   16046   450.5
#Mann= 3 ,0,0
    1007     .07       0    7702    .055       0    7877     .07       0
#XS Ineff= 2 , 0
       0    4925     450               0
Permanent Ineff=
       F       F
Bank Sta=7702,7877
XS Rating Curve= 0 ,0
Exp/Cntr=0.3,0.1

Type RM Length L Ch R = 1 ,87207   ,308,408,390
BEGIN DESCRIPTION:
This cross section corresponds to cross section 87191 of the non-georeferenced CDC model which was the source of this model.
---------------------------------------------------------------------
UPSTREAM END OF CDC COP082301-1 DEVELOPMENT AT 1550 E. BELT LINE ROAD.
CROSS-SECTION 86107 - 87191
---------------------------------------------------------------------
END DESCRIPTION:
XS GIS Cut Line= 6
   2454060.74775 7032917.9004551 2450850.1058781 7032670.0259509
 2450173.5688453 7032553.5389791 2448224.0310777 7032416.5881376
 2443228.3750586 7032535.8631615 2439047.8611099 7032583.4418065
#Sta/Elev= 30
    1007   448.4    1096   424.9    1247   442.1    1548   444.7    2787   444.8
    2891   443.6    2965   430.2    3021   442.9    3495   448.7    4837   443.3
    5122   428.9    5255   437.4    5330   434.6    5330     450    7570     450
    7570   442.7    7702     439    7739   425.5    7757   408.4    7801     407
    7851   412.4    7877   435.8    9871   432.5   10531   443.8   13917   450.7
   15418   443.4   15767   450.8   15836     440   15876   451.3   16046   450.5
#Mann= 5 ,-1,0
    1007    .055       0    5255     .05       0    7570      .1       0
    7702    .055       0    7877     .07       0
#XS Ineff= 2 , 0
       0    4900     450               0
Permanent Ineff=
       F       F
Bank Sta=7702,7877
XS Rating Curve= 0 ,0
Exp/Cntr=0.3,0.1

Type RM Length L Ch R = 1 ,86799   ,140,166,166
BEGIN DESCRIPTION:
This cross section corresponds to cross section 86793 of the non-georeferenced CDC model which was the source of this model.
----------------
XS 86799 to 87207 retored to 1991 topo to remove project COP 082310-01
END DESCRIPTION:
XS GIS Cut Line= 5
  2453906.375684 7032326.3898271 2453299.8099682 7032460.7291254
 2447409.0589544 7032071.9759659 2442924.8950225 7032155.9000106
 2442570.1162045 7031975.0332464
#Sta/Elev= 30
    1007   447.9    1083   422.4    1183   422.6    1229   441.5    1433   443.5
    1771   435.5    2653   442.6    2754   429.2    2865   443.4    4713   439.4
    4952   428.9    5079   437.5    5265   428.9    5337   442.3    5430   442.3
    5430     450    7411   442.1    7713   435.6    7764   408.4    7808  406.51
    7945   440.3  8366.6   427.2  8918.4   442.4  8974.8     442    8990     430
    9411     430   10120   442.8   11902   446.3   12213   427.8   12415   449.9
#Mann= 6 ,-1,0
    1007    .065       0    4713    .055       0    5079     .05       0
    7411      .1       0    7713    .055       0    7945     .07       0
#XS Ineff= 2 , 0
       0    4560     450               0
Permanent Ineff=
       F       F
Bank Sta=7713,7945
XS Rating Curve= 0 ,0
Exp/Cntr=0.3,0.1

Type RM Length L Ch R = 1 ,86633   ,431,510,1114
BEGIN DESCRIPTION:
This cross section corresponds to cross section 86551 of the non-georeferenced CDC model which was the source of this model.
END DESCRIPTION:
XS GIS Cut Line= 6
2454012.779178877032283.428838422453713.343142387032265.04242904
2452715.223020747032203.754397792448004.311044757031914.48809189
2446014.163122187031915.053707552442816.607098677031620.84253979
#Sta/Elev= 30
     700     443    4362     443    4497     442    4793     431    4861     435
    5063     429    5135     438    5227     438    5227     443    5394     443
    5434     450    5960     450    7196     450    7213     438    7340     437
    7496     434    7527     423    7549     408    7585     406    7617     409
    7647     424    7707     439    7737     439    7797     439    7843     428
    8380     426    9661     431    9872     440    9921     446   11921     446
#Mann= 6 ,-1,0
     700    .065       0    4362    .065       0    4497    .055       0
    4793     .05       0    5960    .055       0    7843     .07       0
Bank Sta=7340,7737
XS Rating Curve= 0 ,0
Exp/Cntr=0.3,0.1

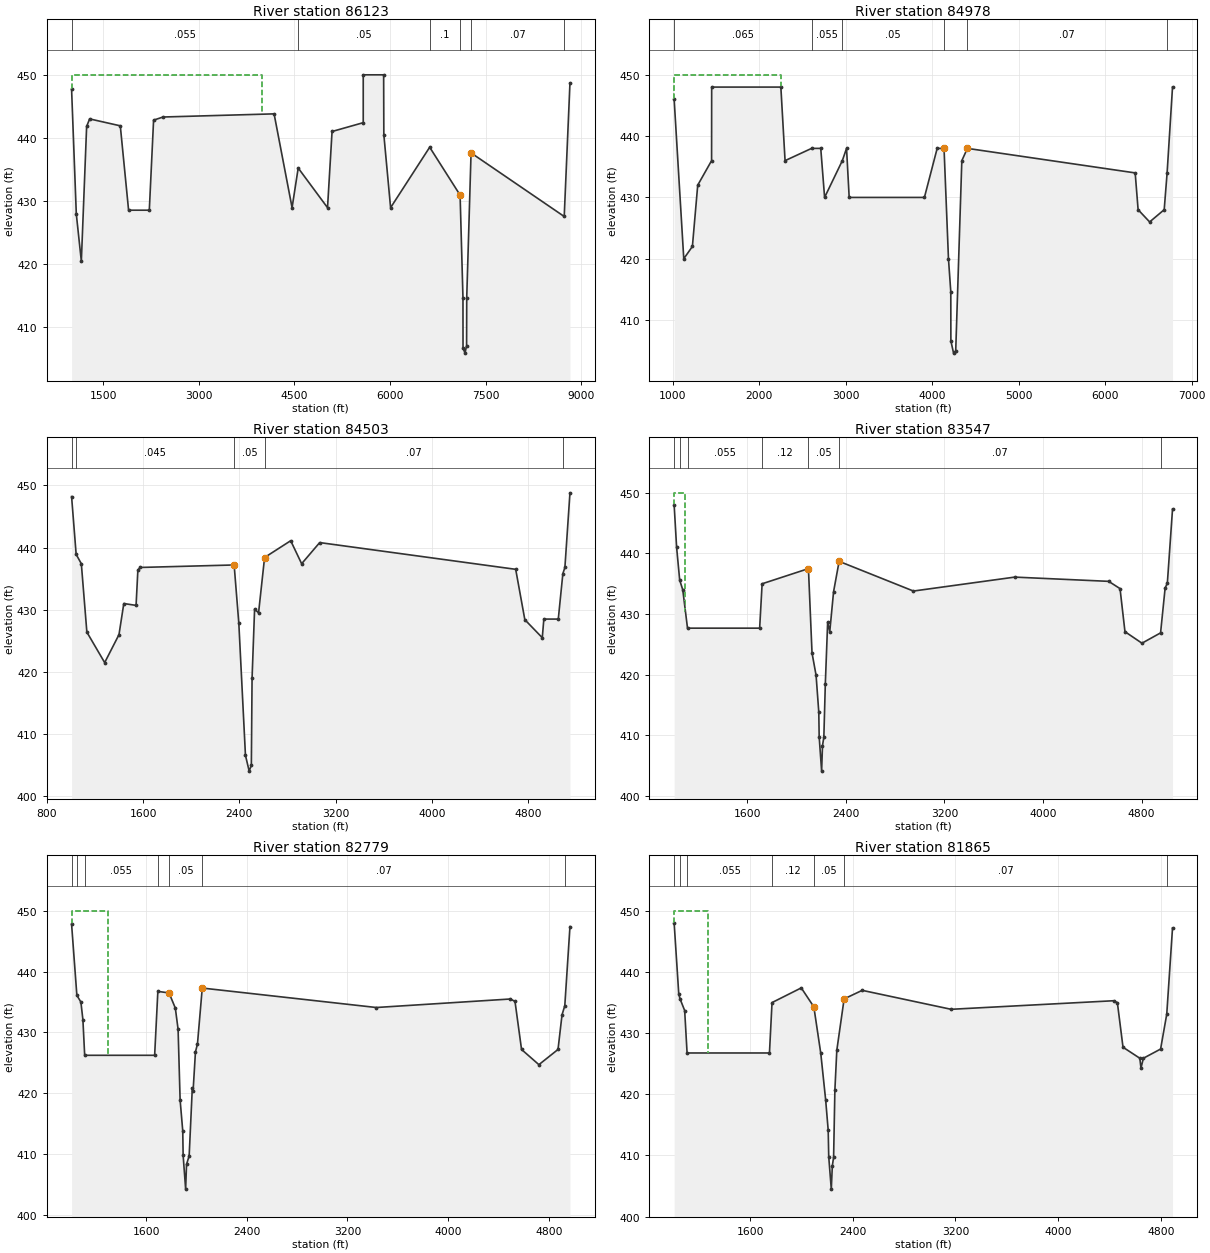
Type RM Length L Ch R = 1 ,86123   ,479,1145,299
BEGIN DESCRIPTION:
This cross section corresponds to cross section 86107 of the non-georeferenced CDC model which was the source of this model.
------------------------------------------------------------------------
DOWNSTREAM END OF CDC COP082301-1 DEVELOPMENT AT 1550 E. BELT LINE ROAD.
CROSS-SECTION 86107 - 87191
------------------------------------------------------------------------
END DESCRIPTION:
XS GIS Cut Line= 4
2453555.21398494 7031698.60040032453070.766134927031820.77404046
2447563.644931357031550.248990972445897.360862347030862.53908031
#Sta/Elev= 30
    1006   447.7    1080   427.9    1159   420.4    1242   441.8    1289     443
    1770   441.9    1900   428.5    2225   428.5    2292   442.8    2440   443.3
    4182   443.8    4464   428.9    4560   435.2    5020   428.9    5091     441
    5580   442.4    5580     450    5900     450    5903   440.5    6009   428.9
    6622   438.5    7099   430.9    7144   414.6    7145   406.6    7176   405.8
    7201     407    7203   414.6    7271   437.6    8732   427.5    8822   448.7
#Mann= 6 ,-1,0
    1006    .055       0    4560     .05       0    6622      .1       0
    7099     .05       0    7271     .07       0    8732     .03       0
#XS Ineff= 2 , 0
       0    4000     450               0
Permanent Ineff=
       F       F
Bank Sta=7099,7271
XS Rating Curve= 0 ,0
Exp/Cntr=0.3,0.1

Type RM Length L Ch R = 1 ,84978   ,512,475,221
BEGIN DESCRIPTION:
This cross section corresponds to cross section 84959 of the non-georeferenced CDC model which was the source of this model.
END DESCRIPTION:
XS GIS Cut Line= 5
 2451546.38565357030892.684361222451228.805908087031204.77297588
  2448559.7479267031205.354995712448354.105948847031077.09901863
  2445978.1664757030697.18212755
#Sta/Elev= 30
  1016.1     446  1127.3     420  1227.1     422  1288.7     432    1449     436
    1450     448    2250     448  2298.6     436  2605.3     438  2711.4     438
  2755.8     430  2960.7     436  3009.5     438    3040     430    3910     430
  4057.5     438  4136.9     438  4188.1     420    4215   414.6    4216   406.6
    4247   404.6    4272     405  4342.6     436  4407.1     438  6347.1     434
    6381     428  6514.3     426  6682.7     428  6716.3     434  6778.9     448
#Mann= 6 ,-1,0
  1016.1    .065       0  2605.3    .055       0  2960.7     .05       0
  4136.9    .055       0  4407.1     .07       0  6716.3     .03       0
#XS Ineff= 2 , 0
       0    2250     450               0
Permanent Ineff=
       F       F
Bank Sta=4136.9,4407.1
XS Rating Curve= 0 ,0
Exp/Cntr=0.3,0.1

Type RM Length L Ch R = 1 ,84503   ,900,956,650
BEGIN DESCRIPTION:
This cross section corresponds to cross section 84436 of the non-georeferenced CDC model which was the source of this model.
END DESCRIPTION:
XS GIS Cut Line= 3
2450143.405519847030683.264832562448828.647978757030744.41595696
2446012.520736997030510.55126722
#Sta/Elev= 30
    1006   448.2    1044   438.9    1087   437.4    1133   426.4    1281   421.5
    1400     426    1440     431    1542   430.7    1557   436.4    1576   436.8
    2357   437.2    2396   427.8    2451   406.6    2482  404.05    2500     405
    2506     419    2527   430.1    2560   429.5    2610   438.4    2827   441.1
    2918   437.4    3068   440.8    4697   436.5    4773   428.4    4918   425.5
    4931   428.5    5051   428.5    5089   435.8    5106   436.8    5148   448.8
#Mann= 5 ,-1,0
    1006     .03       0    1044    .045       0    2357     .05       0
    2610     .07       0    5089     .03       0
Bank Sta=2357,2610
XS Rating Curve= 0 ,0
Exp/Cntr=0.3,0.1

Type RM Length L Ch R = 1 ,83547   ,700,768,690
BEGIN DESCRIPTION:
This cross section corresponds to cross section 83530 of the non-georeferenced CDC model which was the source of this model.
END DESCRIPTION:
XS GIS Cut Line= 2
2450134.949828097029817.165514892446090.594727847029889.38584289
#Sta/Elev= 30
    1006     448    1026     441    1051   435.6    1076     434  1114.4  427.68
    1700  427.68    1720     435    2096   437.5    2125   423.6    2158   419.9
    2180   413.8    2183   409.8    2203   404.1    2210   408.3    2221   409.7
    2233   418.5    2252   428.7    2269   427.1    2300   433.7    2345   438.7
    2948   433.8    3770   436.1    4533   435.4    4625   434.2    4665   427.1
    4803   425.2    4954   426.9    4991   434.3    5009   435.1    5051   447.3
#Mann= 7 ,-1,0
    1006     .03       0    1051    .045       0  1114.4    .055       0
    1720     .12       0    2096     .05       0    2345     .07       0
    4954     .03       0
#XS Ineff= 2 , 0
       0    1098     450               0
Permanent Ineff=
       F       F
Bank Sta=2096,2345
XS Rating Curve= 0 ,0
Exp/Cntr=0.3,0.1

Type RM Length L Ch R = 1 ,82779   ,920,914,780
BEGIN DESCRIPTION:
This cross section corresponds to cross section 82762 of the non-georeferenced CDC model which was the source of this model.
END DESCRIPTION:
XS GIS Cut Line= 2
2450139.973768177029120.920844382446178.006298427029211.37670022
#Sta/Elev= 30
    1006   447.8    1048   436.1    1080     435    1096   432.1 1110.11  426.24
 1666.53  426.24    1692  436.75    1781   436.5    1831     434    1853   430.5
    1869   418.9    1890   413.8    1893   409.8    1913  404.23    1920   408.3
    1941   409.7    1966   420.9    1972   420.3    1991   426.8    2007   428.1
    2045   437.3    3429   434.1    4496   435.5    4532   435.1    4584   427.2
    4722   424.7    4874   427.2    4906   432.9    4928   434.4    4969   447.4
#Mann= 7 ,-1,0
    1006     .03       0    1048    .045       0 1110.11    .055       0
    1692     .12       0    1781     .05       0    2045     .07       0
    4928     .03       0
#XS Ineff= 2 , 0
       0    1298     450               0
Permanent Ineff=
       F       F
Bank Sta=1781,2045
XS Rating Curve= 0 ,0
Exp/Cntr=0.3,0.1

Type RM Length L Ch R = 1 ,81865   ,1090,1269,1200
BEGIN DESCRIPTION:
This cross section corresponds to cross section 81848 of the non-georeferenced CDC model which was the source of this model.
END DESCRIPTION:
XS GIS Cut Line= 3
2450144.67126533 7028172.55627132448247.31088683 7028425.5380488
2446276.46246633 7028425.5380488
#Sta/Elev= 30
    1007     448    1043   436.4    1053   435.6    1089   433.7  1107.8  426.76
    1750  426.76    1770     435    1998   437.4    2096   434.3    2150   426.7
    2188   419.1    2208   414.1    2212   409.8    2232   404.5    2240   408.3
    2250   409.7    2260   420.7    2275   427.2    2332   435.6    2473     437
    3166   433.9    4432   435.3    4462     435    4506   427.7    4637   425.9
    4646   424.3    4665   425.9    4799   427.4    4847   433.1    4892   447.2
#Mann= 7 ,-1,0
    1007     .03       0    1053    .045       0  1107.8    .055       0
    1770     .12       0    2096     .05       0    2332     .07       0
    4847     .03       0
#XS Ineff= 2 , 0
       0    1274     450               0
Permanent Ineff=
       F       F
Bank Sta=2096,2332
XS Rating Curve= 0 ,0
Exp/Cntr=0.3,0.1