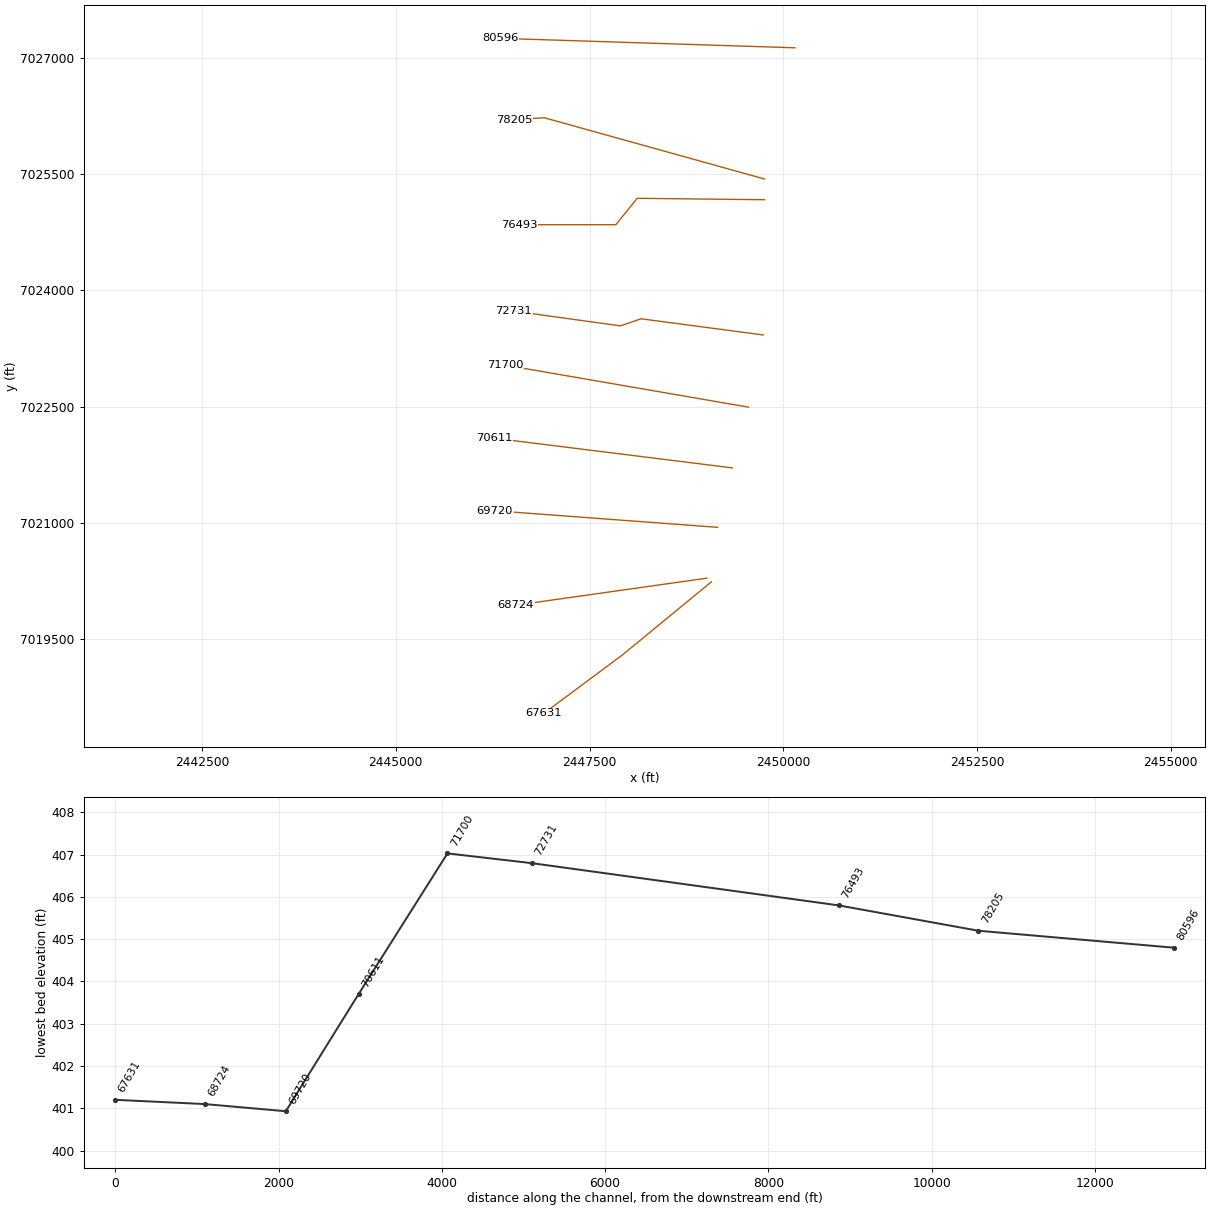
HEC-RAS study CDC_Consolidated_Model.prj: Upper Trinity CDC Consolidated Model

--- CDC_Consolidated_Model.g04 (geometry) --- (continued)

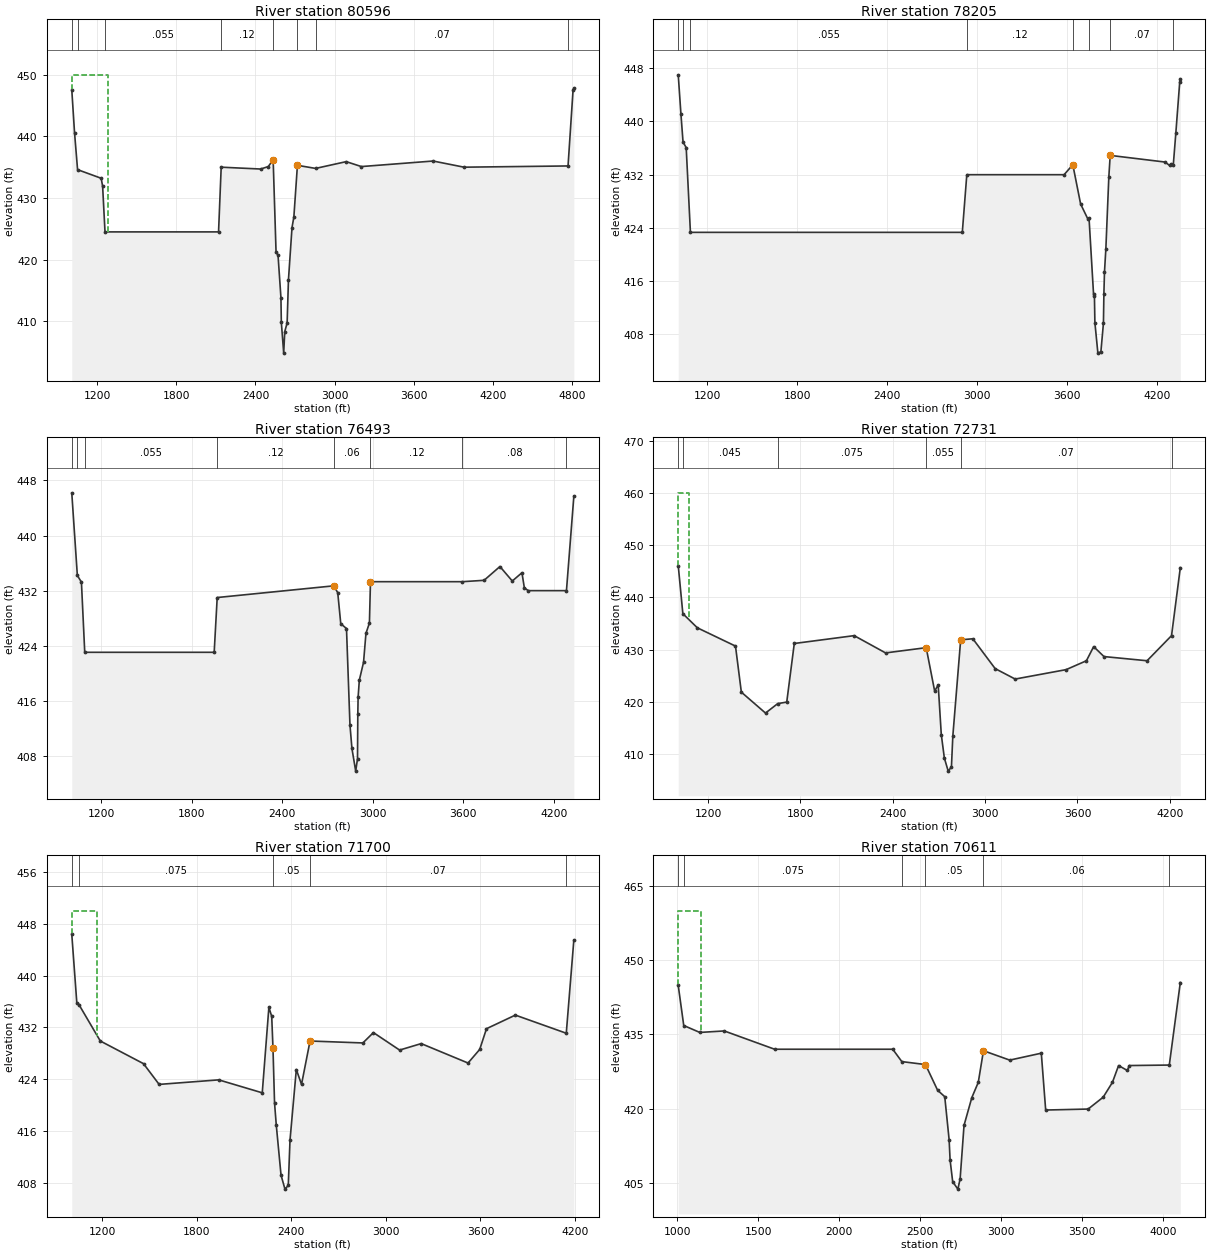
Type RM Length L Ch R = 1 ,80596   ,1599,2391,1030
BEGIN DESCRIPTION:
This cross section corresponds to cross section 80579 of the non-georeferenced CDC model which was the source of this model.
END DESCRIPTION:
XS GIS Cut Line= 2
2450151.002617517027133.076722962446345.963639687027255.25626864
#Sta/Elev= 30
    1007   447.6    1028   440.6    1051   434.6    1230   433.2    1241   431.9
    1259  424.49    2120  424.49    2140     435    2439   434.7    2497   435.1
    2534   436.2    2556   421.2    2571   420.7    2593   413.8    2596   409.8
    2614   404.8    2622   408.3    2640   409.7    2650   416.7    2677   425.2
    2691   426.9    2718   435.3    2856   434.8    3088   435.9    3203   435.1
    3747     436    3981     435    4770   435.2    4808   447.5    4814   447.8
#Mann= 8 ,-1,0
    1007     .03       0    1051    .045       0    1259    .055       0
    2140     .12       0    2534    .055       0    2718     .12       0
    2856     .07       0    4770     .03       0
#XS Ineff= 2 , 0
       0    1279     450               0
Permanent Ineff=
       F       F
Bank Sta=2534,2718
XS Rating Curve= 0 ,0
Exp/Cntr=0.3,0.1

Type RM Length L Ch R = 1 ,78205   ,800,1712,1380
BEGIN DESCRIPTION:
This cross section corresponds to cross section 78187 of the non-georeferenced CDC model which was the source of this model.
END DESCRIPTION:
XS GIS Cut Line= 3
2449757.539821747025438.934770052446916.428049927026229.58115463
2446522.145373917026207.05101597
#Sta/Elev= 30
    1008     447    1026   441.1    1040   436.9    1061  436.07 1089.14  423.34
    2900  423.34    2930     432    3578     432    3636   433.5    3688   427.6
    3735   425.4    3744   425.5    3774   414.1    3780   413.8    3783   409.8
    3803   405.2    3823   405.4    3840   409.7    3843   414.1    3847   417.4
    3856   420.8    3876   431.7    3885   434.9    4250   433.9    4280   433.4
    4289   433.6    4305   433.4    4322   438.2    4348   445.9    4352   446.4
#Mann= 8 ,-1,0
    1008     .03       0    1040    .045       0 1089.14    .055       0
    2930     .12       0    3636     .12       0    3744    .055       0
    3885     .07       0    4305     .03       0
Bank Sta=3636,3885
XS Rating Curve= 0 ,0
Exp/Cntr=0.3,0.1

Type RM Length L Ch R = 1 ,76493   ,1740,3762,1200
BEGIN DESCRIPTION:
This cross section corresponds to cross section 76475 of the non-georeferenced CDC model which was the source of this model.
END DESCRIPTION:
XS GIS Cut Line= 4
2449757.729453927025171.567522632448114.222898427025189.82896905
2447839.728040587024848.789952962446593.120297587024848.78995296
#Sta/Elev= 30
    1006   446.2    1043   434.2    1070  433.24 1091.99  423.05    1950  423.05
    1970     431    2743   432.7    2769   431.7    2789   427.2    2827   426.5
    2850   412.5    2863   409.1    2888   405.8    2900   407.6    2902   414.1
    2904   416.5    2912     419    2940   421.6    2956   425.8    2979   427.3
    2986   433.3    3595   433.3    3739   433.5    3844   435.5    3926   433.4
    3990   434.6    4006   432.4    4032     432    4285     432    4334   445.7
#Mann= 8 ,-1,0
    1006     .03       0    1043    .045       0 1091.99    .055       0
    1970     .12       0    2743     .06       0    2986     .12       0
    3595     .08       0    4285     .03       0
Bank Sta=2743,2986
XS Rating Curve= 0 ,0
Exp/Cntr=0.3,0.1

Type RM Length L Ch R = 1 ,72731   ,940,1031,740
BEGIN DESCRIPTION:
This cross section corresponds to cross section 72713 of the non-georeferenced CDC model which was the source of this model.
END DESCRIPTION:
XS GIS Cut Line= 4
2449740.069056187023425.39581813 2448164.13093517023634.35898288
2447897.953974017023542.861134382446520.236257027023733.20392954
#Sta/Elev= 30
    1006   446.1    1036   436.9    1130   434.2    1378   430.7    1416   421.9
    1573   417.9    1652   419.7    1711     420    1760   431.2    2149   432.7
    2353   429.4    2617   430.4    2672   422.1    2695   423.3    2715   413.8
    2735   409.3    2760   406.8    2781   407.6    2790   413.5    2841   431.9
    2920   432.1    3065   426.4    3195   424.4    3526   426.2    3658   427.9
    3705   430.6    3772   428.7    4052   427.9    4211   432.7    4268   445.7
#Mann= 6 ,-1,0
    1006     .03       0    1036    .045       0    1652    .075       0
    2617    .055       0    2841     .07       0    4211     .03       0
#XS Ineff= 2 , 0
       0    1077     460               0
Permanent Ineff=
       F       F
Bank Sta=2617,2841
XS Rating Curve= 0 ,0
Exp/Cntr=0.3,0.1

Type RM Length L Ch R = 1 ,71700   ,850,1089,920
BEGIN DESCRIPTION:
This cross section corresponds to cross section 71682 of the non-georeferenced CDC model which was the source of this model.
END DESCRIPTION:
XS GIS Cut Line= 2
  2449549.1829557022493.442301472446411.683324527023035.61608589
#Sta/Elev= 30
    1008   446.4    1040   435.8    1054   435.5    1189   429.9    1463   426.4
    1562   423.2    1940   423.9    2216   421.9    2258   435.1    2276   433.7
    2284   428.8    2294   420.3    2305   416.9    2335   409.2    2360  407.03
    2381   407.6    2392   414.6    2432   425.5    2465   423.2    2519   429.9
    2854   429.6    2921   431.2    3087   428.5    3224   429.5    3521   426.5
    3595   428.6    3638   431.8    3821   433.9    4144   431.1    4192   445.5
#Mann= 5 ,-1,0
    1008     .03       0    1054    .075       0    2284     .05       0
    2519     .07       0    4144     .03       0
#XS Ineff= 2 , 0
       0    1171     450               0
Permanent Ineff=
       F       F
Bank Sta=2284,2519
XS Rating Curve= 0 ,0
Exp/Cntr=0.3,0.1

Type RM Length L Ch R = 1 ,70611   ,829,891,899
BEGIN DESCRIPTION:
This cross section corresponds to cross section 70593 of the non-georeferenced CDC model which was the source of this model.
END DESCRIPTION:
XS GIS Cut Line= 2
2449341.456992517021709.253253042446266.247591767022092.51364139
#Sta/Elev= 30
    1006   444.9    1040   436.8    1139   435.4    1290   435.7    1601     432
    2330     432    2386   429.5    2532   428.9    2607   423.7    2651   422.4
    2678   413.7    2684   409.6    2700   405.2    2732   403.7    2746   405.8
    2770   416.6    2818   422.2    2858   425.3    2890   431.7    3052   429.8
    3247   431.2    3274   419.7    3536   419.9    3629   422.3    3686   425.3
    3724   428.7    3778   427.7    3790   428.7    4037   428.8    4105   445.5
#Mann= 6 ,-1,0
    1006     .03       0    1040    .075       0    2386      .1       0
    2532     .05       0    2890     .06       0    4037     .03       0
#XS Ineff= 2 , 0
       0    1148     460               0
Permanent Ineff=
       F       F
Bank Sta=2532,2890
XS Rating Curve= 0 ,0
Exp/Cntr=0.3,0.1

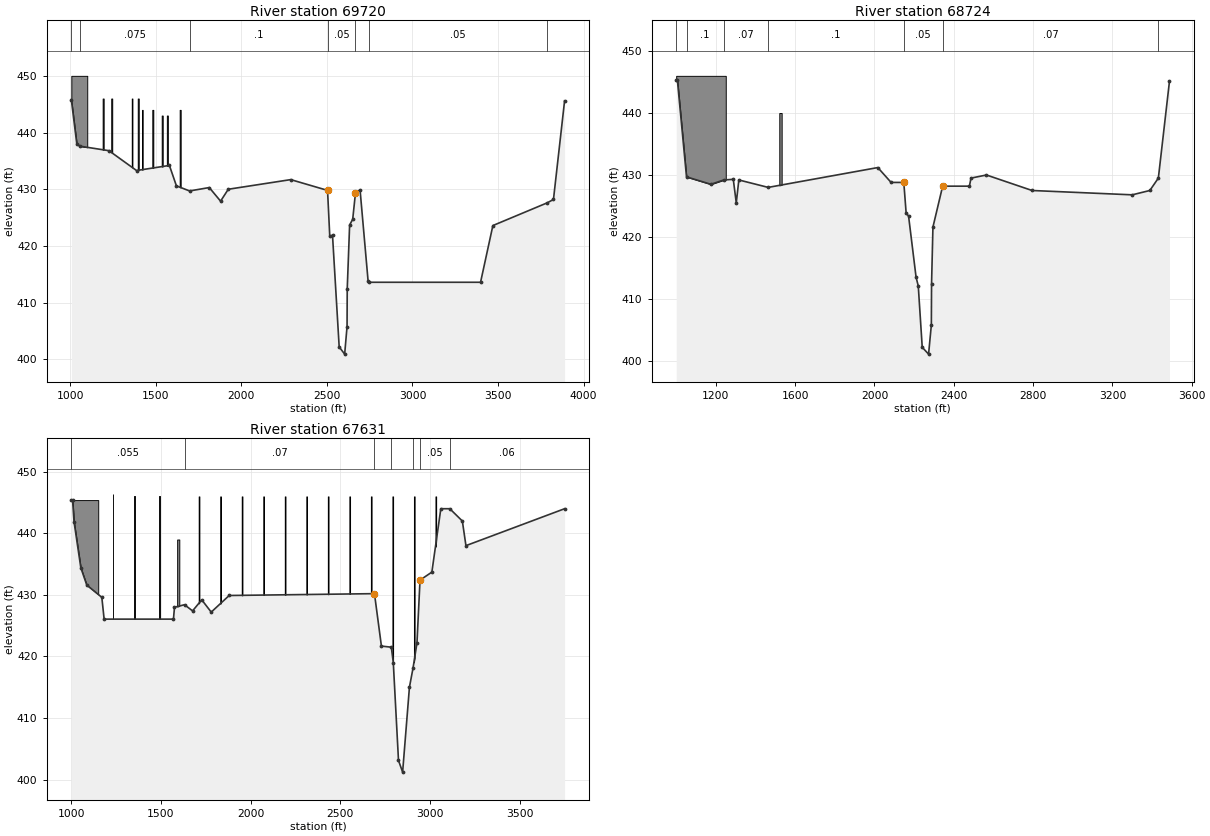
Type RM Length L Ch R = 1 ,69720   ,800,996,1100
BEGIN DESCRIPTION:
This cross section corresponds to cross section 69701 of the non-georeferenced CDC model which was the source of this model.
END DESCRIPTION:
XS GIS Cut Line= 2
2449151.346480347020941.635365712446277.318763857021155.84917614
#Sta/Elev= 30
    1007   445.8    1039     438    1056   437.6    1227   436.8    1388   433.3
    1580   434.2    1621   430.6    1698   429.7    1813   430.3    1879   427.9
    1924     430    2289   431.7    2504   429.8    2517   421.7    2533   421.9
    2572   402.2    2604  400.93    2618   405.8    2619   412.4    2633   423.7
    2651   424.7    2667   429.3    2694   429.9    2741   413.8    2749   413.6
    3398   413.6    3470   423.6    3787   427.6    3824   428.2    3889   445.6
#Mann= 7 ,-1,0
    1007     .03       0    1056    .075       0    1698      .1       0
    2504     .05       0    2667      .1       0    2749     .05       0
    3787     .03       0
#Block Obstruct= 10 ,-1
    1007    1100     450    1190    1196     446    1240    1246     446
    1395    1401     446    1360    1364     446    1420    1424     444
    1480    1486     444    1535    1541     443    1565    1571     443
    1640    1646     444
#XS Lid=4
    1160     449     445    1620     445     441    1620   447.5   443.5
    1665   447.5   443.5
Bank Sta=2504,2667
XS Rating Curve= 0 ,0
Exp/Cntr=0.3,0.1

Type RM Length L Ch R = 1 ,68724   ,581,1093,1087
BEGIN DESCRIPTION:
This cross section corresponds to cross section 68705 of the non-georeferenced CDC model which was the source of this model.
END DESCRIPTION:
XS GIS Cut Line= 2
2449013.525889847020285.36108771 2446550.06920267019936.75811039
#Sta/Elev= 30
    1000   445.3    1006   445.3    1052   429.7    1175   428.5    1240   429.2
    1288   429.3    1303   425.5    1316   429.2    1464     428    2017   431.2
    2084   428.8    2148   428.8    2160   423.8    2172   423.4    2210   413.5
    2221   412.1    2241   402.2    2273   401.1    2287   405.8    2288   412.4
    2295   421.6    2344   428.2    2479   428.2    2487   429.5    2565     430
    2795   427.5    3300   426.8    3389   427.5    3432   429.5    3488   445.1
#Mann= 7 ,-1,0
    1000     .03       0    1052      .1       0    1240     .07       0
    1464      .1       0    2148     .05       0    2344     .07       0
    3432     .03       0
#Block Obstruct= 2 ,-1
    1000    1250     446    1520    1532     440
#XS Lid=2
    1490  441.63  437.46    1570  446.11  441.94
Bank Sta=2148,2344
XS Rating Curve= 0 ,0
Exp/Cntr=0.3,0.1

Type RM Length L Ch R = 1 ,67631   ,166,137,161
BEGIN DESCRIPTION:
This cross section corresponds to cross section 67474 of the non-georeferenced CDC model which was the source of this model.
END DESCRIPTION:
XS GIS Cut Line= 3
2449072.05825308 7020238.17450232447929.897151597019298.86306071
  2446910.4126427018539.51418571
#Sta/Elev= 30
    1000   445.4    1007   445.4    1015   441.9    1053   434.4    1086   431.6
    1170   429.6 1182.88  426.06 1569.37  426.06 1575.14  427.99    1631   428.4
    1676   427.4    1727   429.2    1780   427.2    1880   429.9    2690   430.2
 2728.77  421.68    2784   421.5    2795     419    2824   403.1    2847   401.2
    2885     415    2905   418.1    2927   422.2    2944   432.4    3010   433.7
    3060     444    3110     444    3180     442    3200     438    3750     444
#Mann= 7 ,-1,0
    1000    .055       0    1631     .07       0    2690     .05       0
    2784     .05       0    2905     .07       0    2944     .05       0
    3110     .06       0
#Block Obstruct= 17 ,-1
    1000    1150   445.4    1230    1234  446.42    1350    1354     446
    1490    1494     446    1590    1602     439    1710    1714     446
    1830    1834     446    1950    1954     446    2070    2074     446
    2190    2194     446    2310    2314     446    2430    2434     446
    2550    2554     446    2670    2674     446    2790    2794     446
    2910    2914     446    3030    3034     446
#XS Lid=2
    1554  440.97   436.8    1634  444.33  440.16
Bank Sta=2690,2944
XS Rating Curve= 0 ,0
Exp/Cntr=0.3,0.1