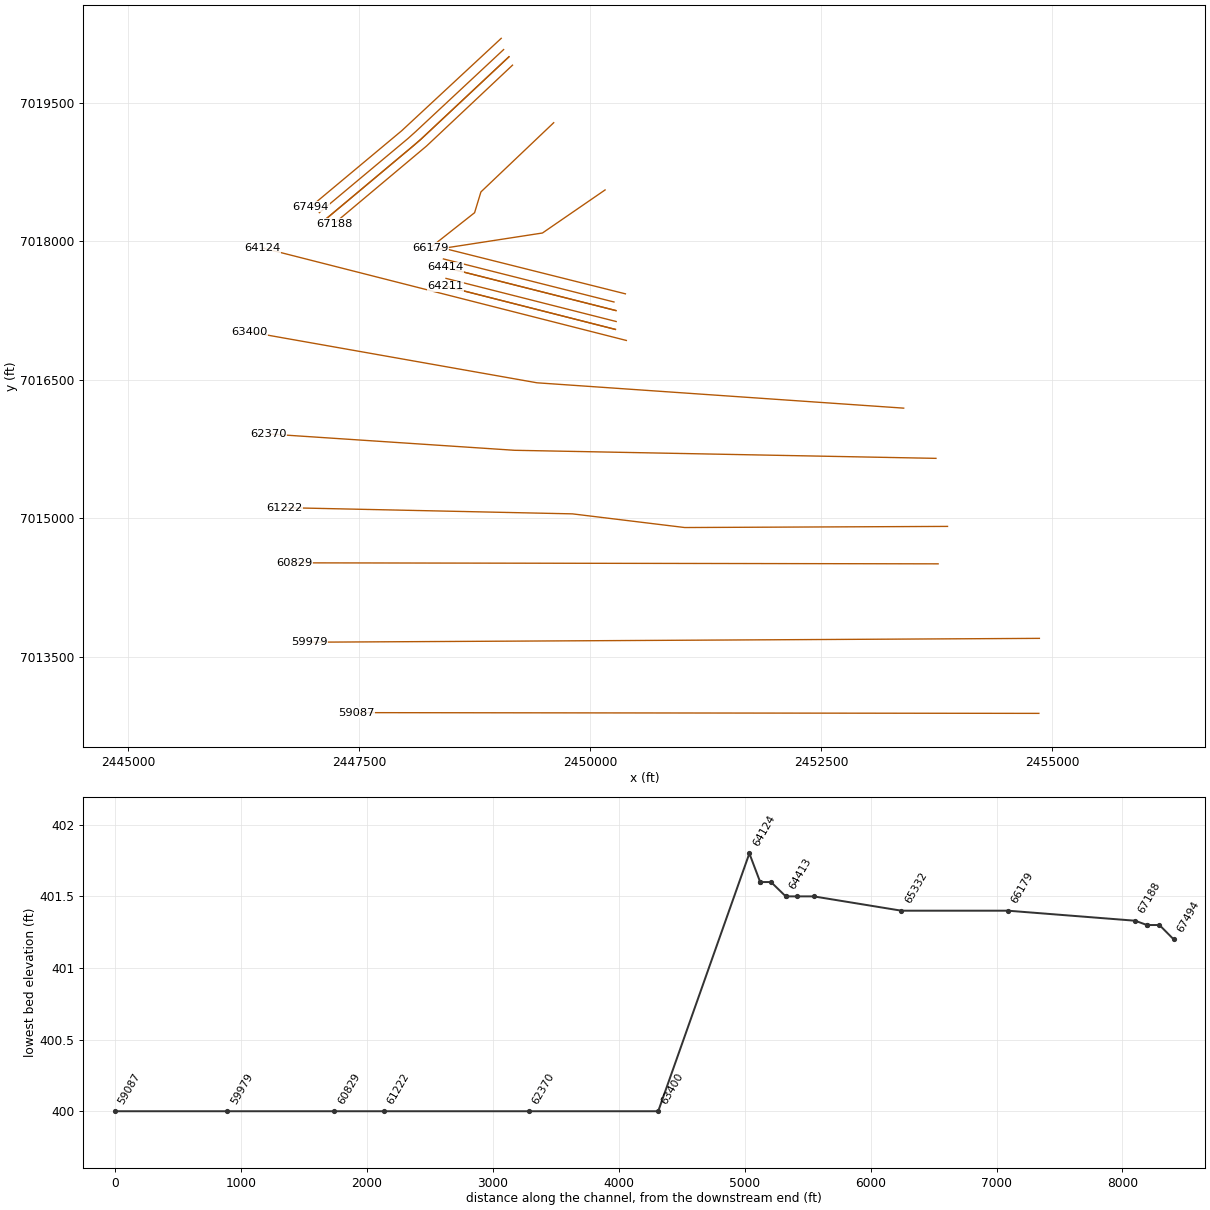
HEC-RAS study CDC_Consolidated_Model.prj: Upper Trinity CDC Consolidated Model

--- CDC_Consolidated_Model.g04 (geometry) --- (continued)

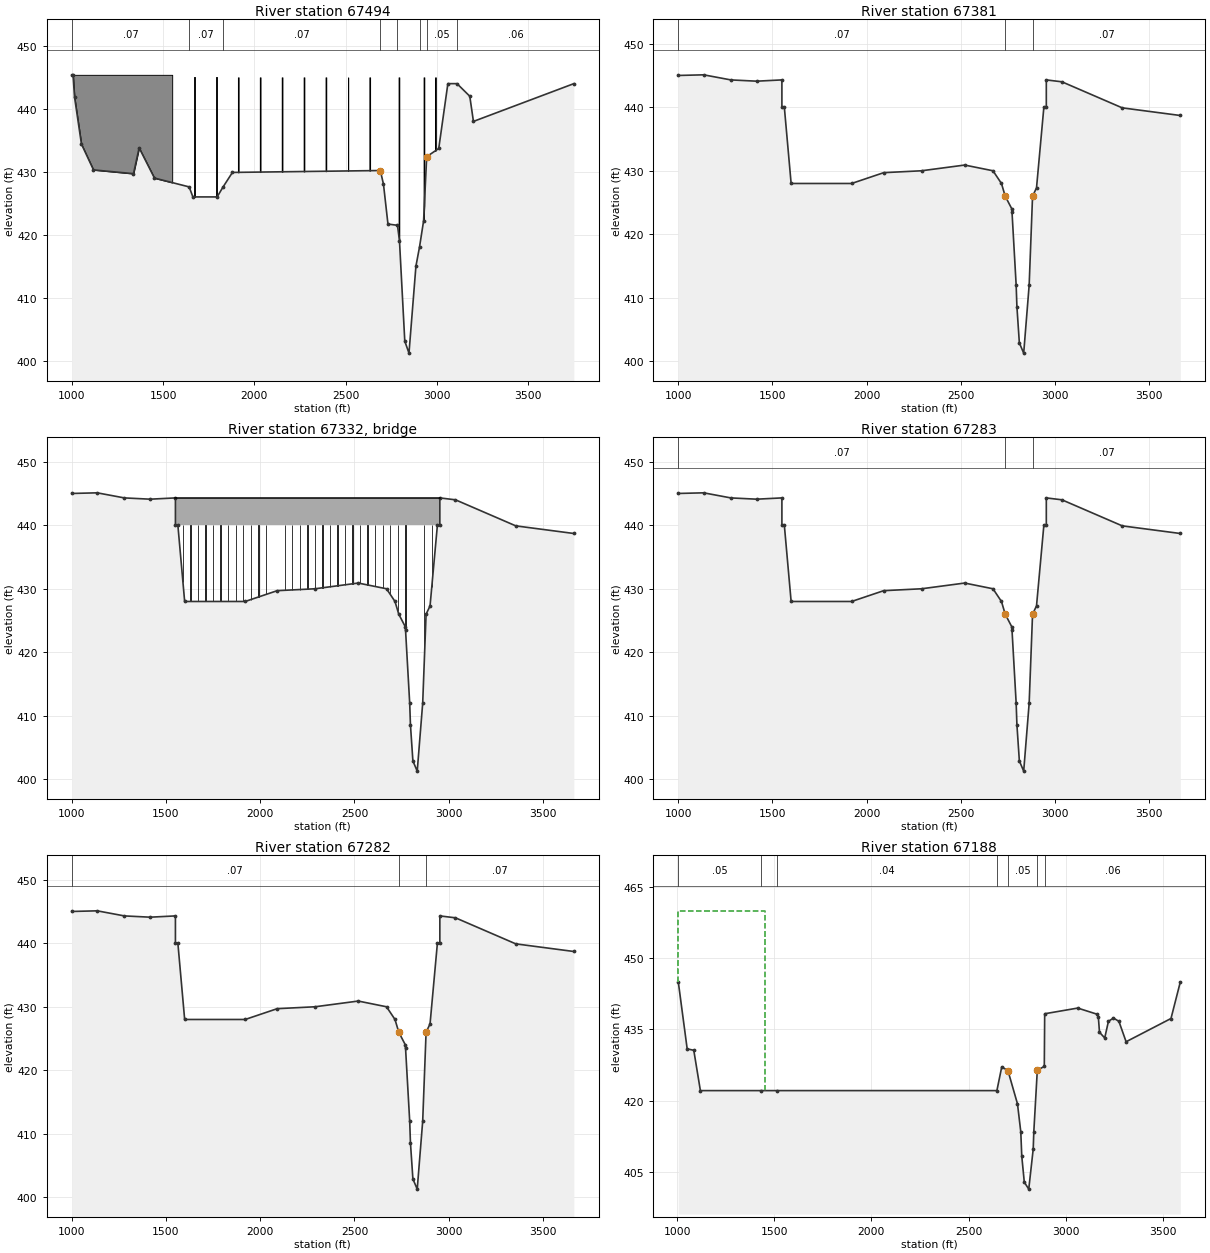
Type RM Length L Ch R = 1 ,67494   ,113,113,113
BEGIN DESCRIPTION:
This cross section corresponds to cross section 67474 of the non-georeferenced CDC model which was the source of this model.
----------------------------------------------
CDC CAR012102-1 President George Bush Turnpike
Cross-section 67474 - 110074
----------------------------------------------
END DESCRIPTION:
XS GIS Cut Line= 3
2449035.995989267020196.284166132447959.731081437019196.17199314
2446976.700567197018375.14804463
#Sta/Elev= 30
    1000   445.4    1007   445.4    1015   441.9    1053   434.4    1119   430.3
    1338   429.7    1369   433.8    1453     429    1643   427.6  1663.4  426.01
 1796.24  426.01 1827.56  427.54    1880   429.9    2690   430.2 2707.26  428.04
 2731.85   421.7    2784   421.5    2795     419    2824   403.1    2847   401.2
    2885     415    2905   418.1    2927   422.2    2944   432.4    3010   433.7
    3060     444    3110     444    3180     442    3200     438    3750     444
#Mann= 8 ,-1,0
    1000     .07       0    1643     .07       0 1827.56     .07       0
    2690     .05       0    2784     .05       0    2905     .07       0
    2944     .05       0    3110     .06       0
#Block Obstruct= 13 ,-1
    1000    1550   445.4    1670    1674     445    1790    1794     445
    1910    1914     445    2030    2034     445    2150    2154     445
    2270    2274     445    2390    2394     445 2513.51    2514     445
    2630    2634     445    2790    2794     445    2927    2931     445
    2990    2994     445
Bank Sta=2690,2944
XS Rating Curve= 0 ,0
Exp/Cntr=0.3,0.1

Type RM Length L Ch R = 1 ,67381   ,98,98,98
BEGIN DESCRIPTION:
This cross section corresponds to cross section 67364 of the non-georeferenced CDC model which was the source of this model.
END DESCRIPTION:
XS GIS Cut Line= 4
2449061.80860168 7020074.49766432448108.346597857019184.48664905
2448027.991443577019112.388696132447067.966788837018309.14620814
#Sta/Elev= 30
    1000     445    1135   445.1    1279   444.3    1416   444.1    1550   444.3
    1550     440    1563     440    1599     428    1920     428    2090   429.7
    2291     430    2520   430.9    2670     430    2715     428    2735     426
    2769  424.06    2771   423.5    2793     412    2797   408.6    2810   402.9
    2833   401.3    2862     412    2880     426    2901   427.3    2940     440
    2953     440    2953   444.3    3036     444    3356   439.9    3664   438.7
#Mann= 3 ,0,0
    1000     .07       0    2735     .05       0    2880     .07       0
Bank Sta=2735,2880
XS Rating Curve= 0 ,0
Exp/Cntr=0.5,0.3

Type RM Length L Ch R = 3 ,67332   ,,,
BEGIN DESCRIPTION:
Valley View Lane
END DESCRIPTION:
Node Name=Valley View Lane
Bridge Culvert--1,0,-1,-1, 0
Deck Dist Width WeirC Skew NumUp NumDn MinLoCord MaxHiCord MaxSubmerge Is_Ogee
2,95,2.6,0, 49, 49, , , 0.95, 0, ,,,
    1550    1589    1591    1628    1632    1709    1711    1748    1752    1829
    1831    1868    1872    1949    1951    1989    1991    2029    2031    2129
    2131    2169    2171    2171    2208    2212    2289    2291    2328    2332
    2409    2411    2448    2452    2529    2531    2568    2572    2649    2651
    2688    2692    2769    2771    2869    2871    2909    2911    2953
   444.3   444.3   444.3   444.3   444.3   444.3   444.3   444.3   444.3   444.3
   444.3   444.3   444.3   444.3   444.3   444.3   444.3   444.3   444.3   444.3
   444.3   444.3   444.3   444.3   444.3   444.3   444.3   444.3   444.3   444.3
   444.3   444.3   444.3   444.3   444.3   444.3   444.3   444.3   444.3   444.3
   444.3   444.3   444.3   444.3   444.3   444.3   444.3   444.3   444.3
     440     440     440     440     440     440     440     440     440     440
     440     440     440     440     440     440     440     440     440     440
     440     440     440     440     440     440     440     440     440     440
     440     440     440     440     440     440     440     440     440     440
     440     440     440     440     440     440     440     440     440
    1550    1589    1591    1628    1632    1709    1711    1748    1752    1829
    1831    1868    1872    1949    1951    1989    1991    2029    2031    2129
    2131    2169    2171    2171    2208    2212    2289    2291    2328    2332
    2409    2411    2448    2452    2529    2531    2568    2572    2649    2651
    2688    2692    2769    2771    2869    2871    2909    2911    2953
   444.3   444.3   444.3   444.3   444.3   444.3   444.3   444.3   444.3   444.3
   444.3   444.3   444.3   444.3   444.3   444.3   444.3   444.3   444.3   444.3
   444.3   444.3   444.3   444.3   444.3   444.3   444.3   444.3   444.3   444.3
   444.3   444.3   444.3   444.3   444.3   444.3   444.3   444.3   444.3   444.3
   444.3   444.3   444.3   444.3   444.3   444.3   444.3   444.3   444.3
     440     440     440     440     440     440     440     440     440     440
     440     440     440     440     440     440     440     440     440     440
     440     440     440     440     440     440     440     440     440     440
     440     440     440     440     440     440     440     440     440     440
     440     440     440     440     440     440     440     440     440
Pier Skew, UpSta & Num, DnSta & Num=  ,1590, 2 ,1590, 2 , 0 , 0 , 0 ,,
       2       2
     410     442
       2       2
     410     442
Pier Skew, UpSta & Num, DnSta & Num=  ,1630, 2 ,1630, 2 , 0 , 0 , 0 ,,
       2       2
     410     442
       2       2
     410     442
Pier Skew, UpSta & Num, DnSta & Num=  ,1670, 2 ,1670, 2 , 0 , 0 , 0 ,,
       2       2
     410     442
       2       2
     410     442
Pier Skew, UpSta & Num, DnSta & Num=  ,1710, 2 ,1710, 2 , 0 , 0 , 0 ,,
       2       2
     410     442
       2       2
     410     442
Pier Skew, UpSta & Num, DnSta & Num=  ,1750, 2 ,1750, 2 , 0 , 0 , 0 ,,
       2       2
     410     442
       2       2
     410     442
Pier Skew, UpSta & Num, DnSta & Num=  ,1790, 2 ,1790, 2 , 0 , 0 , 0 ,,
       2       2
     410     442
       2       2
     410     442
Pier Skew, UpSta & Num, DnSta & Num=  ,1830, 2 ,1830, 2 , 0 , 0 , 0 ,,
       2       2
     410     442
       2       2
     410     442
Pier Skew, UpSta & Num, DnSta & Num=  ,1870, 2 ,1870, 2 , 0 , 0 , 0 ,,
       2       2
     410     442
       2       2
     410     442
Pier Skew, UpSta & Num, DnSta & Num=  ,1910, 2 ,1910, 2 , 0 , 0 , 0 ,,
       2       2
     410     442
       2       2
     410     442
Pier Skew, UpSta & Num, DnSta & Num=  ,1950, 2 ,1950, 2 , 0 , 0 , 0 ,,
       2       2
     410     442
       2       2
     410     442
Pier Skew, UpSta & Num, DnSta & Num=  ,1990, 2 ,1990, 2 , 0 , 0 , 0 ,,
       2       2
     410     442
       2       2
     410     442
Pier Skew, UpSta & Num, DnSta & Num=  ,2030, 2 ,2030, 2 , 0 , 0 , 0 ,,
       2       2
     410     442
       2       2
     410     442
Pier Skew, UpSta & Num, DnSta & Num=  ,2130, 2 ,2130, 2 , 0 , 0 , 0 ,,
       2       2
     410     442
       2       2
     410     442
Pier Skew, UpSta & Num, DnSta & Num=  ,2170, 2 ,2170, 2 , 0 , 0 , 0 ,,
       2       2
     410     442
       2       2
     410     442
Pier Skew, UpSta & Num, DnSta & Num=  ,2210, 2 ,2210, 2 , 0 , 0 , 0 ,,
       2       2
     410     442
       2       2
     410     442
Pier Skew, UpSta & Num, DnSta & Num=  ,2250, 2 ,2250, 2 , 0 , 0 , 0 ,,
       2       2
     410     442
       2       2
     410     442
Pier Skew, UpSta & Num, DnSta & Num=  ,2290, 2 ,2290, 2 , 0 , 0 , 0 ,,
       2       2
     410     442
       2       2
     410     442
Pier Skew, UpSta & Num, DnSta & Num=  ,2330, 2 ,2330, 2 , 0 , 0 , 0 ,,
       2       2
     410     442
       2       2
     410     442
Pier Skew, UpSta & Num, DnSta & Num=  ,2370, 2 ,2370, 2 , 0 , 0 , 0 ,,
       2       2
     410     442
       2       2
     410     442
Pier Skew, UpSta & Num, DnSta & Num=  ,2410, 2 ,2410, 2 , 0 , 0 , 0 ,,
       2       2
     410     442
       2       2
     410     442
Pier Skew, UpSta & Num, DnSta & Num=  ,2450, 2 ,2450, 2 , 0 , 0 , 0 ,,
       2       2
     410     442
       2       2
     410     442
Pier Skew, UpSta & Num, DnSta & Num=  ,2490, 2 ,2490, 2 , 0 , 0 , 0 ,,
       2       2
     410     442
       2       2
     410     442
Pier Skew, UpSta & Num, DnSta & Num=  ,2530, 2 ,2530, 2 , 0 , 0 , 0 ,,
       2       2
     410     442
       2       2
     410     442
Pier Skew, UpSta & Num, DnSta & Num=  ,2570, 2 ,2570, 2 , 0 , 0 , 0 ,,
       2       2
     410     442
       2       2
     410     442
Pier Skew, UpSta & Num, DnSta & Num=  ,2610, 2 ,2610, 2 , 0 , 0 , 0 ,,
       2       2
     410     442
       2       2
     410     442
Pier Skew, UpSta & Num, DnSta & Num=  ,2650, 2 ,2650, 2 , 0 , 0 , 0 ,,
       2       2
     410     442
       2       2
     410     442
Pier Skew, UpSta & Num, DnSta & Num=  ,2690, 2 ,2690, 2 , 0 , 0 , 0 ,,
       2       2
     410     442
       2       2
     410     442
Pier Skew, UpSta & Num, DnSta & Num=  ,2730, 2 ,2730, 2 , 0 , 0 , 0 ,,
       2       2
     410     442
       2       2
     410     442
Pier Skew, UpSta & Num, DnSta & Num=  ,2770, 2 ,2770, 2 , 0 , 0 , 0 ,,
       2       2
     410     442
       2       2
     410     442
Pier Skew, UpSta & Num, DnSta & Num=  ,2870, 2 ,2870, 2 , 0 , 0 , 0 ,,
       2       2
     410     442
       2       2
     410     442
Pier Skew, UpSta & Num, DnSta & Num=  ,2910, 2 ,2910, 2 , 0 , 0 , 0 ,,
       2       2
     410     442
       2       2
     410     442
BR Coef= 1 , 0 , 0 ,1.05, 0 ,,,0.8,-1,0.5,1,
WSPro=,,,, 1 ,,,, 0 ,,,, 0 ,,,,-1 ,-1 ,-1 , 0 , 0 , 0 , 0 , 0
BC Design=,, 0 ,, 0 ,,,,,,
BC HTab HWMax=445.1
BC Use User HTab Curves=0
BC User HTab FreeFlow(D)= 0

Type RM Length L Ch R = 1 ,67283   ,1,1,1
BEGIN DESCRIPTION:
This cross section corresponds to cross section 67265 of the non-georeferenced CDC model which was the source of this model.
END DESCRIPTION:
XS GIS Cut Line= 4
2449119.763210187019997.30195256  2448169.327447 7019106.3460573
2448089.431937527019036.988584472447127.216998437018230.56336005
#Sta/Elev= 30
    1000     445    1135   445.1    1279   444.3    1416   444.1    1550   444.3
    1550     440    1563     440    1599     428    1920     428    2090   429.7
    2291     430    2520   430.9    2670     430    2715     428    2735     426
    2769  424.06    2771   423.5    2793     412    2797   408.6    2810   402.9
    2833   401.3    2862     412    2880     426    2901   427.3    2940     440
    2953     440    2953   444.3    3036     444    3356   439.9    3664   438.7
#Mann= 3 ,0,0
    1000     .07       0    2735     .05       0    2880     .07       0
Bank Sta=2735,2880
XS Rating Curve= 0 ,0
Exp/Cntr=0.5,0.3

Type RM Length L Ch R = 1 ,67282   ,94,94,94
BEGIN DESCRIPTION:
This cross section corresponds to cross section 67264 of the non-georeferenced CDC model which was the source of this model.
END DESCRIPTION:
XS GIS Cut Line= 4
2449120.164128017019996.349854722448169.94555601 7019105.5586573
2448090.052671167019036.227103052447127.622509427018229.60732521
#Sta/Elev= 30
    1000     445    1135   445.1    1279   444.3    1416   444.1    1550   444.3
    1550     440    1563     440    1599     428    1920     428    2090   429.7
    2291     430    2520   430.9    2670     430    2715     428    2735     426
    2769  424.06    2771   423.5    2793     412    2797   408.6    2810   402.9
    2833   401.3    2862     412    2880     426    2901   427.3    2940     440
    2953     440    2953   444.3    3036     444    3356   439.9    3664   438.7
#Mann= 3 ,0,0
    1000     .07       0    2735     .05       0    2880     .07       0
Bank Sta=2735,2880
XS Rating Curve= 0 ,0
Exp/Cntr=0.3,0.1

Type RM Length L Ch R = 1 ,67188   ,769,1009,899
BEGIN DESCRIPTION:
This cross section corresponds to cross section 67169 of the non-georeferenced CDC model which was the source of this model.
LOMR#14-06-2597P & CDC# FB100113-1 Mercer Crossing
Cross-sections 67169 & 62351.  Fill was added in innefective flow area so no physical cross-section change.
END DESCRIPTION:
XS GIS Cut Line= 3
2449158.240167357019905.903185222448228.452000687019030.56504089
2447227.433005337018190.19861138
#Sta/Elev= 30
    1006   445.1    1052   430.9    1086   430.6    1120   422.1    1433   422.1
    1516   422.1    2646   422.1    2671   427.1    2703   426.3    2752   419.3
    2769   413.4    2774   408.3    2787   402.8    2810  401.33    2833   409.8
    2836   413.4    2854   426.4    2890   427.2    2892   438.3    3062   439.5
    3162   438.2    3168   437.7    3174   434.4    3201   433.2    3220   436.7
    3246   437.4    3274   436.7    3311   432.4    3542   437.3    3590     445
#Mann= 7 ,-1,0
    1006     .05       0    1433     .03       0    1516     .04       0
    2646     .08       0    2703     .05       0    2854     .08       0
    2892     .06       0
#XS Ineff= 2 , 0
       0    1450     460               0
Permanent Ineff=
       F       F
Bank Sta=2703,2854
XS Rating Curve= 0 ,0
Exp/Cntr=0.3,0.1

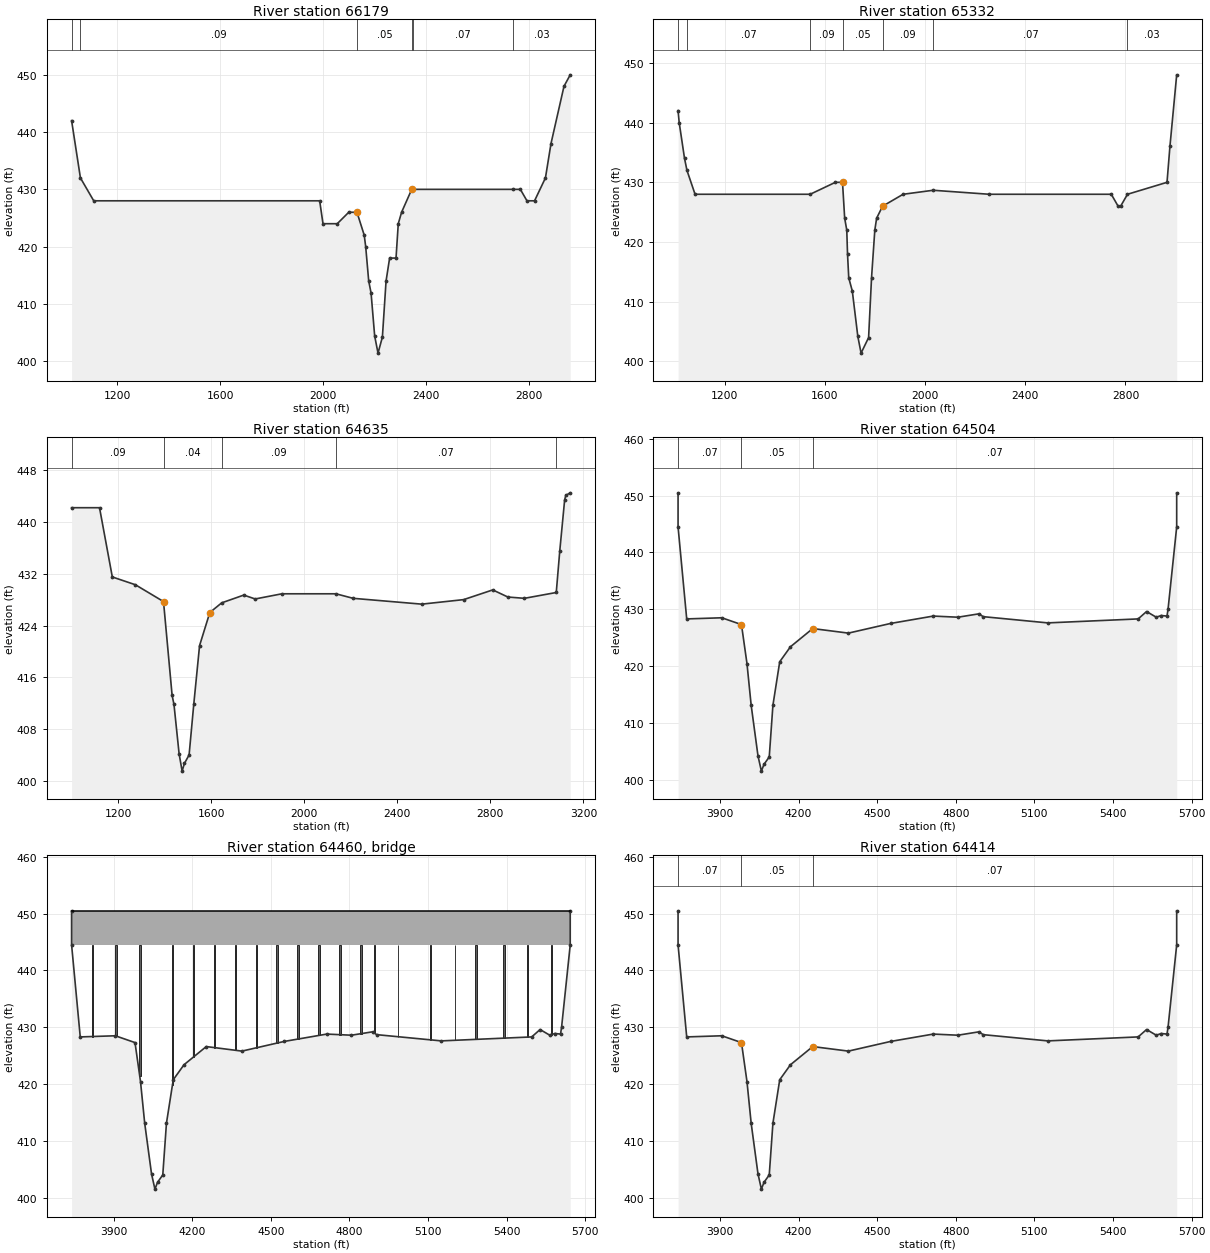
Type RM Length L Ch R = 1 ,66179   ,851,847,400
BEGIN DESCRIPTION:
This cross section corresponds to cross section 66159 of the non-georeferenced CDC model which was the source of this model.
END DESCRIPTION:
XS GIS Cut Line= 4
2449603.804564927019282.871622892448816.365851077018533.54306905
2448747.909951277018308.544175222448264.921087837017927.13942622
#Sta/Elev= 30
  1022.3     442  1056.6     432  1108.3     428  1986.3     428  1999.2     424
  2054.6     424  2099.3     426  2131.2     426  2159.4     422  2165.1     420
  2176.8     414    2186   411.9    2200   404.4    2213   401.4    2230   404.2
  2244.3     414  2258.1     418    2283     418  2291.7     424  2304.6     426
    2344     430  2349.3     430  2736.8     430  2766.1     430  2791.8     428
  2821.3     428  2863.6     432  2885.2     438  2935.7     448  2959.9     450
#Mann= 6 ,-1,0
  1022.3     .03       0  1056.6     .09       0  2131.2     .05       0
    2344     .09       0  2349.3     .07       0  2736.8     .03       0
Bank Sta=2131.2,2344
XS Rating Curve= 0 ,0
Exp/Cntr=0.3,0.1

Type RM Length L Ch R = 1 ,65332   ,951,697,351
BEGIN DESCRIPTION:
This cross section corresponds to cross section 65313 of the non-georeferenced CDC model which was the source of this model.
END DESCRIPTION:
XS GIS Cut Line= 3
2450159.545579437018554.918682472449482.115831917018088.76508722
2448328.394386087017910.71393414
#Sta/Elev= 30
  1014.7     442  1019.2     440  1040.5     434  1050.2     432  1082.5     428
  1541.9     428  1642.4     430  1670.9     430  1679.5     424  1687.9     422
  1690.9     418  1695.8     414    1710   411.8    1732   404.2    1745   401.4
    1775     404  1786.8  414.06  1799.8     422  1807.1     424  1830.8     426
  1912.7     428  2032.7  428.67  2256.5     428  2743.4     428  2770.7     426
  2780.6     426  2808.1     428  2965.8     430  2977.4     436  3004.4     448
#Mann= 7 ,-1,0
  1014.7     .03       0  1050.2     .07       0  1541.9     .09       0
  1670.9     .05       0  1830.8     .09       0  2032.7     .07       0
  2808.1     .03       0
Bank Sta=1670.9,1830.8
XS Rating Curve= 0 ,0
Exp/Cntr=0.3,0.1

Type RM Length L Ch R = 1 ,64635   ,131,131,131
BEGIN DESCRIPTION:
This cross section corresponds to cross section 64617 of the non-georeferenced CDC model which was the source of this model.
END DESCRIPTION:
XS GIS Cut Line= 3
2450379.504128997017430.195210132448417.995912917017922.35433079
2448298.746479517017903.75791129
#Sta/Elev= 30
    1000   442.2    1120   442.2    1175   431.5    1274   430.3    1395   427.7
    1432   413.2    1440   411.8    1462   404.2    1475   401.5    1485   402.7
    1505     404    1525   411.8    1550   420.9    1594     426    1645   427.5
    1740   428.7    1789   428.1    1904   428.9    2136   428.9    2210   428.2
    2505   427.3    2685     428    2810   429.5    2875   428.4    2946   428.2
    3083   429.1    3098   435.5    3119   443.4    3124   444.1    3143   444.5
#Mann= 5 ,-1,0
    1000     .09       0    1395     .04       0    1645     .09       0
    2136     .07       0    3083     .03       0
Bank Sta=1395,1594
XS Rating Curve= 0 ,0
Exp/Cntr=0.3,0.1

Type RM Length L Ch R = 1 ,64504   ,90,90,90
BEGIN DESCRIPTION:
This cross section corresponds to cross section 64495 of the non-georeferenced CDC model which was the source of this model.
END DESCRIPTION:
XS GIS Cut Line= 2
2450255.885609847017341.984428552448410.824667427017807.98710546
#Sta/Elev= 30
    3740   450.5    3740   444.5    3773   428.3    3907   428.5    3982   427.3
    4003  420.44    4019   413.1    4045   404.2    4058   401.5    4068   402.7
    4088     404    4102   413.1    4128  420.76    4169   423.4    4254   426.6
    4390   425.8    4551   427.5    4714   428.8    4808   428.6    4889   429.2
    4904   428.7    5151   427.6    5496   428.3    5528   429.6    5565   428.6
    5584   428.9    5606   428.8    5610     430    5643   444.5    5643   450.5
#Mann= 3 ,0,0
    3740     .07       0    3982     .05       0    4254     .07       0
Bank Sta=3982,4254
XS Rating Curve= 0 ,0
Exp/Cntr=0.5,0.3

Type RM Length L Ch R = 3 ,64460   ,,,
BEGIN DESCRIPTION:
IH 635/LBJ Freeway West Bound
END DESCRIPTION:
Node Name=IH 635
Bridge Culvert--1,0,-1,-1, 0
Deck Dist Width WeirC Skew NumUp NumDn MinLoCord MaxHiCord MaxSubmerge Is_Ogee
2,85,2.6,0, 44, 44, , , 0.95, 0, ,,,
    3740    3817    3823    3907    3913    3997    4003    4122    4128    4202
    4208    4282    4288    4362    4368    4442    4448    4522    4528    4602
    4608    4682    4688    4762    4768    4842    4848  4893.5  4896.5  4984.5
  4987.5  5109.5  5112.5  5201.5  5204.5    5283    5289    5387    5393    5477
    5483    5567    5573    5643
   450.5   450.5   450.5   450.5   450.5   450.5   450.5   450.5   450.5   450.5
   450.5   450.5   450.5   450.5   450.5   450.5   450.5   450.5   450.5   450.5
   450.5   450.5   450.5   450.5   450.5   450.5   450.5   450.5   450.5   450.5
   450.5   450.5   450.5   450.5   450.5   450.5   450.5   450.5   450.5   450.5
   450.5   450.5   450.5   450.5
   444.5   444.5   444.5   444.5   444.5   444.5   444.5   444.5   444.5   444.5
   444.5   444.5   444.5   444.5   444.5   444.5   444.5   444.5   444.5   444.5
   444.5   444.5   444.5   444.5   444.5   444.5   444.5   444.5   444.5   444.5
   444.5   444.5   444.5   444.5   444.5   444.5   444.5   444.5   444.5   444.5
   444.5   444.5   444.5   444.5
    3740    3817    3823    3907    3913    3997    4003    4122    4128    4202
    4208    4282    4288    4362    4368    4442    4448    4522    4528    4602
    4608    4682    4688    4762    4768    4842    4848  4893.5  4896.5  4984.5
  4987.5  5109.5  5112.5  5201.5  5204.5    5283    5289    5387    5393    5477
    5483    5567    5573    5643
   450.5   450.5   450.5   450.5   450.5   450.5   450.5   450.5   450.5   450.5
   450.5   450.5   450.5   450.5   450.5   450.5   450.5   450.5   450.5   450.5
   450.5   450.5   450.5   450.5   450.5   450.5   450.5   450.5   450.5   450.5
   450.5   450.5   450.5   450.5   450.5   450.5   450.5   450.5   450.5   450.5
   450.5   450.5   450.5   450.5
   444.5   444.5   444.5   444.5   444.5   444.5   444.5   444.5   444.5   444.5
   444.5   444.5   444.5   444.5   444.5   444.5   444.5   444.5   444.5   444.5
   444.5   444.5   444.5   444.5   444.5   444.5   444.5   444.5   444.5   444.5
   444.5   444.5   444.5   444.5   444.5   444.5   444.5   444.5   444.5   444.5
   444.5   444.5   444.5   444.5
Pier Skew, UpSta & Num, DnSta & Num=  ,3820, 2 ,3820, 2 , 0 , 0 , 0 ,,
       6       6
     415     450
       6       6
     415     450
Pier Skew, UpSta & Num, DnSta & Num=  ,3910, 2 ,3910, 2 , 0 , 0 , 0 ,,
       6       6
     415     450
       6       6
     415     450
Pier Skew, UpSta & Num, DnSta & Num=  ,4000, 2 ,4000, 2 , 0 , 0 , 0 ,,
       6       6
     415     450
       6       6
     415     450
Pier Skew, UpSta & Num, DnSta & Num=  ,4125, 2 ,4125, 2 , 0 , 0 , 0 ,,
       6       6
     415     450
       6       6
     415     450
Pier Skew, UpSta & Num, DnSta & Num=  ,4205, 2 ,4205, 2 , 0 , 0 , 0 ,,
       6       6
     415     450
       6       6
     415     450
Pier Skew, UpSta & Num, DnSta & Num=  ,4285, 2 ,4285, 2 , 0 , 0 , 0 ,,
       6       6
     415     450
       6       6
     415     450
Pier Skew, UpSta & Num, DnSta & Num=  ,4365, 2 ,4365, 2 , 0 , 0 , 0 ,,
       6       6
     415     450
       6       6
     415     450
Pier Skew, UpSta & Num, DnSta & Num=  ,4445, 2 ,4445, 2 , 0 , 0 , 0 ,,
       6       6
     415     450
       6       6
     415     450
Pier Skew, UpSta & Num, DnSta & Num=  ,4525, 2 ,4525, 2 , 0 , 0 , 0 ,,
       6       6
     415     450
       6       6
     415     450
Pier Skew, UpSta & Num, DnSta & Num=  ,4605, 2 ,4605, 2 , 0 , 0 , 0 ,,
       6       6
     415     450
       6       6
     415     450
Pier Skew, UpSta & Num, DnSta & Num=  ,4685, 2 ,4685, 2 , 0 , 0 , 0 ,,
       6       6
     415     450
       6       6
     415     450
Pier Skew, UpSta & Num, DnSta & Num=  ,4765, 2 ,4765, 2 , 0 , 0 , 0 ,,
       6       6
     415     450
       6       6
     415     450
Pier Skew, UpSta & Num, DnSta & Num=  ,4845, 2 ,4845, 2 , 0 , 0 , 0 ,,
       6       6
     415     450
       6       6
     415     450
Pier Skew, UpSta & Num, DnSta & Num=  ,4895, 2 ,4895, 2 , 0 , 0 , 0 ,,
       3       3
     415     450
       3       3
     415     450
Pier Skew, UpSta & Num, DnSta & Num=  ,4986, 2 ,4986, 2 , 0 , 0 , 0 ,,
       3       3
     415     450
       3       3
     415     450
Pier Skew, UpSta & Num, DnSta & Num=  ,5111, 2 ,5111, 2 , 0 , 0 , 0 ,,
       3       3
     415     450
       3       3
     415     450
Pier Skew, UpSta & Num, DnSta & Num=  ,5203, 2 ,5203, 2 , 0 , 0 , 0 ,,
       3       3
     415     450
       3       3
     415     450
Pier Skew, UpSta & Num, DnSta & Num=  ,5283, 2 ,5283, 2 , 0 , 0 , 0 ,,
       6       6
     415     450
       6       6
     415     450
Pier Skew, UpSta & Num, DnSta & Num=  ,5390, 2 ,5390, 2 , 0 , 0 , 0 ,,
       6       6
     415     450
       6       6
     415     450
Pier Skew, UpSta & Num, DnSta & Num=  ,5480, 2 ,5480, 2 , 0 , 0 , 0 ,,
       6       6
     415     450
       6       6
     415     450
Pier Skew, UpSta & Num, DnSta & Num=  ,5571, 2 ,5571, 2 , 0 , 0 , 0 ,,
       6       6
     415     450
       6       6
     415     450
BR Coef= 1 , 0 , 0 ,1.05, 0 ,,,0.8,-1,0.5,1,
WSPro=,,,, 1 ,,,, 0 ,,,, 0 ,,,,-1 ,-1 ,-1 , 0 , 0 , 0 , 0 , 0
BC Design=,, 0 ,, 0 ,,,,,,
BC HTab HWMax=450.5
BC Use User HTab Curves=0
BC User HTab FreeFlow(D)= 0

Type RM Length L Ch R = 1 ,64414   ,1,1,1
BEGIN DESCRIPTION:
This cross section corresponds to cross section 64406 of the non-georeferenced CDC model which was the source of this model.
END DESCRIPTION:
XS GIS Cut Line= 2
2450277.056499247017249.557776142448432.189782177017716.32948038
#Sta/Elev= 30
    3740   450.5    3740   444.5    3773   428.3    3907   428.5    3982   427.3
    4003  420.44    4019   413.1    4045   404.2    4058   401.5    4068   402.7
    4088     404    4102   413.1    4128  420.76    4169   423.4    4254   426.6
    4390   425.8    4551   427.5    4714   428.8    4808   428.6    4889   429.2
    4904   428.7    5151   427.6    5496   428.3    5528   429.6    5565   428.6
    5584   428.9    5606   428.8    5610     430    5643   444.5    5643   450.5
#Mann= 3 ,0,0
    3740     .07       0    3982     .05       0    4254     .07       0
Bank Sta=3982,4254
XS Rating Curve= 0 ,0
Exp/Cntr=0.5,0.3

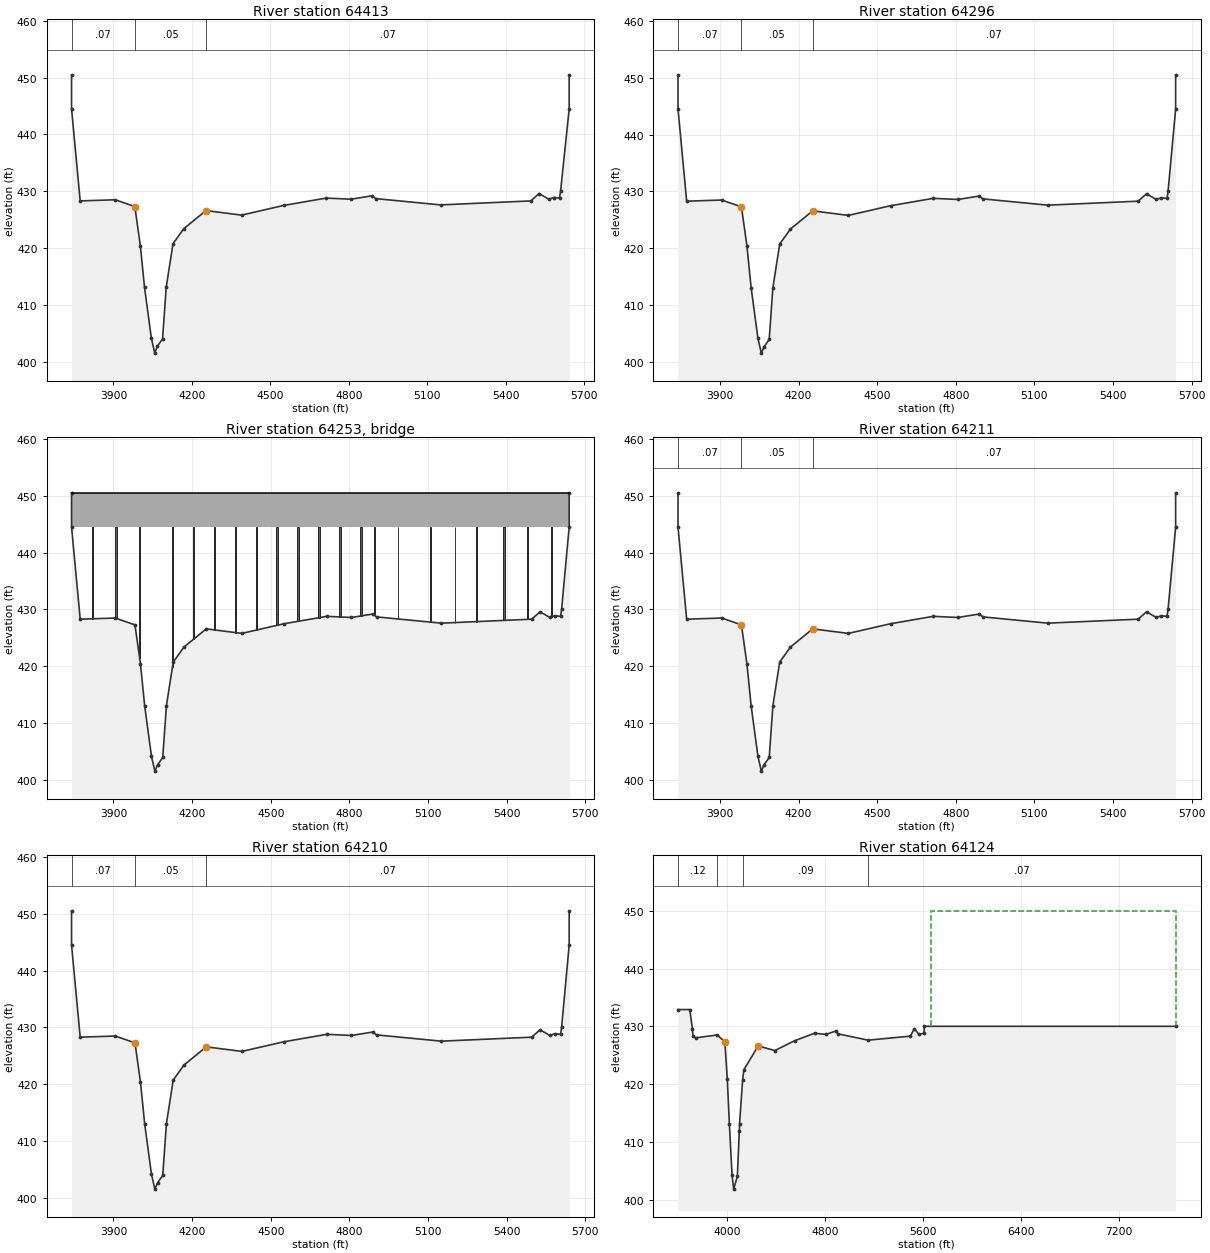
Type RM Length L Ch R = 1 ,64413   ,117,117,117
BEGIN DESCRIPTION:
This cross section corresponds to cross section 64405 of the non-georeferenced CDC model which was the source of this model.
END DESCRIPTION:
XS GIS Cut Line= 2
2450277.07618424 7017248.57418232448432.211763777017715.35441671
#Sta/Elev= 30
    3740   450.5    3740   444.5    3773   428.3    3907   428.5    3982   427.3
    4003  420.44    4019   413.1    4045   404.2    4058   401.5    4068   402.7
    4088     404    4102   413.1    4128  420.76    4169   423.4    4254   426.6
    4390   425.8    4551   427.5    4714   428.8    4808   428.6    4889   429.2
    4904   428.7    5151   427.6    5496   428.3    5528   429.6    5565   428.6
    5584   428.9    5606   428.8    5610     430    5643   444.5    5643   450.5
#Mann= 3 ,0,0
    3740     .07       0    3982     .05       0    4254     .07       0
Bank Sta=3982,4254
XS Rating Curve= 0 ,0
Exp/Cntr=0.5,0.3

Type RM Length L Ch R = 1 ,64296   ,85,85,85
BEGIN DESCRIPTION:
This cross section corresponds to cross section 64285 of the non-georeferenced CDC model which was the source of this model.
END DESCRIPTION:
XS GIS Cut Line= 2
2450279.475457677017130.556373722448438.749152247017597.38286789
#Sta/Elev= 30
    3740   450.5    3740   444.5    3773   428.3    3907   428.5    3982   427.3
    4003  420.44    4019   413.1    4045   404.2    4058   401.6    4068   402.7
    4088     404    4102   413.1    4128  420.76    4169   423.4    4254   426.6
    4390   425.8    4551   427.5    4714   428.8    4808   428.6    4889   429.2
    4904   428.7    5151   427.6    5496   428.3    5528   429.6    5565   428.6
    5584   428.9    5606   428.8    5610     430    5639   444.5    5639   450.5
#Mann= 3 ,0,0
    3740     .07       0    3982     .05       0    4254     .07       0
Bank Sta=3982,4254
XS Rating Curve= 0 ,0
Exp/Cntr=0.5,0.3

Type RM Length L Ch R = 3 ,64253   ,,,
BEGIN DESCRIPTION:
IH 635/L BJ Freeway East Bound
END DESCRIPTION:
Node Name=IH 635
Bridge Culvert--1,0,-1,-1, 0
Deck Dist Width WeirC Skew NumUp NumDn MinLoCord MaxHiCord MaxSubmerge Is_Ogee
2,82,2.6,0, 45, 45, , , 0.95, 0, ,,,
    3740    3817    3823    3907    3913    3997    4003    4122    4128    4202
    4208    4282    4288    4362    4368    4368    4442    4448    4522    4528
    4602    4608    4682    4688    4762    4768    4842    4848  4893.5  4896.5
  4984.5  4987.5  5109.5  5112.5  5201.5  5204.5    5283    5289    5387    5393
    5477    5483    5568    5574    5639
   450.5   450.5   450.5   450.5   450.5   450.5   450.5   450.5   450.5   450.5
   450.5   450.5   450.5   450.5   450.5   450.5   450.5   450.5   450.5   450.5
   450.5   450.5   450.5   450.5   450.5   450.5   450.5   450.5   450.5   450.5
   450.5   450.5   450.5   450.5   450.5   450.5   450.5   450.5   450.5   450.5
   450.5   450.5   450.5   450.5   450.5
   444.5   444.5   444.5   444.5   444.5   444.5   444.5   444.5   444.5   444.5
   444.5   444.5   444.5   444.5   444.5   444.5   444.5   444.5   444.5   444.5
   444.5   444.5   444.5   444.5   444.5   444.5   444.5   444.5   444.5   444.5
   444.5   444.5   444.5   444.5   444.5   444.5   444.5   444.5   444.5   444.5
   444.5   444.5   444.5   444.5   444.5
    3740    3817    3823    3907    3913    3997    4003    4122    4128    4202
    4208    4282    4288    4362    4368    4368    4442    4448    4522    4528
    4602    4608    4682    4688    4762    4768    4842    4848  4893.5  4896.5
  4984.5  4987.5  5109.5  5112.5  5201.5  5204.5    5283    5289    5387    5393
    5477    5483    5568    5574    5639
   450.5   450.5   450.5   450.5   450.5   450.5   450.5   450.5   450.5   450.5
   450.5   450.5   450.5   450.5   450.5   450.5   450.5   450.5   450.5   450.5
   450.5   450.5   450.5   450.5   450.5   450.5   450.5   450.5   450.5   450.5
   450.5   450.5   450.5   450.5   450.5   450.5   450.5   450.5   450.5   450.5
   450.5   450.5   450.5   450.5   450.5
   444.5   444.5   444.5   444.5   444.5   444.5   444.5   444.5   444.5   444.5
   444.5   444.5   444.5   444.5   444.5   444.5   444.5   444.5   444.5   444.5
   444.5   444.5   444.5   444.5   444.5   444.5   444.5   444.5   444.5   444.5
   444.5   444.5   444.5   444.5   444.5   444.5   444.5   444.5   444.5   444.5
   444.5   444.5   444.5   444.5   444.5
Pier Skew, UpSta & Num, DnSta & Num=  ,3820, 2 ,3820, 2 , 0 , 0 , 0 ,,
       6       6
     415     450
       6       6
     415     450
Pier Skew, UpSta & Num, DnSta & Num=  ,3910, 2 ,3910, 2 , 0 , 0 , 0 ,,
       6       6
     415     450
       6       6
     415     450
Pier Skew, UpSta & Num, DnSta & Num=  ,4000, 2 ,4000, 2 , 0 , 0 , 0 ,,
       6       6
     415     450
       6       6
     415     450
Pier Skew, UpSta & Num, DnSta & Num=  ,4125, 2 ,4125, 2 , 0 , 0 , 0 ,,
       6       6
     415     450
       6       6
     415     450
Pier Skew, UpSta & Num, DnSta & Num=  ,4205, 2 ,4205, 2 , 0 , 0 , 0 ,,
       6       6
     415     450
       6       6
     415     450
Pier Skew, UpSta & Num, DnSta & Num=  ,4285, 2 ,4285, 2 , 0 , 0 , 0 ,,
       6       6
     415     450
       6       6
     415     450
Pier Skew, UpSta & Num, DnSta & Num=  ,4365, 2 ,4365, 2 , 0 , 0 , 0 ,,
       6       6
     415     450
       6       6
     415     450
Pier Skew, UpSta & Num, DnSta & Num=  ,4445, 2 ,4445, 2 , 0 , 0 , 0 ,,
       6       6
     415     450
       6       6
     415     450
Pier Skew, UpSta & Num, DnSta & Num=  ,4525, 2 ,4525, 2 , 0 , 0 , 0 ,,
       6       6
     415     450
       6       6
     415     450
Pier Skew, UpSta & Num, DnSta & Num=  ,4605, 2 ,4605, 2 , 0 , 0 , 0 ,,
       6       6
     415     450
       6       6
     415     450
Pier Skew, UpSta & Num, DnSta & Num=  ,4685, 2 ,4685, 2 , 0 , 0 , 0 ,,
       6       6
     415     450
       6       6
     415     450
Pier Skew, UpSta & Num, DnSta & Num=  ,4765, 2 ,4765, 2 , 0 , 0 , 0 ,,
       6       6
     415     450
       6       6
     415     450
Pier Skew, UpSta & Num, DnSta & Num=  ,4845, 2 ,4845, 2 , 0 , 0 , 0 ,,
       6       6
     415     450
       6       6
     415     450
Pier Skew, UpSta & Num, DnSta & Num=  ,4895, 2 ,4895, 2 , 0 , 0 , 0 ,,
       3       3
     415     450
       3       3
     415     450
Pier Skew, UpSta & Num, DnSta & Num=  ,4986, 2 ,4986, 2 , 0 , 0 , 0 ,,
       3       3
     415     450
       3       3
     415     450
Pier Skew, UpSta & Num, DnSta & Num=  ,5111, 2 ,5111, 2 , 0 , 0 , 0 ,,
       3       3
     415     450
       3       3
     415     450
Pier Skew, UpSta & Num, DnSta & Num=  ,5203, 2 ,5203, 2 , 0 , 0 , 0 ,,
       3       3
     415     450
       3       3
     415     450
Pier Skew, UpSta & Num, DnSta & Num=  ,5285, 2 ,5285, 2 , 0 , 0 , 0 ,,
       6       6
     415     450
       6       6
     415     450
Pier Skew, UpSta & Num, DnSta & Num=  ,5390, 2 ,5390, 2 , 0 , 0 , 0 ,,
       6       6
     415     450
       6       6
     415     450
Pier Skew, UpSta & Num, DnSta & Num=  ,5480, 2 ,5480, 2 , 0 , 0 , 0 ,,
       6       6
     415     450
       6       6
     415     450
Pier Skew, UpSta & Num, DnSta & Num=  ,5571, 2 ,5571, 2 , 0 , 0 , 0 ,,
       6       6
     415     450
       6       6
     415     450
BR Coef= 1 , 0 , 0 ,1.05, 0 ,,,0.8,-1,0.5,1,
WSPro=,,,, 1 ,,,, 0 ,,,, 0 ,,,,-1 ,-1 ,-1 , 0 , 0 , 0 , 0 , 0
BC Design=,, 0 ,, 0 ,,,,,,
BC HTab HWMax=450.5
BC Use User HTab Curves=0
BC User HTab FreeFlow(D)= 0

Type RM Length L Ch R = 1 ,64211   ,1,1,1
BEGIN DESCRIPTION:
This cross section corresponds to cross section 64196 of the non-georeferenced CDC model which was the source of this model.
END DESCRIPTION:
XS GIS Cut Line= 2
2450271.562415757017045.48863047 2448431.02803917017513.07102863
#Sta/Elev= 30
    3740   450.5    3740   444.5    3773   428.3    3907   428.5    3982   427.3
    4003  420.44    4019   413.1    4045   404.2    4058   401.6    4068   402.7
    4088     404    4102   413.1    4128  420.76    4169   423.4    4254   426.6
    4390   425.8    4551   427.5    4714   428.8    4808   428.6    4889   429.2
    4904   428.7    5151   427.6    5496   428.3    5528   429.6    5565   428.6
    5584   428.9    5606   428.8    5610     430    5639   444.5    5639   450.5
#Mann= 3 ,0,0
    3740     .07       0    3982     .05       0    4254     .07       0
Bank Sta=3982,4254
XS Rating Curve= 0 ,0
Exp/Cntr=0.5,0.3

Type RM Length L Ch R = 1 ,64210   ,86,86,86
BEGIN DESCRIPTION:
This cross section corresponds to cross section 64195 of the non-georeferenced CDC model which was the source of this model.
END DESCRIPTION:
XS GIS Cut Line= 2
2450271.582756947017044.505036642448431.050348767017512.09629305
#Sta/Elev= 30
    3740   450.5    3740   444.5    3773   428.3    3907   428.5    3982   427.3
    4003  420.44    4019   413.1    4045   404.2    4058   401.6    4068   402.7
    4088     404    4102   413.1    4128  420.76    4169   423.4    4254   426.6
    4390   425.8    4551   427.5    4714   428.8    4808   428.6    4889   429.2
    4904   428.7    5151   427.6    5496   428.3    5528   429.6    5565   428.6
    5584   428.9    5606   428.8    5610     430    5639   444.5    5639   450.5
#Mann= 3 ,0,0
    3740     .07       0    3982     .05       0    4254     .07       0
Bank Sta=3982,4254
XS Rating Curve= 0 ,0
Exp/Cntr=0.3,0.1

Type RM Length L Ch R = 1 ,64124   ,751,724,721
BEGIN DESCRIPTION:
This cross section corresponds to cross section 64104 of the non-georeferenced CDC model which was the source of this model.
END DESCRIPTION:
XS GIS Cut Line= 3
2450389.696037777016925.415707892448393.332576427017433.48293322
2446455.115480987017926.75212034
#Sta/Elev= 30
    3600   432.9    3696   432.9    3718   429.5    3722   428.3    3745     428
    3920   428.5    3982   427.3    4002   420.9    4019   413.1    4041   404.2
    4054   401.8    4084     404    4100   411.8    4102   413.1    4127   420.7
    4138   422.5    4254   426.6    4390   425.8    4551   427.5    4714   428.8
    4808   428.6    4889   429.2    4904   428.7    5151   427.6    5496   428.3
    5528   429.6    5565   428.6    5606   428.8    5610     430    7660     430
#Mann= 4 ,-1,0
    3600     .12       0    3920     .05       0    4127     .09       0
    5151     .07       0
#XS Ineff= 2 , 0
       0                    5660       0     450
Permanent Ineff=
       F       F
Bank Sta=3982,4254
XS Rating Curve= 0 ,0
Exp/Cntr=0.3,0.1

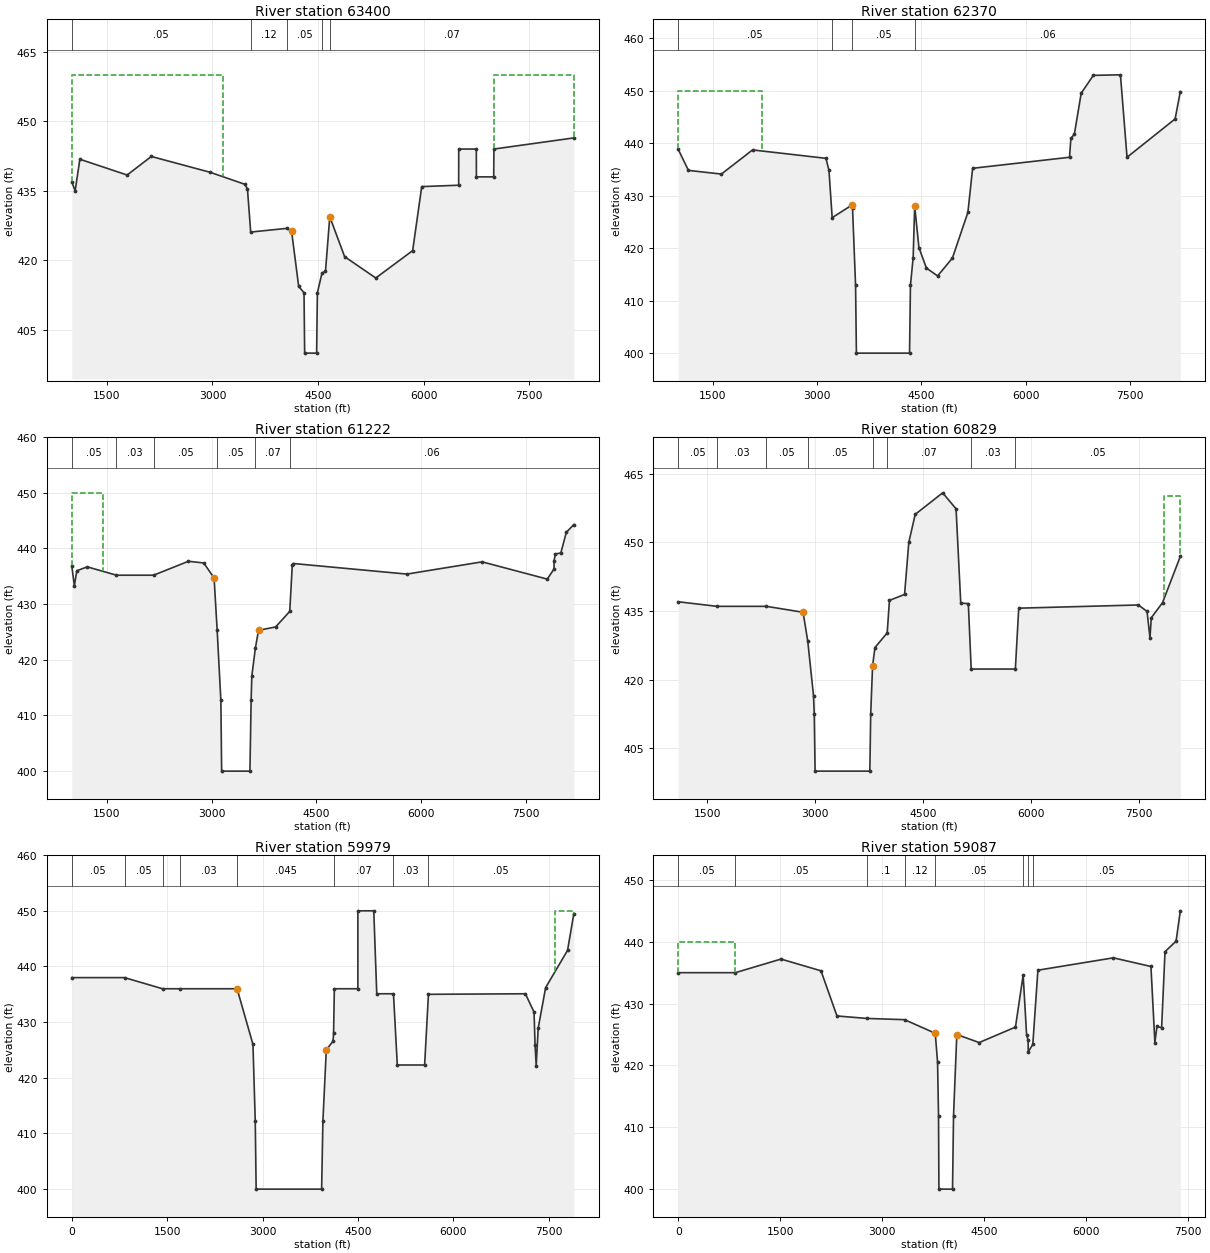
Type RM Length L Ch R = 1 ,63400   ,1000,1030,1100
BEGIN DESCRIPTION:
This cross section corresponds to cross section 63381 of the non-georeferenced CDC model which was the source of this model.
END DESCRIPTION:
XS GIS Cut Line= 3
2453390.246795187016192.570060722449422.949939767016467.05901305
2446312.103471167017017.78232105
#Sta/Elev= 30
    1000   436.9    1048     435    1115   441.8    1787   438.4    2131   442.4
    2964     439    3460   436.4    3497   435.4    3543   426.1    4056   426.9
    4124   426.3    4225   414.4    4301     413    4310     400    4480     400
    4491     413    4557   417.3    4606   417.6    4667   429.4    4878   420.8
    5321   416.2    5845   422.1    5974   435.9    6499   436.2    6500     444
    6750     444    6751     438    6997     438    7000     444    8136   446.4
#Mann= 5 ,-1,0
    1000     .05       0    3543     .12       0    4056     .05       0
    4557     .12       0    4667     .07       0
#XS Ineff= 2 , 0
       0    3150     460    7000       0     460
Permanent Ineff=
       F       F
Bank Sta=4124,4667
XS Rating Curve= 0 ,0
Exp/Cntr=0.3,0.1

Type RM Length L Ch R = 1 ,62370   ,800,1148,700
BEGIN DESCRIPTION:
This cross section corresponds to cross section 62351 of the non-georeferenced CDC model which was the source of this model.
LOMR#14-06-2597P & CDC# FB100113-1 Mercer Crossing
Cross-sections 67169 & 62351.  Fill was added in innefective flow area so no physical cross-section change.
END DESCRIPTION:
XS GIS Cut Line= 3
2453739.509876167015648.992079632449179.379888837015736.34918839
2446518.20542118 7015913.0335463
#Sta/Elev= 30
    1000   438.8    1147   434.8    1621   434.1    2070   438.7    3126   437.1
    3170   434.8    3216   425.8    3501   428.2    3509   427.7    3553   412.9
    3565     400    4330     400    4343   412.9    4382   418.2    4404     428
    4465   420.1    4573   416.2    4734   414.7    4947   418.1    5170   426.8
    5238   435.2    6633   437.3    6653   440.9    6703   441.7    6801   449.5
    6976   452.9    7366     453    7461   437.3    8153   444.6    8228   449.8
#Mann= 4 ,-1,0
    1000     .05       0    3216      .1       0    3501     .05       0
    4404     .06       0
#XS Ineff= 2 , 0
       0    2200     450               0
Permanent Ineff=
       F       F
Bank Sta=3501,4404
XS Rating Curve= 0 ,0
Exp/Cntr=0.3,0.1

Type RM Length L Ch R = 1 ,61222   ,400,393,550
BEGIN DESCRIPTION:
This cross section corresponds to cross section 61203 of the non-georeferenced CDC model which was the source of this model.
END DESCRIPTION:
XS GIS Cut Line= 4
2453864.556870167014912.291125222451020.959867097014900.08609714
2449806.514133247015048.058242132446688.293335597015115.47936714
#Sta/Elev= 30
    1000   436.9    1037   433.3    1072     436    1222   436.7    1640   435.2
    2171   435.2    2669   437.7    2889   437.4    3037   434.7    3081   425.3
    3134   412.7    3145     400    3550     400    3567   412.7    3577   417.1
    3628   422.1    3673   425.3    3917   425.9    4120   428.7    4156     437
    4173   437.3    5796   435.4    6873   437.6    7805   434.5    7902   436.3
    7903   437.8    7921     439    8000   439.2    8078   442.9    8186   444.3
#Mann= 6 ,-1,0
    1000     .05       0    1640     .03       0    2171     .05       0
    3081     .05       0    3628     .07       0    4120     .06       0
#XS Ineff= 2 , 0
       0    1450     450               0
Permanent Ineff=
       F       F
Bank Sta=3037,3673
XS Rating Curve= 0 ,0
Exp/Cntr=0.3,0.1

Type RM Length L Ch R = 1 ,60829   ,830,850,850
BEGIN DESCRIPTION:
This cross section corresponds to cross section 60810 of the non-georeferenced CDC model which was the source of this model.
END DESCRIPTION:
XS GIS Cut Line= 2
 2453763.08200757014506.986161542446793.090698187014517.86606105
#Sta/Elev= 30
    1100     437    1640     436    2325     436    2833   434.7    2898   428.4
    2978   416.5    2988   412.5    3000     400    3760     400    3772   412.5
    3798     423    3831     427    4001   430.2    4032   437.3    4242   438.6
    4301     450    4390   456.1    4771   460.8    4957   457.3    5022   436.7
    5127   436.6    5167   422.3    5780   422.3    5827   435.6    7487   436.3
    7608   434.9    7649   429.1    7667   433.5    7823   436.8    8070   446.9
#Mann= 8 ,-1,0
    1100     .05       0    1640     .03       0    2325     .05       0
    2898     .05       0    3798     .08       0    4001     .07       0
    5167     .03       0    5780     .05       0
#XS Ineff= 2 , 0
       0                    7850       0     460
Permanent Ineff=
       F       F
Bank Sta=2833,3798
XS Rating Curve= 0 ,0
Exp/Cntr=0.3,0.1

Type RM Length L Ch R = 1 ,59979   ,805,892,784
BEGIN DESCRIPTION:
This cross section corresponds to cross section 59960 of the non-georeferenced CDC model which was the source of this model.
END DESCRIPTION:
XS GIS Cut Line= 3
2454858.365645387013700.116963382454028.377080597013695.76009372
2446961.474547747013658.66371122
#Sta/Elev= 30
       0     438     830     438    1428     436    1700     436    2600     436
    2850     426    2886   412.2    2900     400    3930     400    3950   412.2
    4003     425    4110   426.6    4118     428    4130     436    4500     436
    4500     450    4750     450    4797   435.1    5060   435.1    5120   422.3
    5550   422.3    5610     435    7135   435.1    7271   431.8    7287   425.9
    7305   422.2    7336   428.9    7453   436.2    7798   442.9    7897   449.5
#Mann= 8 ,-1,0
       0     .05       0     830     .05       0    1428     .06       0
    1700     .03       0    2600    .045       0    4130     .07       0
    5060     .03       0    5610     .05       0
#XS Ineff= 2 , 0
       0                    7600       0     450
Permanent Ineff=
       F       F
Bank Sta=2600,4003
XS Rating Curve= 0 ,0
Exp/Cntr=0.3,0.1

Type RM Length L Ch R = 1 ,59087   ,414,414,414
BEGIN DESCRIPTION:
This cross section corresponds to cross section 59073 of the non-georeferenced CDC model which was the source of this model.
END DESCRIPTION:
XS GIS Cut Line= 3
2454852.64957959 7012888.10723532454012.650077917012889.02220589
2447466.653983597012896.15244097
#Sta/Elev= 30
       0     435     840     435    1512   437.2    2100   435.3    2335     428
    2777   427.6    3330   427.4    3781   425.2    3815   420.5    3829   411.9
    3835     400    4035     400    4050   411.9    4098     425    4427   423.7
    4961   426.2    5074   434.6    5125   424.9    5147   424.1    5149   422.2
    5216   423.4    5291   435.4    6401   437.4    6954     436    7012   423.7
    7042   426.3    7111   426.1    7161   438.4    7324   440.1    7386     445
#Mann= 8 ,-1,0
       0     .05       0     840     .05       0    2777      .1       0
    3330     .12       0    3781     .05       0    5074     .07       0
    5147     .02       0    5216     .05       0
#XS Ineff= 2 , 0
       0     840     440               0
Permanent Ineff=
       F       F
Bank Sta=3781,4098
XS Rating Curve= 0 ,0
Exp/Cntr=0.3,0.1