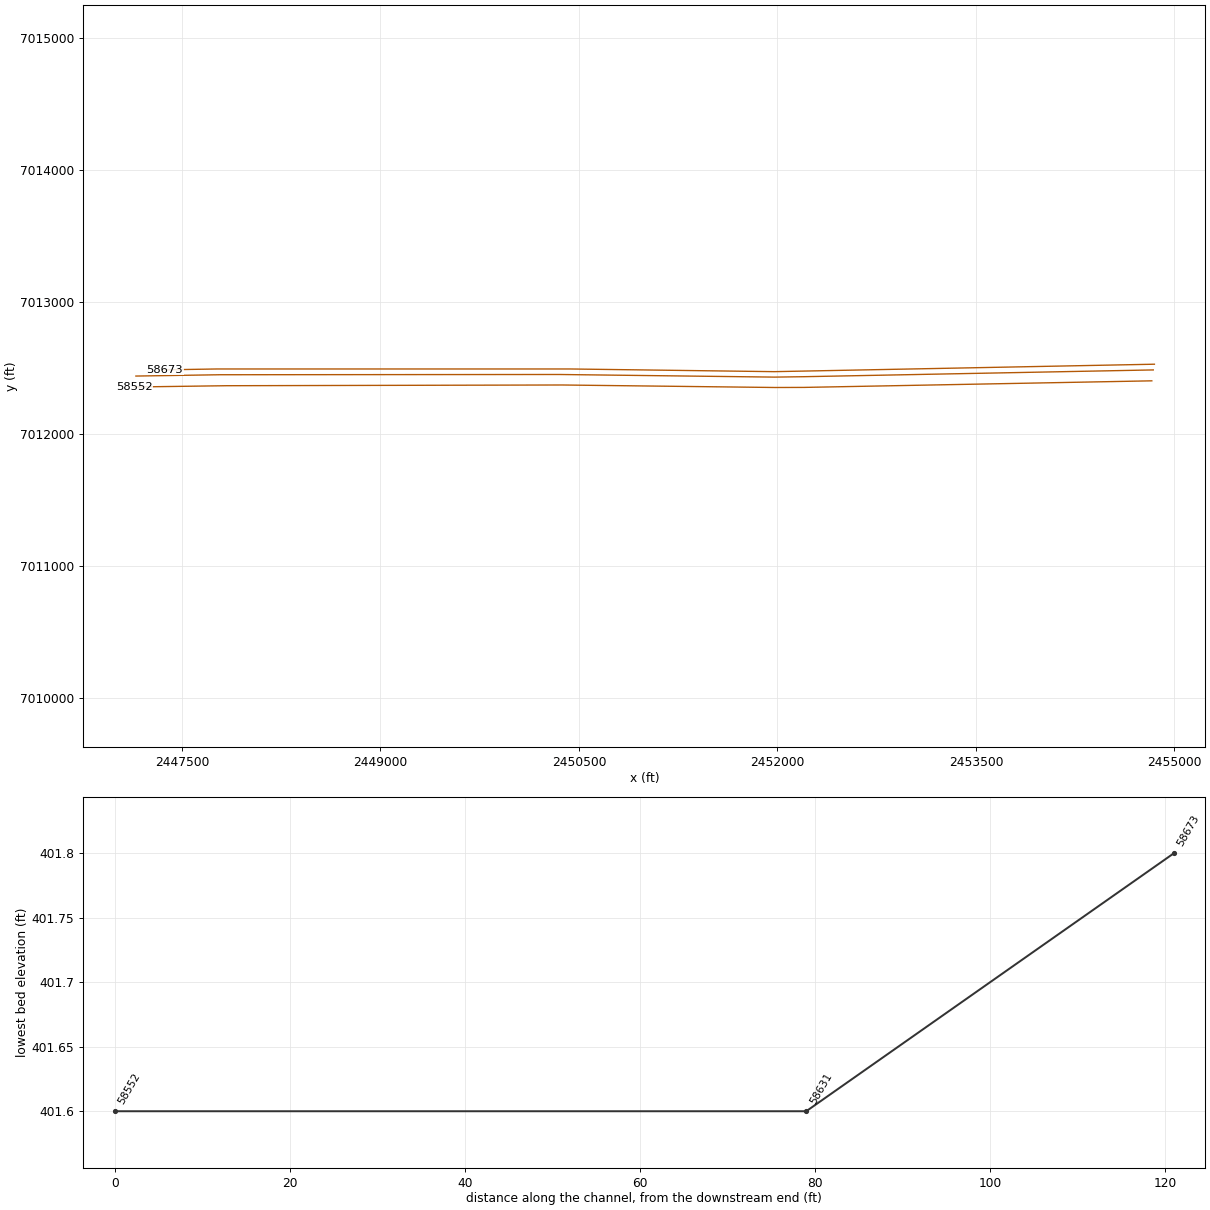
HEC-RAS study CDC_Consolidated_Model.prj: Upper Trinity CDC Consolidated Model

--- CDC_Consolidated_Model.g04 (geometry) --- (continued)

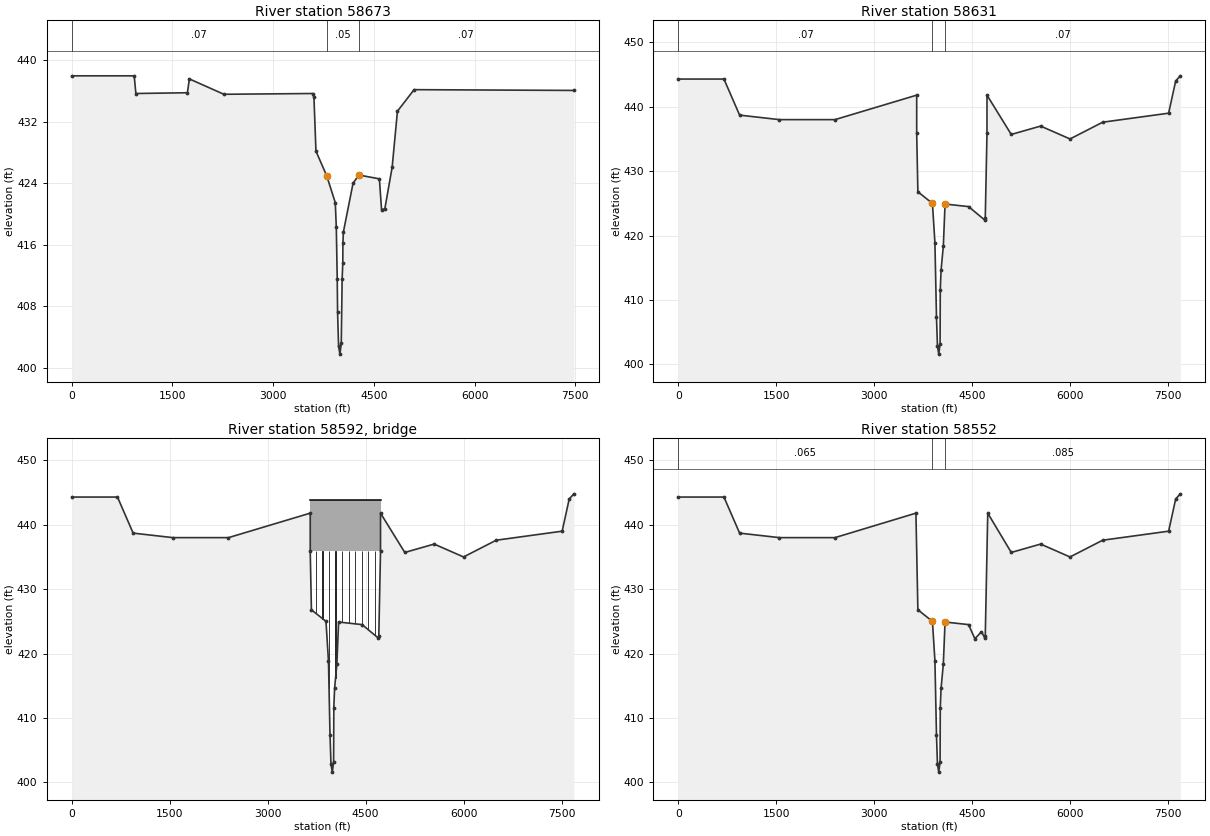
Type RM Length L Ch R = 1 ,58673   ,42,42,42
BEGIN DESCRIPTION:
This cross section corresponds to cross section 58654 of the non-georeferenced CDC model which was the source of this model.
END DESCRIPTION:
XS GIS Cut Line= 6
2454848.755781297012528.446664872453998.919134267012511.78313097
2451975.095097937012472.100139472450436.093910847012492.41604371
2447764.428978597012492.416043712447369.497353767012485.82517764
#Sta/Elev= 30
       0     438     930     438     955   435.7    1723   435.8    1752   437.6
    2266   435.6    3590   435.7    3608   435.2    3638   428.2    3798     425
    3926   421.5    3941   418.3    3955   411.6    3960   407.3    3975   402.8
    3995   401.8    4015   403.2    4028   411.6    4038   413.7    4039   416.2
    4047   417.7    4190     424    4275   425.1    4583   424.6    4615   420.6
    4664   420.7    4773   426.1    4852   433.4    5100   436.2    7480   436.1
#Mann= 3 ,0,0
       0     .07       0    3798     .05       0    4275     .07       0
Bank Sta=3798,4275
XS Rating Curve= 0 ,0
Exp/Cntr=0.3,0.1

Type RM Length L Ch R = 1 ,58631   ,79,79,79
BEGIN DESCRIPTION:
This cross section corresponds to cross section 58612 of the non-georeferenced CDC model which was the source of this model.
END DESCRIPTION:
XS GIS Cut Line= 6
2454840.271420717012485.239766162452198.67831218 7012433.9302683
2451977.422849187012430.837426722450352.339813267012450.69893555
2447789.279650667012448.807535132447151.997460667012438.79607221
#Sta/Elev= 30
       0   444.3     700   444.3     940   438.7    1550     438    2400     438
  3651.8   441.8  3651.8   435.9    3670   426.8    3893     425    3931   418.9
    3955   407.3    3970   402.8    3990   401.6    4010   403.2    4013   411.6
    4025   414.6    4060   418.4    4086   424.9    4446   424.5    4696   422.4
    4702   422.7  4728.3  435.88  4728.3   441.8    5100   435.7    5550     437
    6000     435    6500   437.6    7510     439    7618     444    7689   444.8
#Mann= 3 ,0,0
       0     .07       0    3893     .05       0    4086     .07       0
Bank Sta=3893,4086
XS Rating Curve= 0 ,0
Exp/Cntr=0.5,0.3

Type RM Length L Ch R = 3 ,58592   ,,,
BEGIN DESCRIPTION:
Royal Lane
END DESCRIPTION:
Node Name=Royal Lane
Bridge Culvert--1,0,-1,-1, 0
Deck Dist Width WeirC Skew NumUp NumDn MinLoCord MaxHiCord MaxSubmerge Is_Ogee
1,77,2.6,0, 22, 22, , , 0.95, 0, ,,,
  3651.8  3738.5  3741.5  3838.5  3841.5  3938.5  3941.5  4038.5  4041.5  4138.5
  4141.5  4238.5  4241.5  4338.5  4341.5  4438.5  4441.5  4538.5  4541.5  4638.5
  4641.5  4728.3
   443.8   443.8   443.8   443.8   443.8   443.8   443.8   443.8   443.8   443.8
   443.8   443.8   443.8   443.8   443.8   443.8   443.8   443.8   443.8   443.8
   443.8   443.8
   435.9   435.9   435.9   435.9   435.9   435.9   435.9   435.9   435.9   435.9
   435.9   435.9   435.9   435.9   435.9   435.9   435.9   435.9   435.9   435.9
   435.9   435.9
  3651.8  3738.5  3741.5  3838.5  3841.5  3938.5  3941.5  4038.5  4041.5  4138.5
  4141.5  4238.5  4241.5  4338.5  4341.5  4438.5  4441.5  4538.5  4541.5  4638.5
  4641.5  4728.3
   443.8   443.8   443.8   443.8   443.8   443.8   443.8   443.8   443.8   443.8
   443.8   443.8   443.8   443.8   443.8   443.8   443.8   443.8   443.8   443.8
   443.8   443.8
   435.9   435.9   435.9   435.9   435.9   435.9   435.9   435.9   435.9   435.9
   435.9   435.9   435.9   435.9   435.9   435.9   435.9   435.9   435.9   435.9
   435.9   435.9
Pier Skew, UpSta & Num, DnSta & Num=  ,3740, 2 ,3740, 2 , 0 , 0 , 0 ,,
       3       3
     410     440
       3       3
     410     440
Pier Skew, UpSta & Num, DnSta & Num=  ,3840, 2 ,3840, 2 , 0 , 0 , 0 ,,
       3       3
     410     440
       3       3
     410     440
Pier Skew, UpSta & Num, DnSta & Num=  ,3940, 2 ,3940, 2 , 0 , 0 , 0 ,,
       3       3
     410     440
       3       3
     410     440
Pier Skew, UpSta & Num, DnSta & Num=  ,4040, 2 ,4040, 2 , 0 , 0 , 0 ,,
       3       3
     410     440
       3       3
     410     440
Pier Skew, UpSta & Num, DnSta & Num=  ,4140, 2 ,4140, 2 , 0 , 0 , 0 ,,
       3       3
     410     440
       3       3
     410     440
Pier Skew, UpSta & Num, DnSta & Num=  ,4240, 2 ,4240, 2 , 0 , 0 , 0 ,,
       3       3
     410     440
       3       3
     410     440
Pier Skew, UpSta & Num, DnSta & Num=  ,4340, 2 ,4340, 2 , 0 , 0 , 0 ,,
       3       3
     410     440
       3       3
     410     440
Pier Skew, UpSta & Num, DnSta & Num=  ,4440, 2 ,4440, 2 , 0 , 0 , 0 ,,
       3       3
     410     440
       3       3
     410     440
Pier Skew, UpSta & Num, DnSta & Num=  ,4540, 2 ,4540, 2 , 0 , 0 , 0 ,,
       3       3
     410     440
       3       3
     410     440
Pier Skew, UpSta & Num, DnSta & Num=  ,4640, 2 ,4640, 2 , 0 , 0 , 0 ,,
       3       3
     410     440
       3       3
     410     440
BR Coef= 1 , 0 , 0 ,1.05, 0 ,,,0.8,-1,0.5,1,
WSPro=,,,, 1 ,,,, 0 ,,,, 0 ,,,,-1 ,-1 ,-1 , 0 , 0 , 0 , 0 , 0
BR D #Sta/Elev= 88
     700   444.3     940   438.7    1550     438    1650     438    2050     438
    2150     438    2300     438    2400     438    3620   441.7    3640   441.8
  3651.8   441.8  3651.8   435.9    3670   426.8  3738.5  426.05  3741.5  426.02
    3743     426    3759   425.7    3789   425.4  3838.5  425.77  3841.5   425.8
    3842   425.8    3869   425.6    3893     425    3921   420.3    3931   418.9
  3938.5   415.6  3941.5  414.26    3943   413.6    3948   411.6    3955   407.3
    3970   402.8    3990   401.6    4010   403.2    4013   411.6    4025   414.6
    4031   415.7  4038.5   416.4  4041.5  416.68    4060   418.4    4086   424.9
    4102   425.6  4138.5   425.6  4141.5   425.6    4143   425.6    4205     425
  4238.5  424.81  4241.5   424.8    4259   424.7    4297   424.2  4338.5     424
  4341.5  423.94    4381   423.7    4411   423.8  4438.5  424.35  4441.5   424.4
    4446   424.5    4481   422.9    4512   422.8  4538.5  422.37  4541.5   422.3
    4543   422.3    4598   422.3    4625   422.5  4638.5  423.14  4641.5   423.3
    4644   423.4    4650     423    4678     423    4696   422.4    4702   422.7
  4728.3  435.88  4728.3   441.8    4740   441.8    4760   441.7    5100   435.7
    5200   435.7    5450     437    5550     437    5900     435    6000     435
    6500   437.6    7510     439    7543   439.9    7586   442.4    7600   442.8
    7618     444    7646   444.6    7689   444.8
BR D #Mann= 3
     700     .07    3893     .05    4086     .07
BC Design=,, 0 ,, 0 ,,,,,,
BC HTab HWMax=444.8
BC Use User HTab Curves=0
BC User HTab FreeFlow(D)= 0

Type RM Length L Ch R = 1 ,58552   ,104,104,104
BEGIN DESCRIPTION:
This cross section corresponds to cross section 58532 of the non-georeferenced CDC model which was the source of this model.
END DESCRIPTION:
XS GIS Cut Line= 6
 2454829.11679827012402.706492852452200.856129357012352.91796313
2451981.86083242 7012352.24145532450373.41063726 7012371.2374803
2447836.61452976 7012365.74339682447140.775698337012356.11513522
#Sta/Elev= 30
       0   444.3     700   444.3     940   438.7    1550     438    2400     438
    3640   441.8    3670   426.8    3893     425    3931   418.9    3955   407.3
    3970   402.8    3990   401.6    4010   403.2    4013   411.6    4025   414.6
    4060   418.4    4086   424.9    4446   424.5    4543   422.3    4644   423.4
    4696   422.4    4702   422.7    4740   441.8    5100   435.7    5550     437
    6000     435    6500   437.6    7510     439    7618     444    7689   444.8
#Mann= 3 ,0,0
       0    .065       0    3893     .05       0    4086    .085       0
Bank Sta=3893,4086
XS Rating Curve= 0 ,0
Exp/Cntr=0.3,0.1