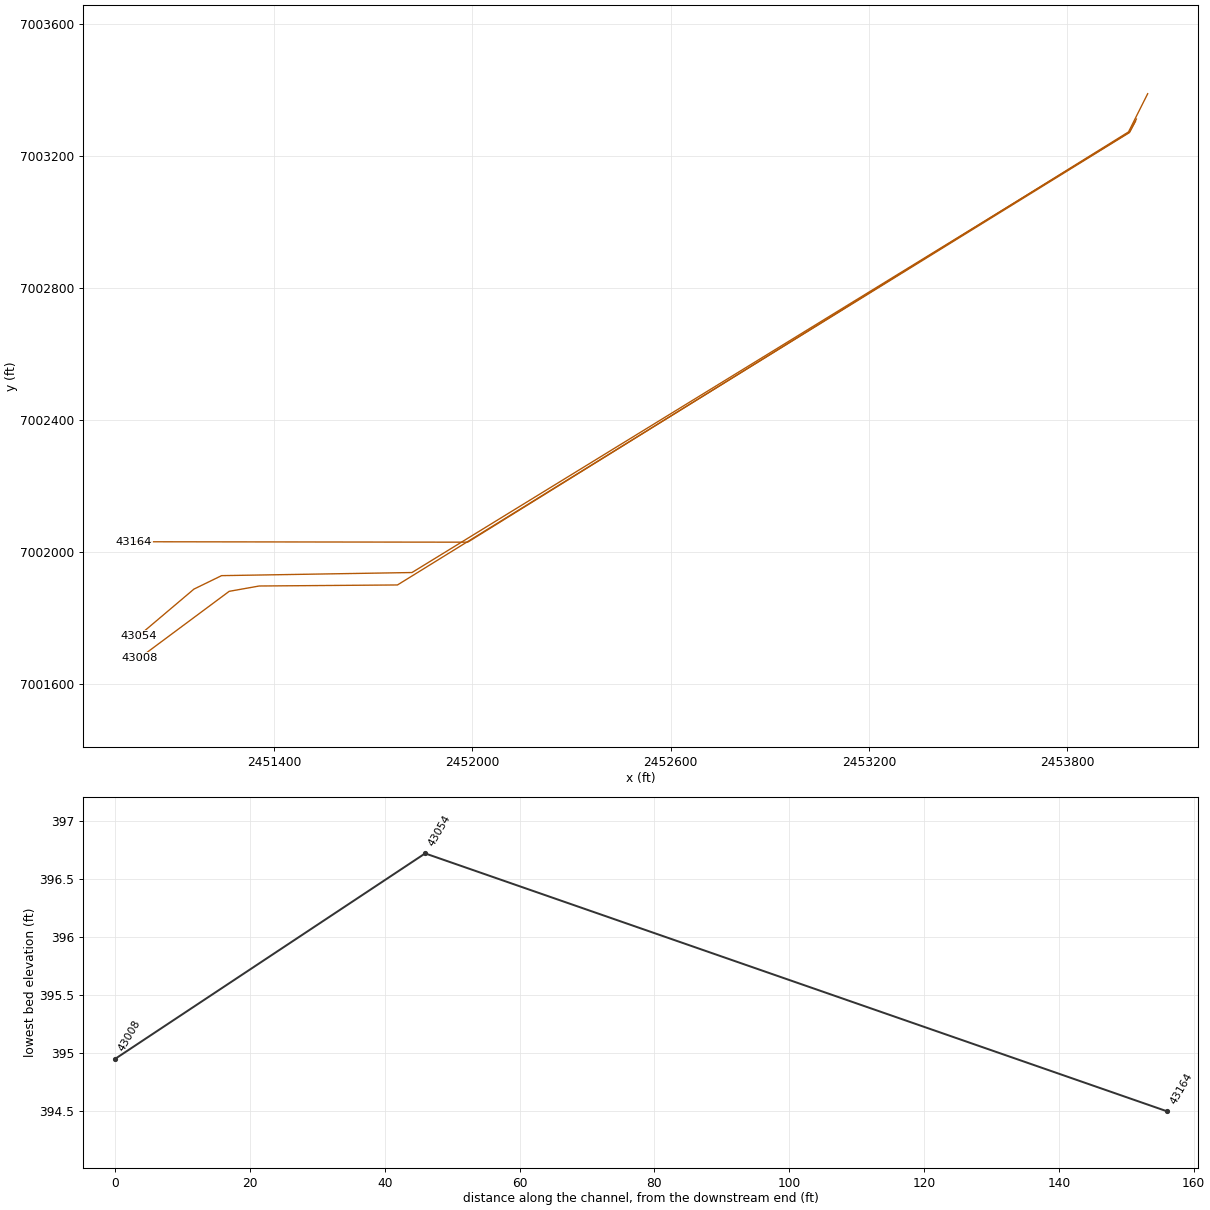
HEC-RAS study CDC_Consolidated_Model.prj: Upper Trinity CDC Consolidated Model

--- CDC_Consolidated_Model.g04 (geometry) --- (continued)

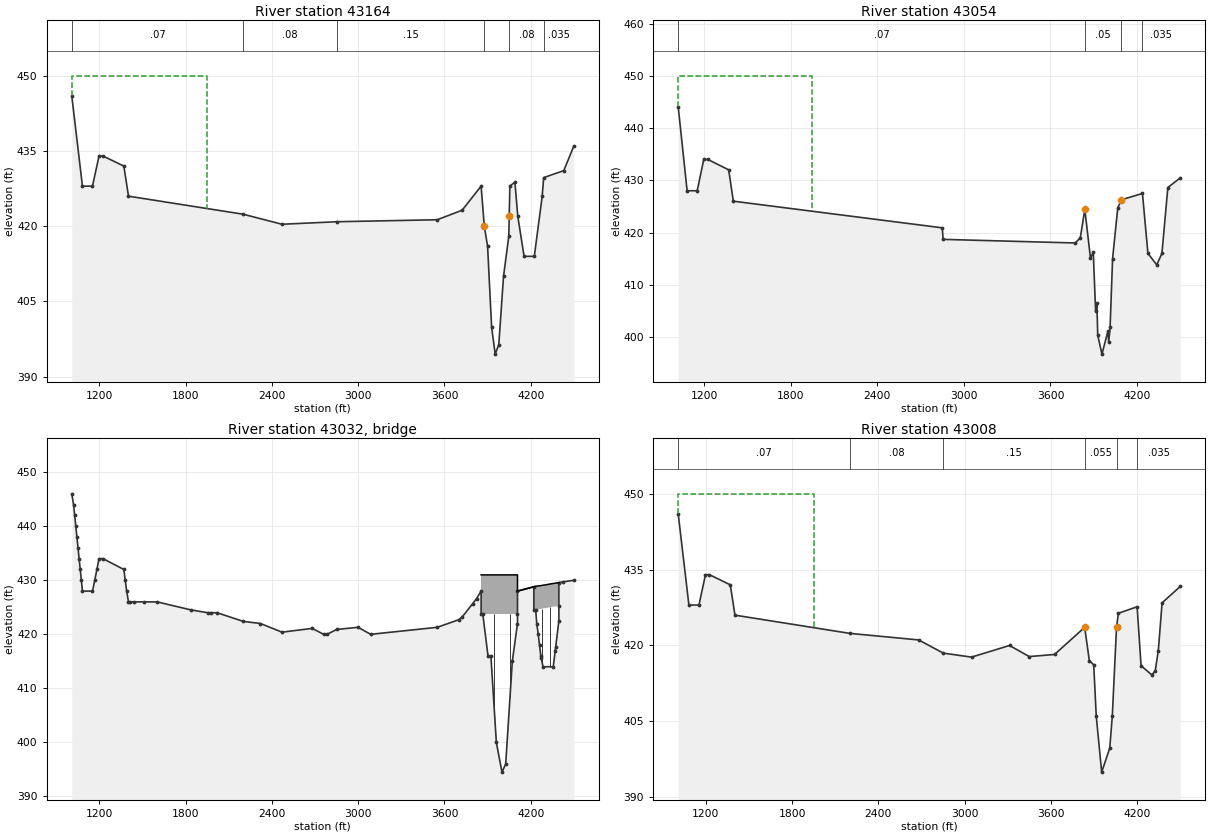
Type RM Length L Ch R = 1 ,43164   ,110,110,110
BEGIN DESCRIPTION:
This cross section corresponds to cross section 43144 of the non-georeferenced CDC model which was the source of this model.
END DESCRIPTION:
XS GIS Cut Line= 5
2454042.977773167003387.689502552454031.395119167003364.59276396
2453984.925395857003271.930547712451985.799800937002030.01603679
2450976.579706527002031.33230713
#Sta/Elev= 30
  1007.8     446    1082     428  1151.9     428  1197.3     434  1225.2     434
    1370     432  1402.3     426    2200   422.4    2470   420.4    2850   420.9
    3550   421.3    3723   423.2    3855     428  3877.2     420  3900.1     416
    3928   399.9    3953   394.5    3978   396.4  4010.8     410  4047.6     418
  4050.6     422    4055     428    4090   428.8    4110     422  4153.8     414
    4225     414    4280     426    4290   429.7    4430   431.1    4500     436
#Mann= 6 ,-1,0
  1007.8     .07       0    2200     .08       0    2850     .15       0
  3877.2     .05       0  4050.6     .08       0    4290    .035       0
#XS Ineff= 2 , 0
       0    1950     450               0
Permanent Ineff=
       F       F
Bank Sta=3877.2,4050.6
XS Rating Curve= 0 ,0
Exp/Cntr=0.3,0.1

Type RM Length L Ch R = 1 ,43054   ,46,46,46
BEGIN DESCRIPTION:
This cross section corresponds to cross section 43026 of the non-georeferenced CDC model which was the source of this model.
-----------------------------------
CDC DAL071508-1 California Crossing
Cross-section 42984 - 43026
-----------------------------------
Cross-section was imported from Geopak
END DESCRIPTION:
XS GIS Cut Line= 6
2454008.696345697003310.946545792453987.395207177003270.87543172
 2451817.26732967001938.14548564 2451241.2389541 7001928.7367118
2451157.605263087001887.965139812450991.633810257001747.51069631
#Sta/Elev= 30
  1020.4     444    1082     428  1151.9     428  1197.3     434  1225.2     434
    1370     432  1402.3     426    2850   420.9 2856.34  418.69 3772.38     418
 3806.94  419.01 3838.27  424.44 3877.32   415.1  3896.7  416.22 3913.15  404.89
 3921.92  406.44 3927.63  400.32    3957  396.72 3998.06  401.09 4003.98  399.05
 4013.35  401.85 4030.62     415 4066.61  424.74  4091.7  426.27 4237.68  427.48
 4275.57     416 4336.88  413.81  4372.5  415.99 4413.74  428.62    4500  430.46
#Mann= 4 ,-1,0
  1020.4     .07       0 3838.27     .05       0  4091.7     .08       0
 4237.68    .035       0
#XS Ineff= 2 , 0
       0    1950     450               0
Permanent Ineff=
       F       F
Bank Sta=3838.27,4091.7
XS Rating Curve= 0 ,0
Exp/Cntr=0.5,0.3

Type RM Length L Ch R = 3 ,43032   ,,,
BEGIN DESCRIPTION:
California Crossing Road
Data from TXDOT bridge plans 2008.
END DESCRIPTION:
Node Name=California Cross
Bridge Culvert--1,0,-1,-1, 0
Deck Dist Width WeirC Skew NumUp NumDn MinLoCord MaxHiCord MaxSubmerge Is_Ogee
1.25,42.5,2.6,0, 13, 13, , , 0.95, 0, ,,,
    3855    4108    4108    4108 4221.94 4221.94 4234.44 4270.74 4273.44 4370.44
 4373.44 4373.44 4395.94
     431     431     428     428   428.8   428.8   428.9  429.02  429.03  429.47
  429.48  429.48  429.56
   423.7   423.7   423.7     428   428.8   424.5  424.56  424.72  424.73  425.17
  425.18  425.18  425.26
    3855    4108    4108    4108 4221.94 4221.94 4234.44 4270.74 4273.44 4370.44
 4373.44 4373.44 4395.94
     431     431     428     428   428.8   428.8   428.9  429.02  429.03  429.47
  429.48  429.48  429.56
   423.7   423.7   423.7     428   428.8   424.5  424.56  424.72  424.73  425.17
  425.18  425.18  425.26
Pier Skew, UpSta & Num, DnSta & Num=  ,3946, 2 ,3946, 2 , 0 , 0 , 0 ,,
     3.5     3.5
     405     425
     3.5     3.5
     405     425
Pier Skew, UpSta & Num, DnSta & Num=  ,4056, 2 ,4056, 2 , 0 , 0 , 0 ,,
     3.5     3.5
     405     425
     3.5     3.5
     405     425
Pier Skew, UpSta & Num, DnSta & Num=  ,4278.438, 2 ,4278.438, 2 , 0 , 0 , 0 ,,
       3       3
     405     425
       3       3
     405     425
Pier Skew, UpSta & Num, DnSta & Num=  ,4334.94, 2 ,4334.94, 2 , 0 , 0 , 0 ,,
       3       3
     405     426
       3       3
     405     426
BR Coef= 1 , 0 , 0 ,1.05, 0 ,,,0.8,-1,0.5,1,
WSPro=,,,, 1 ,,,, 0 ,,,, 0 ,,,,-1 ,-1 ,-1 , 0 , 0 , 0 , 0 , 0
BR U #Sta/Elev= 70
  1007.8     446  1020.4     444  1028.1     442  1035.8     440  1043.5     438
  1051.2     436  1058.8     434  1066.7     432  1074.5     430    1082     428
  1151.9     428  1167.6     430  1182.5     432  1197.3     434  1225.2     434
    1370     432  1379.6     430  1389.7     428  1402.3     426  1415.5     426
  1442.6     426  1509.2     426  1601.7     426    1840   424.5  1953.8     424
  1977.8     424  2018.2     424    2200   422.4  2320.3     422    2470   420.4
    2680   421.1  2759.6     420  2783.4     420    2850   420.9    3000   421.3
  3086.6     420    3550   421.3    3699   422.7    3723   423.2    3797   425.7
    3823   426.6    3855     428    3855   423.7  3866.9   423.7    3903     416
    3923     416    3961     400    4000   394.5    4026     396    4072     415
    4108     422    4108   423.7    4108     428 4221.94   428.8 4221.94   424.5
 4234.44  424.56 4241.94     422 4252.34     420 4261.34     418 4270.44     416
 4273.44  415.61 4285.74     414 4356.94     414 4370.44     417 4373.44   417.6
 4395.94  422.51 4395.94  425.26 4395.94  429.56 4421.94   429.7    4500     430
BR U #Mann= 1
  1007.8     .05
BR U Banks=3866.9,4108
BR D #Sta/Elev= 70
  1007.8     446  1020.4     444  1028.1     442  1035.8     440  1043.5     438
  1051.2     436  1058.8     434  1066.7     432  1074.5     430    1082     428
  1151.9     428  1167.6     430  1182.5     432  1197.3     434  1225.2     434
    1370     432  1379.6     430  1389.7     428  1402.3     426  1415.5     426
  1442.6     426  1509.2     426  1601.7     426    1840   424.5  1953.8     424
  1977.8     424  2018.2     424    2200   422.4  2320.3     422    2470   420.4
    2680   421.1  2759.6     420  2783.4     420    2850   420.9    3000   421.3
  3086.6     420    3550   421.3    3699   422.7    3723   423.2    3797   425.7
    3823   426.6    3855     428    3855   423.7  3866.9   423.7    3903     416
    3923     416    3961     400    4000   394.5    4026     396    4072     415
    4108     422    4108   423.7    4108     428 4221.94   428.8 4221.94   424.5
 4234.44  424.56 4241.94     422 4252.34     420 4261.34     418 4270.44     416
 4273.44  415.61 4285.74     414 4356.94     414 4370.44     417 4373.44   417.6
 4395.94  422.51 4395.94  425.26 4395.94  429.56 4421.94   429.7    4500     430
BR D #Mann= 1
  1007.8     .05
BR D Banks=3866.9,4108
BC Design=,, 0 ,, 0 ,,,,,,
BC HTab HWMax=446
BC Use User HTab Curves=0
BC User HTab FreeFlow(D)= 0

Type RM Length L Ch R = 1 ,43008   ,106,106,106
BEGIN DESCRIPTION:
This cross section corresponds to cross section 42984 of the non-georeferenced CDC model which was the source of this model.
-----------------------------------
CDC DAL071508-1 California Crossing
Cross-section 42984 - 43026
-----------------------------------
Cross-section was imported from Geopak
END DESCRIPTION:
XS GIS Cut Line= 6
2454006.047400837003304.068934892453987.987069527003270.23829389
2451773.359609017001900.510062222451355.190169757001897.37391363
2451264.302884347001881.240415722450992.833939087001679.36352289
#Sta/Elev= 30
  1007.8     446    1082     428  1151.9     428  1197.3     434  1225.2     434
    1370     432  1402.3     426    2200   422.4    2680   421.1 2851.44  418.49
 3047.67   417.7 3312.26     420 3449.05  417.81 3625.17  418.22 3834.86   423.6
 3867.21     417 3897.69  416.17 3915.39     406 3953.03  394.95 4009.07  399.68
 4026.88     406 4056.57   423.7 4069.38  426.37 4199.62  427.66 4227.09     416
 4301.84  414.18 4325.73     415 4347.02     419 4373.27  428.44    4500  431.69
#Mann= 6 ,-1,0
  1007.8     .07       0    2200     .08       0 2851.44     .15       0
 3834.86    .055       0 4056.57     .08       0 4199.62    .035       0
#XS Ineff= 2 , 0
       0    1950     450               0
Permanent Ineff=
       F       F
Bank Sta=3834.86,4056.57
XS Rating Curve= 0 ,0
Exp/Cntr=0.5,0.3