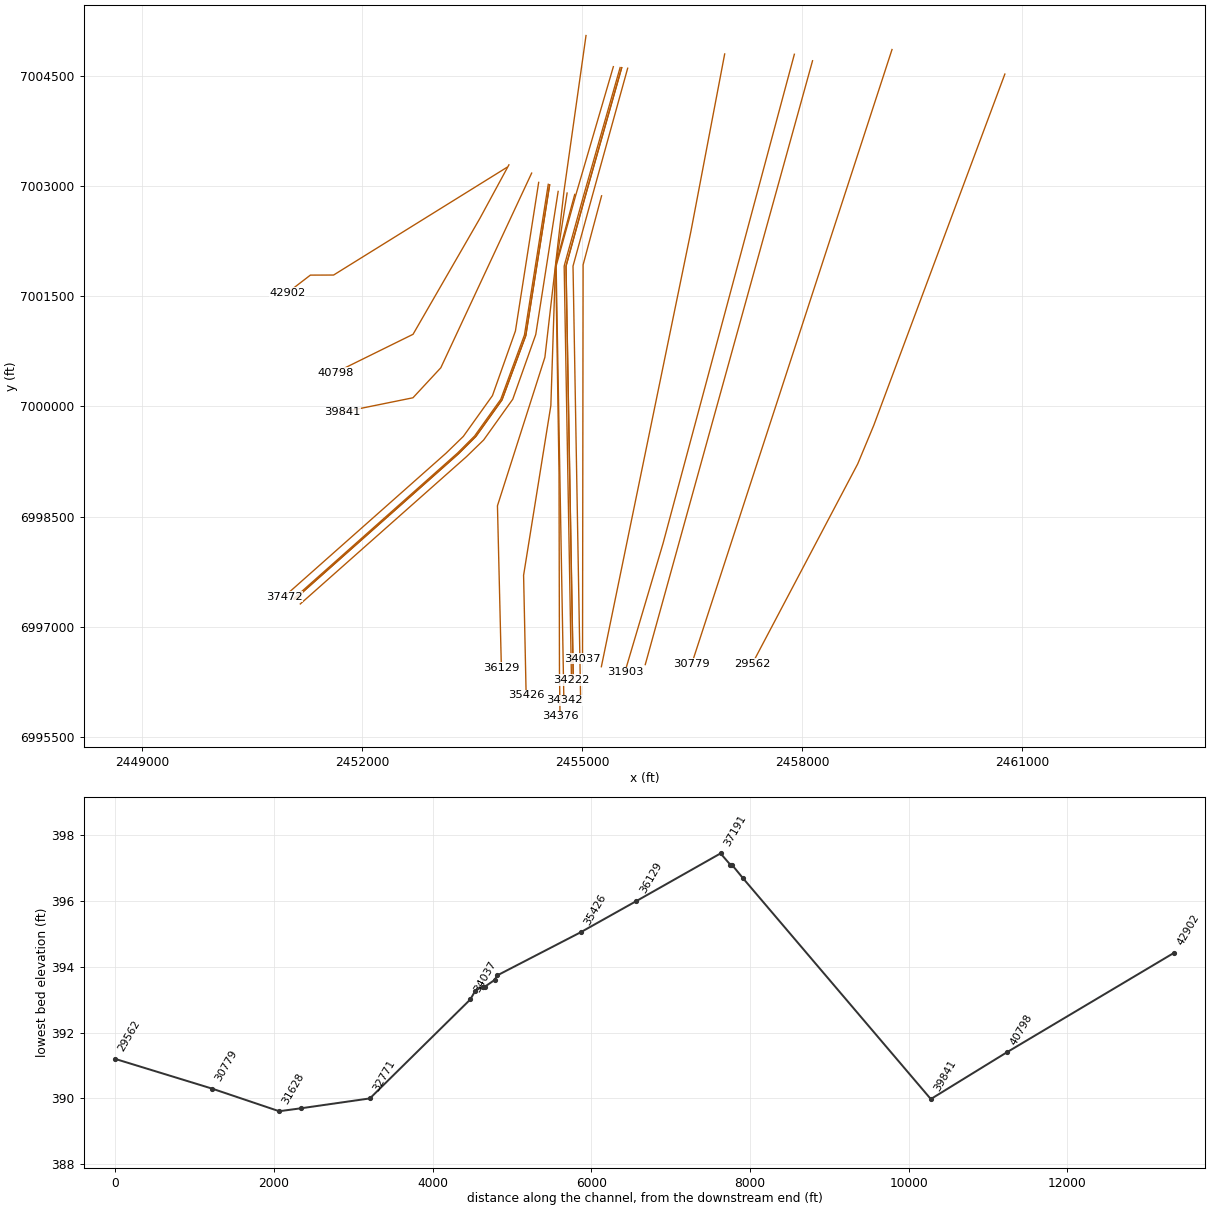
HEC-RAS study CDC_Consolidated_Model.prj: Upper Trinity CDC Consolidated Model

--- CDC_Consolidated_Model.g04 (geometry) --- (continued)

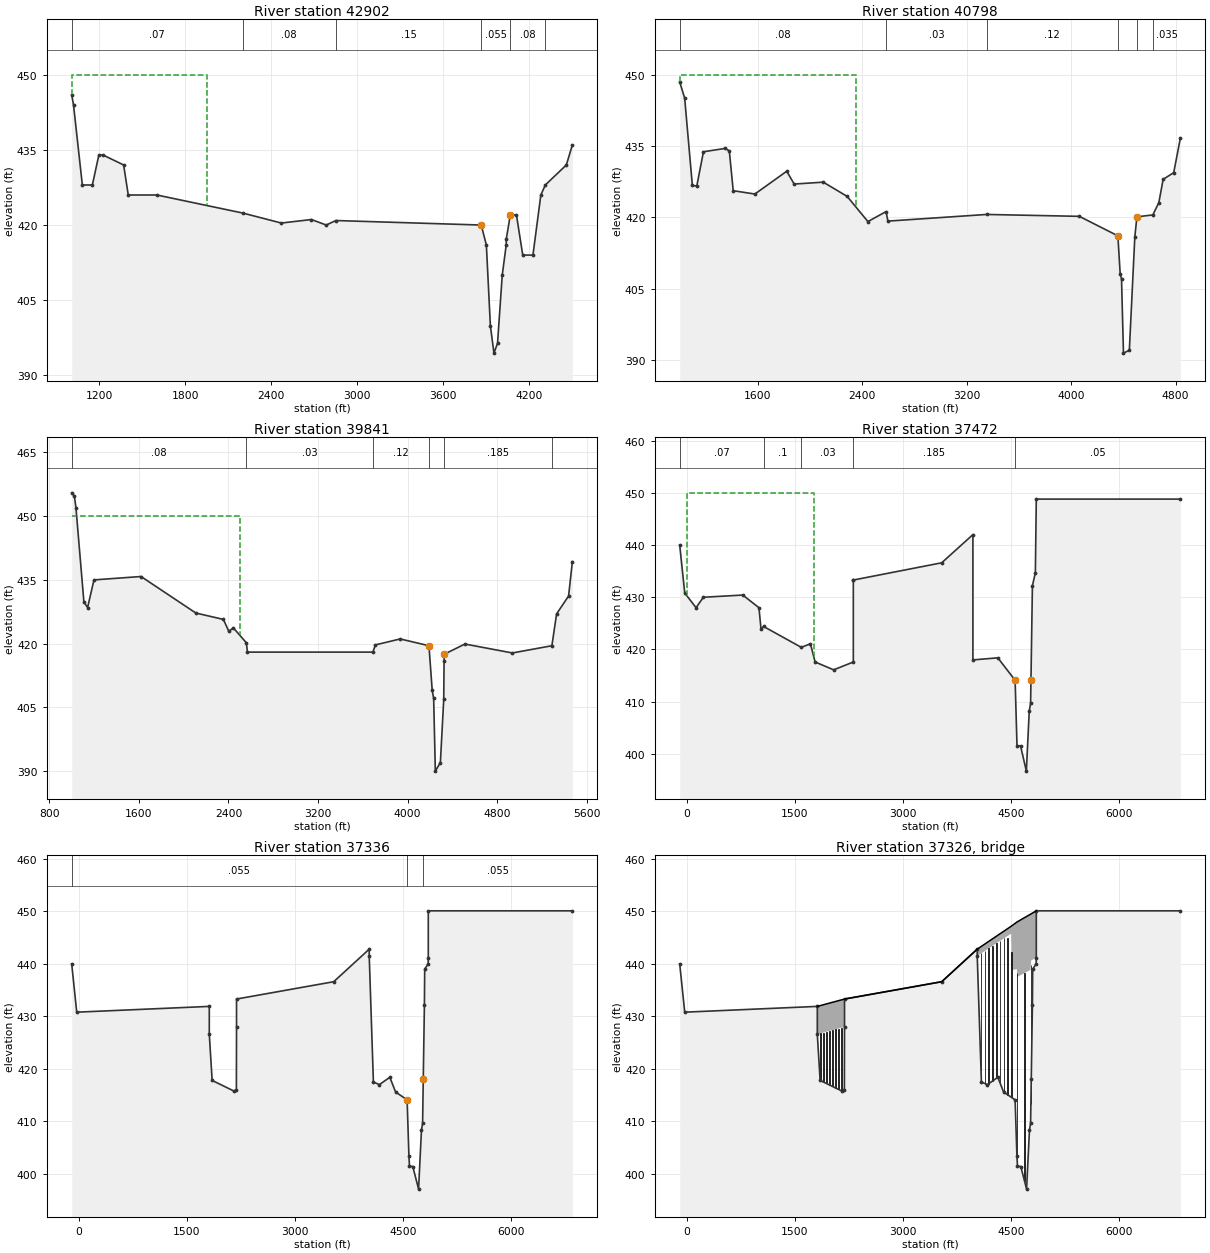
Type RM Length L Ch R = 1 ,42902   ,796,2104,1343
BEGIN DESCRIPTION:
This cross section corresponds to cross section 42882 of the non-georeferenced CDC model which was the source of this model.
END DESCRIPTION:
XS GIS Cut Line= 4
2453974.397201667003259.504391462451611.506914357001791.61001755
2451295.09809834 7001790.61297232450982.647935847001550.47532922
#Sta/Elev= 30
  1007.8     446  1020.4     444    1082     428  1151.9     428  1197.3     434
  1225.2     434    1370     432  1402.3     426  1601.7     426    2200   422.4
    2470   420.4    2680   421.1  2783.4     420    2850   420.9  3864.3     420
  3900.1     416    3928   399.9    3953  394.42    3978   396.4  4010.8     410
  4038.4     416    4039   417.2    4067     422    4110     422  4153.8     414
    4225     414    4280     426  4311.3     428  4457.9     432    4500     436
#Mann= 6 ,-1,0
  1007.8     .07       0    2200     .08       0    2850     .15       0
  3864.3    .055       0    4067     .08       0  4311.3    .035       0
#XS Ineff= 2 , 0
       0    1950     450               0
Permanent Ineff=
       F       F
Bank Sta=3864.3,4067
XS Rating Curve= 0 ,0
Exp/Cntr=0.5,0.3

Type RM Length L Ch R = 1 ,40798   ,525,957,707
BEGIN DESCRIPTION:
This cross section corresponds to cross section 40767 of the non-georeferenced CDC model which was the source of this model.
END DESCRIPTION:
XS GIS Cut Line= 6
2454001.208171677003293.61259097 2453989.58155457003272.17201705
2453988.809902527003270.749447722453605.335931937002563.61798796
2452694.625154917000983.939060722451634.198798097000461.40992205
#Sta/Elev= 30
    1000   448.5    1038   445.1    1097   426.7    1131   426.6    1182   433.8
    1347   434.5    1380     434    1410   425.6    1576   424.9    1820   429.7
    1877     427    2100   427.4    2283   424.4    2442   419.1    2581   421.2
    2595   419.2    3352   420.6    4062   420.2    4357   416.1    4375     408
    4385   407.1    4400   391.4    4445     392    4487   415.9    4503   420.1
    4625   420.5    4671   423.1    4704     428    4785   429.4    4836   436.7
#Mann= 6 ,-1,0
    1000     .08       0    2581     .03       0    3352     .12       0
    4357    .055       0    4503    .185       0    4625    .035       0
#XS Ineff= 2 , 0
       0    2350     450               0
Permanent Ineff=
       F       F
Bank Sta=4357,4503
XS Rating Curve= 0 ,0
Exp/Cntr=0.5,0.3

Type RM Length L Ch R = 1 ,39841   ,800,2369,1649
BEGIN DESCRIPTION:
This cross section corresponds to cross section 39820 of the non-georeferenced CDC model which was the source of this model.
END DESCRIPTION:
XS GIS Cut Line= 4
 2454311.15013717003180.989128542453072.949857597000527.49017046
2452693.306916097000118.645187632451727.137916686999922.39164314
#Sta/Elev= 30
    1000   455.5    1024   454.7    1038     452    1109   429.8    1142   428.5
    1199     435    1619   435.8    2109   427.2    2355   425.7    2403   422.9
    2444   423.7    2560   420.2    2570     418    3690     418    3713   419.7
    3934   421.1    4191   419.5    4220     409    4233   407.1    4248  389.98
    4293     392    4323   406.9    4326   415.9    4328   417.5    4512   419.9
    4936   417.8    5289   419.5    5331     427    5438   431.2    5472   439.3
#Mann= 6 ,-1,0
    1000     .08       0    2560     .03       0    3690     .12       0
    4191     .05       0    4328    .185       0    5289    .035       0
#XS Ineff= 2 , 0
       0    2500     450               0
Permanent Ineff=
       F       F
Bank Sta=4191,4328
XS Rating Curve= 0 ,0
Exp/Cntr=0.5,0.3

Type RM Length L Ch R = 1 ,37472   ,136,136,136
BEGIN DESCRIPTION:
This cross section corresponds to cross section 37450 of the non-georeferenced CDC model which was the source of this model.
END DESCRIPTION:
XS GIS Cut Line= 6
2454407.025273417003054.568121552454090.067902097001029.25524305
2453776.884145267000147.81409255   2453380.139866999592.24893072
2453144.702994916999363.637183222450936.798971556997406.74613178
#Sta/Elev= 30
    -100     440     -30   430.8  127.31     428  228.07     430  775.63  430.42
    1000     428    1029   423.9    1065   424.4    1589   420.4    1714   421.1
    1780   417.6    2037   416.1    2310   417.6    2310   433.3    2311   433.3
    3537   436.6    3970     442    3970     418    4316   418.4    4556   414.1
    4582   401.6    4632   401.5    4712   396.7    4752   408.2    4771   409.7
    4776   414.1    4796   432.2    4837   434.7    4850   448.8    6850   448.8
#Mann= 5 ,-1,0
    -100     .07       0    1065      .1       0    1589     .03       0
    2311    .185       0    4556     .05       0
#XS Ineff= 2 , 0
       0    1769     450               0
Permanent Ineff=
       F       F
Bank Sta=4556,4776
XS Rating Curve= 0 ,0
Exp/Cntr=0.5,0.3

Type RM Length L Ch R = 1 ,37336   ,19,19,19
BEGIN DESCRIPTION:
This cross section corresponds to cross section 37317 of the non-georeferenced CDC model which was the source of this model.
END DESCRIPTION:
XS GIS Cut Line= 6
2454537.668712917003028.402163392454213.076186277000974.06178388
2453890.112921427000096.861438542453534.077544246999598.14196356
2453302.281091846999366.248726552451066.22281674 6997379.8996082
#Sta/Elev= 30
    -100     440     -30   430.8    1810   431.9    1810   426.6  1849.5   417.8
  2148.5   415.8    2186   415.9    2188     428    2188   433.3    3537   436.6
    4030   442.8    4030   441.5    4088   417.5    4171     417    4316   418.4
    4396   415.6    4556   414.1    4581  403.38    4589  401.49    4635   401.4
    4715   397.1    4755   408.3    4771   409.7    4780     418    4796   432.2
    4800     439    4848     440    4850   441.2    4850   450.1    6850   450.1
#Mann= 3 ,0,0
    -100    .055       0    4556     .05       0    4780    .055       0
Bank Sta=4556,4780
XS Rating Curve= 0 ,0
Exp/Cntr=0.5,0.3

Type RM Length L Ch R = 3 ,37326   ,,,
BEGIN DESCRIPTION:
Burlington Northern Railroad
END DESCRIPTION:
Node Name=BN Railroad
Bridge Culvert--1,0,-1,-1, 0
Deck Dist Width WeirC Skew NumUp NumDn MinLoCord MaxHiCord MaxSubmerge Is_Ogee
2,16,2.6,0, 47, 47, , , 0.95, 0, ,,,
    1810  1849.5  1854.5  1891.5  1896.5  1933.5  1938.5  1975.5  1980.5  2017.5
  2022.5  2059.5  2064.5  2101.5  2106.5  2143.5  2148.5    2188    2188    3537
    4030    4030    4079    4087    4132    4140    4185    4193    4238    4246
    4291    4299    4344    4352    4397    4405    4450    4458    4501    4509
    4581    4589    4681    4689    4771    4779    4850
   431.9  432.05  432.06   432.2  432.22  432.36  432.38  432.51  432.53  432.67
  432.69  432.82  432.84  432.98     433  433.14  433.15   433.3   433.3   436.6
   442.8   442.8  443.25  443.33  443.74  443.82  444.24  444.31  444.73   444.8
  445.22  445.29  445.71  445.78   446.2  446.27  446.69  446.76  447.16  447.24
  447.96  448.02  448.76  448.82  449.47  449.53   450.1
   426.6  426.75  426.76   426.9  426.92  427.06  427.08  427.21  427.23  427.37
  427.39  427.52  427.54  427.68   427.7  427.84  427.85     428   433.3   436.6
   442.8   441.5  441.94  442.02  442.42   442.5   442.9  442.98  443.38  443.46
  443.86  443.94  444.34  444.41  444.82  444.89   445.3  445.37  445.76  438.81
  438.99  437.53  438.21  438.26  438.87  440.63   441.2
    1810  1849.5  1854.5  1891.5  1896.5  1933.5  1938.5  1975.5  1980.5  2017.5
  2022.5  2059.5  2064.5  2101.5  2106.5  2143.5  2148.5    2188    2188    3537
    4030    4030    4079    4087    4132    4140    4185    4193    4238    4246
    4291    4299    4344    4352    4397    4405    4450    4458    4501    4509
    4581    4589    4681    4689    4771    4779    4850
   431.9  432.05  432.06   432.2  432.22  432.36  432.38  432.51  432.53  432.67
  432.69  432.82  432.84  432.98     433  433.14  433.15   433.3   433.3   436.6
   442.8   442.8  443.25  443.33  443.74  443.82  444.24  444.31  444.73   444.8
  445.22  445.29  445.71  445.78   446.2  446.27  446.69  446.76  447.16  447.24
  447.96  448.02  448.76  448.82  449.47  449.53   450.1
   426.6  426.75  426.76   426.9  426.92  427.06  427.08  427.21  427.23  427.37
  427.39  427.52  427.54  427.68   427.7  427.84  427.85     428   433.3   436.6
   442.8   441.5  441.94  442.02  442.42   442.5   442.9  442.98  443.38  443.46
  443.86  443.94  444.34  444.41  444.82  444.89   445.3  445.37  445.76  438.81
  438.99  437.53  438.21  438.26  438.87  440.63   441.2
Pier Skew, UpSta & Num, DnSta & Num=  ,1852, 2 ,1852, 2 , 0 , 0 , 0 ,,
       5       5
     415     430
       5       5
     415     430
Pier Skew, UpSta & Num, DnSta & Num=  ,1894, 2 ,1894, 2 , 0 , 0 , 0 ,,
       5       5
     415     430
       5       5
     415     430
Pier Skew, UpSta & Num, DnSta & Num=  ,1936, 2 ,1936, 2 , 0 , 0 , 0 ,,
       5       5
     415     430
       5       5
     415     430
Pier Skew, UpSta & Num, DnSta & Num=  ,1978, 2 ,1978, 2 , 0 , 0 , 0 ,,
       5       5
     415     430
       5       5
     415     430
Pier Skew, UpSta & Num, DnSta & Num=  ,2020, 2 ,2020, 2 , 0 , 0 , 0 ,,
       5       5
     415     430
       5       5
     415     430
Pier Skew, UpSta & Num, DnSta & Num=  ,2062, 2 ,2062, 2 , 0 , 0 , 0 ,,
       5       5
     415     430
       5       5
     415     430
Pier Skew, UpSta & Num, DnSta & Num=  ,2104, 2 ,2104, 2 , 0 , 0 , 0 ,,
       5       5
     415     430
       5       5
     415     430
Pier Skew, UpSta & Num, DnSta & Num=  ,2146, 2 ,2146, 2 , 0 , 0 , 0 ,,
       5       5
     415     430
       5       5
     415     430
Pier Skew, UpSta & Num, DnSta & Num=  ,4083, 2 ,4083, 2 , 0 , 0 , 0 ,,
       8       8
     410     442
       8       8
     410     442
Pier Skew, UpSta & Num, DnSta & Num=  ,4136, 2 ,4136, 2 , 0 , 0 , 0 ,,
       8       8
     410     443
       8       8
     410     443
Pier Skew, UpSta & Num, DnSta & Num=  ,4189, 2 ,4189, 2 , 0 , 0 , 0 ,,
       8       8
     410     444
       8       8
     410     444
Pier Skew, UpSta & Num, DnSta & Num=  ,4242, 2 ,4242, 2 , 0 , 0 , 0 ,,
       8       8
     410     444
       8       8
     410     444
Pier Skew, UpSta & Num, DnSta & Num=  ,4295, 2 ,4295, 2 , 0 , 0 , 0 ,,
       8       8
     410     444
       8       8
     410     444
Pier Skew, UpSta & Num, DnSta & Num=  ,4348, 2 ,4348, 2 , 0 , 0 , 0 ,,
       8       8
     410     445
       8       8
     410     445
Pier Skew, UpSta & Num, DnSta & Num=  ,4401, 2 ,4401, 2 , 0 , 0 , 0 ,,
       8       8
     410     445
       8       8
     410     445
Pier Skew, UpSta & Num, DnSta & Num=  ,4454, 2 ,4454, 2 , 0 , 0 , 0 ,,
       8       8
     410     445
       8       8
     410     445
Pier Skew, UpSta & Num, DnSta & Num=  ,4505, 2 ,4505, 2 , 0 , 0 , 0 ,,
       8       8
     390     446
       8       8
     390     446
Pier Skew, UpSta & Num, DnSta & Num=  ,4585, 2 ,4585, 2 , 0 , 0 , 0 ,,
       8       8
     390     446
       8       8
     390     446
Pier Skew, UpSta & Num, DnSta & Num=  ,4685, 2 ,4685, 2 , 0 , 0 , 0 ,,
       8       8
     390     446
       8       8
     390     446
Pier Skew, UpSta & Num, DnSta & Num=  ,4775, 2 ,4775, 2 , 0 , 0 , 0 ,,
       8       8
     390     446
       8       8
     390     446
BR Coef= 1 , 0 , 0 ,1.05, 0 ,,,0.8,-1,0.5,1,
WSPro=,,,, 1 ,,,, 0 ,,,, 0 ,,,,-1 ,-1 ,-1 , 0 , 0 , 0 , 0 , 0
BC Design=,, 0 ,, 0 ,,,,,,
BC HTab HWMax=450.1
BC Use User HTab Curves=0
BC User HTab FreeFlow(D)= 0

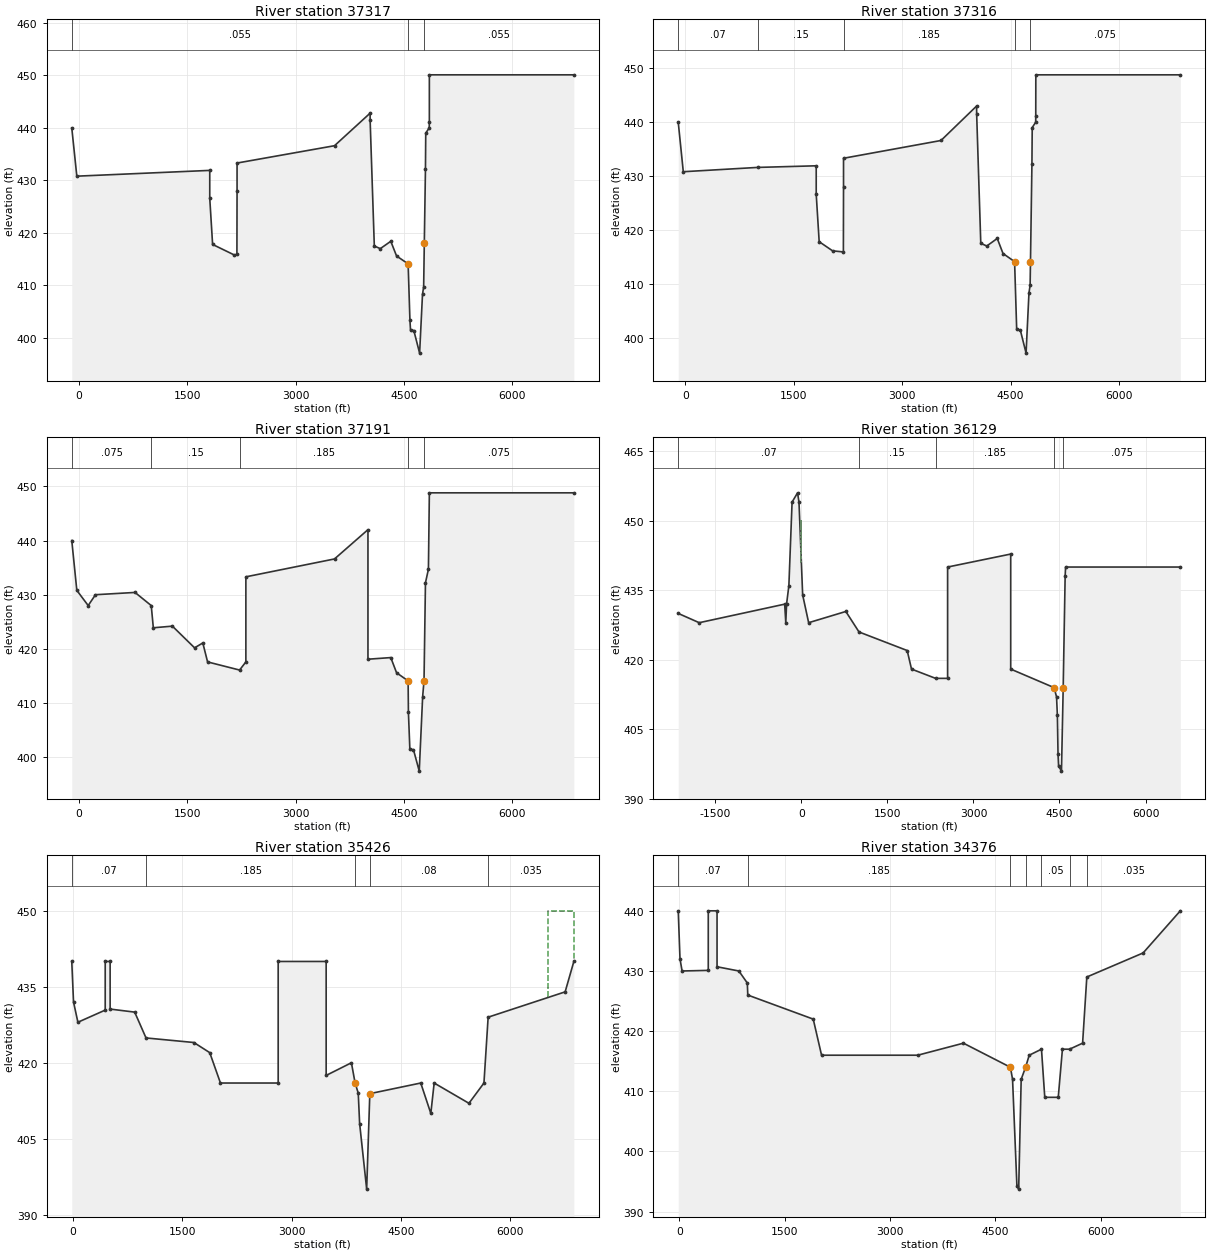
Type RM Length L Ch R = 1 ,37317   ,1,1,1
BEGIN DESCRIPTION:
This cross section corresponds to cross section 37298 of the non-georeferenced CDC model which was the source of this model.
END DESCRIPTION:
XS GIS Cut Line= 6
 2454555.66933317003020.430066472454230.642752177000966.15300705
2453906.289070167000089.583565972453549.882630776999591.12885422
2453317.539919596999359.582073212451081.265758266997373.63392849
#Sta/Elev= 30
    -100     440     -30   430.8    1810   431.9    1810   426.6  1849.5   417.8
  2148.5   415.8    2186   415.9    2188     428    2188   433.3    3537   436.6
    4030   442.8    4030   441.5    4088   417.5    4171     417    4316   418.4
    4396   415.6    4556   414.1    4581  403.38    4589  401.49    4635   401.4
    4715   397.1    4755   408.3    4771   409.7    4780     418    4796   432.2
    4800     439    4848     440    4850   441.2    4850   450.1    6850   450.1
#Mann= 3 ,0,0
    -100    .055       0    4556     .05       0    4780    .055       0
Bank Sta=4556,4780
XS Rating Curve= 0 ,0
Exp/Cntr=0.5,0.3

Type RM Length L Ch R = 1 ,37316   ,98,125,98
BEGIN DESCRIPTION:
This cross section corresponds to cross section 37297 of the non-georeferenced CDC model which was the source of this model.
END DESCRIPTION:
XS GIS Cut Line= 6
2454556.616837777003020.010447892454231.56729099 7000965.7366693
2453907.140446427000089.20036463  2453550.7143226999590.75943239
2453318.336834016999359.225118552451082.057928556997373.30469787
#Sta/Elev= 30
    -100     440     -30   430.8    1000   431.6    1810   431.9    1810   426.6
    1851   417.8    2037   416.1    2186   415.9    2188     428    2188   433.3
    3537   436.6    4030     443    4031   441.5    4088   417.5    4171     417
    4316   418.4    4396   415.6    4556   414.1    4585   401.5    4635   401.4
    4715   397.1    4755   408.3    4771   409.7    4776   414.1    4796   432.2
    4800     439    4848     440    4849   441.2    4850   448.8    6850   448.8
#Mann= 5 ,-1,0
    -100     .07       0    1000     .15       0    2188    .185       0
    4556     .05       0    4776    .075       0
Bank Sta=4556,4776
XS Rating Curve= 0 ,0
Exp/Cntr=0.3,0.1

Type RM Length L Ch R = 1 ,37191   ,600,1062,1150
BEGIN DESCRIPTION:
This cross section corresponds to cross section 37169 of the non-georeferenced CDC model which was the source of this model.
END DESCRIPTION:
XS GIS Cut Line= 6
2454672.473233347002931.723879052454367.111967417000980.50894947
2454053.927882497000099.068127052453657.183925336999543.50296521
2453421.747060276999314.891217722451157.647179466997308.33043539
#Sta/Elev= 30
    -100     440     -30   430.8  127.31     428  228.07     430  775.63  430.42
    1000     428    1029   423.9    1293   424.2    1600   420.2    1714   421.1
    1780   417.6    2223   416.1    2310   417.6    2310   433.3    3537   436.6
    4000     442    4000   418.1    4316   418.4    4396   415.6    4556   414.1
    4560   408.3    4580   401.5    4630   401.4    4710  397.45    4757   411.2
    4776   414.1    4796   432.2    4837   434.7    4850   448.8    6850   448.8
#Mann= 5 ,-1,0
    -100    .075       0    1000     .15       0    2223    .185       0
    4556     .05       0    4776    .075       0
Bank Sta=4556,4776
XS Rating Curve= 0 ,0
Exp/Cntr=0.3,0.1

Type RM Length L Ch R = 1 ,36129   ,438,703,547
BEGIN DESCRIPTION:
This cross section corresponds to cross section 36107 of the non-georeferenced CDC model which was the source of this model.
END DESCRIPTION:
XS GIS Cut Line= 6
2455052.236909517005056.261624722454752.938951677002941.94269063
2454491.786914917000670.694936542453845.071016766998646.27214813
2453850.06280467 6998440.25549982453898.508629526996440.84233538
#Sta/Elev= 30
 -2146.1     430 -1780.4     428  -290.3     432  -271.1     428  -257.6     432
  -217.2     436  -161.4     454   -66.1     456     -41     454   22.95     434
  127.31     428  775.63  430.42  1005.5     426  1845.3     422  1920.6     418
  2340.7     416    2550     416    2550     440    3650   442.8    3650     418
  4406.9     414  4449.1     412  4463.7     408    4475   399.6    4485   397.1
    4535     396  4565.1     414    4599     438  4606.8     440  6606.8     440
#Mann= 5 ,-1,0
 -2146.1     .07       0  1005.5     .15       0  2340.7    .185       0
  4406.9     .05       0  4565.1    .075       0
#XS Ineff= 2 , 0
       0    1.03     450               0
Permanent Ineff=
       F       F
Bank Sta=4406.9,4565.1
XS Rating Curve= 0 ,0
Exp/Cntr=0.3,0.1

Type RM Length L Ch R = 1 ,35426   ,314,1050,195
BEGIN DESCRIPTION:
This cross section corresponds to cross section 35400 of the non-georeferenced CDC model which was the source of this model.
STA 354+00  New X-section
-----------------------------------------------
CDC IRV082109-1 NORTHWEST LEVEE SEEPAGE CONTROL
CROSS-SECTION 13293 - 55400
UPSTREAM END
-----------------------------------------------
END DESCRIPTION:
XS GIS Cut Line= 6
 2454794.62948517002909.716705222454637.936885097001911.17605138
2454633.30369225 7001849.90616082454572.889114927000012.10799913
2454201.420369686997699.429553632454236.189985196996065.33177197
#Sta/Elev= 30
   -18.7     440     5.4     432    65.4     428   440.1   430.4   440.1     440
   507.6     440   507.6   430.6   844.5     430    1000   424.9  1656.8     424
    1874     422  2021.1     416    2813     416    2813     440  3471.3     440
  3471.3   417.5  3817.6     420  3868.4     416  3911.5     414  3930.4     408
    4027  395.05  4070.2   413.9  4768.9     416  4907.2     410  4952.9     416
  5430.1     412    5636     416 5693.44     429 6749.83     434 6869.23     440
#Mann= 5 ,-1,0
   -18.7     .07       0    1000    .185       0  3868.4     .05       0
  4070.2     .08       0 5693.44    .035       0
#XS Ineff= 2 , 0
       0                    6520       0     450
Permanent Ineff=
       F       F
Bank Sta=3868.4,4070.2
XS Rating Curve= 0 ,0
Exp/Cntr=0.3,0.1

Type RM Length L Ch R = 1 ,34376   ,15,34,43
BEGIN DESCRIPTION:
This cross section corresponds to cross section 34430 of the non-georeferenced CDC model which was the source of this model.
STA 344+30  New X-section
END DESCRIPTION:
XS GIS Cut Line= 6
    2454898.32587002890.412609962454651.234102587001975.48563404
2454640.112733757001901.505467042454684.47156891 6999091.0475053
2454690.305874826996401.708067722454698.22777501 6995778.5521618
#Sta/Elev= 30
   -14.1     440    11.1     432    40.9     430   413.3   430.1   413.3     440
   538.3     440   538.3   430.7   848.6     430     969     428   975.7     426
  1907.1     422  2025.8     416  3394.6     416  4044.7     418  4713.2     414
 4743.91     412    4806  394.24    4831  393.74  4866.7     412  4929.3     414
    4981     416 5155.58     417 5202.36     409 5394.21     409 5453.74     417
  5554.8     417  5740.8     418  5800.8     429 6602.11     433 7131.39     440
#Mann= 7 ,-1,0
   -14.1     .07       0   975.7    .185       0  4713.2     .05       0
  4929.3     .08       0 5155.58     .05       0  5554.8     .08       0
  5800.8    .035       0
Bank Sta=4713.2,4929.3
XS Rating Curve= 0 ,0
Exp/Cntr=0.3,0.1

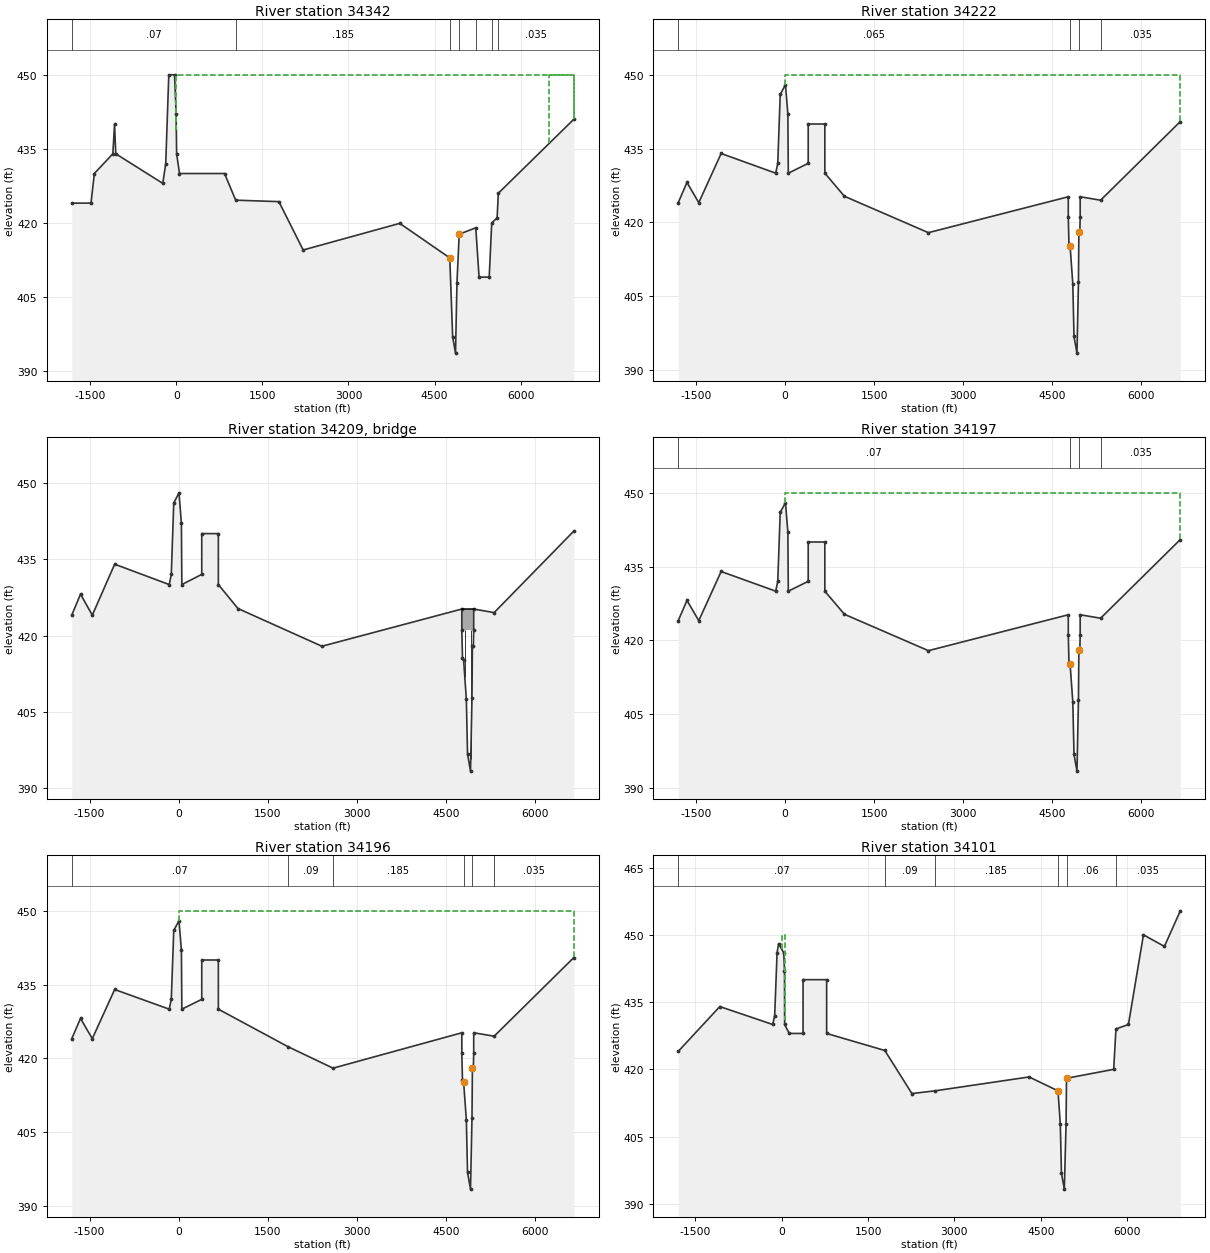
Type RM Length L Ch R = 1 ,34342   ,120,120,120
BEGIN DESCRIPTION:
This cross section corresponds to cross section 34320 of the non-georeferenced CDC model which was the source of this model.
END DESCRIPTION:
XS GIS Cut Line= 4
2455424.882489687004631.867788462454908.776566517002867.75747155
2454645.024141257001914.231163382454750.396633926995993.25678489
#Sta/Elev= 30
 -1822.3     424 -1486.8     424 -1429.2     430 -1106.3     434 -1077.2     440
 -1055.5     434    -236     428  -184.9     432  -131.6     450   -30.8     450
    -3.4     442       5     434      55     430     840     430    1034   424.6
    1787   424.3    2210   414.5    3893   419.9    4765   412.9    4815   396.9
    4865   393.6    4890   407.8    4929   417.7    5218     419 5275.34     409
    5452     409    5496     420    5590     421  5610.7     426    6927     441
#Mann= 7 ,-1,0
 -1822.3     .07       0    1034    .185       0    4765     .05       0
    4929     .08       0    5218     .05       0    5496     .08       0
  5610.7    .035       0
#XS Ineff= 2 , 0
       0       0     450    6500       0     450
Permanent Ineff=
       F       F
Bank Sta=4765,4929
XS Rating Curve= 0 ,0
Exp/Cntr=0.3,0.1

Type RM Length L Ch R = 1 ,34222   ,25,25,25
BEGIN DESCRIPTION:
This cross section corresponds to cross section 34205 of the non-georeferenced CDC model which was the source of this model.
END DESCRIPTION:
XS GIS Cut Line= 5
2455517.159536097004620.04596172 2455013.12117417002852.50717397
2454756.784416417001922.592695222454754.500300267001905.58682372
2454854.076872776996271.02460206
#Sta/Elev= 30
 -1798.8     424 -1651.7  428.12   -1453     424 -1076.4     434  -157.4     430
  -122.8     432   -81.4     446     6.8     448    47.5     442      55     430
     390     432     390     440     670     440     670     430    1000   425.3
    2414   417.9    4770   425.2    4770     421    4781   415.6    4800   415.2
    4846   407.5    4866   396.8    4916   393.4    4941   407.8    4948     418
    4964     418    4970     421    4970   425.2    5314   424.5  6656.4   440.5
#Mann= 4 ,-1,0
 -1798.8    .065       0    4800     .05       0    4948    .065       0
    5314    .035       0
#XS Ineff= 2 , 0
       0       0     450               0
Permanent Ineff=
       F       F
Bank Sta=4800,4948
XS Rating Curve= 0 ,0
Exp/Cntr=0.5,0.3

Type RM Length L Ch R = 3 ,34209   ,,,
BEGIN DESCRIPTION:
Wildwood Drive
END DESCRIPTION:
Node Name=Wildwood Drive
Bridge Culvert--1,0,-1,-1, 0
Deck Dist Width WeirC Skew NumUp NumDn MinLoCord MaxHiCord MaxSubmerge Is_Ogee
2,22,2.6,0, 6, 6, , , 0.95, 0, ,,,
    4770  4818.5  4821.5  4918.5  4921.5    4970
   425.2   425.2   425.2   425.2   425.2   425.2
     421     421     421     421     421     421
    4770  4818.5  4821.5  4918.5  4921.5    4970
   425.2   425.2   425.2   425.2   425.2   425.2
     421     421     421     421     421     421
Pier Skew, UpSta & Num, DnSta & Num=  ,4820, 2 ,4820, 2 , 0 , 0 , 0 ,,
       3       3
     390     424
       3       3
     390     424
Pier Skew, UpSta & Num, DnSta & Num=  ,4920, 2 ,4920, 2 , 0 , 0 , 0 ,,
       3       3
     390     424
       3       3
     390     424
BR Coef= 1 , 0 , 0 ,1.05, 0 ,,,0.8,-1,0.5,1,
WSPro=,,,, 1 ,,,, 0 ,,,, 0 ,,,,-1 ,-1 ,-1 , 0 , 0 , 0 , 0 , 0
BC Design=,, 0 ,, 0 ,,,,,,
BC HTab HWMax=446
BC Use User HTab Curves=0
BC User HTab FreeFlow(D)= 0

Type RM Length L Ch R = 1 ,34197   ,1,1,1
BEGIN DESCRIPTION:
This cross section corresponds to cross section 34179 of the non-georeferenced CDC model which was the source of this model.
END DESCRIPTION:
XS GIS Cut Line= 5
2455538.244467687004618.132579712455037.095535587002850.36938296
2454781.011074017001920.719011312454779.250906917001903.66359922
2454878.685747416996268.18996204
#Sta/Elev= 30
 -1798.8     424 -1651.7  428.12   -1453     424 -1076.4     434  -157.4     430
  -122.8     432   -81.4     446     6.8     448    47.5     442      55     430
     390     432     390     440     670     440     670     430    1000   425.3
    2414   417.9    4770   425.2    4770     421    4781   415.6    4800   415.2
    4846   407.5    4866   396.8    4916   393.4    4941   407.8    4948     418
    4964     418    4970     421    4970   425.2    5314   424.5  6656.4   440.5
#Mann= 4 ,-1,0
 -1798.8     .07       0    4800     .05       0    4948    .065       0
    5314    .035       0
#XS Ineff= 2 , 0
       0       0     450               0
Permanent Ineff=
       F       F
Bank Sta=4800,4948
XS Rating Curve= 0 ,0
Exp/Cntr=0.5,0.3

Type RM Length L Ch R = 1 ,34196   ,95,95,95
BEGIN DESCRIPTION:
This cross section corresponds to cross section 34178 of the non-georeferenced CDC model which was the source of this model.
END DESCRIPTION:
XS GIS Cut Line= 5
 2455539.05516167004618.059089052455038.017777837002850.28736213
2454781.943158757001920.648473382454780.203004757001903.58978046
2454879.631939776996268.08169454
#Sta/Elev= 30
 -1798.8     424 -1651.7  428.12   -1453     424 -1076.4     434  -157.4     430
  -122.8     432   -81.4     446     6.8     448    47.5     442      55     430
     390     432     390     440     670     440     670     430    1838   422.4
    2601     418    4770   425.2    4770     421    4781   415.6    4800   415.2
    4846   407.5    4866   396.8    4916   393.4    4941   407.8    4948     418
    4964     418    4970     421    4970   425.2    5314   424.5  6656.4   440.5
#Mann= 6 ,-1,0
 -1798.8     .07       0    1838     .09       0    2601    .185       0
    4800     .05       0    4948    .075       0    5314    .035       0
#XS Ineff= 2 , 0
       0       0     450               0
Permanent Ineff=
       F       F
Bank Sta=4800,4948
XS Rating Curve= 0 ,0
Exp/Cntr=0.3,0.1

Type RM Length L Ch R = 1 ,34101   ,64,64,64
BEGIN DESCRIPTION:
This cross section corresponds to cross section 34078 of the non-georeferenced CDC model which was the source of this model.
Right Overbank updated with 2007 levee topo.
END DESCRIPTION:
XS GIS Cut Line= 4
2455620.150471847004610.700507972455127.401129257002831.86515488
2454875.096843847001913.347963052454978.987712176995988.55961581
#Sta/Elev= 30
 -1798.8     424 -1076.4     434  -157.4     430  -122.8     432   -81.4     446
   -54.9     448    34.2     446    47.5     442      50     430     130     428
     370     428     370     440     780     440     780     428    1791   424.2
    2261   414.6    2661   415.2    4298   418.3    4800   415.2    4840   407.8
    4860   396.8    4910  393.28    4940   407.8    4948     418  5767.6     420
    5807     429  6023.7     430 6284.87     450 6649.01  447.41 6925.26  455.35
#Mann= 6 ,-1,0
 -1798.8     .07       0    1791     .09       0    2661    .185       0
    4800     .05       0    4948     .06       0    5807    .035       0
#XS Ineff= 2 , 0
       0      50     450               0
Permanent Ineff=
       F       F
Bank Sta=4800,4948
XS Rating Curve= 0 ,0
Exp/Cntr=0.3,0.1

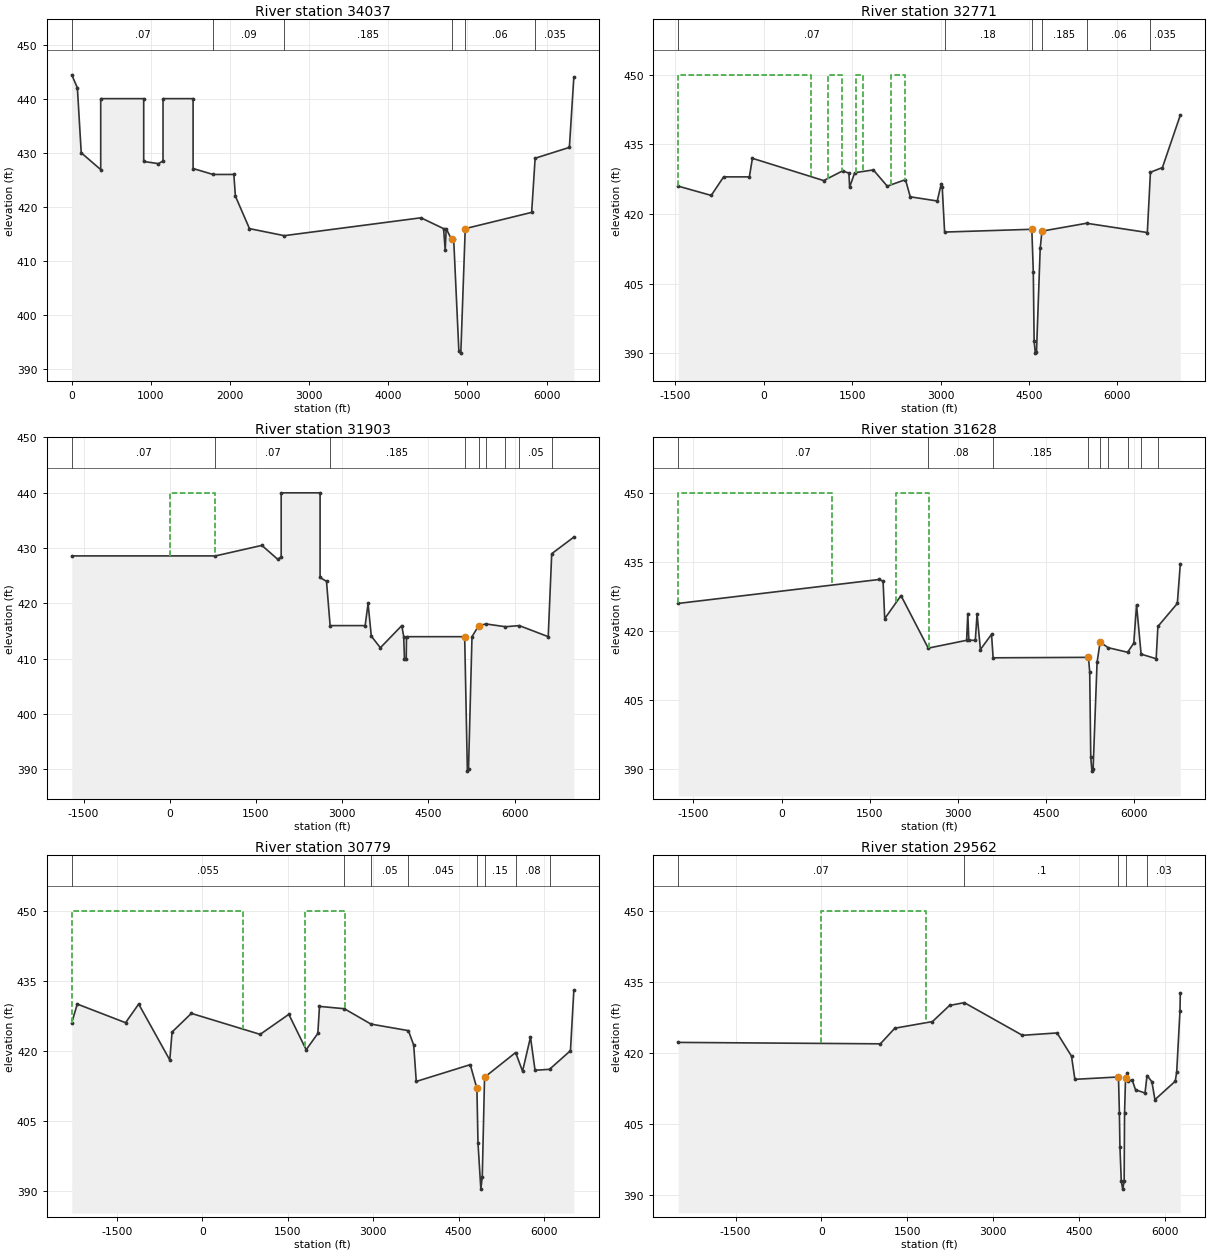
Type RM Length L Ch R = 1 ,34037   ,752,1266,533
BEGIN DESCRIPTION:
This cross section corresponds to cross section 33960 of the non-georeferenced CDC model which was the source of this model.
STA 339+60  New X-section
END DESCRIPTION:
XS GIS Cut Line= 3
2455264.355907837002871.339485382455012.740597437001931.38795322
2455004.753408676996558.94036479
#Sta/Elev= 30
       0   444.4    70.9     442   119.6     430   365.8   426.9   365.8     440
   909.1     440   909.1   428.4  1096.1     428  1153.1   428.5  1153.1     440
  1533.4     440  1533.4   427.1    1786     426  2048.5     426    2068     422
  2246.1     416  2686.1   414.7  4413.4     418  4699.3     416  4719.6     412
  4732.3     416  4800.2     414  4827.1     414    4892  393.47    4917  393.01
  4972.7     416 5812.31     419 5856.16     429  6289.1     431  6345.5     444
#Mann= 6 ,-1,0
       0     .07       0    1786     .09       0  2686.1    .185       0
  4800.2     .05       0  4972.7     .06       0 5856.16    .035       0
Bank Sta=4800.2,4972.7
XS Rating Curve= 0 ,0
Exp/Cntr=0.3,0.1

Type RM Length L Ch R = 1 ,32771   ,620,868,430
BEGIN DESCRIPTION:
This cross section corresponds to cross section 32748 of the non-georeferenced CDC model which was the source of this model.
Right Overbank updated with 2007 levee topo.
END DESCRIPTION:
XS GIS Cut Line= 3
2456942.421121277004805.130893382456482.853142777002390.61210038
2455261.452370356996452.72502606
#Sta/Elev= 30
 -1453.4     426  -893.5     424 -683.27     428  -246.2     428  -194.6     432
    1015   427.2    1337   429.3    1443   428.8    1455   425.8    1542   428.9
    1858   429.5    2093     426    2403   427.4    2484   423.7    2942   422.8
    3010   426.5    3026   425.9    3067   416.1    4547   416.7    4572   407.5
    4586   392.6    4606     390    4626   390.2    4689   412.6    4719   416.3
    5476     418    6507     416  6559.7     429  6762.7     430 7066.67  441.31
#Mann= 6 ,-1,0
 -1453.4     .07       0    3067     .18       0    4547     .05       0
    4719    .185       0    5476     .06       0  6559.7    .035       0
#XS Ineff= 4 ,-1
 -1453.4     800     450    1080    1320     450    1560    1680     450
    2150    2400     450
Permanent Ineff=
       F       F       F       F
Bank Sta=4547,4719
XS Rating Curve= 0 ,0
Exp/Cntr=0.3,0.1

Type RM Length L Ch R = 1 ,31903   ,275,275,275
BEGIN DESCRIPTION:
This cross section corresponds to cross section 31880 of the non-georeferenced CDC model which was the source of this model.
STA 318+80  New X-section
END DESCRIPTION:
XS GIS Cut Line= 4
2457892.258667017004800.988710142457244.051751587002386.48514013
2456102.621947836998134.777436212455581.752910856996378.02766888
#Sta/Elev= 30
 -1704.2   428.6   795.8   428.6  1603.4   430.5  1877.7     428  1938.9   428.4
  1938.9     440  2615.7     440  2615.7   424.7  2727.4     424  2790.4     416
  3399.8     416  3450.5     420  3506.7   414.1  3664.4     412  4036.6     416
    4071     414  4083.3     410  4114.3     410  4119.1     414  5131.3     414
    5178   389.7    5198   390.1  5258.5     414  5375.5     416    5502   416.3
  5840.1   415.8 6081.62     416 6584.64     414 6645.38     429  7030.4     432
#Mann= 9 ,-1,0
 -1704.2     .07       0   795.8     .07       0  2790.4    .185       0
  5131.3     .05       0  5375.5    .185       0    5502     .06       0
  5840.1      .1       0 6081.62     .05       0 6645.38    .035       0
#XS Ineff= 2 , 0
       0   795.8     440               0
Permanent Ineff=
       F       F
Bank Sta=5131.3,5375.5
XS Rating Curve= 0 ,0
Exp/Cntr=0.3,0.1

Type RM Length L Ch R = 1 ,31628   ,739,849,649
BEGIN DESCRIPTION:
This cross section corresponds to cross section 31605 of the non-georeferenced CDC model which was the source of this model.
Right Overbank updated with 2007 levee topo.
*********************************************************************
CDC Irving 050301-1 University of Dallas
Cross-section 31605 - 35400
Located in ROB.
*********************************************************************
******************************************************************
CDC Irving 012607-1 Widening of SH114
Cross-section 31605 - 35400
Located in ROB.
******************************************************************
END DESCRIPTION:
XS GIS Cut Line= 2
 2458140.08736117004712.652075722455859.869480586996481.62555879
#Sta/Elev= 30
 -1758.7     426    1661   431.2    1726   430.8    1754   422.7    2031   427.7
    2494   416.3    3147     418    3167   423.8    3185     418    3295     418
    3325   423.7    3382     416    3571   419.3    3598   414.2    5220   414.3
    5241   411.1    5259   392.6    5279  389.61    5299   390.1    5366   413.2
    5418   417.6    5555   416.4    5886   415.4    5991   417.4    6038   425.7
 6115.18     415  6371.6     414  6400.9     421 6731.81     426 6782.33   434.6
#Mann= 9 ,-1,0
 -1758.7     .07       0    2494     .08       0    3598    .185       0
    5220     .05       0    5418     .13       0    5555     .06       0
    5886     .13       0 6115.18     .05       0  6400.9     .13       0
#XS Ineff= 2 ,-1
 -1758.7     850     450    1950    2500     450
Permanent Ineff=
       F       F
Bank Sta=5220,5418
XS Rating Curve= 0 ,0
Exp/Cntr=0.3,0.1

Type RM Length L Ch R = 1 ,30779   ,1091,1217,901
BEGIN DESCRIPTION:
This cross section corresponds to cross section 30755 of the non-georeferenced CDC model which was the source of this model.
Right Overbank updated with 2007 levee topo
END DESCRIPTION:
XS GIS Cut Line= 2
2459223.183948167004865.41456546 2456492.74616766996490.03006954
#Sta/Elev= 30
 -2288.4     426 -2191.9     430 -1344.5     426 -1114.3     430  -568.7     418
  -528.6     424  -190.3     428    1017   423.5    1520   427.8    1824   420.2
    2029   423.7    2058   429.5    2494     429    2962   425.7    3618   424.3
    3711   421.2    3756   413.4    4703     417    4820   411.9    4839   400.2
    4889   390.3    4914   392.9    4954   414.3    5499   419.6    5621   415.6
    5760   422.9    5840   415.8    6094     416 6461.37     420 6520.82     433
#Mann= 8 ,-1,0
 -2288.4    .055       0    2494     .06       0    2962     .05       0
    3618    .045       0    4820     .05       0    4954     .15       0
    5499     .08       0    6094     .12       0
#XS Ineff= 2 ,-1
 -2288.4     720     450    1800    2500     450
Permanent Ineff=
       F       F
Bank Sta=4820,4954
XS Rating Curve= 0 ,0
Exp/Cntr=0.3,0.1

Type RM Length L Ch R = 1 ,29562   ,103,103,103
BEGIN DESCRIPTION:
This cross section corresponds to cross section 29539 of the non-georeferenced CDC model which was the source of this model.
Right Overbank updated with 2007 levee topo.
END DESCRIPTION:
XS GIS Cut Line= 5
2460761.552754427004531.063646032459537.779775687001251.98150364
2458974.645075176999743.070151392458755.869922166999217.50099255
2457317.215975346996490.42869081
#Sta/Elev= 30
   -2500   422.2    1028   421.9    1280   425.2    1937   426.6    2235     430
    2493   430.6    3507   423.7    4112   424.2    4364   419.3    4423   414.4
    5184   414.9    5200   407.3    5209   400.2    5233   392.9    5258   391.2
    5283   392.9    5290   407.3    5307   414.6    5339   415.8    5357     414
    5422   414.3    5481   412.2    5647   411.5    5682   415.2    5767   413.9
    5820   410.1 6174.93     414 6200.25     416 6257.05  428.77 6263.14   432.6
#Mann= 5 ,-1,0
   -2500     .07       0    2493      .1       0    5184     .05       0
    5307      .1       0    5682     .03       0
#XS Ineff= 2 , 0
       0    1820     450               0
Permanent Ineff=
       F       F
Bank Sta=5184,5307
XS Rating Curve= 0 ,0
Exp/Cntr=0.3,0.1