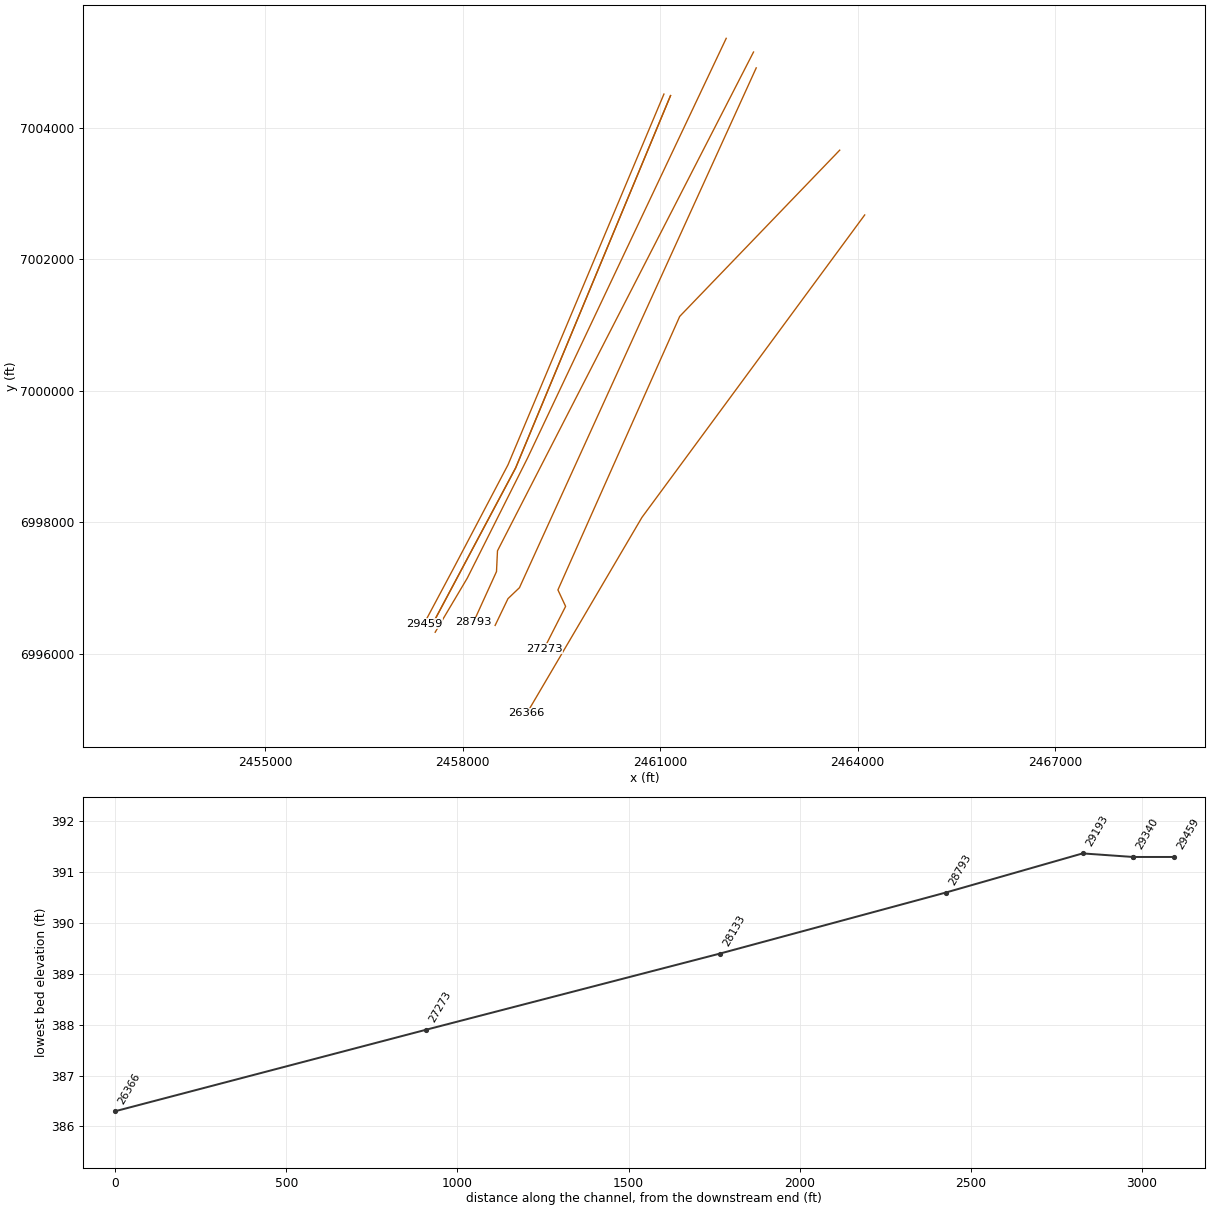
HEC-RAS study CDC_Consolidated_Model.prj: Upper Trinity CDC Consolidated Model

--- CDC_Consolidated_Model.g04 (geometry) --- (continued)

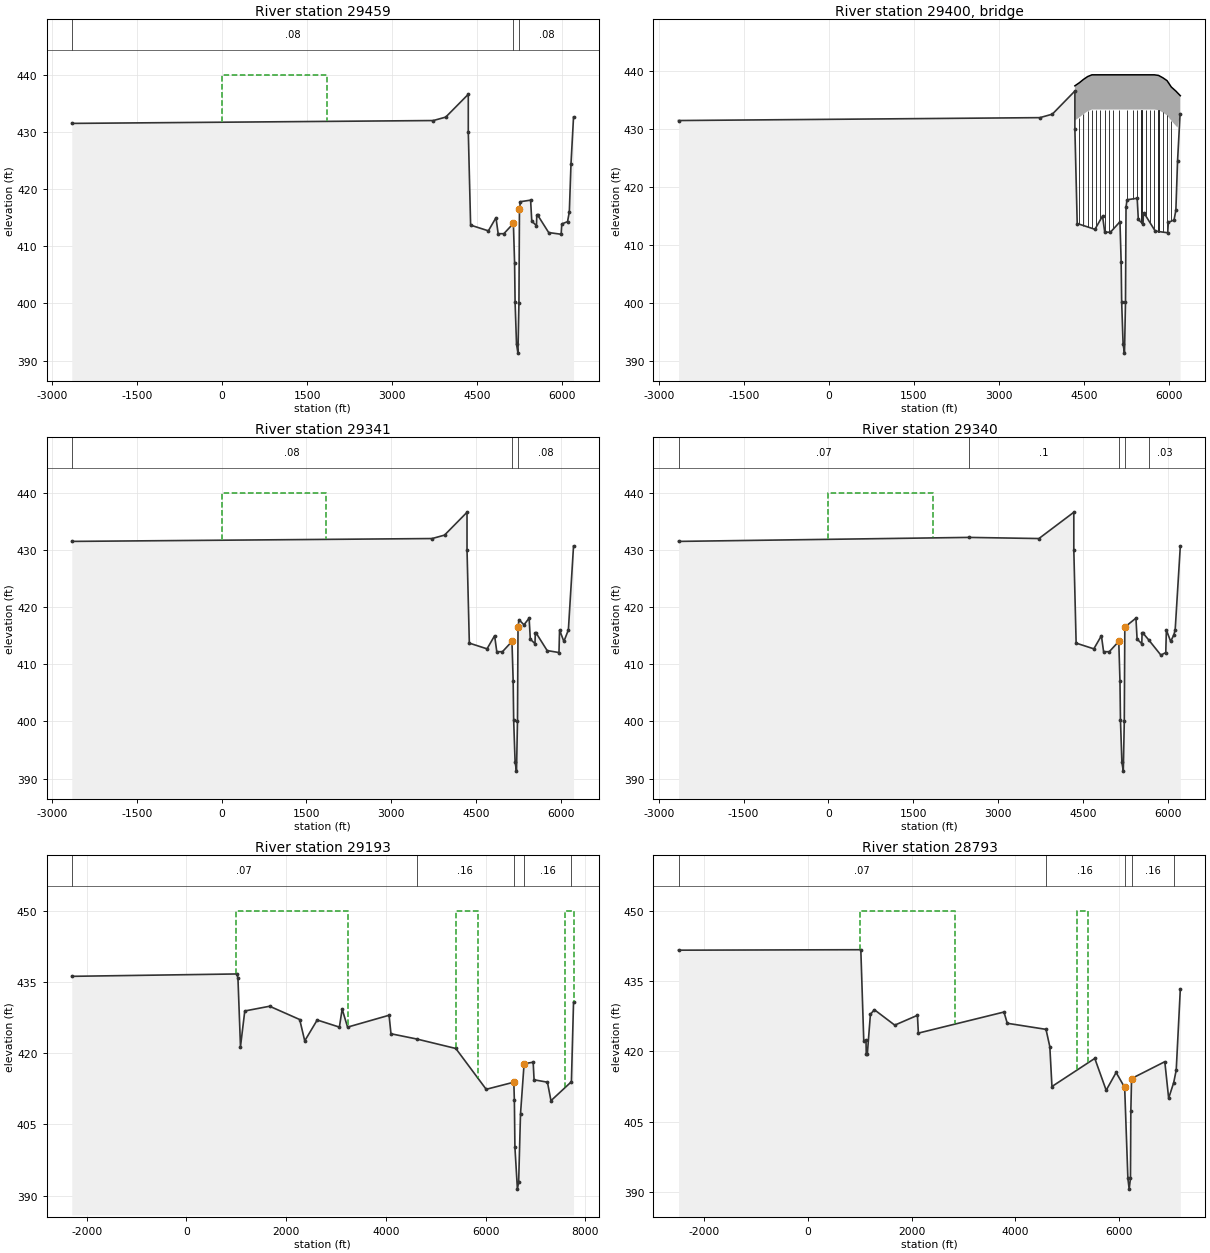
Type RM Length L Ch R = 1 ,29459   ,118,118,118
BEGIN DESCRIPTION:
This cross section corresponds to cross section 29438 of the non-georeferenced CDC model which was the source of this model.
Right Overbank updated with 2007 levee topo.
END DESCRIPTION:
XS GIS Cut Line= 5
2461057.618049797004512.107408382459313.870774697000363.69259781
2458687.587250356998873.749711542457872.600035166997323.13339022
2457413.172804426996460.78668971
#Sta/Elev= 30
   -2650   431.5    3723     432    3942   432.6    4340   436.6    4340     430
    4381   413.7    4694   412.7    4828     415  4866.5   412.2    4967   412.2
    5135     414    5156   407.1    5165   400.2    5190   392.9    5215   391.3
 5232.66  400.08    5242   416.5    5259   417.8  5438.5  418.07    5459   414.4
    5542   413.6    5547   415.4    5560   415.5    5757   412.4    5977   412.1
  5988.1   413.9 6089.21  414.31 6121.02     416 6150.63  424.47 6195.06   432.6
#Mann= 3 ,0,0
   -2650     .08       0    5135     .05       0    5242     .08       0
#XS Ineff= 2 , 0
       0    1850     440               0
Permanent Ineff=
       F       F
Bank Sta=5135,5242
XS Rating Curve= 0 ,0
Exp/Cntr=0.5,0.3

Type RM Length L Ch R = 3 ,29400   ,,,
BEGIN DESCRIPTION:
Loop 12/Walton Walker Boulevard
END DESCRIPTION:
Node Name=Loop 12
Bridge Culvert--1,0,-1,-1, 0
Deck Dist Width WeirC Skew NumUp NumDn MinLoCord MaxHiCord MaxSubmerge Is_Ogee
2,115,2.6,0, 45, 45, , , 0.95, 0, ,,,
    4340 4413.75 4416.25 4488.75 4491.25  4563.5  4566.5  4638.5  4641.5  4713.5
  4716.5  4788.5  4791.5  4863.5  4866.5  4938.5  4941.5  5013.5  5016.5  5113.5
  5116.5  5263.5  5266.5  5363.5  5366.5  5438.5  5441.5  5513.5  5516.5  5588.5
  5591.5  5663.5  5666.5 5738.75 5741.25 5813.75 5816.25 5888.75 5891.25 5963.75
 5966.25 6038.75 6041.25    6120 6199.69
   437.5     438  438.01  438.59 438.608  439.09 439.106 439.394   439.4   439.4
   439.4   439.4   439.4   439.4   439.4   439.4   439.4   439.4   439.4   439.4
   439.4   439.4   439.4   439.4   439.4   439.4   439.4   439.4   439.4   439.4
   439.4   439.4   439.4   439.4   439.4 439.302 439.293 438.907 438.892 438.408
 438.387 437.318 437.288   436.6  435.79
   431.5     432  432.01  432.59 432.608  433.09 433.106 433.394   433.4   433.4
   433.4   433.4   433.4   433.4   433.4   433.4   433.4   433.4   433.4   433.4
   433.4   433.4   433.4   433.4   433.4   433.4   433.4   433.4   433.4   433.4
   433.4   433.4   433.4   433.4   433.4 433.302 433.293 432.907 432.892 432.408
 432.387 431.521 431.491   430.6  429.79
    4340 4413.75 4416.25 4488.75 4491.25  4563.5  4566.5  4638.5  4641.5  4713.5
  4716.5  4788.5  4791.5  4863.5  4866.5  4938.5  4941.5  5013.5  5016.5  5113.5
  5116.5  5263.5  5266.5  5363.5  5366.5  5438.5  5441.5  5513.5  5516.5  5588.5
  5591.5  5663.5  5666.5 5738.75 5741.25 5813.75 5816.25 5888.75 5891.25 5963.75
 5966.25 6038.75 6041.25    6120 6225.87
   437.5     438  438.01  438.59 438.608  439.09 439.106 439.394   439.4   439.4
   439.4   439.4   439.4   439.4   439.4   439.4   439.4   439.4   439.4   439.4
   439.4   439.4   439.4   439.4   439.4   439.4   439.4   439.4   439.4   439.4
   439.4   439.4   439.4   439.4   439.4 439.302 439.293 438.907 438.892 438.408
 438.387 437.318 437.288   436.6  435.79
   431.5     432  432.01  432.59 432.608  433.09 433.106 433.394   433.4   433.4
   433.4   433.4   433.4   433.4   433.4   433.4   433.4   433.4   433.4   433.4
   433.4   433.4   433.4   433.4   433.4   433.4   433.4   433.4   433.4   433.4
   433.4   433.4   433.4   433.4   433.4 433.302 433.293 432.907 432.892 432.408
 432.387 431.521 431.491   430.6  429.79
Pier Skew, UpSta & Num, DnSta & Num=  ,4415, 2 ,4415, 2 , 0 , 0 , 0 ,,
     2.5     2.5
     390     444
     2.5     2.5
     390     444
Pier Skew, UpSta & Num, DnSta & Num=  ,4490, 2 ,4490, 2 , 0 , 0 , 0 ,,
     2.5     2.5
     390     444
     2.5     2.5
     390     444
Pier Skew, UpSta & Num, DnSta & Num=  ,4565, 2 ,4565, 2 , 0 , 0 , 0 ,,
       3       3
     390     444
       3       3
     390     444
Pier Skew, UpSta & Num, DnSta & Num=  ,4641, 2 ,4641, 2 , 0 , 0 , 0 ,,
       3       3
     390     444
       3       3
     390     444
Pier Skew, UpSta & Num, DnSta & Num=  ,4715, 2 ,4715, 2 , 0 , 0 , 0 ,,
       3       3
     390     444
       3       3
     390     444
Pier Skew, UpSta & Num, DnSta & Num=  ,4790, 2 ,4790, 2 , 0 , 0 , 0 ,,
       3       3
     390     444
       3       3
     390     444
Pier Skew, UpSta & Num, DnSta & Num=  ,4865, 2 ,4865, 2 , 0 , 0 , 0 ,,
       3       3
     390     444
       3       3
     390     444
Pier Skew, UpSta & Num, DnSta & Num=  ,4940, 2 ,4940, 2 , 0 , 0 , 0 ,,
       3       3
     390     444
       3       3
     390     444
Pier Skew, UpSta & Num, DnSta & Num=  ,5015, 2 ,5015, 2 , 0 , 0 , 0 ,,
       3       3
     390     444
       3       3
     390     444
Pier Skew, UpSta & Num, DnSta & Num=  ,5115, 2 ,5115, 2 , 0 , 0 , 0 ,,
       3       3
     390     444
       3       3
     390     444
Pier Skew, UpSta & Num, DnSta & Num=  ,5265, 2 ,5265, 2 , 0 , 0 , 0 ,,
       3       3
     390     444
       3       3
     390     444
Pier Skew, UpSta & Num, DnSta & Num=  ,5365, 2 ,5365, 2 , 0 , 0 , 0 ,,
       3       3
     390     444
       3       3
     390     444
Pier Skew, UpSta & Num, DnSta & Num=  ,5440, 2 ,5440, 2 , 0 , 0 , 0 ,,
       3       3
     390     444
       3       3
     390     444
Pier Skew, UpSta & Num, DnSta & Num=  ,5515, 2 ,5515, 2 , 0 , 0 , 0 ,,
       3       3
     390     444
       3       3
     390     444
Pier Skew, UpSta & Num, DnSta & Num=  ,5590, 2 ,5590, 2 , 0 , 0 , 0 ,,
       3       3
     390     444
       3       3
     390     444
Pier Skew, UpSta & Num, DnSta & Num=  ,5665, 2 ,5665, 2 , 0 , 0 , 0 ,,
       3       3
     390     444
       3       3
     390     444
Pier Skew, UpSta & Num, DnSta & Num=  ,5740, 2 ,5740, 2 , 0 , 0 , 0 ,,
     2.5     2.5
     390     444
     2.5     2.5
     390     444
Pier Skew, UpSta & Num, DnSta & Num=  ,5815, 2 ,5815, 2 , 0 , 0 , 0 ,,
     2.5     2.5
     390     444
     2.5     2.5
     390     444
Pier Skew, UpSta & Num, DnSta & Num=  ,5890, 2 ,5890, 2 , 0 , 0 , 0 ,,
     2.5     2.5
     390     444
     2.5     2.5
     390     444
Pier Skew, UpSta & Num, DnSta & Num=  ,5965, 2 ,5965, 2 , 0 , 0 , 0 ,,
     2.5     2.5
     390     444
     2.5     2.5
     390     444
Pier Skew, UpSta & Num, DnSta & Num=  ,6040, 2 ,6040, 2 , 0 , 0 , 0 ,,
     2.5     2.5
     390     444
     2.5     2.5
     390     444
BR Coef= 1 , 0 , 0 ,1.05, 0 ,,,0.8,-1,0.5,1,
WSPro=,,,, 1 ,,,, 0 ,,,, 0 ,,,,-1 ,-1 ,-1 , 0 , 0 , 0 , 0 , 0
BC Design=,, 0 ,, 0 ,,,,,,
BC HTab HWMax=436.6
BC Use User HTab Curves=0
BC User HTab FreeFlow(D)= 0

Type RM Length L Ch R = 1 ,29341   ,1,1,1
BEGIN DESCRIPTION:
This cross section corresponds to cross section 29320 of the non-georeferenced CDC model which was the source of this model.
Right Overbank updated with 2007 levee topo.
END DESCRIPTION:
XS GIS Cut Line= 4
2461157.621579477004488.838138672459429.567721757000333.86162071
2458803.524354436998828.587072222457515.645368526996406.39703472
#Sta/Elev= 30
   -2650   431.5    3723     432    3942   432.6    4340   436.6    4340     430
    4381   413.7    4694   412.7    4828     415  4866.5   412.2    4967   412.2
    5135     414    5156   407.1    5165   400.2    5190   392.9    5215   391.3
 5232.66  400.08    5242   416.5    5259   417.8    5347   416.9  5438.5  418.07
    5459   414.4    5542   413.6    5547   415.4    5560   415.5    5757   412.4
 5966.25  412.05 5976.57  415.98 6053.09     414 6132.41     416 6223.56   430.7
#Mann= 3 ,0,0
   -2650     .08       0    5135     .05       0    5242     .08       0
#XS Ineff= 2 , 0
       0    1850     440               0
Permanent Ineff=
       F       F
Bank Sta=5135,5242
XS Rating Curve= 0 ,0
Exp/Cntr=0.5,0.3

Type RM Length L Ch R = 1 ,29340   ,147,147,147
BEGIN DESCRIPTION:
This cross section corresponds to cross section 29319 of the non-georeferenced CDC model which was the source of this model.
Right Overbank updated with 2007 levee topo.
END DESCRIPTION:
XS GIS Cut Line= 4
2461158.115553377004488.565110742459431.03294191 7000333.1847848
2458805.454468676998828.035892222457516.453437756996406.10897756
#Sta/Elev= 30
   -2650   431.5    2484   432.2    3723     432    4340   436.6    4340     430
    4381   413.7    4694   412.7    4828     415  4866.5   412.2    4967   412.2
    5135     414    5156   407.1    5165   400.2    5190   392.9    5215   391.3
 5232.66  400.08    5242   416.5  5438.5  418.07    5459   414.4    5542   413.6
    5547   415.4    5560   415.5  5666.5  414.24    5880   411.6 5966.25  412.05
 5976.57  415.98 6053.09     414 6108.63  415.14 6132.41     416 6223.56   430.7
#Mann= 5 ,-1,0
   -2650     .07       0    2484      .1       0    5135     .05       0
    5242      .1       0  5666.5     .03       0
#XS Ineff= 2 , 0
       0    1850     440               0
Permanent Ineff=
       F       F
Bank Sta=5135,5242
XS Rating Curve= 0 ,0
Exp/Cntr=0.3,0.1

Type RM Length L Ch R = 1 ,29193   ,230,400,390
BEGIN DESCRIPTION:
This cross section corresponds to cross section 29170 of the non-georeferenced CDC model which was the source of this model.
Right Overbank updated with 2007 levee topo.
END DESCRIPTION:
XS GIS Cut Line= 5
2462004.206311227005359.590957272460593.016182247002376.54848021
  2458981.7388936998970.552011392458068.408042526997150.21805364
 2457580.91131416996328.34961863
#Sta/Elev= 30
   -2300   436.2    1010   436.7    1032   435.8    1083   421.4    1169   428.9
    1667   429.9    2270   427.1    2371   422.6    2621     427    3066   425.5
    3121   429.3    3230   425.5    4062     428    4100   424.1    4615     423
    5400     421    6009   412.4    6563   413.9    6574   410.1    6585   400.2
    6635  391.37    6660   392.9    6697   407.2    6769   417.8    6951   418.1
    6969   414.4    7237   413.9 7307.77     410 7717.67     414 7760.08   430.7
#Mann= 5 ,-1,0
   -2300     .07       0    4615     .16       0    6563     .05       0
    6769     .16       0 7717.67     .03       0
#XS Ineff= 3 ,-1
    1000    3230     450    5400    5850     450    7580 7760.08     450
Permanent Ineff=
       F       F       F
Bank Sta=6563,6769
XS Rating Curve= 0 ,0
Exp/Cntr=0.3,0.1

Type RM Length L Ch R = 1 ,28793   ,529,660,339
BEGIN DESCRIPTION:
This cross section corresponds to cross section 28770 of the non-georeferenced CDC model which was the source of this model.
Right Overbank updated with 2007 levee topo.
END DESCRIPTION:
XS GIS Cut Line= 5
2462419.249360357005151.46204691 2460821.65483267002037.35033971
2458527.822149936997566.09615888  2458512.9760516997250.61516255
2458162.704113756996480.13179538
#Sta/Elev= 30
   -2500   441.6    1019   441.7    1076   422.2    1119   422.4    1124   419.5
    1145   419.5    1204   427.9    1280   428.9    1674   425.6    2112   427.7
    2130   423.9    3783   428.4    3846     426    4594   424.7    4668     421
    4709   412.5    5536   418.5    5756   411.7    5948   415.5    6113   412.3
    6175   392.9    6200   390.6    6225   392.9    6232   407.2    6246   414.2
    6888   417.8 6962.14     410 7059.91  413.35 7108.28     416 7187.51   433.3
#Mann= 5 ,-1,0
   -2500     .07       0    4594     .16       0    6113     .05       0
    6246     .16       0 7059.91     .03       0
#XS Ineff= 2 ,-1
    1000    2830     450    5200    5400     450
Permanent Ineff=
       F       F
Bank Sta=6113,6246
XS Rating Curve= 0 ,0
Exp/Cntr=0.3,0.1

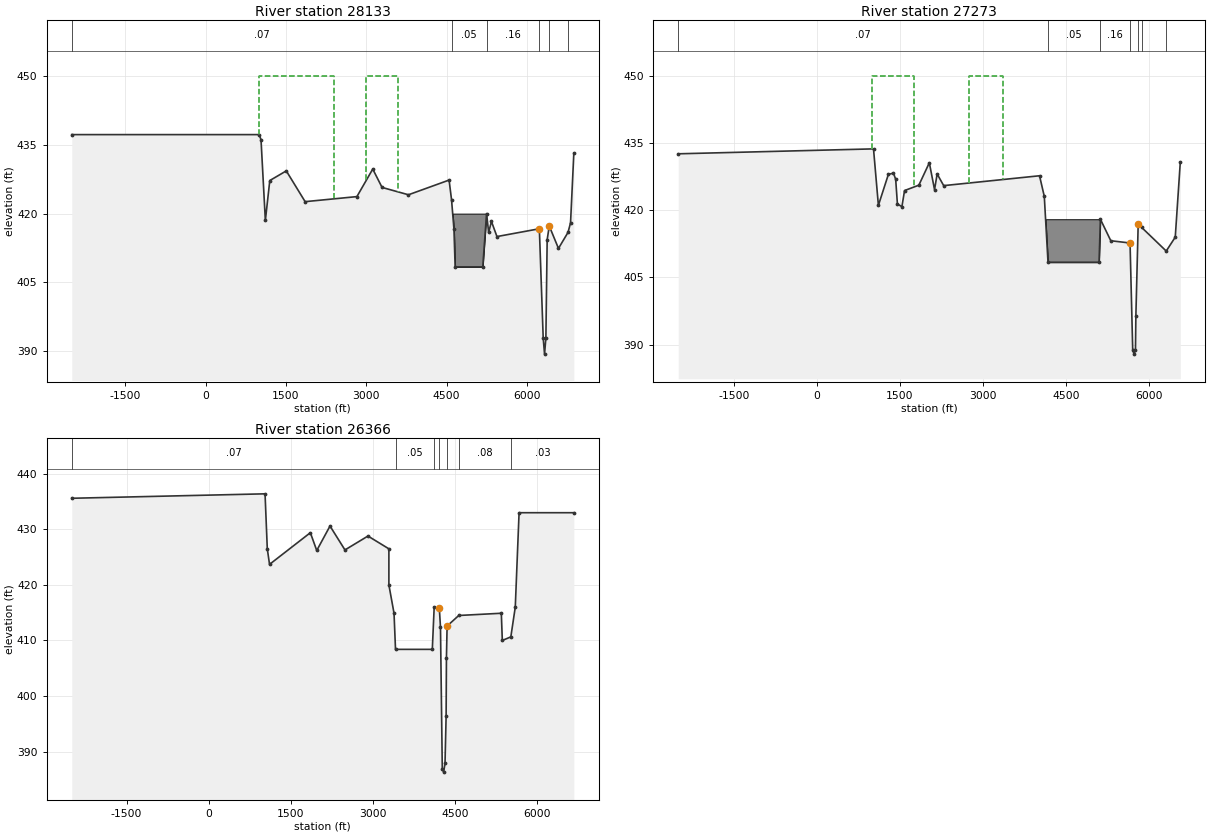
Type RM Length L Ch R = 1 ,28133   ,550,860,840
BEGIN DESCRIPTION:
This cross section corresponds to cross section 28109 of the non-georeferenced CDC model which was the source of this model.
Right Overbank updated with 2007 levee topo.
END DESCRIPTION:
XS GIS Cut Line= 5
 2462460.44887437004910.22740512 2461010.26830057001724.79551864
2458861.859867666997005.653054042458687.417959336996838.63403113
2458491.851749426996431.53838864
#Sta/Elev= 30
   -2500   437.2    1000   437.2    1035   436.1    1116   418.5    1199   427.2
    1507   429.3    1859   422.6    2826   423.7    3122   429.7    3296   425.7
    3789   424.1    4548   427.3    4594     423    4639   416.6    4661   408.4
    5177   408.4    5248     420    5287   415.9    5339   418.3    5442     415
    6234   416.7    6306   392.9    6331   389.4    6356   392.9    6380   414.3
    6419   417.3  6591.2  412.42 6770.37  415.93 6816.63     418 6878.35   433.2
#Mann= 6 ,-1,0
   -2500     .07       0    4594     .05       0    5248     .16       0
    6234     .05       0    6419     .16       0 6770.37     .03       0
#XS Ineff= 2 ,-1
    1000    2400     450    3000    3600     450
Permanent Ineff=
       F       F
#Block Obstruct= 2 ,-1
                            4607    5248     420
Bank Sta=6234,6419
XS Rating Curve= 0 ,0
Exp/Cntr=0.3,0.1

Type RM Length L Ch R = 1 ,27273   ,700,907,400
BEGIN DESCRIPTION:
This cross section corresponds to cross section 27249 of the non-georeferenced CDC model which was the source of this model.
Right Overbank updated with 2007 levee topo.
END DESCRIPTION:
XS GIS Cut Line= 6
 2463729.0261799 7003658.81911182461302.577755247001136.44958247
2461297.64797509 7001131.32492082459446.397084426996971.78402729
2459563.31089258 6996721.25500082459236.204919526996078.32124729
#Sta/Elev= 30
   -2500   432.6    1023   433.7    1111   421.1    1291     428    1383   428.3
    1423   426.9    1454   421.4    1535   420.8    1583   424.4    1841   425.6
    2030   430.6    2124   424.6    2171   428.1    2289   425.5    4018   427.7
    4104   423.1    4171   408.4    5092   408.4    5116     418    5304   413.2
    5651   412.7    5699   388.9    5724   387.9    5749   388.9    5756   396.4
    5798     417    5858   416.2 6303.86   410.9 6466.67     414 6557.84   430.8
#Mann= 7 ,-1,0
   -2500     .07       0    4171     .05       0    5116     .16       0
    5651     .05       0    5798     .16       0    5858     .08       0
 6303.86     .03       0
#XS Ineff= 2 ,-1
    2750    3350     450    1000    1750     450
Permanent Ineff=
       F       F
#Block Obstruct= 2 ,-1
                            4104    5116     418
Bank Sta=5651,5798
XS Rating Curve= 0 ,0
Exp/Cntr=0.3,0.1

Type RM Length L Ch R = 1 ,26366   ,859,1093,450
BEGIN DESCRIPTION:
This cross section corresponds to cross section 26342 of the non-georeferenced CDC model which was the source of this model.
Right Overbank updated with 2007 levee topo.
********************************************************************
CDC Dallas 050901-1 B&B Lakes Office Site
Located in LOB.
Cross-sections 26342 - 27249
********************************************************************
END DESCRIPTION:
XS GIS Cut Line= 5
2464108.811545847002673.554848022462033.922093096999854.89669938
2460723.404044846998074.607937132459479.393737586995956.42746222
2458972.972018566995094.14152211
#Sta/Elev= 30
   -2500   435.6    1029   436.4    1070   426.5    1111   423.7    1856   429.4
    1973   426.2    2215   430.6    2488   426.3    2908   428.8    3290   426.5
    3290     420    3384   414.9    3411   408.4    4083   408.4    4117     416
    4211   415.8    4232   412.4    4265   386.9    4290   386.3    4315   387.9
    4335   396.4    4341   406.9    4353   412.6    4566   414.5    5343   414.9
 5361.11     410 5516.57  410.65 5597.79     416 5667.13     433 6667.13     433
#Mann= 7 ,-1,0
   -2500     .07       0    3411     .05       0    4117     .16       0
    4211     .05       0    4353     .16       0    4566     .08       0
 5516.57     .03       0
#Block Obstruct= 2 , 0
            4117     416
Bank Sta=4211,4353
XS Rating Curve= 0 ,0
Exp/Cntr=0.3,0.1