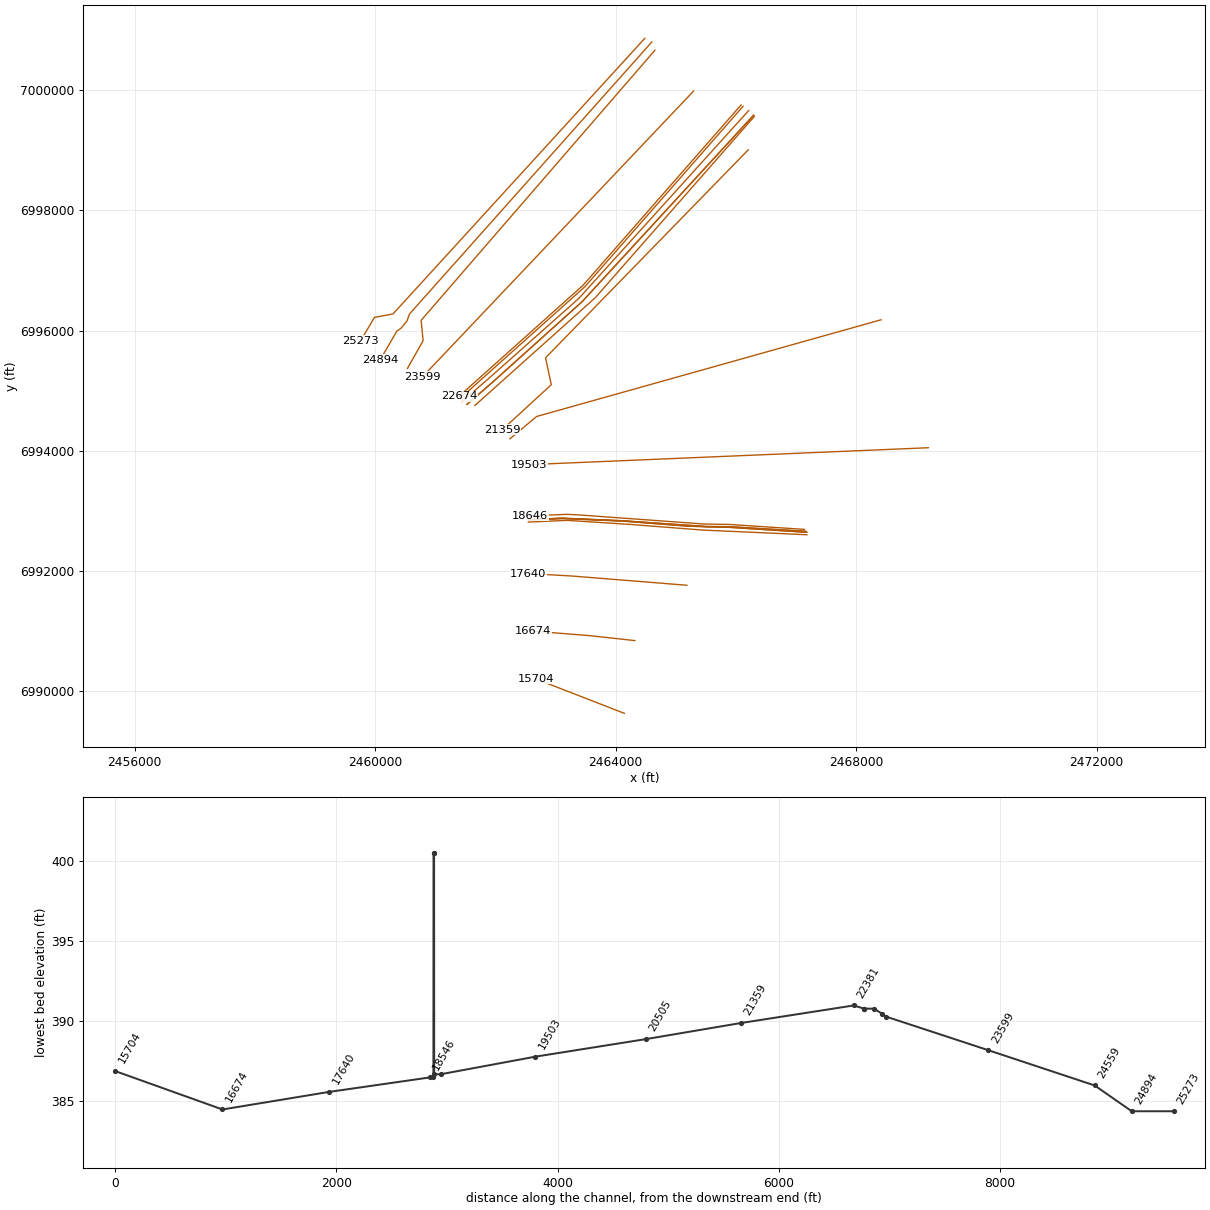
HEC-RAS study CDC_Consolidated_Model.prj: Upper Trinity CDC Consolidated Model

--- CDC_Consolidated_Model.g04 (geometry) --- (continued)

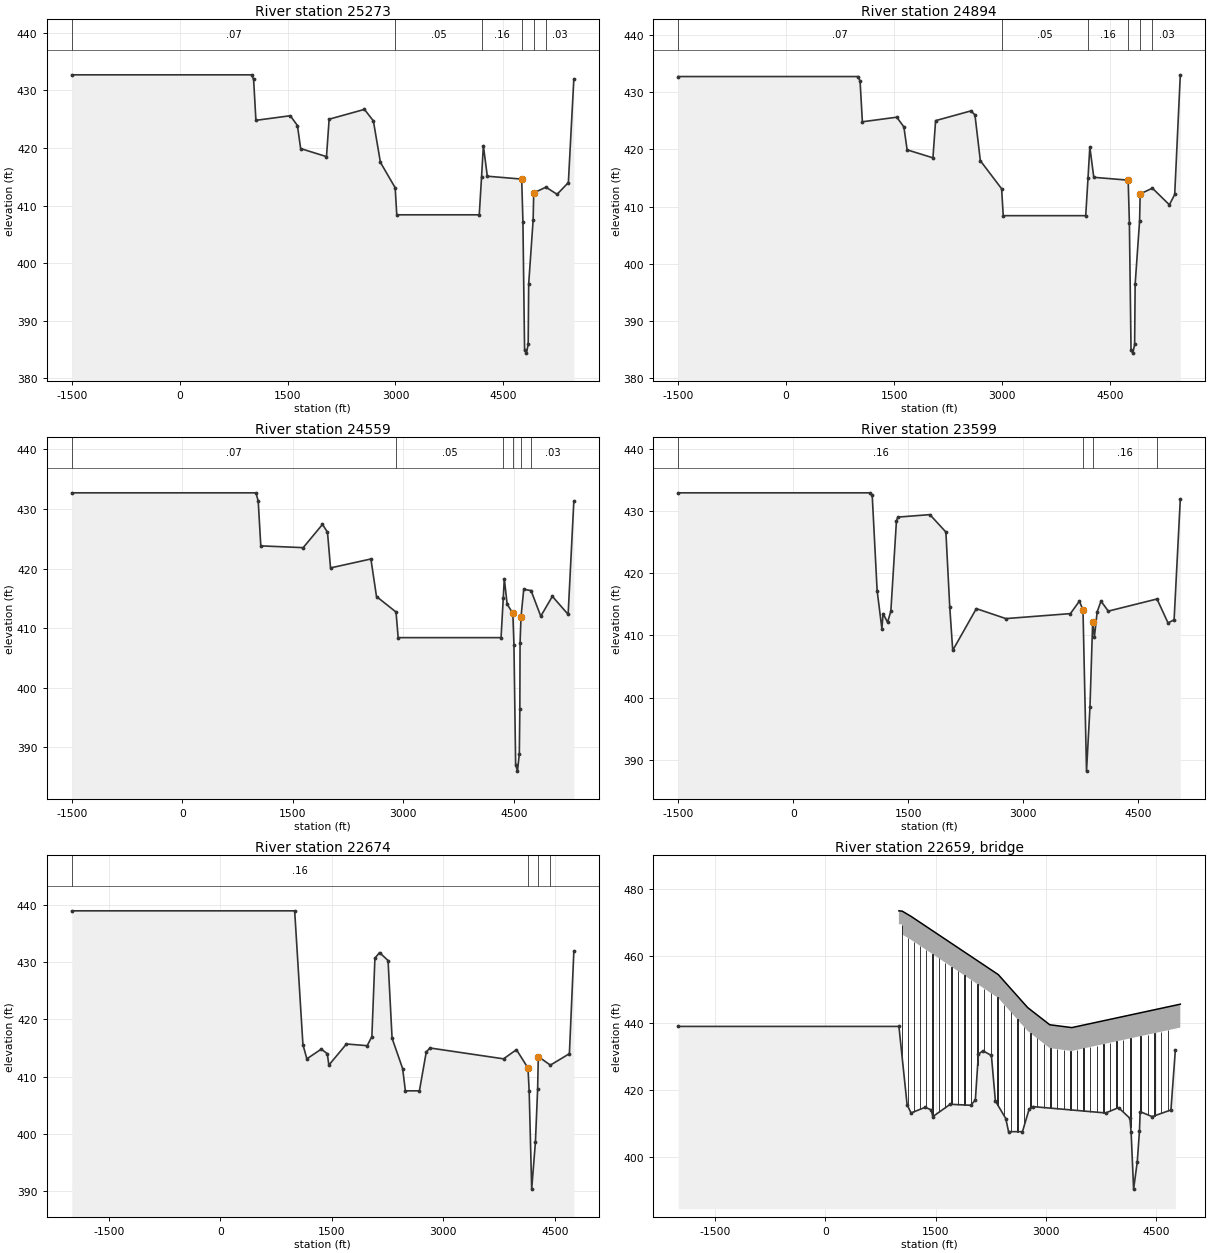
Type RM Length L Ch R = 1 ,25273   ,207,379,483
BEGIN DESCRIPTION:
This cross section corresponds to cross section 25248 of the non-georeferenced CDC model which was the source of this model.
Right Overbank updated with 2007 levee topo.
END DESCRIPTION:
XS GIS Cut Line= 5
2464485.704832587000863.586858992462800.08821169 6999017.3212748
2460298.195905756996276.984235792459990.87991935 6996220.1969478
2459757.472249696995827.64720796
#Sta/Elev= 30
   -1500   432.7    1000   432.7    1028   431.9    1060   424.8    1538   425.6
    1637   423.9    1682   419.9    2041   418.5    2078     425    2569   426.7
    2693   424.7    2791   417.5    2996   413.1    3018   408.4    4165   408.4
    4197     415    4222   420.4    4277   415.1    4755   414.6    4772   407.2
    4795   384.9    4820  384.39    4845   385.9    4852   396.4    4914   407.5
    4922   412.2    5092   413.2 5246.85  411.96 5403.73     414 5479.87     432
#Mann= 6 ,-1,0
   -1500     .07       0    2996     .05       0    4197     .16       0
    4755     .05       0    4922     .16       0    5092     .03       0
#Block Obstruct= 2 , 0
            4197     415
Bank Sta=4755,4922
XS Rating Curve= 0 ,0
Exp/Cntr=0.3,0.1

Type RM Length L Ch R = 1 ,24894   ,219,335,370
BEGIN DESCRIPTION:
This cross section corresponds to cross section 24900 of the non-georeferenced CDC model which was the source of this model.
END DESCRIPTION:
XS GIS Cut Line= 6
2464602.615385677000803.267097522460572.26064634 6996275.4212468
2460532.298784026996162.557627382460432.175952766996040.07952589
2460363.263032856995992.982179142460084.030323596995511.23478305
#Sta/Elev= 30
   -1500   432.7    1000   432.7    1028   431.9    1060   424.8    1538   425.6
    1637   423.9    1682   419.9    2041   418.5    2078     425    2569   426.7
    2625     426    2700     418    2996   413.1    3018   408.4    4165   408.4
    4197     415    4222   420.4    4277   415.1    4755   414.6    4772   407.2
    4795   384.9    4820  384.39    4845   385.9    4852   396.4    4914   407.5
    4922   412.2    5092   413.2    5328   410.3    5402   412.1    5480     433
#Mann= 6 ,-1,0
   -1500     .07       0    2996     .05       0    4197     .16       0
    4755     .05       0    4922     .16       0    5092     .03       0
Bank Sta=4755,4922
XS Rating Curve= 0 ,0
Exp/Cntr=0.3,0.1

Type RM Length L Ch R = 1 ,24559   ,740,960,400
BEGIN DESCRIPTION:
This cross section corresponds to cross section 24534 of the non-georeferenced CDC model which was the source of this model.
Right Overbank updated with 2007 levee topo.
*********************************************************************
CDC Dallas 021800-1 DEA Laboratory
Located in LOB.
Cross-sections 24534 - 25248
*********************************************************************
END DESCRIPTION:
XS GIS Cut Line= 5
2464654.130596817000665.476740062463018.658968756998774.64820372
2460765.848841856996170.092061132460799.252974516995832.71314272
2460538.997917596995370.85087746
#Sta/Elev= 30
   -1500   432.7    1000   432.7    1030   431.3    1065   423.8    1640   423.5
    1902   427.4    1970   426.1    2011   420.1    2559   421.6    2635   415.3
    2900   412.7    2929   408.4    4325   408.4    4355     415    4369   418.3
    4408     414    4485   412.5    4500   407.2    4523   387.1    4548     386
    4573   388.9    4580   396.4    4583   407.5    4596   411.9    4633   416.5
    4732   416.3    4864     412 5021.38  415.33 5235.34   412.3 5312.84  431.32
#Mann= 6 ,-1,0
   -1500     .07       0    2900     .05       0    4355     .16       0
    4485     .05       0    4596     .16       0    4732     .03       0
#Block Obstruct= 2 , 0
            4355     415
Bank Sta=4485,4596
XS Rating Curve= 0 ,0
Exp/Cntr=0.3,0.1

Type RM Length L Ch R = 1 ,23599   ,840,925,700
BEGIN DESCRIPTION:
This cross section corresponds to cross section 23574 of the non-georeferenced CDC model which was the source of this model.
Right Overbank updated with 2007 levee topo.
END DESCRIPTION:
XS GIS Cut Line= 3
2465297.408271936999986.549689572463577.522352346998172.16482863
2460792.483631076995234.10246331
#Sta/Elev= 30
   -1500   432.9    1000   432.9    1030   432.5    1094   417.2    1156   411.1
    1172   413.5    1230   412.1    1273   413.9    1346   428.4    1364     429
    1782   429.4    1991   426.6    2041   414.6    2080   407.6    2388   414.3
    2773   412.7    3615   413.5    3732   415.5    3779   414.1    3825   388.2
    3870   398.5    3905   412.1    3928   409.8    3964   413.8    4014   415.5
    4109   413.9  4744.3  415.85 4888.25     412 4967.28  412.51 5048.29   431.9
#Mann= 4 ,-1,0
   -1500     .16       0    3779     .05       0    3905     .16       0
  4744.3     .03       0
Bank Sta=3779,3905
XS Rating Curve= 0 ,0
Exp/Cntr=0.3,0.1

Type RM Length L Ch R = 1 ,22674   ,39,39,39
BEGIN DESCRIPTION:
This cross section corresponds to cross section 22649 of the non-georeferenced CDC model which was the source of this model.
Right Overbank updated with 2007 levee topo.
END DESCRIPTION:
XS GIS Cut Line= 5
2466086.676240926999754.437743742465757.277602466999378.27748935
2464110.284410186997497.476217392463461.233871016996756.28609872
2461396.079208676994906.93809138
#Sta/Elev= 30
   -2000     439    1000     439    1111   415.6    1164   413.1    1358   414.8
    1439     414    1460     412    1697   415.7    1976   415.4    2039     417
    2080   430.7    2142   431.7    2257   430.3    2311   416.7    2453   411.4
    2490   407.5    2679   407.5    2771   414.3    2821     415    3811   413.1
    3985   414.7    4140   411.5    4156   407.5    4190   390.3    4240   398.5
    4270   407.8    4279   413.5 4441.62     412 4697.54     414 4757.38   431.9
#Mann= 4 ,-1,0
   -2000     .16       0    4140     .05       0    4279     .16       0
 4441.62     .03       0
#Block Obstruct= 2 , 0
            2771   414.3
Bank Sta=4140,4279
XS Rating Curve= 0 ,0
Exp/Cntr=0.3,0.1

Type RM Length L Ch R = 3 ,22659   ,,,
BEGIN DESCRIPTION:
DART Northwest Transit Line
END DESCRIPTION:
Node Name=DART
Bridge Culvert--1,0,-1,-1, 0
Deck Dist Width WeirC Skew NumUp NumDn MinLoCord MaxHiCord MaxSubmerge Is_Ogee
3,25,2.6,0, 13, 13, , , 0.98, 0, 0,0,,
    1000    1045    1045    1165    1980    2250    2350    2450    2750    3050
    3350    4750    4825
   473.6   473.5   473.5  471.94  459.96  455.99  454.52  452.05  444.64   439.5
  438.65   445.3  445.66
   469.6   469.5   466.5  464.94  452.96  448.99  447.52  445.05  437.64   432.5
  431.65   438.3  438.66
    1000    1045    1045    1165    1980    2250    2350    2450    2750    3050
    3350    4750    4825
   473.6   473.5   473.5  471.94  459.96  455.99  454.52  452.05  444.64   439.5
  438.65   445.3  445.66
   469.6   469.5   466.5  464.94  452.96  448.99  447.52  445.05  437.64   432.5
  431.65   438.3  438.66
Pier Skew, UpSta & Num, DnSta & Num=  ,1045, 2 ,1045, 2 , 0 , 0 , 0 ,,
       5       5
     400     470
       5       5
     400     470
Pier Skew, UpSta & Num, DnSta & Num=  ,1125, 2 ,1125, 2 , 0 , 0 , 0 ,,
       5       5
     400     470
       5       5
     400     470
Pier Skew, UpSta & Num, DnSta & Num=  ,1205, 2 ,1205, 2 , 0 , 0 , 0 ,,
       5       5
     400     465
       5       5
     400     465
Pier Skew, UpSta & Num, DnSta & Num=  ,1285, 2 ,1285, 2 , 0 , 0 , 0 ,,
       5       5
     400     465
       5       5
     400     465
Pier Skew, UpSta & Num, DnSta & Num=  ,1365, 2 ,1365, 2 , 0 , 0 , 0 ,,
       5       5
     400     465
       5       5
     400     465
Pier Skew, UpSta & Num, DnSta & Num=  ,1455, 2 ,1455, 2 , 0 , 0 , 0 ,,
       5       5
     400     465
       5       5
     400     465
Pier Skew, UpSta & Num, DnSta & Num=  ,1545, 2 ,1545, 2 , 0 , 0 , 0 ,,
       5       5
     400     463
       5       5
     400     463
Pier Skew, UpSta & Num, DnSta & Num=  ,1630, 2 ,1630, 2 , 0 , 0 , 0 ,,
       5       5
     400     460
       5       5
     400     460
Pier Skew, UpSta & Num, DnSta & Num=  ,1715, 2 ,1715, 2 , 0 , 0 , 0 ,,
       5       5
     400     460
       5       5
     400     460
Pier Skew, UpSta & Num, DnSta & Num=  ,1800, 2 ,1800, 2 , 0 , 0 , 0 ,,
       5       5
     400     460
       5       5
     400     460
Pier Skew, UpSta & Num, DnSta & Num=  ,1890, 2 ,1890, 2 , 0 , 0 , 0 ,,
       5       5
     400     458
       5       5
     400     458
Pier Skew, UpSta & Num, DnSta & Num=  ,1980, 2 ,1980, 2 , 0 , 0 , 0 ,,
       5       5
     400     455
       5       5
     400     455
Pier Skew, UpSta & Num, DnSta & Num=  ,2070, 2 ,2070, 2 , 0 , 0 , 0 ,,
       5       5
     400     455
       5       5
     400     455
Pier Skew, UpSta & Num, DnSta & Num=  ,2160, 2 ,2160, 2 , 0 , 0 , 0 ,,
       5       5
     400   454.3
       5       5
     400   454.3
Pier Skew, UpSta & Num, DnSta & Num=  ,2250, 2 ,2250, 2 , 0 , 0 , 0 ,,
       5       5
     400   454.3
       5       5
     400   454.3
Pier Skew, UpSta & Num, DnSta & Num=  ,2340, 2 ,2340, 2 , 0 , 0 , 0 ,,
       5       5
     400   454.3
       5       5
     400   454.3
Pier Skew, UpSta & Num, DnSta & Num=  ,2430, 2 ,2430, 2 , 0 , 0 , 0 ,,
       5       5
     400   454.3
       5       5
     400   454.3
Pier Skew, UpSta & Num, DnSta & Num=  ,2520, 2 ,2520, 2 , 0 , 0 , 0 ,,
       5       5
     400   454.3
       5       5
     400   454.3
Pier Skew, UpSta & Num, DnSta & Num=  ,2610, 2 ,2610, 2 , 0 , 0 , 0 ,,
       5       5
     400   454.3
       5       5
     400   454.3
Pier Skew, UpSta & Num, DnSta & Num=  ,2700, 2 ,2700, 2 , 0 , 0 , 0 ,,
       5       5
     400   454.3
       5       5
     400   454.3
Pier Skew, UpSta & Num, DnSta & Num=  ,2790, 2 ,2790, 2 , 0 , 0 , 0 ,,
       5       5
     400   454.3
       5       5
     400   454.3
Pier Skew, UpSta & Num, DnSta & Num=  ,2880, 2 ,2880, 2 , 0 , 0 , 0 ,,
       5       5
     400   454.3
       5       5
     400   454.3
Pier Skew, UpSta & Num, DnSta & Num=  ,2970, 2 ,2970, 2 , 0 , 0 , 0 ,,
       5       5
     400   454.3
       5       5
     400   454.3
Pier Skew, UpSta & Num, DnSta & Num=  ,3060, 2 ,3060, 2 , 0 , 0 , 0 ,,
       5       5
     400   454.3
       5       5
     400   454.3
Pier Skew, UpSta & Num, DnSta & Num=  ,3150, 2 ,3150, 2 , 0 , 0 , 0 ,,
       5       5
     400   454.3
       5       5
     400   454.3
Pier Skew, UpSta & Num, DnSta & Num=  ,3240, 2 ,3240, 2 , 0 , 0 , 0 ,,
       5       5
     400   454.3
       5       5
     400   454.3
Pier Skew, UpSta & Num, DnSta & Num=  ,3330, 2 ,3330, 2 , 0 , 0 , 0 ,,
       5       5
     400   454.3
       5       5
     400   454.3
Pier Skew, UpSta & Num, DnSta & Num=  ,3420, 2 ,3420, 2 , 0 , 0 , 0 ,,
       5       5
     400   454.3
       5       5
     400   454.3
Pier Skew, UpSta & Num, DnSta & Num=  ,3510, 2 ,3510, 2 , 0 , 0 , 0 ,,
       5       5
     400   454.3
       5       5
     400   454.3
Pier Skew, UpSta & Num, DnSta & Num=  ,3600, 2 ,3600, 2 , 0 , 0 , 0 ,,
       5       5
     400   454.3
       5       5
     400   454.3
Pier Skew, UpSta & Num, DnSta & Num=  ,3690, 2 ,3690, 2 , 0 , 0 , 0 ,,
       5       5
     400   454.3
       5       5
     400   454.3
Pier Skew, UpSta & Num, DnSta & Num=  ,3780, 2 ,3780, 2 , 0 , 0 , 0 ,,
       5       5
     400   454.3
       5       5
     400   454.3
Pier Skew, UpSta & Num, DnSta & Num=  ,3870, 2 ,3870, 2 , 0 , 0 , 0 ,,
       5       5
     400   454.3
       5       5
     400   454.3
Pier Skew, UpSta & Num, DnSta & Num=  ,3960, 2 ,3960, 2 , 0 , 0 , 0 ,,
       5       5
     400   454.3
       5       5
     400   454.3
Pier Skew, UpSta & Num, DnSta & Num=  ,4050, 2 ,4050, 2 , 0 , 0 , 0 ,,
       5       5
     400   454.3
       5       5
     400   454.3
Pier Skew, UpSta & Num, DnSta & Num=  ,4150, 2 ,4150, 2 , 0 , 0 , 0 ,,
       5       5
     400   454.3
       5       5
     400   454.3
Pier Skew, UpSta & Num, DnSta & Num=  ,4285, 2 ,4285, 2 , 0 , 0 , 0 ,,
       5       5
     400   454.3
       5       5
     400   454.3
Pier Skew, UpSta & Num, DnSta & Num=  ,4385, 2 ,4385, 2 , 0 , 0 , 0 ,,
       5       5
     400   454.3
       5       5
     400   454.3
Pier Skew, UpSta & Num, DnSta & Num=  ,4475, 2 ,4475, 2 , 0 , 0 , 0 ,,
       5       5
     400   454.3
       5       5
     400   454.3
Pier Skew, UpSta & Num, DnSta & Num=  ,4565, 2 ,4565, 2 , 0 , 0 , 0 ,,
       5       5
     400   454.3
       5       5
     400   454.3
Pier Skew, UpSta & Num, DnSta & Num=  ,4655, 2 ,4655, 2 , 0 , 0 , 0 ,,
       6       6
     400   454.3
       6       6
     400   454.3
BR Coef=-1 , 0 , 0 ,1.05, 0 ,,,0.8,-1,0.5,0,
WSPro=,,,, 1 ,,,, 0 ,,,, 0 ,,,,-1 ,-1 ,-1 , 0 , 0 , 0 , 0 , 0
BC Design=,, 0 ,, 0 ,,,,,,
BC Use User HTab Curves=0
BC User HTab FreeFlow(D)= 0

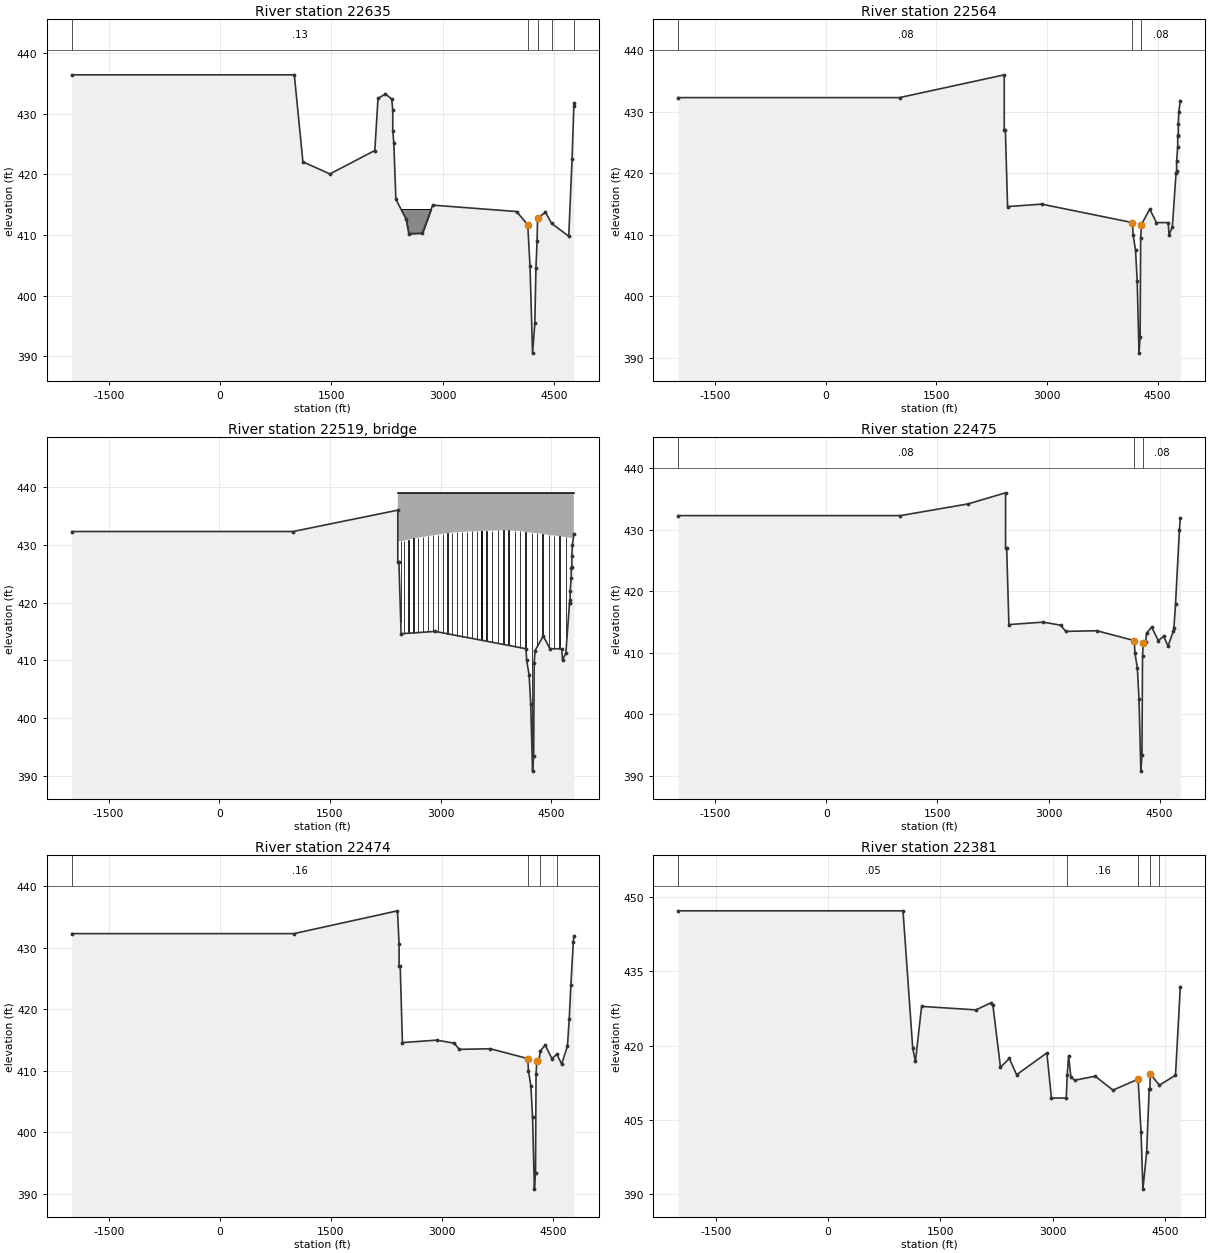
Type RM Length L Ch R = 1 ,22635   ,71,71,71
BEGIN DESCRIPTION:
This cross section corresponds to cross section 22610 of the non-georeferenced CDC model which was the source of this model.
*********************************************************************
CDC Irving 110308-01 DART Northwest Corridor Light Rail Transit Line
Cross-sections 22610 - 22649
*********************************************************************
Interpolated cross-section
END DESCRIPTION:
XS GIS Cut Line= 5
2466120.054379636999733.089409342465790.594566196999356.98273388
  2464143.2954996997476.449356562463492.124229166996733.08142072
2461421.602779696994877.96209946
#Sta/Elev= 30
   -2000  436.46    1000  436.46 1115.94  422.08 1480.46  420.09 2085.21  423.96
 2128.04  432.56 2228.31   433.3 2312.91  432.46 2327.25  430.67 2327.25  427.26
 2341.27  425.21 2369.31   415.9 2507.31  412.62 2543.27  410.22 2726.95   410.3
 2864.95  414.94 3996.18  413.88 4146.82  411.69 4177.38  404.88 4211.58  390.49
 4242.44  395.43 4257.43  404.61 4272.51  409.01 4279.36  412.81 4386.06  413.74
 4468.68  411.91 4699.39   409.8 4744.46  422.56 4768.27  431.37 4768.27  431.82
#Mann= 5 ,-1,0
   -2000     .13       0 4146.82     .05       0 4279.36     .13       0
 4468.68    .049       0 4768.27    .049       0
#Block Obstruct= 2 , 0
       0    2900   414.3               0
Bank Sta=4146.82,4279.36
XS Rating Curve= 0 ,0
Exp/Cntr=0.3,0.1

Type RM Length L Ch R = 1 ,22564   ,89,89,89
BEGIN DESCRIPTION:
This cross section corresponds to cross section 22546 of the non-georeferenced CDC model which was the source of this model.
Right Overbank updated with 2007 levee topo.
END DESCRIPTION:
XS GIS Cut Line= 6
2466213.721526016999662.195220132465878.501442316999291.21342073
2464202.401023836997436.304423722463389.522072176996536.70648538
2461876.051345836995191.109439052461446.075827846994818.12560497
#Sta/Elev= 30
   -2000   432.3    1000   432.3    2420     436    2420     427    2435     427
    2465   414.6  2926.5     415    4158     412    4167     410    4200   407.5
    4222   402.5    4247   390.8    4262   393.5 4269.29 409.451 4279.95  411.68
  4392.5   414.2    4483     412 4643.02     412 4653.38     410 4698.89  411.28
  4748.5     420 4754.97     420 4756.57  420.43 4756.78     422 4771.52  424.33
  4771.8     426 4779.01  426.21 4779.25     428 4786.48     430 4806.81   431.8
#Mann= 3 ,0,0
   -2000     .08       0    4158     .05       0 4279.95     .08       0
Bank Sta=4158,4279.95
XS Rating Curve= 0 ,0
Exp/Cntr=0.5,0.3

Type RM Length L Ch R = 3 ,22519   ,,,
BEGIN DESCRIPTION:
SH 482/Storey Lane
END DESCRIPTION:
Node Name=SH 482
Bridge Culvert--1,0,-1,-1, 0
Deck Dist Width WeirC Skew NumUp NumDn MinLoCord MaxHiCord MaxSubmerge Is_Ogee
2,86,2.6,0, 51, 51, , , 0.95, 0, ,,,
    2420  2497.5  2502.5 2564.75 2567.25 2630.75 2633.25  2761.5  2766.5 2828.75
 2831.25  2959.5  2964.5  3025.5  3030.5 3158.75 3161.25 3224.75 3227.25  3355.5
  3360.5  3487.5  3492.5 3554.75 3557.25  3689.5  3694.5  3779.5  3784.5 3920.75
 3923.25 4010.75 4013.25 4080.75 4083.25 4150.75 4153.25 4240.75 4243.25 4310.75
 4313.25 4380.75 4383.25 4470.75 4473.25 4540.75 4543.25  4609.5  4614.5    4772
 4806.81
     439     439     439     439     439     439     439     439     439     439
     439     439     439     439     439     439     439     439     439     439
     439     439     439     439     439     439     439     439     439     439
     439     439     439     439     439     439     439     439     439     439
     439     439     439     439     439     439     439     439     439     439
     439
   430.6 430.697 430.708 430.896 430.904 431.096 431.102 431.362 431.372 431.498
 431.504 431.763 431.773 431.896 431.904 432.098 432.102 432.198 432.202 432.283
 432.286 432.366 432.369   432.4 432.402  432.46 432.462   432.5   432.5   432.5
 432.499 432.401   432.4   432.4 432.396 432.204   432.2   432.1 432.088 432.004
 431.998 431.902 431.897 431.703 431.698 431.602 431.596 431.482 431.473   431.2
   431.2
    2420  2497.5  2502.5 2564.75 2567.25 2630.75 2633.25  2761.5  2766.5 2828.75
 2831.25  2959.5  2964.5  3025.5  3030.5 3158.75 3161.25 3224.75 3227.25  3355.5
  3360.5  3487.5  3492.5 3554.75 3557.25  3689.5  3694.5  3779.5  3784.5 3920.75
 3923.25 4010.75 4013.25 4080.75 4083.25 4150.75 4153.25 4240.75 4243.25 4310.75
 4313.25 4380.75 4383.25 4470.75 4473.25 4540.75 4543.25  4609.5  4614.5    4772
 4779.67
     439     439     439     439     439     439     439     439     439     439
     439     439     439     439     439     439     439     439     439     439
     439     439     439     439     439     439     439     439     439     439
     439     439     439     439     439     439     439     439     439     439
     439     439     439     439     439     439     439     439     439     439
     439
   430.6 430.697 430.708 430.896 430.904 431.096 431.102 431.362 431.372 431.498
 431.504 431.763 431.773 431.896 431.904 432.098 432.102 432.198 432.202 432.283
 432.286 432.366 432.369   432.4 432.402  432.46 432.462   432.5   432.5   432.5
 432.499 432.401   432.4   432.4 432.396 432.204   432.2   432.1 432.088 432.004
 431.998 431.902 431.897 431.703 431.698 431.602 431.596 431.482 431.473   431.2
   431.2
Pier Skew, UpSta & Num, DnSta & Num=  ,2460, 2 ,2460, 2 , 0 , 0 , 0 ,,
     2.5     2.5
     390     446
     2.5     2.5
     390     446
Pier Skew, UpSta & Num, DnSta & Num=  ,2500, 2 ,2500, 2 , 0 , 0 , 0 ,,
     2.5     2.5
     390     446
     2.5     2.5
     390     446
Pier Skew, UpSta & Num, DnSta & Num=  ,2566, 2 ,2566, 2 , 0 , 0 , 0 ,,
     2.5     2.5
     390     446
     2.5     2.5
     390     446
Pier Skew, UpSta & Num, DnSta & Num=  ,2632, 2 ,2632, 2 , 0 , 0 , 0 ,,
     2.5     2.5
     390     446
     2.5     2.5
     390     446
Pier Skew, UpSta & Num, DnSta & Num=  ,2698, 2 ,2698, 2 , 0 , 0 , 0 ,,
     2.5     2.5
     390     446
     2.5     2.5
     390     446
Pier Skew, UpSta & Num, DnSta & Num=  ,2764, 2 ,2764, 2 , 0 , 0 , 0 ,,
     2.5     2.5
     390     446
     2.5     2.5
     390     446
Pier Skew, UpSta & Num, DnSta & Num=  ,2830, 2 ,2830, 2 , 0 , 0 , 0 ,,
     2.5     2.5
     390     446
     2.5     2.5
     390     446
Pier Skew, UpSta & Num, DnSta & Num=  ,2896, 2 ,2896, 2 , 0 , 0 , 0 ,,
     2.5     2.5
     390     446
     2.5     2.5
     390     446
Pier Skew, UpSta & Num, DnSta & Num=  ,2962, 2 ,2962, 2 , 0 , 0 , 0 ,,
     2.5     2.5
     390     446
     2.5     2.5
     390     446
Pier Skew, UpSta & Num, DnSta & Num=  ,3028, 2 ,3028, 2 , 0 , 0 , 0 ,,
     2.5     2.5
     390     446
     2.5     2.5
     390     446
Pier Skew, UpSta & Num, DnSta & Num=  ,3094, 2 ,3094, 2 , 0 , 0 , 0 ,,
     2.5     2.5
     390     446
     2.5     2.5
     390     446
Pier Skew, UpSta & Num, DnSta & Num=  ,3160, 2 ,3160, 2 , 0 , 0 , 0 ,,
     2.5     2.5
     390     446
     2.5     2.5
     390     446
Pier Skew, UpSta & Num, DnSta & Num=  ,3226, 2 ,3226, 2 , 0 , 0 , 0 ,,
     2.5     2.5
     390     446
     2.5     2.5
     390     446
Pier Skew, UpSta & Num, DnSta & Num=  ,3292, 2 ,3292, 2 , 0 , 0 , 0 ,,
     2.5     2.5
     390     446
     2.5     2.5
     390     446
Pier Skew, UpSta & Num, DnSta & Num=  ,3358, 2 ,3358, 2 , 0 , 0 , 0 ,,
     2.5     2.5
     390     446
     2.5     2.5
     390     446
Pier Skew, UpSta & Num, DnSta & Num=  ,3424, 2 ,3424, 2 , 0 , 0 , 0 ,,
     2.5     2.5
     390     446
     2.5     2.5
     390     446
Pier Skew, UpSta & Num, DnSta & Num=  ,3490, 2 ,3490, 2 , 0 , 0 , 0 ,,
     2.5     2.5
     390     446
     2.5     2.5
     390     446
Pier Skew, UpSta & Num, DnSta & Num=  ,3556, 2 ,3556, 2 , 0 , 0 , 0 ,,
     2.5     2.5
     390     446
     2.5     2.5
     390     446
Pier Skew, UpSta & Num, DnSta & Num=  ,3556, 2 ,3556, 2 , 0 , 0 , 0 ,,
     2.5     2.5
     390     446
     2.5     2.5
     390     446
Pier Skew, UpSta & Num, DnSta & Num=  ,3622, 2 ,3622, 2 , 0 , 0 , 0 ,,
     2.5     2.5
     390     446
     2.5     2.5
     390     446
Pier Skew, UpSta & Num, DnSta & Num=  ,3692, 2 ,3692, 2 , 0 , 0 , 0 ,,
     2.5     2.5
     390     446
     2.5     2.5
     390     446
Pier Skew, UpSta & Num, DnSta & Num=  ,3782, 2 ,3782, 2 , 0 , 0 , 0 ,,
     2.5     2.5
     390     446
     2.5     2.5
     390     446
Pier Skew, UpSta & Num, DnSta & Num=  ,3852, 2 ,3852, 2 , 0 , 0 , 0 ,,
     2.5     2.5
     390     446
     2.5     2.5
     390     446
Pier Skew, UpSta & Num, DnSta & Num=  ,3922, 2 ,3922, 2 , 0 , 0 , 0 ,,
     2.5     2.5
     390     446
     2.5     2.5
     390     446
Pier Skew, UpSta & Num, DnSta & Num=  ,4012, 2 ,4012, 2 , 0 , 0 , 0 ,,
     2.5     2.5
     390     446
     2.5     2.5
     390     446
Pier Skew, UpSta & Num, DnSta & Num=  ,4082, 2 ,4082, 2 , 0 , 0 , 0 ,,
     2.5     2.5
     390     446
     2.5     2.5
     390     446
Pier Skew, UpSta & Num, DnSta & Num=  ,4152, 2 ,4152, 2 , 0 , 0 , 0 ,,
     2.5     2.5
     390     446
     2.5     2.5
     390     446
Pier Skew, UpSta & Num, DnSta & Num=  ,4242, 2 ,4242, 2 , 0 , 0 , 0 ,,
     2.5     2.5
     390     446
     2.5     2.5
     390     446
Pier Skew, UpSta & Num, DnSta & Num=  ,4311, 2 ,4311, 2 , 0 , 0 , 0 ,,
     2.5     2.5
     390     446
     2.5     2.5
     390     446
Pier Skew, UpSta & Num, DnSta & Num=  ,4382, 2 ,4382, 2 , 0 , 0 , 0 ,,
     2.5     2.5
     390     446
     2.5     2.5
     390     446
Pier Skew, UpSta & Num, DnSta & Num=  ,4472, 2 ,4472, 2 , 0 , 0 , 0 ,,
     2.5     2.5
     390     446
     2.5     2.5
     390     446
Pier Skew, UpSta & Num, DnSta & Num=  ,4542, 2 ,4542, 2 , 0 , 0 , 0 ,,
     2.5     2.5
     390     446
     2.5     2.5
     390     446
Pier Skew, UpSta & Num, DnSta & Num=  ,4612, 2 ,4612, 2 , 0 , 0 , 0 ,,
       5       5
     390     446
     2.5     2.5
     390     446
Pier Skew, UpSta & Num, DnSta & Num=  ,4702, 2 ,4702, 2 , 0 , 0 , 0 ,,
     2.5     2.5
     390     446
     2.5     2.5
     390     446
BR Coef= 1 , 0 , 0 ,1.05, 0 ,,,0.8,-1,0.5,1,
WSPro=,,,, 1 ,,,, 0 ,,,, 0 ,,,,-1 ,-1 ,-1 , 0 , 0 , 0 , 0 , 0
BC Design=,, 0 ,, 0 ,,,,,,
BC HTab HWMax=436.1
BC Use User HTab Curves=0
BC User HTab FreeFlow(D)= 0

Type RM Length L Ch R = 1 ,22475   ,1,1,1
BEGIN DESCRIPTION:
This cross section corresponds to cross section 22457 of the non-georeferenced CDC model which was the source of this model.
Right Overbank updated with 2007 levee topo.
END DESCRIPTION:
XS GIS Cut Line= 6
2466294.615507126999584.726372022464264.798864936997375.68938747
2463444.908772416996483.408035552461941.305152336995130.35792014
2461529.763652596994773.588292462461529.400136266994773.27333246
#Sta/Elev= 30
   -2000   432.3    1000   432.3    1914   434.2    2420     436    2420     427
    2435     427    2465   414.6  2926.5     415  3165.5   414.5    3232   413.5
  3652.5   413.6    4158     412    4167     410    4200   407.5    4222   402.5
    4247   390.8    4262   393.5 4269.29 409.451 4279.95  411.68  4310.5   411.7
    4324   413.2  4392.5   414.2    4483     412  4553.5   412.7  4614.5 411.117
 4683.95  413.51 4692.95     414 4715.14     418 4767.81     430 4779.67   431.9
#Mann= 3 ,0,0
   -2000     .08       0    4158     .05       0 4279.95     .08       0
Bank Sta=4158,4279.95
XS Rating Curve= 0 ,0
Exp/Cntr=0.5,0.3

Type RM Length L Ch R = 1 ,22474   ,93,93,93
BEGIN DESCRIPTION:
This cross section corresponds to cross section 22456 of the non-georeferenced CDC model which was the source of this model.
Right Overbank updated with 2007 levee topo.
END DESCRIPTION:
XS GIS Cut Line= 6
2466296.252193496999583.149704742465957.822253056999215.09376414
2463445.497353916996482.841107552461942.059415946995129.69814456
2461530.059583756994773.05253239 2461529.82467616994772.84912072
#Sta/Elev= 30
   -2000   432.3    1000   432.3    2398     436    2420   430.6    2420     427
    2435     427    2465   414.6  2926.5     415  3165.5   414.5    3232   413.5
  3652.5   413.6    4158     412    4167     410    4200   407.5    4222   402.5
    4247   390.8    4262   393.5 4269.29 409.451 4279.95  411.68  4310.5   411.7
    4324   413.2  4392.5   414.2    4483     412    4551   412.7  4614.5 411.117
 4692.95     414  4717.3  418.43 4739.99     424 4772.28  430.95 4779.67   431.9
#Mann= 4 ,-1,0
   -2000     .16       0    4158     .05       0    4324     .16       0
    4551     .03       0
Bank Sta=4158,4279.95
XS Rating Curve= 0 ,0
Exp/Cntr=0.3,0.1

Type RM Length L Ch R = 1 ,22381   ,170,1022,629
BEGIN DESCRIPTION:
This cross section corresponds to cross section 22356 of the non-georeferenced CDC model which was the source of this model.
Right Overbank updated with 2007 levee topo.
END DESCRIPTION:
XS GIS Cut Line= 5
2466307.205482396999563.958806072465977.621669746999187.96078687
 2464329.70260656997307.970690882463665.247898676996549.94300747
2461659.184325526994753.14246722
#Sta/Elev= 30
   -2000   447.2    1000   447.2    1130   419.4    1166   416.8    1248   427.9
    1973   427.2    2170   428.6    2200   428.1    2301   415.6    2419   417.4
    2516   414.1    2920   418.5    2981   409.4    3179   409.4    3191     414
    3210   417.9    3241   413.6    3293     413    3565   413.8    3802     411
    4138   413.2    4177   402.5    4202     391    4252   398.5    4286   411.3
    4294   411.2    4301   414.2    4423     412 4636.75     414 4701.12   431.9
#Mann= 5 ,-1,0
   -2000     .05       0    3191     .16       0    4138     .05       0
    4301     .16       0    4423     .03       0
#Block Obstruct= 2 , 0
            3191     414
Bank Sta=4138,4301
XS Rating Curve= 0 ,0
Exp/Cntr=0.3,0.1

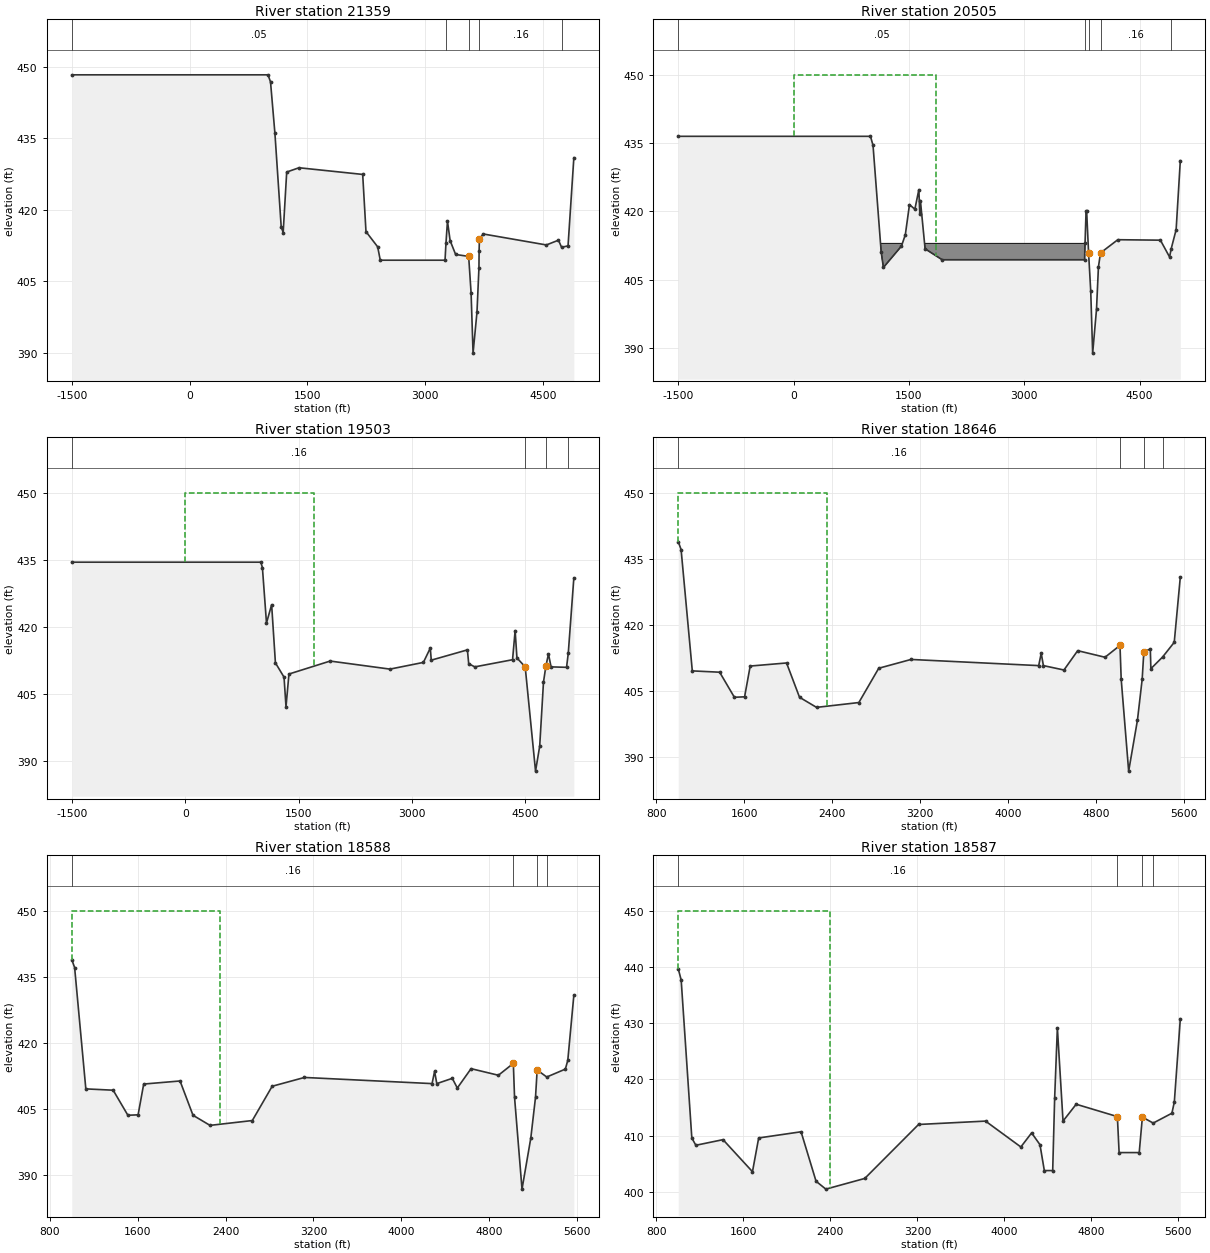
Type RM Length L Ch R = 1 ,21359   ,1251,854,220
BEGIN DESCRIPTION:
This cross section corresponds to cross section 21333 of the non-georeferenced CDC model which was the source of this model.
Right Overbank updated with 2007 levee topo.
END DESCRIPTION:
XS GIS Cut Line= 5
2466206.728350886999008.439819222464462.372288676997217.56798455
 2462835.13505766995546.938123722462930.937031336995099.86519897
2462116.145025766994351.13802189
#Sta/Elev= 30
   -1500   448.3    1000   448.3    1032   446.8    1088     436    1168   416.4
    1193   415.2    1238   427.9    1395   428.8    2206   427.4    2248   415.4
    2397   412.2    2430   409.4    3255   409.4    3267     413    3286   417.6
    3320   413.5    3390   410.6    3556   410.2    3587   402.5    3612   389.9
    3662   398.5    3687   407.8    3689   411.3    3693   413.9    3743   414.9
    4546   412.6    4700   413.6 4739.43  412.12 4822.02   412.4 4895.93   430.9
#Mann= 5 ,-1,0
   -1500     .05       0    3267     .16       0    3556     .05       0
    3693     .16       0 4739.43     .03       0
#Block Obstruct= 2 , 0
            3267     413
Bank Sta=3556,3693
XS Rating Curve= 0 ,0
Exp/Cntr=0.3,0.1

Type RM Length L Ch R = 1 ,20505   ,1099,1002,699
BEGIN DESCRIPTION:
This cross section corresponds to cross section 20480 of the non-georeferenced CDC model which was the source of this model.
Right Overbank updated with 2007 levee topo.
END DESCRIPTION:
XS GIS Cut Line= 4
2468415.272110666996180.070888352466008.458107266995503.87095264
2462686.856154686994570.659236392462243.046018666994199.47231472
#Sta/Elev= 30
   -1500   436.5    1000   436.5    1033   434.5    1139   411.1    1168   407.7
    1403   412.4    1453   414.9    1507   421.5    1577   420.5    1629   424.8
    1641   419.5    1649   422.4    1710   411.8    1932   409.4    3784   409.4
    3790     413    3803     420    3811     420    3836   410.9    3864   402.5
    3889   388.9    3939   398.5    3964   407.8    3991   410.9    4216   413.8
    4770   413.7 4889.32     410 4911.12  411.87 4974.38     416 5028.78  431.15
#Mann= 5 ,-1,0
   -1500     .05       0    3790      .1       0    3836     .05       0
    3991     .16       0 4911.12     .03       0
#XS Ineff= 2 , 0
       0    1850     450               0
Permanent Ineff=
       F       F
#Block Obstruct= 2 , 0
       0    3790     413               0
Bank Sta=3836,3991
XS Rating Curve= 0 ,0
Exp/Cntr=0.3,0.1

Type RM Length L Ch R = 1 ,19503   ,941,857,857
BEGIN DESCRIPTION:
This cross section corresponds to cross section 19477 of the non-georeferenced CDC model which was the source of this model.
Right Overbank updated with 2007 levee topo.
END DESCRIPTION:
XS GIS Cut Line= 3
2469201.277757516994050.72805524 2466703.51905316993944.89113097
2462567.770106766993769.64804313
#Sta/Elev= 30
   -1500   434.5    1000   434.5    1021   433.3    1075   420.9    1143     425
    1193     412    1307   408.8    1333   402.2    1372   409.5    1917   412.4
    2708   410.6    3150   412.1    3241   415.3    3254   412.6    3732   414.9
    3749   411.8    3830   411.1    4329   412.7    4363   419.2    4387   413.1
    4496   411.1    4633   387.8    4688   393.4    4738   407.7    4769   411.2
    4804     414    4838   411.1    5043     411 5065.63  414.13 5139.46     431
#Mann= 4 ,-1,0
   -1500     .16       0    4496    .035       0    4769     .09       0
 5065.63     .03       0
#XS Ineff= 2 , 0
       0    1700     450               0
Permanent Ineff=
       F       F
Bank Sta=4496,4769
XS Rating Curve= 0 ,0
Exp/Cntr=0.3,0.1

Type RM Length L Ch R = 1 ,18646   ,58,58,58
BEGIN DESCRIPTION:
This cross section corresponds to cross section 18621 of the non-georeferenced CDC model which was the source of this model.
Right Overbank updated with 2007 levee topo.
END DESCRIPTION:
XS GIS Cut Line= 6
2467142.067716666992691.711878812465881.004622016992774.94432388
2465468.325985436992781.417079972463377.266191186992933.72517429
2463186.99983943 6992942.16019682462581.209384356992917.82888064
#Sta/Elev= 30
    1000   438.9    1026   437.1    1128   409.5    1377   409.2    1511   403.5
    1604   403.6    1655   410.6    1986   411.3    2104   403.5    2259   401.2
    2644   402.3    2825   410.1    3119   412.1    4281   410.7    4304   413.5
    4324   410.7    4511   409.7    4636   414.1    4885   412.6    5021   415.3
    5032   407.6    5100   386.7    5180   398.3    5223   407.6    5238   413.8
    5297   414.5 5302.15     410 5408.99  412.66 5514.85     416  5570.1  430.85
#Mann= 4 ,-1,0
    1000     .16       0    5021    .035       0    5238     .09       0
 5408.99     .03       0
#XS Ineff= 2 , 0
       0    2350     450               0
Permanent Ineff=
       F       F
Bank Sta=5021,5238
XS Rating Curve= 0 ,0
Exp/Cntr=0.3,0.1

Type RM Length L Ch R = 1 ,18588   ,1,1,1
BEGIN DESCRIPTION:
This cross section corresponds to cross section 18577 of the non-georeferenced CDC model which was the source of this model.
END DESCRIPTION:
XS GIS Cut Line= 6
2467153.318022256992660.74802996 2465901.3493976 6992737.1074573
2465500.271131526992741.911253472464097.138439096992836.77523696
2463108.754261026992879.171477632462588.256614336992857.04652189
#Sta/Elev= 30
    1000   438.9    1026   437.1    1128   409.5    1377   409.2    1511   403.5
    1604   403.6    1655   410.6    1986   411.3    2104   403.5    2259   401.2
    2644   402.3    2825   410.1    3119   412.1    4281   410.7    4304   413.5
    4324   410.7    4465   411.9    4511   409.7    4636   414.1    4885   412.6
    5021   415.3    5032   407.6    5100   386.7    5180   398.3    5223   407.6
    5238   413.8 5325.22   412.2 5494.63     414 5516.96     416 5572.03   430.8
#Mann= 4 ,-1,0
    1000     .16       0    5021    .035       0    5238     .09       0
 5325.22     .03       0
#XS Ineff= 2 , 0
       0    2350     450               0
Permanent Ineff=
       F       F
Bank Sta=5021,5238
XS Rating Curve= 0 ,0
Exp/Cntr=0.3,0.1

Type RM Length L Ch R = 1 ,18587   ,5,5,5
BEGIN DESCRIPTION:
This cross section corresponds to cross section 18576 of the non-georeferenced CDC model which was the source of this model.
END DESCRIPTION:
XS GIS Cut Line= 6
2467168.62967142 6992658.07218232465924.089509586992733.17308196
2465511.603129836992736.290201722464129.732205936992833.94879904
 2463115.28016666992878.409996212462557.091322336992852.88708138
#Sta/Elev= 30
    1000   439.7    1027   437.7    1125   409.6    1162   408.3    1412   409.3
    1683   403.6    1740   409.6    2130   410.7    2268   401.9    2358   400.5
    2716   402.4    3211     412    3827   412.6    4152     408    4251   410.5
    4328   408.4    4368   403.8    4445   403.8    4463   416.7    4488   429.2
    4540   412.6    4661   415.6    5040   413.4    5056     407    5241     407
    5270   413.3 5369.71  412.25 5541.63     414 5563.96     416 5619.03   430.8
#Mann= 4 ,-1,0
    1000     .16       0    5040     .02       0    5270     .07       0
 5369.71     .03       0
#XS Ineff= 2 , 0
       0    2400     450               0
Permanent Ineff=
       F       F
Bank Sta=5040,5270
XS Rating Curve= 0 ,0
Exp/Cntr=0.3,0.1

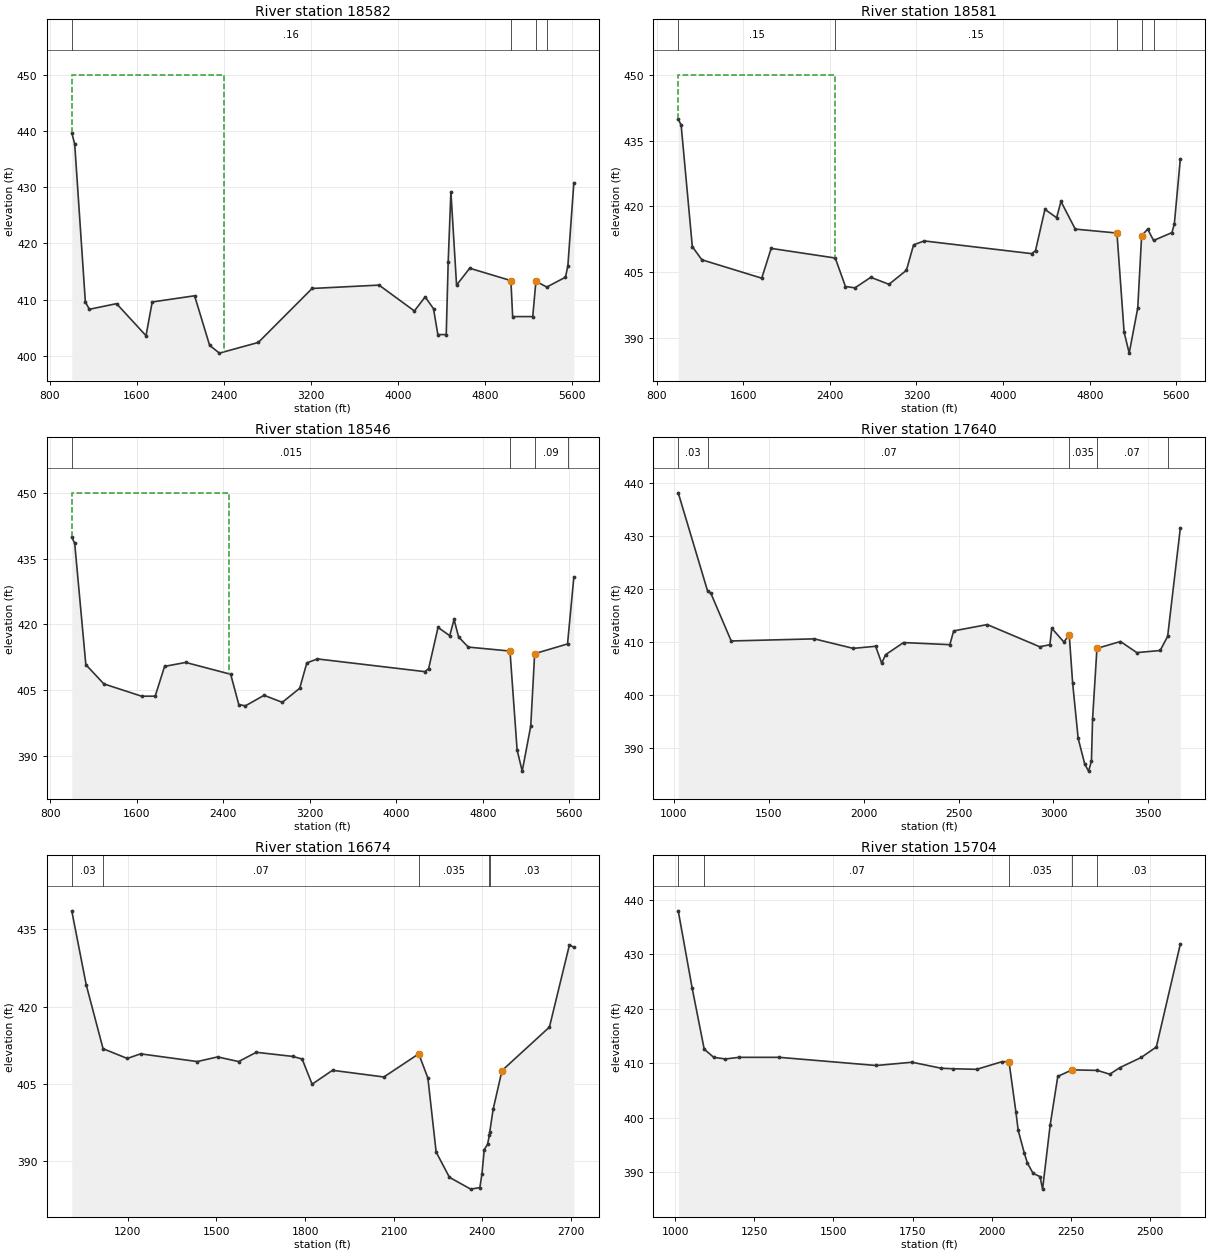
Type RM Length L Ch R = 1 ,18582   ,1,1,1
BEGIN DESCRIPTION:
This cross section corresponds to cross section 18571 of the non-georeferenced CDC model which was the source of this model.
Frasier Dam
-----------------------------------------
CDC DAL021201-1 Frasier Dam Modifications
Cross-section 18571 - 18576
-----------------------------------------
END DESCRIPTION:
Node Name=Frasier Dam
XS GIS Cut Line= 6
       2467169.3     6992644.849     2465917.426     6992725.511
     2465206.977     6992746.233     2464113.071     6992831.255
     2463114.446     6992873.398     2462558.268     6992848.167
#Sta/Elev= 30
    1000   439.7    1027   437.7    1125   409.6    1162   408.3    1412   409.3
    1683   403.6    1740   409.6    2130   410.7    2268   401.9    2358   400.5
    2716   402.4    3211     412    3827   412.6    4152     408    4251   410.5
    4328   408.4    4368   403.8    4445   403.8    4463   416.7    4488   429.2
    4540   412.6    4661   415.6    5040   413.4    5056     407    5241     407
    5270   413.3 5369.71  412.25 5541.63     414 5563.96     416 5619.03   430.8
#Mann= 4 ,-1,0
    1000     .16       0    5040     .02       0    5270     .07       0
 5369.71     .03       0
#XS Ineff= 2 , 0
       0    2400     450               0
Permanent Ineff=
       F       F
Bank Sta=5040,5270
XS Rating Curve= 0 ,0
Exp/Cntr=0.3,0.1

Type RM Length L Ch R = 1 ,18581   ,35,35,35
BEGIN DESCRIPTION:
This cross section corresponds to cross section 18570 of the non-georeferenced CDC model which was the source of this model.
END DESCRIPTION:
XS GIS Cut Line= 6
2467183.315665666992643.066634882465917.463210496992724.50774497
2465207.013844016992745.230144472464113.108223416992830.25162797
2463114.483580266992872.394916392462555.309501776992847.00914039
#Sta/Elev= 30
    1000   439.9    1027   438.5    1130   410.8    1218   407.8    1771   403.6
    1858   410.4    2450   408.2    2544   401.7    2632   401.4    2778   403.8
    2946   402.2    3107   405.4    3173   411.2    3271   412.1    4264   409.2
    4299   409.9    4386   419.3    4494   417.4    4534   421.1    4666   414.8
    5051   413.9    5117   391.3    5164   386.5    5243   396.8    5279   413.3
    5335   414.8 5389.22   412.2 5558.63     414 5580.96     416 5636.03   430.8
#Mann= 5 ,-1,0
    1000     .15       0    2450     .15       0    5051    .035       0
    5279     .09       0 5389.22     .03       0
#XS Ineff= 2 , 0
       0    2450     450               0
Permanent Ineff=
       F       F
Bank Sta=5051,5279
XS Rating Curve= 0 ,0
Exp/Cntr=0.3,0.1

Type RM Length L Ch R = 1 ,18546   ,960,906,906
BEGIN DESCRIPTION:
This cross section corresponds to cross section 18521 of the non-georeferenced CDC model which was the source of this model.
Right Overbank updated with 2007 levee topo.
END DESCRIPTION:
XS GIS Cut Line= 6
2467182.491848416992602.669405972465445.249259926992680.86642805
2464236.476415016992774.954494462463214.511923496992840.84182988
2463187.191112016992842.053113552462549.376114676992813.51970606
#Sta/Elev= 30
    1000   439.9    1027   438.5    1130   410.8    1297   406.4    1645   403.6
    1771   403.6    1858   410.4    2053   411.3    2469   408.6    2544   401.7
    2605   401.4    2778   403.8    2946   402.2    3107   405.4    3173   411.2
    3271   412.1    4264   409.2    4299   409.9    4386   419.3    4494   417.4
    4534   421.1    4576   417.1    4666   414.8    5051   413.9    5117   391.3
    5164   386.5    5243   396.8    5279   413.3 5582.95  415.52 5641.32  430.78
#Mann= 4 ,-1,0
    1000    .015       0    5051    .035       0    5279     .09       0
 5582.95     .03       0
#XS Ineff= 2 , 0
       0    2450     450               0
Permanent Ineff=
       F       F
Bank Sta=5051,5279
XS Rating Curve= 0 ,0
Exp/Cntr=0.3,0.1

Type RM Length L Ch R = 1 ,17640   ,1000,966,950
BEGIN DESCRIPTION:
This cross section corresponds to cross section 17615 of the non-georeferenced CDC model which was the source of this model.
Right Overbank updated with 2007 levee topo.
END DESCRIPTION:
XS GIS Cut Line= 3
2465185.311131516991762.060850962463278.727346246991915.61730239
 2462547.4738875 6991957.5086228
#Sta/Elev= 30
    1023   438.2    1178   419.6    1195   419.2    1302   410.2    1740   410.6
    1945   408.8    2063   409.2    2095     406    2115   407.6    2210   409.9
    2454   409.5    2474   412.1    2651   413.3    2928   409.1    2981   409.5
    2991   412.6    3055     410    3083   411.4    3101   402.2    3130   391.8
    3165   386.9    3185   385.6    3200   387.5    3206   395.5    3229   408.8
    3353   410.1    3439     408    3562   408.4  3601.4  411.06 3668.21  431.52
#Mann= 5 ,-1,0
    1023     .03       0    1178     .07       0    3083    .035       0
    3229     .07       0  3601.4     .03       0
Bank Sta=3083,3229
XS Rating Curve= 0 ,0
Exp/Cntr=0.3,0.1

Type RM Length L Ch R = 1 ,16674   ,1049,970,849
BEGIN DESCRIPTION:
This cross section corresponds to cross section 16649 of the non-georeferenced CDC model which was the source of this model.
Proposed grading for levee overbank.
Right Overbank updated with 2007 levee topo.
END DESCRIPTION:
XS GIS Cut Line= 3
2464321.024146176990841.184739962463571.845526436990923.54153064
2462628.231600026990998.89964764
#Sta/Elev= 30
    1010   438.6    1059   424.2    1116   411.8    1198   409.9    1243   410.8
    1435   409.3    1504   410.2    1575   409.3    1635   411.1    1758   410.3
    1790   409.8    1824   404.9    1893   407.6    2067   406.3    2185   410.8
    2216   406.1    2244   391.7    2289   386.8    2361   384.5    2392   384.8
    2399   387.4    2407   392.2    2418   393.2  2424.2  394.96 2425.34  395.54
 2436.94     400    2467  407.55 2627.64     416 2695.44     432 2710.31  431.49
#Mann= 5 ,-1,0
    1010     .03       0    1116     .07       0    2185    .035       0
  2424.2     .07       0 2425.34     .03       0
Bank Sta=2185,2467
XS Rating Curve= 0 ,0
Exp/Cntr=0.3,0.1

Type RM Length L Ch R = 1 ,15704   ,1061,1031,851
BEGIN DESCRIPTION:
This cross section corresponds to cross section 15678 of the non-georeferenced CDC model which was the source of this model.
Proposed grading for levee overbank.
Right Overbank updated with 2007 levee topo.
END DESCRIPTION:
XS GIS Cut Line= 2
2464147.013667436989630.166492722462670.037946856990204.54624946
#Sta/Elev= 30
    1010     438    1054   423.8    1092   412.6    1122   411.1    1159   410.8
    1202   411.1    1329   411.1    1635   409.6    1748   410.2    1840   409.1
    1878     409    1952   408.9    2032   410.3    2054   410.3    2076     401
    2083   397.7    2102   393.6    2112   391.7    2130   389.8    2152   389.2
    2160   386.9    2184   398.7    2208   407.6    2253   408.8    2333   408.7
 2372.06     408 2404.04  409.22 2471.15  411.07 2519.11     413 2594.73  431.89
#Mann= 5 ,-1,0
    1010     .03       0    1092     .07       0    2054    .035       0
    2253     .07       0    2333     .03       0
Bank Sta=2054,2253
XS Rating Curve= 0 ,0
Exp/Cntr=0.3,0.1