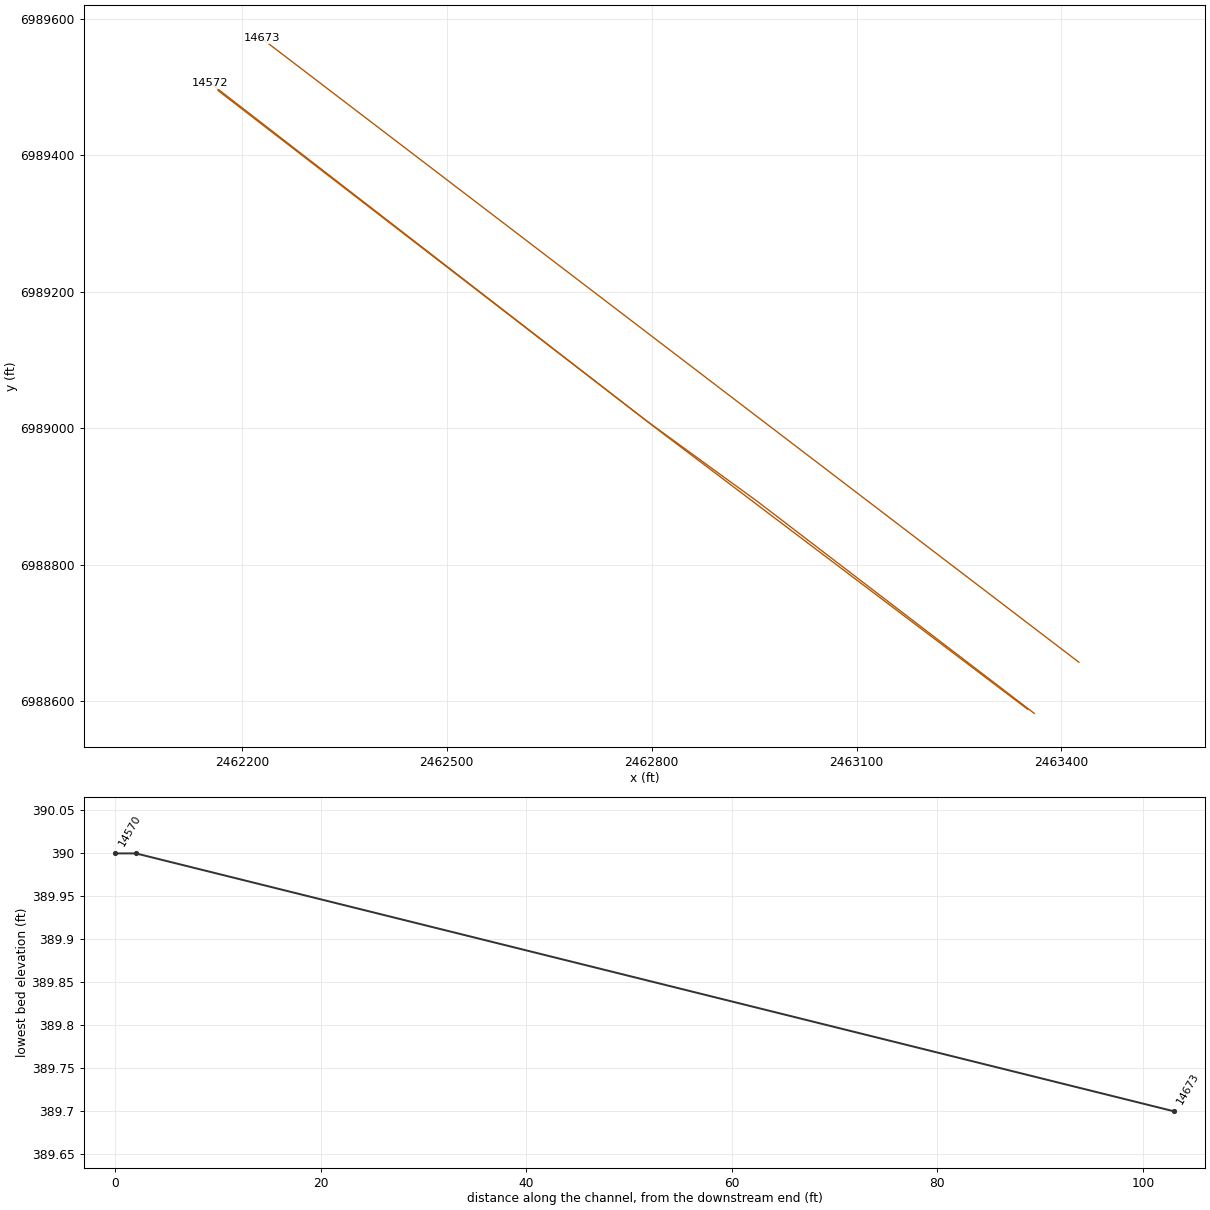
HEC-RAS study CDC_Consolidated_Model.prj: Upper Trinity CDC Consolidated Model

--- CDC_Consolidated_Model.g04 (geometry) --- (continued)

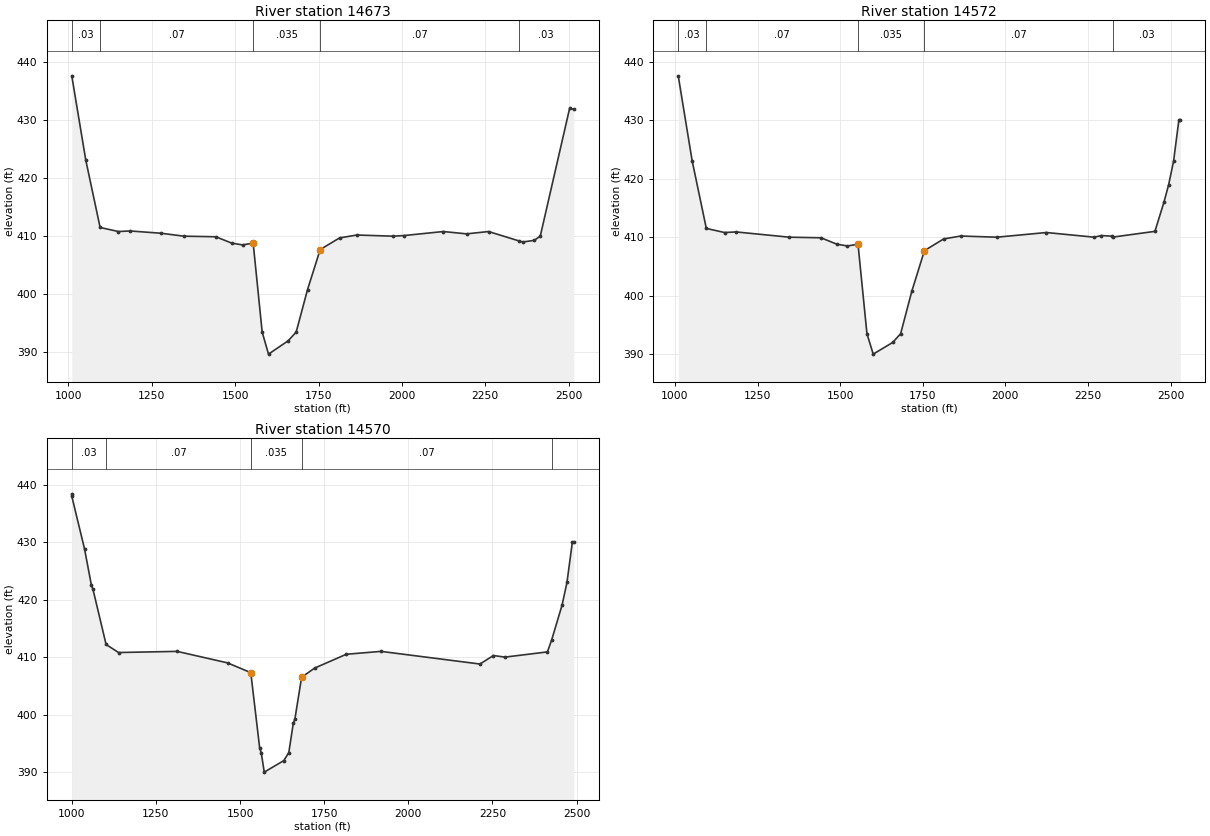
Type RM Length L Ch R = 1 ,14673   ,101,101,101
BEGIN DESCRIPTION:
This cross section corresponds to cross section 14648 of the non-georeferenced CDC model which was the source of this model.
Proposed grading for levee overbank.
Right Overbank updated with 2007 levee topo.
END DESCRIPTION:
XS GIS Cut Line= 2
 2463425.48033366988657.478477462462228.986007426989571.50453655
#Sta/Elev= 30
    1010   437.6    1052   423.1    1095   411.5    1150   410.8    1185   410.9
    1279   410.5    1346     410    1442   409.9    1490   408.8    1522   408.5
    1554   408.8    1581   393.5    1600   389.7    1659     392    1683   393.5
    1717   400.8    1755   407.7    1813   409.7    1865   410.2    1974     410
    2005   410.1    2124   410.8    2194   410.4 2259.93   410.8  2349.7  409.21
 2362.59     409 2396.68  409.28 2414.94     410 2502.98     432 2515.67  431.83
#Mann= 5 ,-1,0
    1010     .03       0    1095     .07       0    1554    .035       0
    1755     .07       0  2349.7     .03       0
Bank Sta=1554,1755
XS Rating Curve= 0 ,0
Exp/Cntr=0.3,0.1

Type RM Length L Ch R = 1 ,14572   ,2,2,2
BEGIN DESCRIPTION:
This cross section corresponds to cross section 14545 of the non-georeferenced CDC model which was the source of this model.
Proposed grading for levee overbank.
Right Overbank updated with 2007 levee topo.
END DESCRIPTION:
XS GIS Cut Line= 4
2463360.138600776988582.560976392462954.787377336988893.08528972
2462792.263096096989011.351457392462153.760764186989505.91542888
#Sta/Elev= 30
    1010   437.6    1052   423.1    1095   411.5    1150   410.8    1185   410.9
    1346     410    1442   409.9    1490   408.8    1522   408.5    1554   408.8
    1581   393.5    1600     390    1659     392    1683   393.5    1717   400.8
    1755   407.7    1813   409.7    1865   410.2    1974     410    2124   410.8
    2269     410 2290.21  410.28 2321.22  410.18 2324.22  410.01 2452.44     411
 2479.83     416 2494.05     419 2508.87     423 2524.81     430 2529.26     430
#Mann= 5 ,-1,0
    1010     .03       0    1095     .07       0    1554    .035       0
    1755     .07       0 2324.22     .03       0
Bank Sta=1554,1755
XS Rating Curve= 0 ,0
Exp/Cntr=0.5,0.3

Type RM Length L Ch R = 1 ,14570   ,135,135,135
BEGIN DESCRIPTION:
This cross section corresponds to cross section 14544 of the non-georeferenced CDC model which was the source of this model.
Proposed grading for levee overbank.
Right Overbank updated with 2007 levee topo.
END DESCRIPTION:
XS GIS Cut Line= 3
2463350.542163256988588.547184882462811.876245836988996.14610721
2462165.39886427 6989494.9682723
#Sta/Elev= 30
    1000   438.4    1000     438    1038   428.8  1058.5 422.464    1063   421.8
    1102   412.2    1139   410.8    1313     411    1463     409    1532   407.3
  1558.5  394.15    1563   393.4    1572     390    1630     392    1645   393.4
  1658.5  398.57    1663   399.2    1683   406.5    1722   408.1    1816   410.5
    1919     411    2213   408.8    2253  410.28 2287.25     410 2413.57  410.91
 2426.17     413 2456.84     419 2471.66     423  2487.6     430 2492.05     430
#Mann= 5 ,-1,0
    1000     .03       0    1102     .07       0    1532    .035       0
    1683     .07       0 2426.17     .03       0
Bank Sta=1532,1683
XS Rating Curve= 0 ,0
Exp/Cntr=0.5,0.3