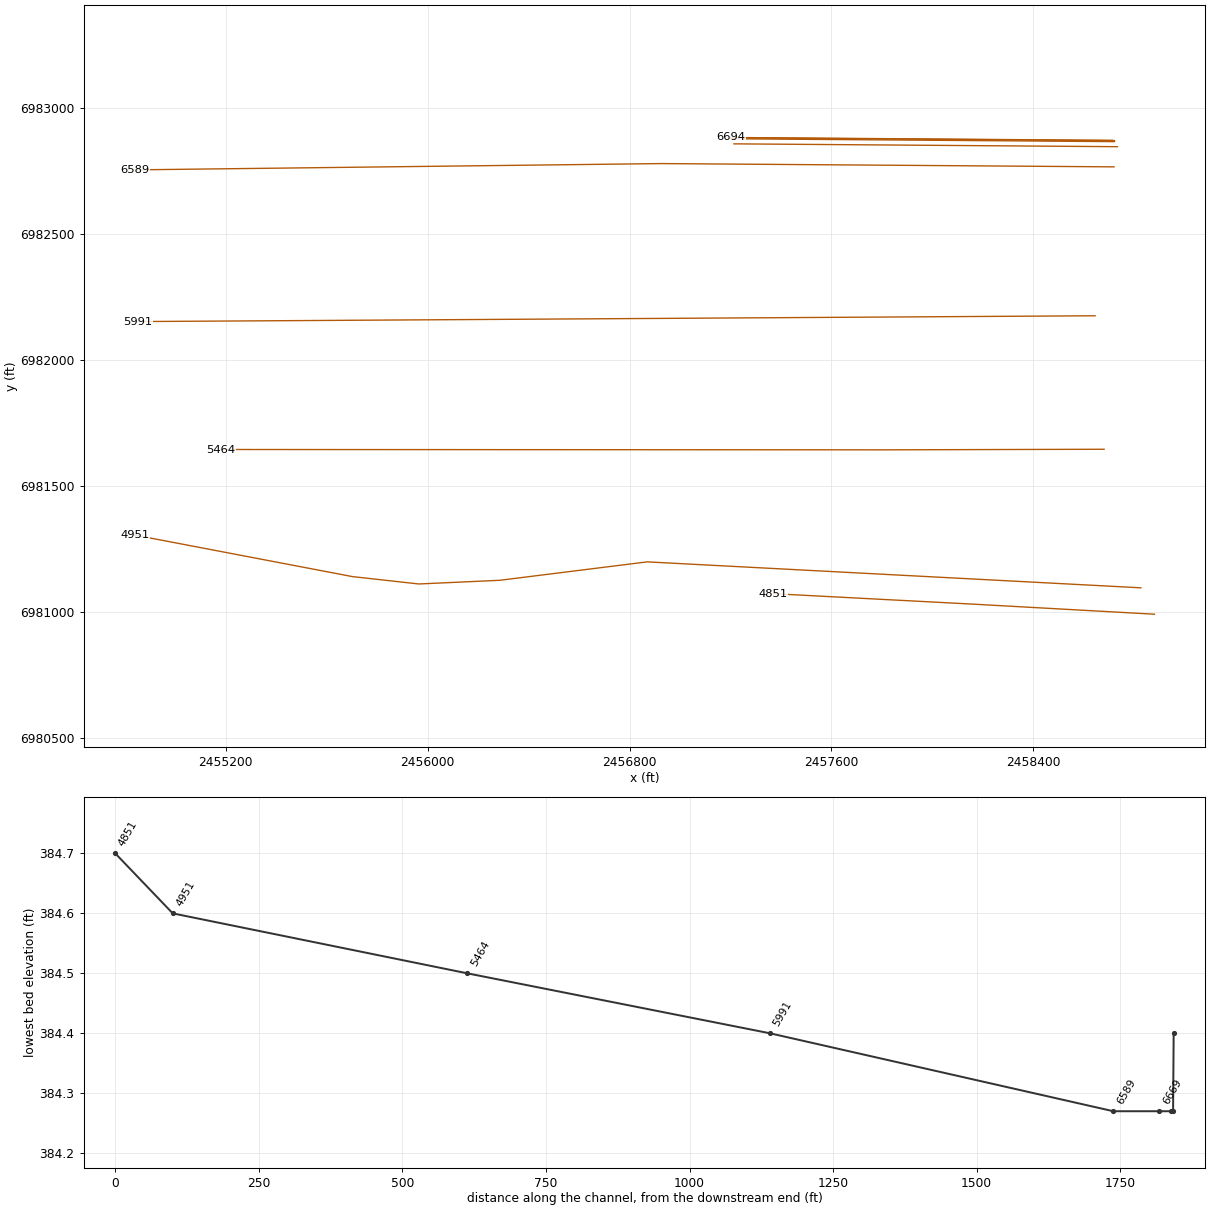
HEC-RAS study CDC_Consolidated_Model.prj: Upper Trinity CDC Consolidated Model

--- CDC_Consolidated_Model.g04 (geometry) --- (continued)

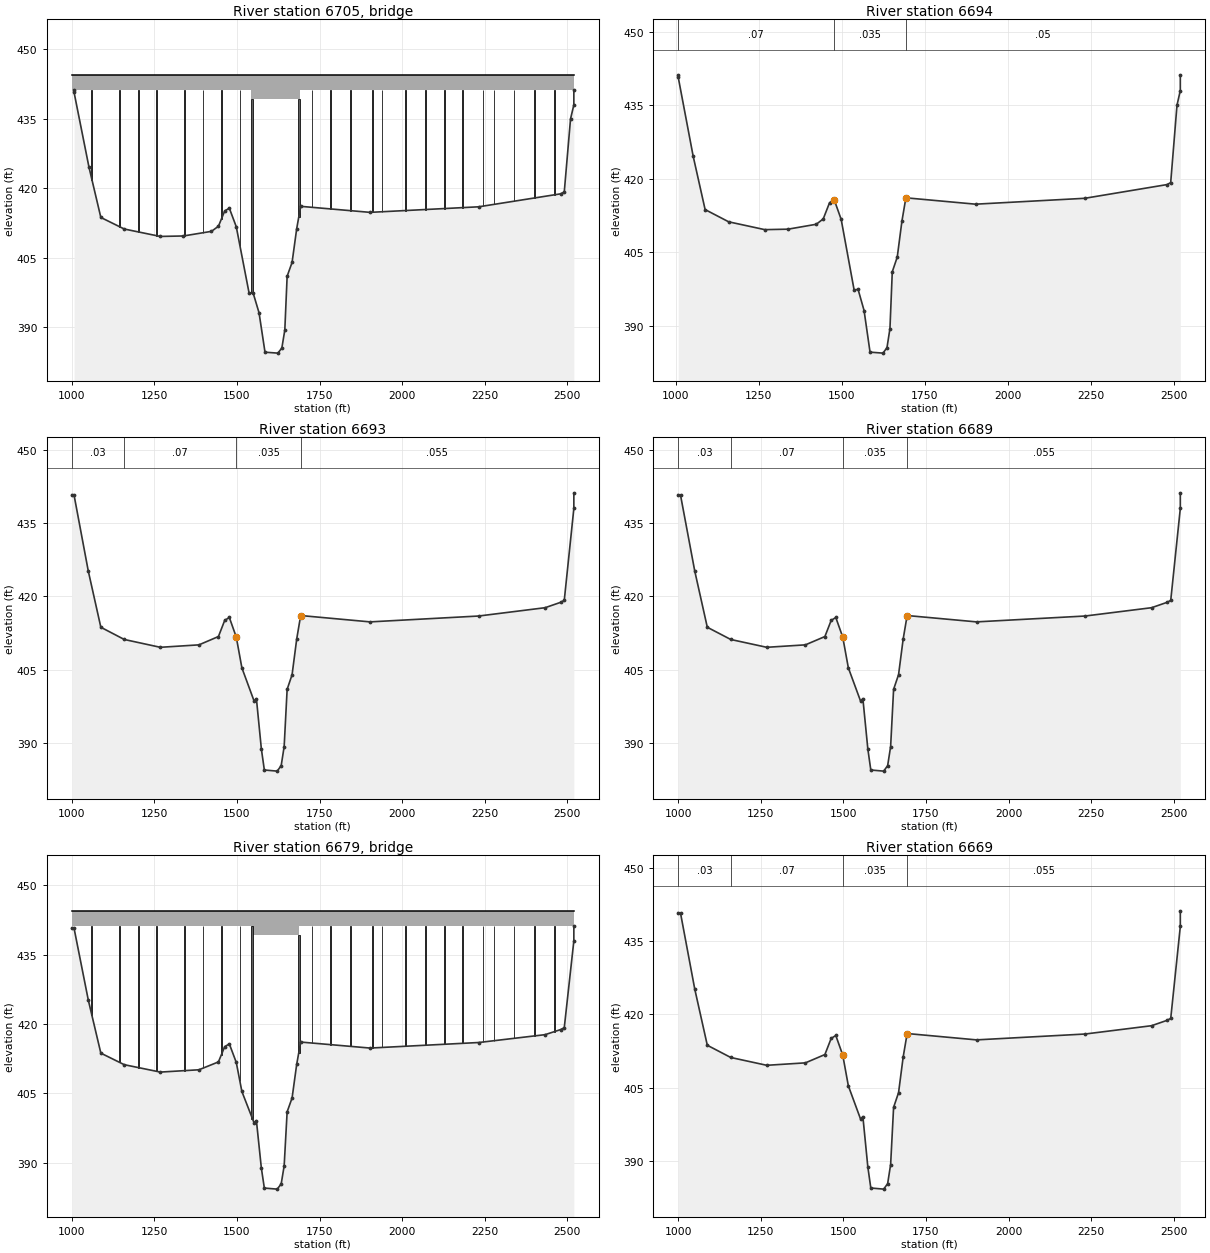
Type RM Length L Ch R = 3 ,6705    ,,,
BEGIN DESCRIPTION:
Burlington Northen Sante Fe Railroad
END DESCRIPTION:
Node Name=BNSF RR
Bridge Culvert--1,0,-1,-1, 0
Deck Dist Width WeirC Skew NumUp NumDn MinLoCord MaxHiCord MaxSubmerge Is_Ogee
1,19,2.6,0, 53, 53, , , 0.95, 0, 0,0,,
    1000    1007    1048    1052    1146    1154    1296    1304    1348    1352
    1398    1402    1448    1452  1489.5  1490.5  1519.5  1520.5  1526.5    1544
    1544    1617    1690    1690  1724.5  1725.5  1739.5  1740.5    1788    1792
    1848    1852    1898    1902    1958    1962    1998    2002    2048    2052
    2148    2152    2256    2264    2298    2302    2426    2434    2468    2472
    2489    2491    2520
   444.5   444.5   444.5   444.5   444.5   444.5   444.5   444.5   444.5   444.5
   444.5   444.5   444.5   444.5   444.5   444.5   444.5   444.5   444.5   444.5
   444.5   444.5   444.5   444.5   444.5   444.5   444.5   444.5   444.5   444.5
   444.5   444.5   444.5   444.5   444.5   444.5   444.5   444.5   444.5   444.5
   444.5   444.5   444.5   444.5   444.5   444.5   444.5   444.5   444.5   444.5
   444.5   444.5   444.5
   441.2   441.2   441.2   441.2   441.2   441.2   441.2   441.2   441.2   441.2
   441.2   441.2   441.2   441.2   441.2   441.2   441.2   441.2   441.2   441.2
   439.3   439.3   439.3   441.2   441.2   441.2   441.2   441.2   441.2   441.2
   441.2   441.2   441.2   441.2   441.2   441.2   441.2   441.2   441.2   441.2
   441.2   441.2   441.2   441.2   441.2   441.2   441.2   441.2   441.2   441.2
   441.2   441.2   441.2
    1000    1007    1048    1052    1146    1154    1296    1304    1348    1352
    1398    1402    1448    1452  1489.5  1490.5  1519.5  1520.5  1526.5    1544
    1544    1617    1690    1690  1724.5  1725.5  1739.5  1740.5    1788    1792
    1848    1852    1898    1902    1958    1962    1998    2002    2048    2052
    2148    2152    2256    2264    2298    2302    2426    2434    2468    2472
    2489    2491    2520
   444.5   444.5   444.5   444.5   444.5   444.5   444.5   444.5   444.5   444.5
   444.5   444.5   444.5   444.5   444.5   444.5   444.5   444.5   444.5   444.5
   444.5   444.5   444.5   444.5   444.5   444.5   444.5   444.5   444.5   444.5
   444.5   444.5   444.5   444.5   444.5   444.5   444.5   444.5   444.5   444.5
   444.5   444.5   444.5   444.5   444.5   444.5   444.5   444.5   444.5   444.5
   444.5   444.5   444.5
   441.2   441.2   441.2   441.2   441.2   441.2   441.2   441.2   441.2   441.2
   441.2   441.2   441.2   441.2   441.2   441.2   441.2   441.2   441.2   441.2
   439.3   439.3   439.3   441.2   441.2   441.2   441.2   441.2   441.2   441.2
   441.2   441.2   441.2   441.2   441.2   441.2   441.2   441.2   441.2   441.2
   441.2   441.2   441.2   441.2   441.2   441.2   441.2   441.2   441.2   441.2
   441.2   441.2   441.2
Pier Skew, UpSta & Num, DnSta & Num=  ,1061, 2 ,10613.5, 2 , 0 , 0 , 0 ,,
     3.5     3.5
       0     442
     3.5     3.5
       0     442
Pier Skew, UpSta & Num, DnSta & Num=  ,1145, 2 ,1145, 2 , 0 , 0 , 0 ,,
     3.5     3.5
       0     442
     3.5     3.5
       0     442
Pier Skew, UpSta & Num, DnSta & Num=  ,1201, 2 ,1201, 2 , 0 , 0 , 0 ,,
    2.34    2.34
       0     442
    2.34    2.34
       0     442
Pier Skew, UpSta & Num, DnSta & Num=  ,1257, 2 ,1257, 2 , 0 , 0 , 0 ,,
     3.5     3.5
       0     442
     3.5     3.5
       0     442
Pier Skew, UpSta & Num, DnSta & Num=  ,1341, 2 ,1341, 2 , 0 , 0 , 0 ,,
     3.5     3.5
       0     442
     3.5     3.5
       0     442
Pier Skew, UpSta & Num, DnSta & Num=  ,1397, 2 ,1397, 2 , 0 , 0 , 0 ,,
    2.34    2.34
       0     442
    2.34    2.34
       0     442
Pier Skew, UpSta & Num, DnSta & Num=  ,1453, 2 ,1453, 2 , 0 , 0 , 0 ,,
     3.5     3.5
       0     442
     3.5     3.5
       0     442
Pier Skew, UpSta & Num, DnSta & Num=  ,1509, 2 ,1509, 2 , 0 , 0 , 0 ,,
    1.17    1.17
       0     442
    1.17    1.17
       0     442
Pier Skew, UpSta & Num, DnSta & Num=  ,1547, 2 ,1547, 2 , 0 , 0 , 0 ,,
       6       6
       0     442
       6       6
       0     442
Pier Skew, UpSta & Num, DnSta & Num=  ,1687, 2 ,1687, 2 , 0 , 0 , 0 ,,
       6       6
       0     442
       6       6
       0     442
Pier Skew, UpSta & Num, DnSta & Num=  ,1728, 2 ,1728, 2 , 0 , 0 , 0 ,,
    1.17    1.17
       0     442
    1.17    1.17
       0     442
Pier Skew, UpSta & Num, DnSta & Num=  ,1784, 2 ,1784, 2 , 0 , 0 , 0 ,,
     3.5     3.5
       0     442
     3.5     3.5
       0     442
Pier Skew, UpSta & Num, DnSta & Num=  ,1845, 2 ,1845, 2 , 0 , 0 , 0 ,,
    2.34    2.34
       0     442
    2.34    2.34
       0     442
Pier Skew, UpSta & Num, DnSta & Num=  ,1911, 2 ,1911, 2 , 0 , 0 , 0 ,,
    2.34    2.34
       0     442
    2.34    2.34
       0     442
Pier Skew, UpSta & Num, DnSta & Num=  ,1939, 2 ,1939, 2 , 0 , 0 , 0 ,,
    2.34    2.34
       0     442
    2.34    2.34
       0     442
Pier Skew, UpSta & Num, DnSta & Num=  ,2011, 2 ,2011, 2 , 0 , 0 , 0 ,,
    2.34    2.34
       0     442
    2.34    2.34
       0     442
Pier Skew, UpSta & Num, DnSta & Num=  ,2072, 2 ,2072, 2 , 0 , 0 , 0 ,,
     3.5     3.5
       0     442
     3.5     3.5
       0     442
Pier Skew, UpSta & Num, DnSta & Num=  ,2128, 2 ,2128, 2 , 0 , 0 , 0 ,,
    2.34    2.34
       4     442
    2.34    2.34
       4     442
Pier Skew, UpSta & Num, DnSta & Num=  ,2184, 2 ,2184, 2 , 0 , 0 , 0 ,,
    2.34    2.34
       4     442
    2.34    2.34
       4     442
Pier Skew, UpSta & Num, DnSta & Num=  ,2245, 2 ,2245, 2 , 0 , 0 , 0 ,,
    2.34    2.34
       4     442
    2.34    2.34
       4     442
Pier Skew, UpSta & Num, DnSta & Num=  ,2278, 2 ,2278, 2 , 0 , 0 , 0 ,,
    2.34    2.34
       4     442
    2.34    2.34
       4     442
Pier Skew, UpSta & Num, DnSta & Num=  ,2339, 2 ,2339, 2 , 0 , 0 , 0 ,,
    2.34    2.34
       4     442
    2.34    2.34
       4     442
Pier Skew, UpSta & Num, DnSta & Num=  ,2400, 2 ,2400, 2 , 0 , 0 , 0 ,,
    2.34    2.34
       4     442
    2.34    2.34
       4     442
Pier Skew, UpSta & Num, DnSta & Num=  ,2461, 2 ,24613.54, 2 , 0 , 0 , 0 ,,
     3.5     3.5
       4     442
     3.5     3.5
       4     442
BR Coef=-1 , 0 , 0 ,1.05, 0 ,,,0.8,-1,0.5,0,
WSPro=,,,, 1 ,,,, 0 ,,,, 0 ,,,,-1 ,-1 ,-1 , 0 , 0 , 0 , 0 , 0
BC Design=,, 0 ,, 0 ,,,,,,
BC Use User HTab Curves=0
BC User HTab FreeFlow(D)= 0

Type RM Length L Ch R = 1 ,6694    ,1,1,1
BEGIN DESCRIPTION:
This cross section corresponds to cross section 6668 of the non-georeferenced CDC model which was the source of this model.
END DESCRIPTION:
XS GIS Cut Line= 2
      2458714.85     6982869.982     2457201.766       6982881.3
#Sta/Elev= 30
    1007   441.2    1007   440.7    1052  424.59    1088   413.7    1159   411.2
    1268   409.6    1338   409.7    1423   410.7    1444   411.8    1463   415.1
    1477   415.7    1498   411.7    1537   397.3    1549   397.4    1567   393.1
    1585   384.6    1624   384.4    1636   385.5    1645   389.4    1652     401
    1667     404    1681   411.3    1693   416.1    1903   414.8    2232     416
    2480   418.8    2491   419.2    2510     435    2520     438    2520   441.2
#Mann= 3 ,0,0
    1007     .07       0    1477    .035       0    1693     .05       0
Bank Sta=1477,1693
XS Rating Curve= 0 ,0
Exp/Cntr=0.5,0.3

Type RM Length L Ch R = 1 ,6693    ,4,4,4
BEGIN DESCRIPTION:
This cross section corresponds to cross section 6663 of the non-georeferenced CDC model which was the source of this model.
END DESCRIPTION:
XS GIS Cut Line= 2
 2458721.95791656982868.929030972457201.95144209 6982880.2807143
#Sta/Elev= 30
    1000   440.8    1007   440.7    1050   425.2    1088   413.7    1159   411.2
    1268   409.6    1385   410.1    1444   411.8    1463   415.1    1477   415.7
    1498   411.7    1515   405.4    1552   398.6    1559   399.1    1574   388.8
    1583   384.5    1622  384.27    1634   385.4    1643   389.3    1652     401
    1667     404    1681   411.3    1693   416.1    1903   414.8    2232     416
    2433   417.7    2480   418.8    2491   419.2    2520     438    2520   441.2
#Mann= 4 ,-1,0
    1000     .03       0    1159     .07       0    1498    .035       0
    1693    .055       0
Bank Sta=1498,1693
XS Rating Curve= 0 ,0
Exp/Cntr=0.3,0.1

Type RM Length L Ch R = 1 ,6689    ,20,20,20
BEGIN DESCRIPTION:
This cross section corresponds to cross section 6663 of the non-georeferenced CDC model which was the source of this model.
END DESCRIPTION:
XS GIS Cut Line= 2
2458721.842103096982864.93166363 2457201.89435566982876.24299271
#Sta/Elev= 30
    1000   440.8    1007   440.7    1050   425.2    1088   413.7    1159   411.2
    1268   409.6    1385   410.1    1444   411.8    1463   415.1    1477   415.7
    1498   411.7    1515   405.4    1552   398.6    1559   399.1    1574   388.8
    1583   384.5    1622  384.27    1634   385.4    1643   389.3    1652     401
    1667     404    1681   411.3    1693   416.1    1903   414.8    2232     416
    2433   417.7    2480   418.8    2491   419.2    2520     438    2520   441.2
#Mann= 4 ,-1,0
    1000     .03       0    1159     .07       0    1498    .035       0
    1693    .055       0
Bank Sta=1498,1693
XS Rating Curve= 0 ,0
Exp/Cntr=0.5,0.3

Type RM Length L Ch R = 3 ,6679    ,,,
BEGIN DESCRIPTION:
Burlington Northern Sante Fe Railroad
END DESCRIPTION:
Node Name=BNSF RR
Bridge Culvert--1,0,-1,-1, 0
Deck Dist Width WeirC Skew NumUp NumDn MinLoCord MaxHiCord MaxSubmerge Is_Ogee
0.5,19,2.6,0, 52, 52, , , 0.95, 0, 0,0,,
    1000    1048    1052    1146    1154    1296    1304    1348    1352    1398
    1402    1448    1452  1489.5  1490.5  1519.5  1520.5  1526.5    1547    1547
    1617    1687    1687  1724.5  1725.5  1739.5  1740.5    1788    1792    1848
    1852    1898    1902    1958    1962    1998    2002    2048    2052    2148
    2152    2256    2264    2298    2302    2426    2434    2468    2472    2489
    2491    2520
   444.5   444.5   444.5   444.5   444.5   444.5   444.5   444.5   444.5   444.5
   444.5   444.5   444.5   444.5   444.5   444.5   444.5   444.5   444.5   444.5
   444.5   444.5   444.5   444.5   444.5   444.5   444.5   444.5   444.5   444.5
   444.5   444.5   444.5   444.5   444.5   444.5   444.5   444.5   444.5   444.5
   444.5   444.5   444.5   444.5   444.5   444.5   444.5   444.5   444.5   444.5
   444.5   444.5
   441.2   441.2   441.2   441.2   441.2   441.2   441.2   441.2   441.2   441.2
   441.2   441.2   441.2   441.2   441.2   441.2   441.2   441.2   441.2   439.3
   439.3   439.3   441.2   441.2   441.2   441.2   441.2   441.2   441.2   441.2
   441.2   441.2   441.2   441.2   441.2   441.2   441.2   441.2   441.2   441.2
   441.2   441.2   441.2   441.2   441.2   441.2   441.2   441.2   441.2   441.2
   441.2   441.2
    1000    1048    1052    1146    1154    1296    1304    1348    1352    1398
    1402    1448    1452  1489.5  1490.5  1519.5  1520.5  1526.5    1547    1547
    1617    1687    1687  1724.5  1725.5  1739.5  1740.5    1788    1792    1848
    1852    1898    1902    1958    1962    1998    2002    2048    2052    2148
    2152    2256    2264    2298    2302    2426    2434    2468    2472    2489
    2491    2520
   444.5   444.5   444.5   444.5   444.5   444.5   444.5   444.5   444.5   444.5
   444.5   444.5   444.5   444.5   444.5   444.5   444.5   444.5   444.5   444.5
   444.5   444.5   444.5   444.5   444.5   444.5   444.5   444.5   444.5   444.5
   444.5   444.5   444.5   444.5   444.5   444.5   444.5   444.5   444.5   444.5
   444.5   444.5   444.5   444.5   444.5   444.5   444.5   444.5   444.5   444.5
   444.5   444.5
   441.2   441.2   441.2   441.2   441.2   441.2   441.2   441.2   441.2   441.2
   441.2   441.2   441.2   441.2   441.2   441.2   441.2   441.2   441.2   439.3
   439.3   439.3   441.2   441.2   441.2   441.2   441.2   441.2   441.2   441.2
   441.2   441.2   441.2   441.2   441.2   441.2   441.2   441.2   441.2   441.2
   441.2   441.2   441.2   441.2   441.2   441.2   441.2   441.2   441.2   441.2
   441.2   441.2
Pier Skew, UpSta & Num, DnSta & Num=  ,1061, 2 ,1061, 2 , 0 , 0 , 0 ,,
     3.5     3.5
       0     442
     3.5     3.5
       0     442
Pier Skew, UpSta & Num, DnSta & Num=  ,1145, 2 ,1145, 2 , 0 , 0 , 0 ,,
     3.5     3.5
       0     442
     3.5     3.5
       0     442
Pier Skew, UpSta & Num, DnSta & Num=  ,1201, 2 ,1201, 2 , 0 , 0 , 0 ,,
    2.34    2.34
       0     442
    2.34    2.34
       0     442
Pier Skew, UpSta & Num, DnSta & Num=  ,1257, 2 ,12573.5, 2 , 0 , 0 , 0 ,,
     3.5     3.5
       0     442
     3.5     3.5
       0     442
Pier Skew, UpSta & Num, DnSta & Num=  ,1341, 2 ,1341, 2 , 0 , 0 , 0 ,,
     3.5     3.5
       0     442
     3.5     3.5
       0     442
Pier Skew, UpSta & Num, DnSta & Num=  ,1397, 2 ,1397, 2 , 0 , 0 , 0 ,,
    2.34    2.34
       0     442
    2.34    2.34
       0     442
Pier Skew, UpSta & Num, DnSta & Num=  ,1453, 2 ,1453, 2 , 0 , 0 , 0 ,,
     3.5     3.5
       0     442
     3.5     3.5
       0     442
Pier Skew, UpSta & Num, DnSta & Num=  ,1509, 2 ,1509, 2 , 0 , 0 , 0 ,,
    1.17    1.17
       0     442
    1.17    1.17
       0     442
Pier Skew, UpSta & Num, DnSta & Num=  ,1547, 2 ,1547, 2 , 0 , 0 , 0 ,,
       6       6
       0     442
       6       6
       0     442
Pier Skew, UpSta & Num, DnSta & Num=  ,1687, 2 ,1687, 2 , 0 , 0 , 0 ,,
       6       6
       0     442
       6       6
       0     442
Pier Skew, UpSta & Num, DnSta & Num=  ,1728, 2 ,1728, 2 , 0 , 0 , 0 ,,
    1.17    1.17
       0     442
    1.17    1.17
       0     442
Pier Skew, UpSta & Num, DnSta & Num=  ,1784, 2 ,1784, 2 , 0 , 0 , 0 ,,
     3.5     3.5
       0     442
     3.5     3.5
       0     442
Pier Skew, UpSta & Num, DnSta & Num=  ,1845, 2 ,1845, 2 , 0 , 0 , 0 ,,
    2.34    2.34
       0     442
    2.34    2.34
       0     442
Pier Skew, UpSta & Num, DnSta & Num=  ,1911, 2 ,1911, 2 , 0 , 0 , 0 ,,
    2.34    2.34
       0     442
    2.34    2.34
       0     442
Pier Skew, UpSta & Num, DnSta & Num=  ,1939, 2 ,1939, 2 , 0 , 0 , 0 ,,
    2.34    2.34
       0     442
    2.34    2.34
       0     442
Pier Skew, UpSta & Num, DnSta & Num=  ,2011, 2 ,2011, 2 , 0 , 0 , 0 ,,
    2.34    2.34
       0     442
    2.34    2.34
       0     442
Pier Skew, UpSta & Num, DnSta & Num=  ,2072, 2 ,2072, 2 , 0 , 0 , 0 ,,
     3.5     3.5
       0     442
     3.5     3.5
       0     442
Pier Skew, UpSta & Num, DnSta & Num=  ,2128, 2 ,2128, 2 , 0 , 0 , 0 ,,
    2.34    2.34
       0     442
    2.34    2.34
       0     442
Pier Skew, UpSta & Num, DnSta & Num=  ,2184, 2 ,2184, 2 , 0 , 0 , 0 ,,
    2.34    2.34
       0     442
    2.34    2.34
       0     442
Pier Skew, UpSta & Num, DnSta & Num=  ,2245, 2 ,2245, 2 , 0 , 0 , 0 ,,
    2.34    2.34
       0     442
    2.34    2.34
       0     442
Pier Skew, UpSta & Num, DnSta & Num=  ,2278, 2 ,2278, 2 , 0 , 0 , 0 ,,
    2.34    2.34
       0     442
    2.34    2.34
       0     442
Pier Skew, UpSta & Num, DnSta & Num=  ,2339, 2 ,2339, 2 , 0 , 0 , 0 ,,
    2.34    2.34
       0     442
    2.34    2.34
       0     442
Pier Skew, UpSta & Num, DnSta & Num=  ,2400, 2 ,2400, 2 , 0 , 0 , 0 ,,
    2.34    2.34
       0     442
    2.34    2.34
       0     442
Pier Skew, UpSta & Num, DnSta & Num=  ,2461, 2 ,2461, 2 , 0 , 0 , 0 ,,
     3.5     3.5
       0     442
     3.5     3.5
       0     442
BR Coef=-1 , 0 , 0 ,1.05, 0 ,,,0.8,-1,0.5,0,
WSPro=,,,, 1 ,,,, 0 ,,,, 0 ,,,,-1 ,-1 ,-1 , 0 , 0 , 0 , 0 , 0
BC Design=,, 0 ,, 0 ,,,,,,
BC Use User HTab Curves=0
BC User HTab FreeFlow(D)= 0

Type RM Length L Ch R = 1 ,6669    ,80,80,80
BEGIN DESCRIPTION:
This cross section corresponds to cross section 6643 of the non-georeferenced CDC model which was the source of this model.
---------------------------
CDC IRV092399-1 BNSF Bridge
CROSS-SECTION 6643 - 6689
---------------------------
END DESCRIPTION:
XS GIS Cut Line= 2
2458733.769572686982844.843121132457213.812966916982856.12689121
#Sta/Elev= 30
    1000   440.8    1007   440.7    1050   425.2    1088   413.7    1159   411.2
    1268   409.6    1385   410.1    1444   411.8    1463   415.1    1477   415.7
    1498   411.7    1515   405.4    1552   398.6    1559   399.1    1574   388.8
    1583   384.5    1622  384.27    1634   385.4    1643   389.3    1652     401
    1667     404    1681   411.3    1693   416.1    1903   414.8    2232     416
    2433   417.7    2480   418.8    2491   419.2    2520     438    2520   441.2
#Mann= 4 ,-1,0
    1000     .03       0    1159     .07       0    1498    .035       0
    1693    .055       0
Bank Sta=1498,1693
XS Rating Curve= 0 ,0
Exp/Cntr=0.5,0.3

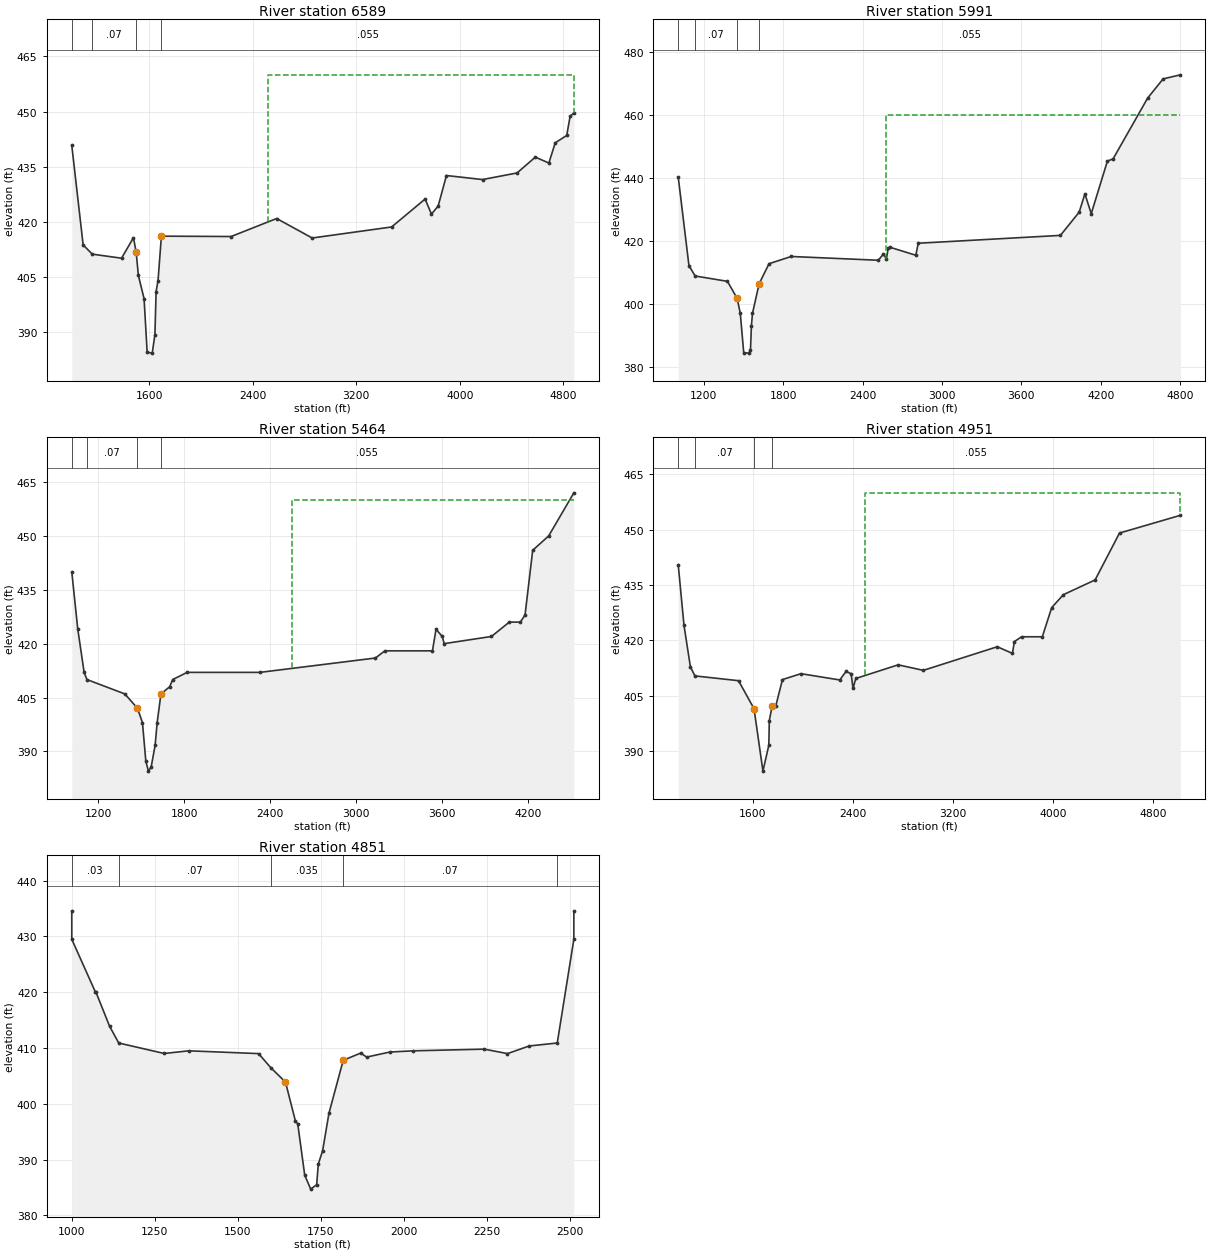
Type RM Length L Ch R = 1 ,6589    ,598,598,598
BEGIN DESCRIPTION:
This cross section corresponds to cross section 6563 of the non-georeferenced CDC model which was the source of this model.
END DESCRIPTION:
XS GIS Cut Line= 3
2458720.327014276982764.951220562456926.186901756982777.93413422
2454838.522770026982753.02407905
#Sta/Elev= 30
    1000   440.8    1088   413.7    1159   411.2    1385   410.1    1477   415.7
    1498   411.7    1515   405.4    1559   399.1    1583   384.5    1622  384.27
    1643   389.3    1652     401    1667     404    1693   416.1    2232     416
    2584   420.9    2859   415.6    3473   418.6    3732   426.2    3781   422.1
    3833   424.3    3897   432.6    4176   431.5    4443   433.3    4584   437.6
    4689     436    4738   441.5    4827   443.5    4853   448.7    4882   449.6
#Mann= 4 ,-1,0
    1000     .03       0    1159     .07       0    1498    .035       0
    1693    .055       0
#XS Ineff= 2 , 0
       0                    2520       0     460
Permanent Ineff=
       F       F
Bank Sta=1498,1693
XS Rating Curve= 0 ,0
Exp/Cntr=0.3,0.1

Type RM Length L Ch R = 1 ,5991    ,527,527,527
BEGIN DESCRIPTION:
This cross section corresponds to cross section 5965 of the non-georeferenced CDC model which was the source of this model.
END DESCRIPTION:
XS GIS Cut Line= 2
2458645.244159166982174.781797222454851.314083016982151.77790621
#Sta/Elev= 30
    1007   440.3    1088   412.2    1135   408.9    1379   407.2    1452   401.8
    1476     397    1502   384.5    1541   384.4    1553   385.4    1560   393.1
    1568     397    1618   406.4    1693   412.8    1861   415.1    2519   413.9
    2558   415.9    2580   414.3    2594   417.8    2609     418    2802   415.5
    2821   419.3    3895   421.8    4037   429.2    4080     435    4128   428.7
    4250   445.4    4293   446.1    4554   465.4    4671   471.5    4801   472.8
#Mann= 4 ,-1,0
    1007     .03       0    1135     .07       0    1452    .035       0
    1618    .055       0
#XS Ineff= 2 , 0
       0                    2580       0     460
Permanent Ineff=
       F       F
Bank Sta=1452,1618
XS Rating Curve= 0 ,0
Exp/Cntr=0.3,0.1

Type RM Length L Ch R = 1 ,5464    ,513,513,513
BEGIN DESCRIPTION:
This cross section corresponds to cross section 5438 of the non-georeferenced CDC model which was the source of this model.
END DESCRIPTION:
XS GIS Cut Line= 3
2458680.768366346981645.731346132457814.093918596981643.43902788
2455179.271432346981644.76120372
#Sta/Elev= 30
  1016.6     440  1058.6     424  1102.8     412  1122.4     410  1386.6     406
  1474.9     402  1509.7     398    1533   387.3    1551   384.5    1570   385.6
    1598   391.7    1612     398  1638.7     406  1699.4     408  1720.4     410
  1821.3     412  2328.6     412  3134.5     416  3200.3     418    3532     418
    3557     424  3600.7     422  3613.6     420  3943.5     422    4068     426
  4144.9     426  4177.8     428  4231.2     446  4342.6     450  4518.1     462
#Mann= 4 ,-1,0
  1016.6     .03       0  1122.4     .07       0  1474.9    .035       0
  1638.7    .055       0
#XS Ineff= 2 , 0
       0                    2550       0     460
Permanent Ineff=
       F       F
Bank Sta=1474.9,1638.7
XS Rating Curve= 0 ,0
Exp/Cntr=0.3,0.1

Type RM Length L Ch R = 1 ,4951    ,100,100,100
BEGIN DESCRIPTION:
This cross section corresponds to cross section 4925 of the non-georeferenced CDC model which was the source of this model.
END DESCRIPTION:
XS GIS Cut Line= 6
2458826.461316446981096.603179312456870.079074356981199.42416789
2456286.012985266981126.415127552455964.778063426981111.81410688
2455701.947880426981141.01713246 2454838.2396341 6981305.8271703
#Sta/Elev= 30
    1006   440.5    1052   424.1    1103   412.9    1139   410.4    1488   409.1
    1612   401.5    1683   384.6    1730   391.6    1734   398.3    1757   402.3
    1786   402.3    1839   409.4    1987     411    2297   409.3    2347   411.6
    2388     411    2403     407    2425   409.7    2764   413.4    2965   411.9
    3556   418.3    3677   416.5    3693   419.7    3750     421    3916     421
    3991   428.9    4084   432.4    4338   436.4    4533   449.1    5019   453.9
#Mann= 4 ,-1,0
    1006     .03       0    1139     .07       0    1612    .035       0
    1757    .055       0
#XS Ineff= 2 , 0
       0                    2500       0     460
Permanent Ineff=
       F       F
Bank Sta=1612,1757
XS Rating Curve= 0 ,0
Exp/Cntr=0.3,0.1

Type RM Length L Ch R = 1 ,4851    ,62,62,62
BEGIN DESCRIPTION:
This cross section corresponds to cross section 4826 of the non-georeferenced CDC model which was the source of this model.
END DESCRIPTION:
XS GIS Cut Line= 3
2458880.24992275 6980991.97149882458152.950196276981032.34608996
2457369.44356117 6981073.3768478
#Sta/Elev= 30
    1000   434.6    1000   429.5  1071.5     420    1073     420    1114   413.9
  1141.5   410.9  1278.5 409.022    1353   409.5    1563     409 1599.77 406.469
    1644   403.9    1674   396.9    1681   396.4    1702   387.2    1720   384.7
    1738   385.5    1743   389.2    1756   391.6    1775   398.3    1818   407.8
    1871   409.1  1888.5 408.375  1958.5  409.28  2028.5 409.496    2243   409.8
    2313     409  2378.5 410.369    2463   410.9    2513   429.5    2513   434.5
#Mann= 5 ,-1,0
    1000     .03       0  1141.5     .07       0 1599.77    .035       0
    1818     .07       0    2463     .03       0
Bank Sta=1644,1818
XS Rating Curve= 0 ,0
Exp/Cntr=0.5,0.3