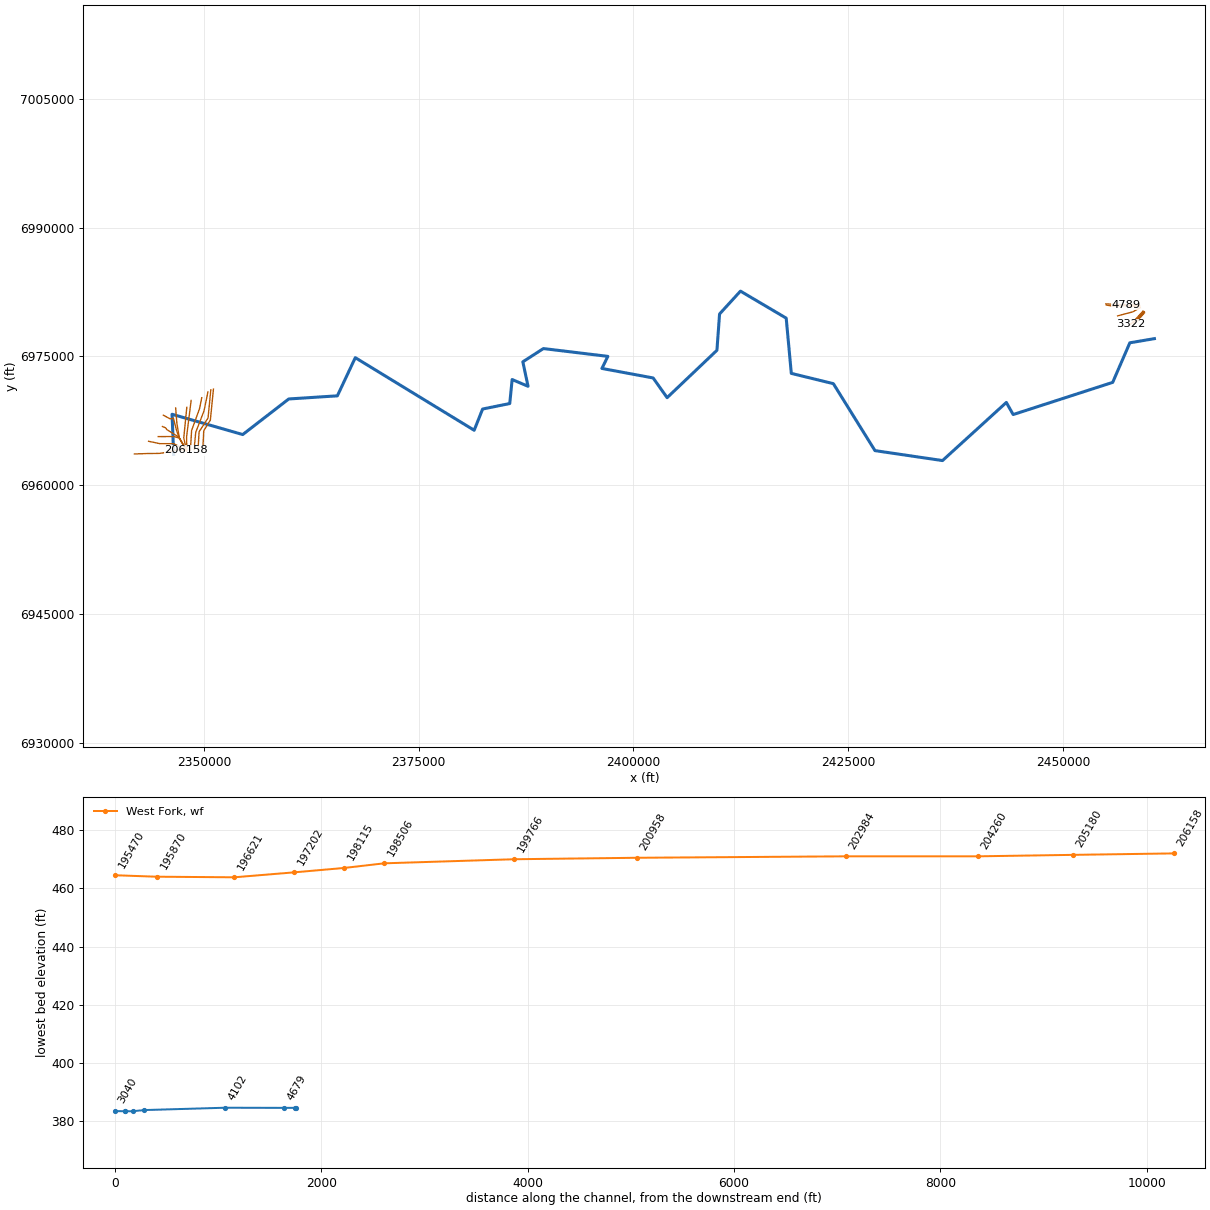
HEC-RAS study CDC_Consolidated_Model.prj: Upper Trinity CDC Consolidated Model

--- CDC_Consolidated_Model.g04 (geometry) --- (continued)

Type RM Length L Ch R = 3 ,4820    ,,,
BEGIN DESCRIPTION:
SH 356/Irving Boulevard
END DESCRIPTION:
Node Name=SH 356/Irving Bl
Bridge Culvert--1,0,-1,-1, 0
Deck Dist Width WeirC Skew NumUp NumDn MinLoCord MaxHiCord MaxSubmerge Is_Ogee
2,59,2.6,0, 44, 44, , , 0.95, 0, ,,,
    1000  1068.5  1071.5  1138.5  1141.5  1208.5  1211.5  1278.5  1281.5  1348.5
  1351.5  1418.5  1421.5  1488.5  1491.5  1558.5  1561.5  1561.5 1628.25 1631.75
 1748.25 1751.75  1818.5  1821.5  1821.5  1888.5  1891.5  1958.5  1961.5  2028.5
  2031.5  2098.5  2101.5  2168.5  2171.5  2238.5  2241.5  2308.5  2311.5  2378.5
  2381.5  2448.5  2451.5    2513
   440.6 440.698 440.702 440.798 440.802 440.898 440.902 440.998 441.002 441.098
 441.102 441.198 441.202 441.298 441.302 441.398   441.4   441.4   441.4   441.4
   441.4   441.4   441.4   441.4   441.4 441.402 441.396 441.204 441.198 441.102
 441.098 441.002 440.998 440.902 440.896 440.704 440.699 440.651 440.649 440.601
 440.598 440.502   440.5   440.5
   434.6 434.698 434.702 434.798 434.802 434.898 434.902 434.998 435.002 435.098
 435.102 435.198 435.202 435.298 435.302 435.398   435.4   434.5   434.5   434.5
   434.5   434.5   434.5  434.52   435.5 435.402 435.396 435.204 435.198 435.102
 435.098 435.002 434.998 434.902 434.896 434.704 434.699 434.651 434.649 434.601
 434.598 434.502   434.5   434.5
    1000  1068.5  1071.5  1138.5  1141.5  1208.5  1211.5  1278.5  1281.5  1348.5
  1351.5  1418.5  1421.5  1488.5  1491.5  1558.5  1561.5  1561.5 1628.25 1631.75
 1748.25 1751.75  1818.5  1821.5  1821.5  1888.5  1891.5  1958.5  1961.5  2028.5
  2031.5  2098.5  2101.5  2168.5  2171.5  2238.5  2241.5  2308.5  2311.5  2378.5
  2381.5  2448.5  2451.5    2513
   440.6 440.698 440.702 440.798 440.802 440.898 440.902 440.998 441.002 441.098
 441.102 441.198 441.202 441.298 441.302 441.398   441.4   441.4   441.4   441.4
   441.4   441.4   441.4   441.4   441.4 441.402 441.396 441.204 441.198 441.102
 441.098 441.002 440.998 440.902 440.896 440.704 440.699 440.651 440.649 440.601
 440.598 440.502   440.5   440.5
   434.6 434.698 434.702 434.798 434.802 434.898 434.902 434.998 435.002 435.098
 435.102 435.198 435.202 435.298 435.302 435.398   435.4   434.5   434.5   434.5
   434.5   434.5   434.5  434.52   435.5 435.402 435.396 435.204 435.198 435.102
 435.098 435.002 434.998 434.902 434.896 434.704 434.699 434.651 434.649 434.601
 434.598 434.502   434.5   434.5
Pier Skew, UpSta & Num, DnSta & Num=  ,1070, 2 ,1070, 2 , 0 , 0 , 0 ,,
       3       3
       0     440
       3       3
       0     440
Pier Skew, UpSta & Num, DnSta & Num=  ,1140, 2 ,1140, 2 , 0 , 0 , 0 ,,
       3       3
       0     440
       3       3
       0     440
Pier Skew, UpSta & Num, DnSta & Num=  ,1210, 2 ,1210, 2 , 0 , 0 , 0 ,,
       3       3
       0     440
       3       3
       0     440
Pier Skew, UpSta & Num, DnSta & Num=  ,1280, 2 ,1280, 2 , 0 , 0 , 0 ,,
       3       3
       0     440
       3       3
       0     440
Pier Skew, UpSta & Num, DnSta & Num=  ,1350, 2 ,1350, 2 , 0 , 0 , 0 ,,
       3       3
       0     440
       3       3
       0     440
Pier Skew, UpSta & Num, DnSta & Num=  ,1420, 2 ,1420, 2 , 0 , 0 , 0 ,,
       3       3
       0     440
       3       3
       0     440
Pier Skew, UpSta & Num, DnSta & Num=  ,1490, 2 ,1490, 2 , 0 , 0 , 0 ,,
       3       3
       0     440
       3       3
       0     440
Pier Skew, UpSta & Num, DnSta & Num=  ,1560, 2 ,1560, 2 , 0 , 0 , 0 ,,
       3       3
       0     440
       3       3
       0     440
Pier Skew, UpSta & Num, DnSta & Num=  ,1630, 2 ,1630, 2 , 0 , 0 , 0 ,,
       3       3
       0     440
       3       3
       0     440
Pier Skew, UpSta & Num, DnSta & Num=  ,1750, 2 ,1750, 2 , 0 , 0 , 0 ,,
       3       3
       0     440
       3       3
       0     440
Pier Skew, UpSta & Num, DnSta & Num=  ,1820, 2 ,1820, 2 , 0 , 0 , 0 ,,
       3       3
       0     440
       3       3
       0     440
Pier Skew, UpSta & Num, DnSta & Num=  ,1890, 2 ,1890, 2 , 0 , 0 , 0 ,,
       3       3
       0     440
       3       3
       0     440
Pier Skew, UpSta & Num, DnSta & Num=  ,1960, 2 ,1960, 2 , 0 , 0 , 0 ,,
       3       3
       0     440
       3       3
       0     440
Pier Skew, UpSta & Num, DnSta & Num=  ,2030, 2 ,2030, 2 , 0 , 0 , 0 ,,
       3       3
       0     440
       3       3
       0     440
Pier Skew, UpSta & Num, DnSta & Num=  ,2100, 2 ,2100, 2 , 0 , 0 , 0 ,,
       3       3
       0     440
       3       3
       0     440
Pier Skew, UpSta & Num, DnSta & Num=  ,2170, 2 ,2170, 2 , 0 , 0 , 0 ,,
       3       3
       0     440
       3       3
       0     440
Pier Skew, UpSta & Num, DnSta & Num=  ,2240, 2 ,2240, 2 , 0 , 0 , 0 ,,
       3       3
       0     440
       3       3
       0     440
Pier Skew, UpSta & Num, DnSta & Num=  ,2310, 2 ,2310, 2 , 0 , 0 , 0 ,,
       3       3
       0     440
       3       3
       0     440
Pier Skew, UpSta & Num, DnSta & Num=  ,2380, 2 ,2380, 2 , 0 , 0 , 0 ,,
       3       3
       3     440
       3       3
       3     440
Pier Skew, UpSta & Num, DnSta & Num=  ,2450, 2 ,2450, 2 , 0 , 0 , 0 ,,
       3       3
       3     440
       3       3
       3     440
BR Coef= 1 , 0 , 0 ,1.05, 0 ,,,0.8,-1,0.5,1,
WSPro=,,,, 1 ,,,, 0 ,,,, 0 ,,,,-1 ,-1 ,-1 , 0 , 0 , 0 , 0 , 0
BC Design=,, 0 ,, 0 ,,,,,,
BC HTab HWMax=434.6
BC Use User HTab Curves=0
BC User HTab FreeFlow(D)= 0

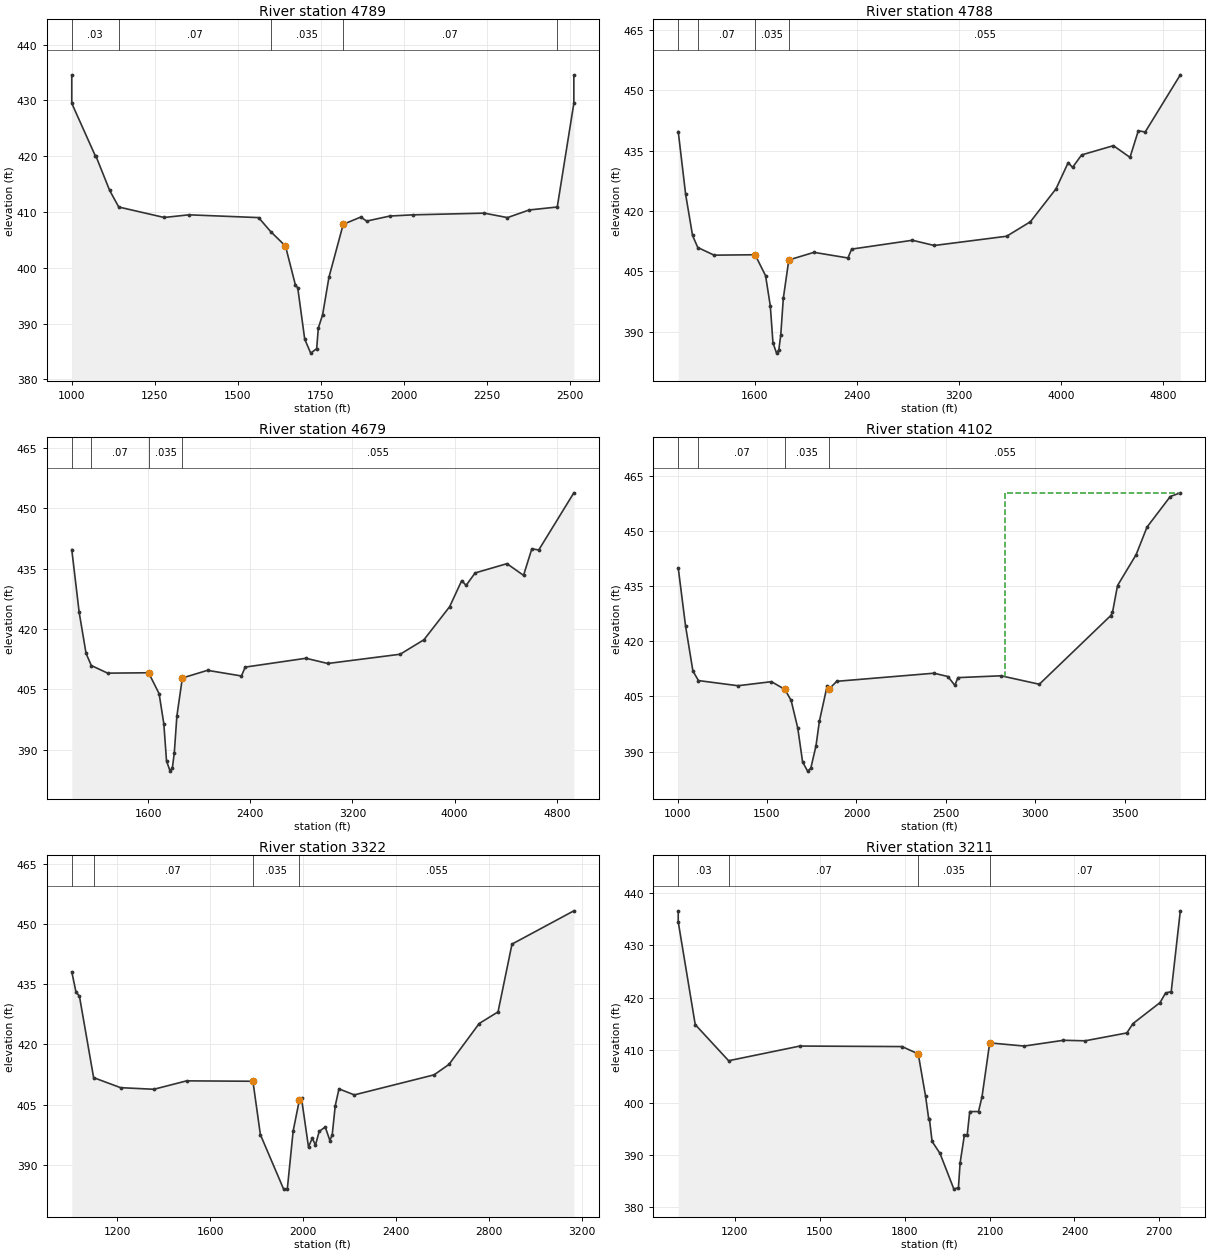
Type RM Length L Ch R = 1 ,4789    ,1,1,1
BEGIN DESCRIPTION:
This cross section corresponds to cross section 4760 of the non-georeferenced CDC model which was the source of this model.
END DESCRIPTION:
XS GIS Cut Line= 3
  2458876.860493 6980928.6740532  2458155.764167  6980970.027317
 2457366.0223082 6981009.3195612
#Sta/Elev= 30
    1000   434.6    1000   429.5  1071.5     420    1073     420    1114   413.9
  1141.5   410.9  1278.5 409.022    1353   409.5    1563     409 1599.77 406.469
    1644   403.9    1674   396.9    1681   396.4    1702   387.2    1720   384.7
    1738   385.5    1743   389.2    1756   391.6    1775   398.3    1818   407.8
    1871   409.1  1888.5 408.375  1958.5  409.28  2028.5 409.496    2243   409.8
    2313     409  2378.5 410.369    2463   410.9    2513   429.5    2513   434.5
#Mann= 5 ,-1,0
    1000     .03       0  1141.5     .07       0 1599.77    .035       0
    1818     .07       0    2463     .03       0
Bank Sta=1644,1818
XS Rating Curve= 0 ,0
Exp/Cntr=0.5,0.3

Type RM Length L Ch R = 1 ,4788    ,109,109,109
BEGIN DESCRIPTION:
This cross section corresponds to cross section 4759 of the non-georeferenced CDC model which was the source of this model.
END DESCRIPTION:
XS GIS Cut Line= 4
2458926.217350516980923.890270132458155.827815186980969.03191213
2457350.472470496981007.818908052454999.197799566981121.05945667
#Sta/Elev= 30
    1002   439.7    1060   424.1    1114   413.9    1155   410.9    1283     409
    1604   409.1    1686   403.9    1723   396.4    1744   387.2    1772  384.66
    1790   385.5    1805   389.2    1825   398.3    1868   407.8    2065   409.7
    2331   408.3    2360   410.5    2836   412.7    3007   411.4    3574   413.7
    3760   417.3    3961   425.5    4056     432    4090   430.8    4161   433.9
    4410   436.2    4540   433.3    4605   439.9    4659   439.6    4934   453.8
#Mann= 4 ,-1,0
    1002     .03       0    1155     .07       0    1604    .035       0
    1868    .055       0
Bank Sta=1604,1868
XS Rating Curve= 0 ,0
Exp/Cntr=0.3,0.1

Type RM Length L Ch R = 1 ,4679    ,400,577,750
BEGIN DESCRIPTION:
This cross section corresponds to cross section 4653 of the non-georeferenced CDC model which was the source of this model.
END DESCRIPTION:
XS GIS Cut Line= 6
  2458949.899717 6980819.7608852 2456986.8918328 6980921.9929642
 2456359.0220256 6980863.5859288  2455993.981089 6980834.3832313
 2455716.5498853 6980863.5859288 2455038.4892336 6980994.4856014
#Sta/Elev= 30
    1002   439.7    1060   424.1    1114   413.9    1155   410.9    1283     409
    1604   409.1    1686   403.9    1723   396.4    1744   387.2    1772  384.66
    1790   385.5    1805   389.2    1825   398.3    1868   407.8    2065   409.7
    2331   408.3    2360   410.5    2836   412.7    3007   411.4    3574   413.7
    3760   417.3    3961   425.5    4056     432    4090   430.8    4161   433.9
    4410   436.2    4540   433.3    4605   439.9    4659   439.6    4934   453.8
#Mann= 4 ,-1,0
    1002     .03       0    1155     .07       0    1604    .035       0
    1868    .055       0
Bank Sta=1604,1868
XS Rating Curve= 0 ,0
Exp/Cntr=0.3,0.1

Type RM Length L Ch R = 1 ,4102    ,649,780,899
BEGIN DESCRIPTION:
This cross section corresponds to cross section 4076 of the non-georeferenced CDC model which was the source of this model.
END DESCRIPTION:
XS GIS Cut Line= 3
     2458989.484      6980666.39     2458129.345     6980192.919
     2456366.582     6979723.647
#Sta/Elev= 30
    1004   439.9    1045   424.1    1086   411.9    1117   409.3    1338   407.9
    1525     409    1600   406.9    1635   403.9    1672   396.4    1699   387.2
    1727   384.7    1745   385.5    1774   391.6    1793   398.3    1836   407.8
    1849   407.1    1890   409.1    2433   411.3    2511   410.4    2550     408
    2567   410.1    2808   410.6    3022   408.3    3420   426.9    3431   427.8
    3459   435.1    3563   443.5    3624     451    3754   459.3    3810   460.3
#Mann= 4 ,-1,0
    1004     .03       0    1117     .07       0    1600    .035       0
    1849    .055       0
#XS Ineff= 3 ,-1
    1004    1600   406.9    1849    2830   407.1    2830    3810   460.3
Permanent Ineff=
       F       F       F
Bank Sta=1600,1849
XS Rating Curve= 0 ,0
Exp/Cntr=0.3,0.1

Type RM Length L Ch R = 1 ,3322    ,111,111,111
BEGIN DESCRIPTION:
This cross section corresponds to cross section 3295 of the non-georeferenced CDC model which was the source of this model.
END DESCRIPTION:
XS GIS Cut Line= 3
  2459323.422264 6980282.2186532 2458096.3180917 6978935.6580261
  2457835.823862 6978721.5636381
#Sta/Elev= 30
    1005   438.1    1023   433.1    1038     432    1099   411.7    1215   409.2
    1358   408.8    1499   410.9    1784   410.8    1816   397.5    1916   383.9
    1932     384    1957   398.4    1984   406.2    1993   406.5    2023   394.4
    2039   396.6    2053   394.9    2069   398.3    2095   399.4    2115     396
    2125   397.5    2138   404.7    2154   408.9    2220   407.4    2563   412.4
    2627     415    2757   425.2    2838   428.1    2898     445    3164   453.3
#Mann= 4 ,-1,0
    1005     .03       0    1099     .07       0    1784    .035       0
    1984    .055       0
#Block Obstruct= 2 , 0
                            1993           406.5
Bank Sta=1784,1984
XS Rating Curve= 0 ,0
Exp/Cntr=0.3,0.1

Type RM Length L Ch R = 1 ,3211    ,71,71,71
BEGIN DESCRIPTION:
This cross section corresponds to cross section 3190 of the non-georeferenced CDC model which was the source of this model.
END DESCRIPTION:
XS GIS Cut Line= 3
2459425.753424916980231.53830838 2458789.85541856979535.99278347
2458230.308309266978920.82012931
#Sta/Elev= 30
    1000   436.5    1000   434.5    1060   414.9    1178     408    1430   410.8
 1790.75   410.7    1848   409.3    1874   401.2    1885   396.9  1887.5   396.9
    1897   392.6    1925   390.3    1974   383.5    1990   383.8    1996   388.5
    2011   393.8    2021   393.8    2030   398.3    2061   398.3 2073.25 401.084
  2100.5   411.4  2222.5   410.8 2361.25   411.9  2437.5   411.8    2585   413.3
    2607   415.1  2702.5   419.1  2721.7   420.9  2741.9   421.2    2774   436.6
#Mann= 4 ,-1,0
    1000     .03       0    1178     .07       0    1848    .035       0
  2100.5     .07       0
Bank Sta=1848,2100.5
XS Rating Curve= 0 ,0
Exp/Cntr=0.5,0.3

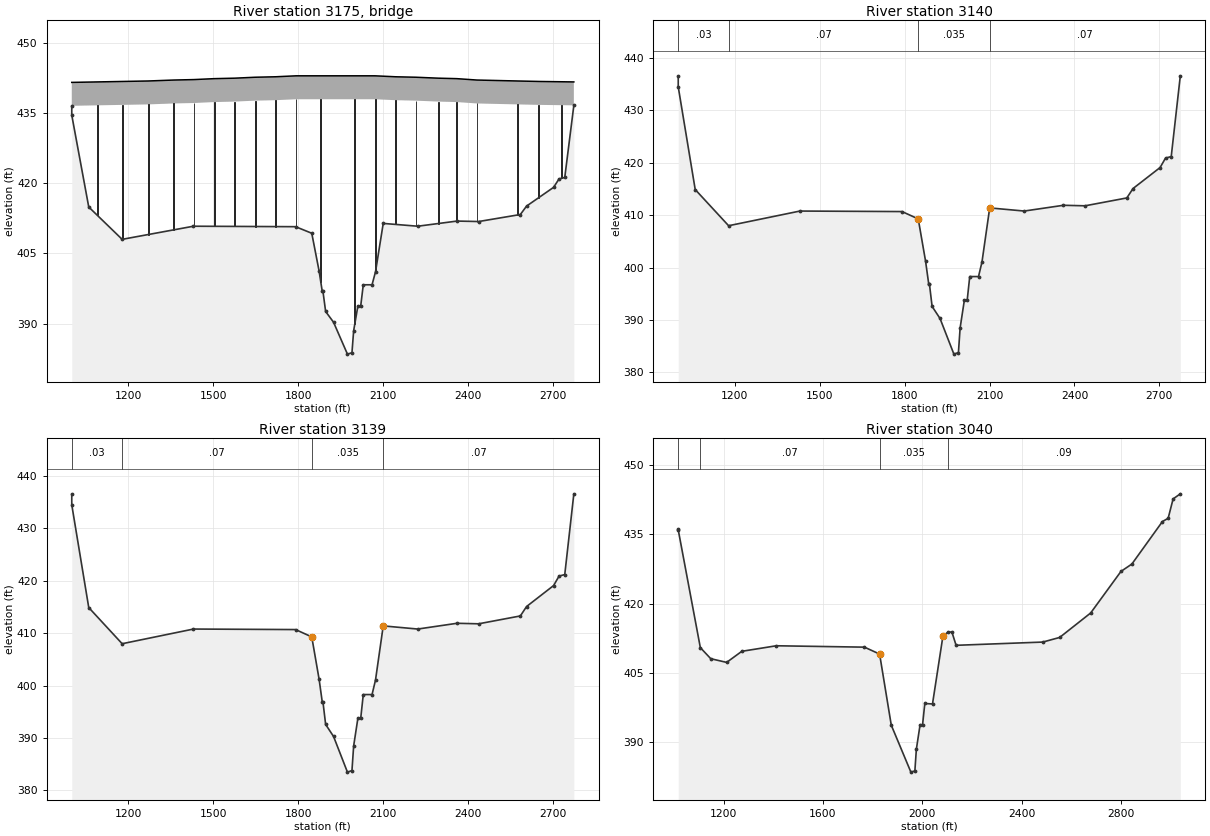
Type RM Length L Ch R = 3 ,3175    ,,,
BEGIN DESCRIPTION:
Shady Grove Road
END DESCRIPTION:
Node Name=Shady Grove Road
Bridge Culvert--1,0,-1,-1, 0
Deck Dist Width WeirC Skew NumUp NumDn MinLoCord MaxHiCord MaxSubmerge Is_Ogee
2,68,2.6,0, 46, 46, , , 0.95, 0, ,,,
    1000  1088.5 1088.75 1091.25  1091.5 1178.75 1181.25 1268.75 1271.25 1358.75
 1361.25 1430.75 1433.25 1502.75 1505.25 1574.75 1577.25 1646.75 1649.25 1718.75
 1721.25 1790.75 1793.25 1878.75 1881.25 1998.75 2001.25 2070.75 2073.25 2142.75
 2145.25 2214.75 2217.25 2293.75 2296.25 2358.75 2361.25 2430.75 2433.25 2573.75
 2576.25 2648.75 2651.25 2728.75 2731.25    2774
   441.5 441.598 441.599 441.601 441.602 441.699 441.701 441.799 441.803 441.997
 442.002 442.098 442.103 442.297 442.302 442.398 442.404 442.596 442.602 442.698
 442.703 442.897   442.9   442.9   442.9   442.9   442.9   442.9 442.897 442.703
 442.698 442.602 442.597 442.403 442.398 442.302 442.295 442.005 441.998 441.802
 441.798 441.702 441.698 441.636 441.634   441.6
   436.5 436.598 436.599 436.601 436.602 436.699 436.701 436.799 436.803 436.997
 437.002 437.098 437.103 437.297 437.302 437.398 437.404 437.596 437.602 437.698
 437.703 437.897   437.9   437.9   437.9   437.9   437.9   437.9 437.897 437.703
 437.698 437.602 437.597 437.403 437.398 437.302 437.295 437.005 436.998 436.802
 436.798 436.702 436.698 436.636 436.634   436.6
    1000  1088.5 1088.75 1091.25  1091.5 1178.75 1181.25 1268.75 1271.25 1358.75
 1361.25 1430.75 1433.25 1502.75 1505.25 1574.75 1577.25 1646.75 1649.25 1718.75
 1721.25 1790.75 1793.25 1878.75 1881.25 1998.75 2001.25 2070.75 2073.25 2142.75
 2145.25 2214.75 2217.25 2293.75 2296.25 2358.75 2361.25 2430.75 2433.25 2573.75
 2576.25 2648.75 2651.25 2728.75 2731.25    2774
   441.5 441.598 441.599 441.601 441.602 441.699 441.701 441.799 441.803 441.997
 442.002 442.098 442.103 442.297 442.302 442.398 442.404 442.596 442.602 442.698
 442.703 442.897   442.9   442.9   442.9   442.9   442.9   442.9 442.897 442.703
 442.698 442.602 442.597 442.403 442.398 442.302 442.295 442.005 441.998 441.802
 441.798 441.702 441.698 441.636 441.634   441.6
   436.5 436.598 436.599 436.601 436.602 436.699 436.701 436.799 436.803 436.997
 437.002 437.098 437.103 437.297 437.302 437.398 437.404 437.596 437.602 437.698
 437.703 437.897   437.9   437.9   437.9   437.9   437.9   437.9 437.897 437.703
 437.698 437.602 437.597 437.403 437.398 437.302 437.295 437.005 436.998 436.802
 436.798 436.702 436.698 436.636 436.634   436.6
Pier Skew, UpSta & Num, DnSta & Num=  ,1090, 2 ,1090, 2 , 0 , 0 , 0 ,,
     2.5     2.5
       0     440
     2.5     2.5
       0     440
Pier Skew, UpSta & Num, DnSta & Num=  ,1180, 2 ,1180, 2 , 0 , 0 , 0 ,,
     2.5     2.5
       0     440
     2.5     2.5
       0     440
Pier Skew, UpSta & Num, DnSta & Num=  ,1270, 2 ,1270, 2 , 0 , 0 , 0 ,,
     2.5     2.5
       0     440
     2.5     2.5
       0     440
Pier Skew, UpSta & Num, DnSta & Num=  ,1360, 2 ,1360, 2 , 0 , 0 , 0 ,,
     2.5     2.5
       0     440
     2.5     2.5
       0     440
Pier Skew, UpSta & Num, DnSta & Num=  ,1432, 2 ,1432, 2 , 0 , 0 , 0 ,,
     2.5     2.5
       0     440
     2.5     2.5
       0     440
Pier Skew, UpSta & Num, DnSta & Num=  ,1504, 2 ,1504, 2 , 0 , 0 , 0 ,,
     2.5     2.5
       0     440
     2.5     2.5
       0     440
Pier Skew, UpSta & Num, DnSta & Num=  ,1576, 2 ,1576, 2 , 0 , 0 , 0 ,,
     2.5     2.5
       0     440
     2.5     2.5
       0     440
Pier Skew, UpSta & Num, DnSta & Num=  ,1648, 2 ,1648, 2 , 0 , 0 , 0 ,,
     2.5     2.5
       0     440
     2.5     2.5
       0     440
Pier Skew, UpSta & Num, DnSta & Num=  ,1720, 2 ,1720, 2 , 0 , 0 , 0 ,,
     2.5     2.5
       0     440
     2.5     2.5
       0     440
Pier Skew, UpSta & Num, DnSta & Num=  ,1792, 2 ,1792, 2 , 0 , 0 , 0 ,,
     2.5     2.5
       0     440
     2.5     2.5
       0     440
Pier Skew, UpSta & Num, DnSta & Num=  ,1880, 2 ,1880, 2 , 0 , 0 , 0 ,,
     2.5     2.5
       0     440
     2.5     2.5
       0     440
Pier Skew, UpSta & Num, DnSta & Num=  ,2000, 2 ,2000, 2 , 0 , 0 , 0 ,,
     2.5     2.5
       0     440
     2.5     2.5
       0     440
Pier Skew, UpSta & Num, DnSta & Num=  ,2072, 2 ,2072, 2 , 0 , 0 , 0 ,,
     2.5     2.5
       0     440
     2.5     2.5
       0     440
Pier Skew, UpSta & Num, DnSta & Num=  ,2144, 2 ,2144, 2 , 0 , 0 , 0 ,,
     2.5     2.5
       0     440
     2.5     2.5
       0     440
Pier Skew, UpSta & Num, DnSta & Num=  ,2216, 2 ,2216, 2 , 0 , 0 , 0 ,,
     2.5     2.5
       0     440
     2.5     2.5
       0     440
Pier Skew, UpSta & Num, DnSta & Num=  ,2295, 2 ,2295, 2 , 0 , 0 , 0 ,,
     2.5     2.5
       0     440
     2.5     2.5
       0     440
Pier Skew, UpSta & Num, DnSta & Num=  ,2360, 2 ,2360, 2 , 0 , 0 , 0 ,,
     2.5     2.5
       0     440
     2.5     2.5
       0     440
Pier Skew, UpSta & Num, DnSta & Num=  ,2432, 2 ,2432, 2 , 0 , 0 , 0 ,,
     2.5     2.5
       0     440
     2.5     2.5
       0     440
Pier Skew, UpSta & Num, DnSta & Num=  ,2575, 2 ,2575, 2 , 0 , 0 , 0 ,,
     2.5     2.5
       0     440
     2.5     2.5
       0     440
Pier Skew, UpSta & Num, DnSta & Num=  ,2650, 2 ,2650, 2 , 0 , 0 , 0 ,,
     2.5     2.5
       0     440
     2.5     2.5
       0     440
Pier Skew, UpSta & Num, DnSta & Num=  ,2730, 2 ,2730, 2 , 0 , 0 , 0 ,,
     2.5     2.5
       0     440
     2.5     2.5
       0     440
BR Coef= 1 , 0 , 0 ,1.05, 0 ,,,0.8,-1,0.5,1,
WSPro=,,,, 1 ,,,, 0 ,,,, 0 ,,,,-1 ,-1 ,-1 , 0 , 0 , 0 , 0 , 0
BC Design=,, 0 ,, 0 ,,,,,,
BC HTab HWMax=436.6
BC Use User HTab Curves=0
BC User HTab FreeFlow(D)= 0

Type RM Length L Ch R = 1 ,3140    ,1,1,1
BEGIN DESCRIPTION:
This cross section corresponds to cross section 3119 of the non-georeferenced CDC model which was the source of this model.
END DESCRIPTION:
XS GIS Cut Line= 3
2459466.637857596980178.474438132458826.652588996979475.10839079
2458275.535909096978863.81269738
#Sta/Elev= 30
    1000   436.5    1000   434.5    1060   414.9    1178     408    1430   410.8
 1790.75   410.7    1848   409.3    1874   401.2    1885   396.9  1887.5   396.9
    1897   392.6    1925   390.3    1974   383.5    1990   383.8    1996   388.5
    2011   393.8    2021   393.8    2030   398.3    2061   398.3 2073.25 401.084
  2100.5   411.4  2222.5   410.8 2361.25   411.9  2437.5   411.8    2585   413.3
    2607   415.1  2702.5   419.1  2721.7   420.9  2741.9   421.2    2774   436.6
#Mann= 4 ,-1,0
    1000     .03       0    1178     .07       0    1848    .035       0
  2100.5     .07       0
Bank Sta=1848,2100.5
XS Rating Curve= 0 ,0
Exp/Cntr=0.5,0.3

Type RM Length L Ch R = 1 ,3139    ,99,99,99
BEGIN DESCRIPTION:
This cross section corresponds to cross section 3118 of the non-georeferenced CDC model which was the source of this model.
END DESCRIPTION:
XS GIS Cut Line= 3
2459467.939364176980177.220831722458827.149635266979474.23831379
2458276.238335526978863.11223947
#Sta/Elev= 30
    1000   436.5    1000   434.5    1060   414.9    1178     408    1430   410.8
 1790.75   410.7    1848   409.3    1874   401.2    1885   396.9  1887.5   396.9
    1897   392.6    1925   390.3    1974   383.5    1990   383.8    1996   388.5
    2011   393.8    2021   393.8    2030   398.3    2061   398.3 2073.25 401.084
  2100.5   411.4  2222.5   410.8 2361.25   411.9  2437.5   411.8    2585   413.3
    2607   415.1  2702.5   419.1  2721.7   420.9  2741.9   421.2    2774   436.6
#Mann= 4 ,-1,0
    1000     .03       0    1178     .07       0    1848    .035       0
  2100.5     .07       0
Bank Sta=1848,2100.5
XS Rating Curve= 0 ,0
Exp/Cntr=0.3,0.1

Type RM Length L Ch R = 1 ,3040    ,0,0,0
BEGIN DESCRIPTION:
This cross section corresponds to cross section 3013 of the non-georeferenced CDC model which was the source of this model.
END DESCRIPTION:
XS GIS Cut Line= 3
  2459501.030505 6980073.9300278 2458285.6090517 6978741.9130068
 2458116.6218568 6978602.9234554
#Sta/Elev= 30
    1017   436.1    1017     436    1106   410.5    1148   408.1    1212   407.3
    1273   409.7    1412   410.9    1767   410.6    1828   409.1    1875   393.7
    1954  383.54    1970   383.8    1976   388.5    1991   393.8    2001   393.8
    2010   398.4    2041   398.3    2083     413    2102   413.8    2119   413.9
    2136     411    2485   411.7    2553   412.7    2678     418    2800     427
    2844   428.6    2967   437.8    2990   438.5    3010   442.7    3039   443.8
#Mann= 4 ,-1,0
    1017     .03       0    1106     .07       0    1828    .035       0
    2102     .09       0
Bank Sta=1828,2083
XS Rating Curve= 0 ,0
Exp/Cntr=0.3,0.1

River Reach=West Fork       ,wf
Reach XY= 30
       2346473.9        6963584.      2346286.59      6968259.29
       2354512.4      6965894.36      2359871.65      6970041.49
      2365532.14      6970407.58      2367619.48       6974853.9
      2381458.46      6966394.67      2382440.84      6968870.18
       2385600.2      6969508.62      2385877.69      6972305.46
      2387730.11       6971519.9      2387123.85      6974369.92
      2389517.29      6975915.22      2397024.23      6975004.71
      2396328.62      6973598.51      2402295.53       6972489.5
       2403920.5      6970193.02      2409720.17      6975714.25
      2410027.07      6979946.39      2412459.53      6982607.21
      2417785.24      6979460.17       2418378.9      6973023.19
      2423274.88      6971824.69      2428119.37      6964022.21
      2435982.11      6962862.51      2443411.24      6969635.42
      2444209.34      6968225.94      2455794.74      6971975.24
       2457790.9      6976586.85       2460651.9      6977070.51

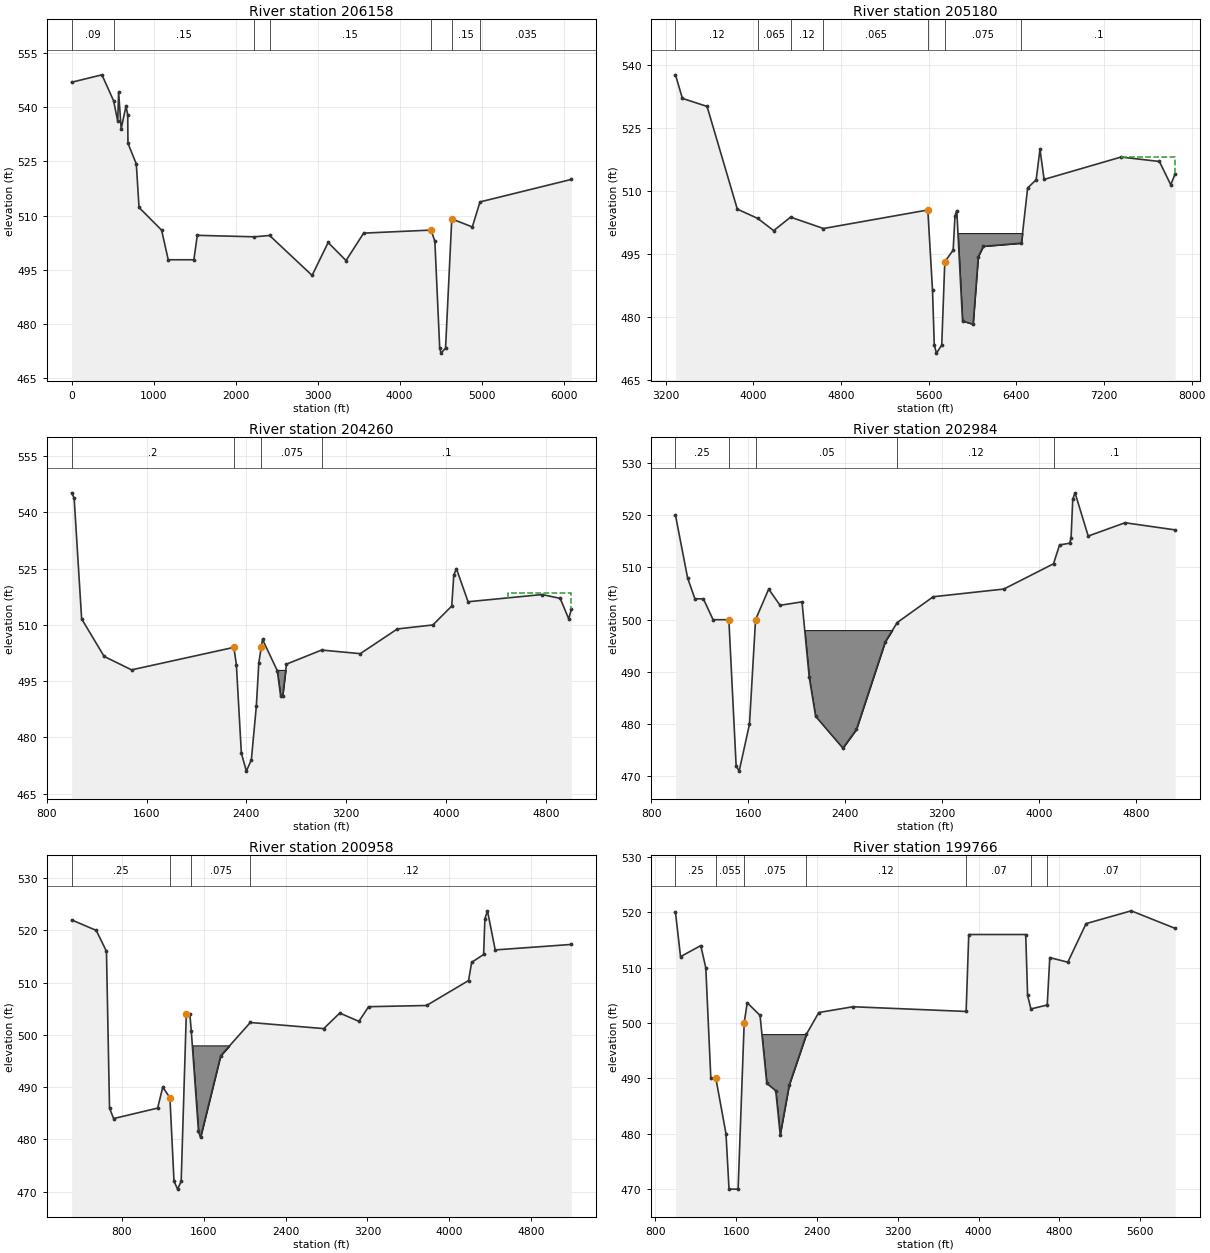
Type RM Length L Ch R = 1 ,206158  ,1071,978,460
BEGIN DESCRIPTION:
This cross section corresponds to cross section 206218 of the non-georeferenced CDC model which was the source of this model.
Downstream of East 1st Street.
END DESCRIPTION:
XS GIS Cut Line= 6
  2341904.095961 6963632.5437376   2343430.68391   6963683.60684
     2344852.789   6963698.88109   2345465.41508   6963790.52001
   2347058.22685   6964146.116082347947.114721516964085.10118596
#Sta/Elev= 30
       0  546.85  369.23   548.9  512.04  541.71  562.18  536.03  572.53  544.23
  603.81  533.98  663.08  540.28  684.12  537.77  686.41     530  788.51  524.26
  821.63  512.25 1096.67     506  1177.8   497.8 1490.48   497.8  1532.1  504.55
 2227.97  504.14 2413.28  504.51 2932.16  493.48 3128.06  502.57 3345.99  497.58
 3560.99  505.16 4383.29     506 4429.29  502.89 4488.22  473.47 4503.96     472
 4559.71  473.37 4635.51  509.09 4886.06  506.87 4979.55  513.78  6093.5     520
#Mann= 7 ,-1,0
       0     .09       0  512.04     .15       0 2227.97     .06       0
 2413.28     .15       0 4383.29    .066       0 4635.51     .15       0
 4979.55    .035       0
Bank Sta=4383.29,4635.51
XS Rating Curve= 0 ,0
Exp/Cntr=0.3,0.1

Type RM Length L Ch R = 1 ,205180  ,800,920,900
BEGIN DESCRIPTION:
This cross section corresponds to cross section 205240 of the non-georeferenced CDC model which was the source of this model.
ROB updated with 2009 TNRIS LiDAR
END DESCRIPTION:
XS GIS Cut Line= 6
2343553.770143826965112.22718057   2344871.03011      6964833.93
   2346477.14501      6964833.93 2347670.1078499 6964217.5993343
     2347947.246     6964085.0922347968.191686126964001.06927625
#Sta/Elev= 30
    3291   537.6    3354     532    3579   530.1    3855   505.7    4041   503.5
    4187   500.6    4341   503.8    4641   501.1    5593   505.5    5636   486.4
    5652   473.4    5672   471.5    5720   473.4    5748   493.2 5824.32  495.96
 5840.89  504.11  5857.3  505.35 5909.68  479.13 6006.13  478.36  6053.3  494.42
  6099.2  496.87 6447.21  497.62 6503.68  510.73 6581.57  512.68 6616.27  519.92
 6653.93  512.76  7355.7  518.07 7705.91  517.02 7809.26  511.48 7849.67  514.11
#Mann= 7 ,-1,0
    3291     .12       0    4041    .065       0    4341     .12       0
    4641    .065       0    5593    .055       0    5748    .075       0
 6447.21      .1       0
#XS Ineff= 3 ,-1
    3291    5593   505.5    5748 7358.97   493.2 7358.97 7849.67  518.05
Permanent Ineff=
       F       F       F
#Block Obstruct= 1 ,-1
 5861.35 6480.54     500
Bank Sta=5593,5748
XS Rating Curve= 0 ,0
Exp/Cntr=0.3,0.1

Type RM Length L Ch R = 1 ,204260  ,1000,1276,200
BEGIN DESCRIPTION:
This cross section corresponds to cross section 204336 of the non-georeferenced CDC model which was the source of this model.
ROB updated with Halff Survey & 2009 TNRIS LiDAR
END DESCRIPTION:
XS GIS Cut Line= 6
     2344675.495     6965656.765     2344766.751     6965657.144
     2346520.754     6965664.422     2347139.385     6965475.194
 2347946.74364766964085.956933832347946.994879386964085.52463464
#Sta/Elev= 30
    1000   545.2    1020   543.8    1080   511.6    1260   501.6    1480     498
    2300     504    2320   499.4    2360   475.8    2400     471    2440     474
    2480   488.3    2500   499.9    2520   504.1 2529.47  506.11 2647.55  497.81
  2674.9     491 2690.71     491 2721.35  499.52 3002.93  503.28 3313.06  502.32
 3610.27  508.91 3894.45  509.97 4045.89  515.01 4062.53  523.31 4083.48  524.97
 4176.83  516.16 4770.05  518.08 4914.96  517.06 4983.21  511.61 5004.37   514.1
#Mann= 4 ,-1,0
    1000      .2       0    2300    .055       0    2520    .075       0
 3002.93      .1       0
#XS Ineff= 3 ,-1
    1000    2300     504    2520 4494.78   504.1 4494.78 5004.37  518.51
Permanent Ineff=
       F       F       F
#Block Obstruct= 1 ,-1
 2628.13 2742.16     498
Bank Sta=2300,2520
XS Rating Curve= 0 ,0
Exp/Cntr=0.3,0.1

Type RM Length L Ch R = 1 ,202984  ,1688,2026,226
BEGIN DESCRIPTION:
This cross section corresponds to cross section 203180 of the non-georeferenced CDC model which was the source of this model.
New XS from 99 topo, interpolated FL, ROB updated with Halff Survey & 2009 TNRIS LiDAR
END DESCRIPTION:
XS GIS Cut Line= 6
      2345163.49      6966832.88      2345534.79      6966678.18
      2345689.49      6966461.59      2347077.94      6965597.59
       2347139.5     6965475.2162347948.487997476964084.05120195
#Sta/Elev= 30
    1000     520    1100     508    1160     504    1230     504    1310     500
    1440     500    1500     472    1525     471    1610     480    1660     500
 1768.15  505.86 1861.89  502.76 2043.01  503.42 2102.64  488.94 2155.16   481.5
 2379.83  475.41 2491.72     479 2729.01  495.77 2828.13  499.46 3124.91   504.4
 3706.36  505.87 4116.31  510.71 4166.18  514.32 4248.99  514.65 4260.97  515.57
 4274.86  523.08 4293.79   524.3 4402.38  516.02 4705.99  518.57 5119.25   517.2
#Mann= 5 ,-1,0
    1000     .25       0    1440    .055       0    1660     .05       0
 2828.13     .12       0 4116.31      .1       0
#XS Ineff= 2 , 0
       0    1440     500 1768.15       0  505.86
Permanent Ineff=
       F       F
#Block Obstruct= 1 ,-1
    2040    2840     498
Bank Sta=1440,1660
XS Rating Curve= 0 ,0
Exp/Cntr=0.3,0.1

Type RM Length L Ch R = 1 ,200958  ,930,1192,380
BEGIN DESCRIPTION:
This cross section corresponds to cross section 201380 of the non-georeferenced CDC model which was the source of this model.
New XS from 99 topo, ROB updated with Halff Survey & 2009 TNRIS LiDAR
END DESCRIPTION:
XS GIS Cut Line= 6
      2345266.63      6968153.05       2346071.1      6967719.87
       2346442.4      6967802.38      2346844.64      6966255.32
      2347139.74      6965475.342347945.940442246964095.00547947
#Sta/Elev= 30
     310     522     550     520     650     516     680     486     720     484
    1150     486    1200     490    1270     488    1310     472    1345   470.5
    1380     472    1430     504 1464.58  504.03 1478.78  500.75  1549.1  481.54
 1568.96  480.38 1765.56     496 2055.38  502.38 2772.55  501.21 2929.15  504.18
 3116.13   502.6 3211.09   505.4 3777.11  505.63 4187.32   510.4 4217.82  513.88
 4334.55  515.39 4347.11  522.23 4372.27  523.74 4447.89  516.26 5191.53  517.31
#Mann= 4 ,-1,0
     310     .25       0    1270    .055       0 1478.78    .075       0
 2055.38     .12       0
#XS Ineff= 2 , 0
       0    1270     488    1430       0     504
Permanent Ineff=
       F       F
#Block Obstruct= 1 ,-1
    1450    1850     498
Bank Sta=1270,1430
XS Rating Curve= 0 ,0
Exp/Cntr=0.3,0.1

Type RM Length L Ch R = 1 ,199766  ,1454,1260,582
BEGIN DESCRIPTION:
This cross section corresponds to cross section 199650 of the non-georeferenced CDC model which was the source of this model.
New XS from 99 topo, ROB updated with Halff Survey & 2009 TNRIS LiDAR
END DESCRIPTION:
XS GIS Cut Line= 6
2346705.969551196968989.37062247     2346709.982     6968939.532
     2346848.265     6967221.919      2347139.86      6965475.38
     2347900.201     6964175.2772347925.442715766964132.11632553
#Sta/Elev= 30
    1000     520    1050     512    1250     514    1300     510    1350     490
    1400     490    1500     480    1530     470    1620     470    1680     500
 1710.03  503.67 1837.22  501.39 1903.67  489.13 1992.62  487.77 2036.58  479.85
 2125.81   488.8 2296.56     498 2419.07  501.91  2756.9  502.95 3877.32   502.1
 3903.31     516 4467.21     516 4485.82     505 4518.55  502.55 4680.23  503.27
 4705.46  511.83 4884.01     511  5064.8  517.97  5511.5  520.28 5946.79  517.11
#Mann= 7 ,-1,0
    1000     .25       0    1400    .055       0    1680    .075       0
 2296.56     .12       0 3877.32     .07       0 4518.55     .12       0
 4680.23     .07       0
#XS Ineff= 2 , 0
       0    1400     490 1710.03       0  503.67
Permanent Ineff=
       F       F
#Block Obstruct= 1 ,-1
 1837.06 2346.15     498
Bank Sta=1400,1680
XS Rating Curve= 0 ,0
Exp/Cntr=0.3,0.1

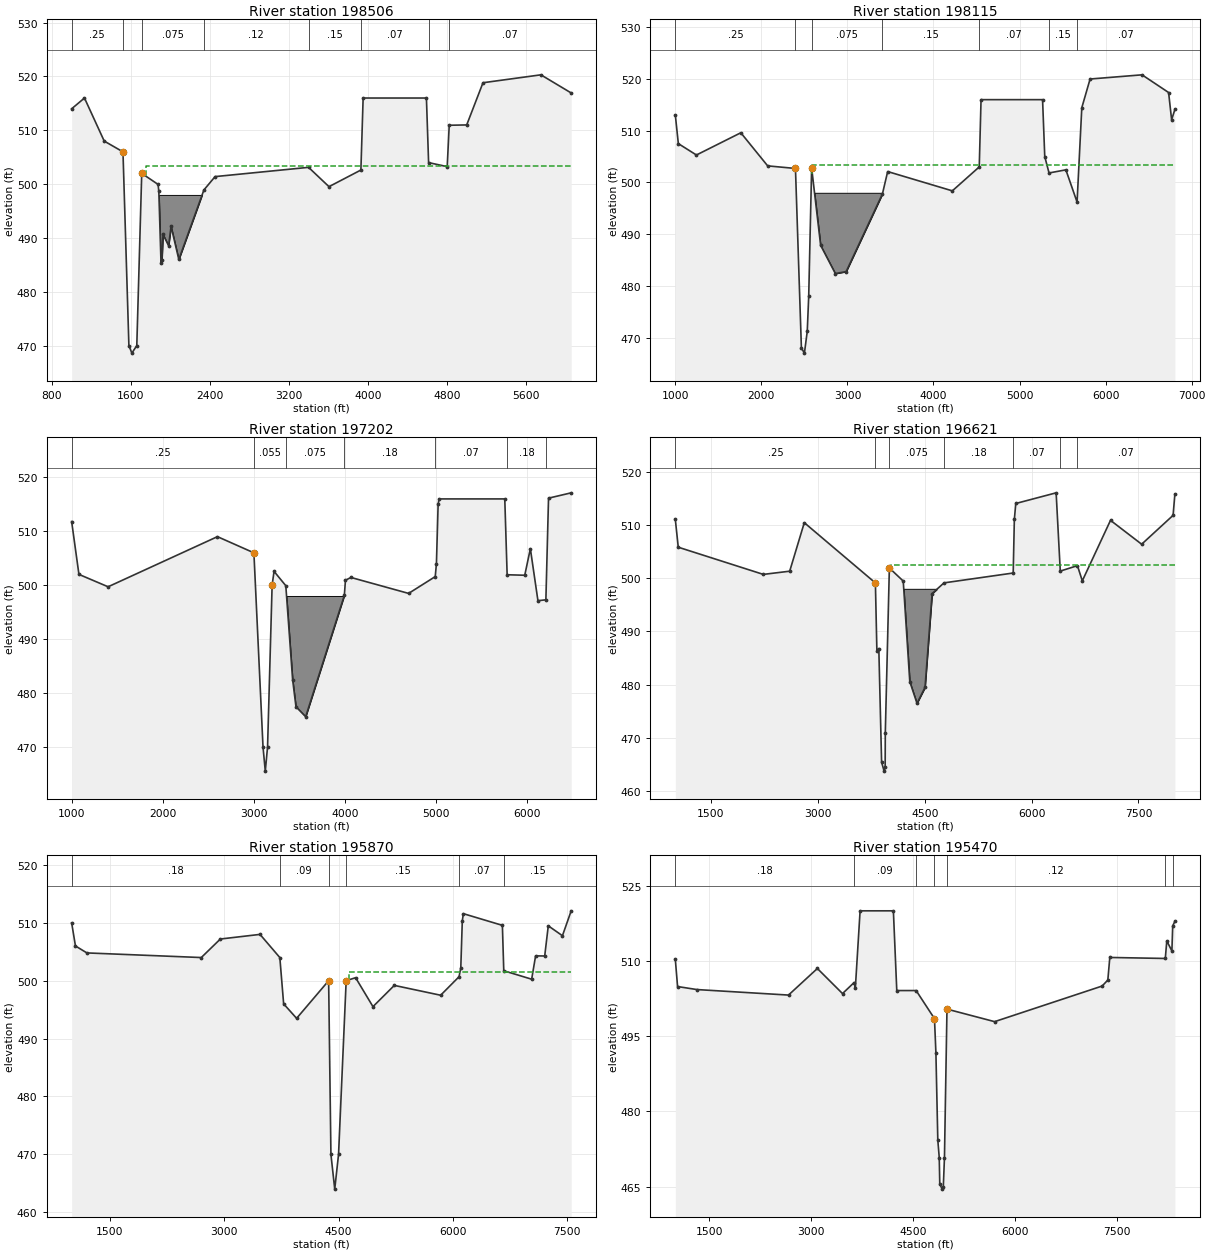
Type RM Length L Ch R = 1 ,198506  ,349,391,368
BEGIN DESCRIPTION:
This cross section corresponds to cross section 199000 of the non-georeferenced CDC model which was the source of this model.
ROB updated with Halff Survey & 2009 TNRIS LiDAR
END DESCRIPTION:
XS GIS Cut Line= 4
     2348003.085     6969069.651     2347648.191     6965520.706
     2347906.296     6964326.969     2347976.465     6964002.435
#Sta/Elev= 30
    1000     514    1130     516    1330     508    1520     506    1580     470
    1610   468.6    1660     470    1710     502 1875.43  499.95 1883.11  498.64
 1905.52   485.3 1914.73  485.94 1925.51  490.66 1982.34  488.55 2007.16  492.15
 2085.73     486 2339.86  498.92 2453.16   501.4  3399.9  503.12 3606.91  499.53
 3930.15  502.62 3952.88     516    4594     516 4616.11     504 4804.64  503.25
 4824.95  510.94  5002.2     511 5167.04  518.84 5753.77  520.31 6060.59  516.94
#Mann= 8 ,-1,0
    1000     .25       0    1520    .055       0    1710    .075       0
 2339.86     .12       0  3399.9     .15       0 3930.15     .07       0
 4616.11     .15       0 4824.95     .07       0
#XS Ineff= 2 , 0
       0    1520     506 1749.35       0  503.34
Permanent Ineff=
       F       F
#Block Obstruct= 1 ,-1
 1840.91 2392.05     498
Bank Sta=1520,1710
XS Rating Curve= 0 ,0
Exp/Cntr=0.3,0.1

Type RM Length L Ch R = 1 ,198115  ,536,482,386
BEGIN DESCRIPTION:
This cross section corresponds to cross section 198174 of the non-georeferenced CDC model which was the source of this model.
ROB updated with Halff Survey & 2009 TNRIS LiDAR
END DESCRIPTION:
XS GIS Cut Line= 4
      2348504.95     6969868.623     2348502.254     6969846.832
      2347980.22      6965626.85      2347997.38      6964089.91
#Sta/Elev= 30
    1000     513    1035   507.5    1245   505.3    1761   509.6    2073   503.2
    2396   502.7    2465     468    2500     467    2533   471.2    2550     478
    2584   502.8 2688.58  487.83 2859.56  482.38 2985.18  482.76 3406.38  497.76
 3467.49   502.1 4218.93  498.37 4531.75     503 4552.65     516 5267.57     516
    5293     505 5342.63  501.83 5538.47  502.43 5668.55   496.2 5723.42  514.44
 5819.85  519.99 6423.42   520.8 6732.17  517.38 6767.22  512.11 6805.11   514.1
#Mann= 7 ,-1,0
    1000     .25       0    2396    .055       0    2584    .075       0
 3406.38     .15       0 4531.75     .07       0 5342.63     .15       0
 5668.55     .07       0
#XS Ineff= 2 , 0
       0    2396   502.7 2592.56       0  503.36
Permanent Ineff=
       F       F
#Block Obstruct= 1 ,-1
 2602.27 3460.23     498
Bank Sta=2396,2584
XS Rating Curve= 0 ,0
Exp/Cntr=0.3,0.1

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
Type RM Length L Ch R = 1 ,197202  ,645,581,488
BEGIN DESCRIPTION:
This cross section corresponds to cross section 197450 of the non-georeferenced CDC model which was the source of this model.
New XS from 99 topo, interpolated FL, ROB updated with Halff Survey & 2009 TNRIS LiDAR
END DESCRIPTION:
XS GIS Cut Line= 5
   2349741.33176 6970183.8905078 2349487.1895125 6968919.0894779
 2348562.3127533 6966370.3012684 2348476.2778204 6965004.4949449
 2348416.5537532 6964056.3741531
#Sta/Elev= 30
    1000   511.8    1080     502    1400   499.7    2600     509    3000     506
    3100     470    3125   465.5    3150     470    3200     500  3221.2  502.56
 3350.16   499.9 3424.87  482.49 3461.66  477.45 3568.31   475.6 3992.64  498.11
 4004.66  500.91 4064.85  501.43  4697.8  498.47  4990.1  501.59 5003.08     504
 5021.71     515 5032.14     516 5753.18     516 5779.05  501.93 5972.35  501.84
 6033.88  506.77 6117.03  497.12 6204.19  497.28 6233.31  516.14 6481.95  517.13
#Mann= 7 ,-1,0
    1000     .25       0    3000    .055       0 3350.16    .075       0
 3992.64     .18       0  4990.1     .07       0 5779.05     .18       0
 6204.19     .07       0
#XS Ineff= 3 ,-1
    1000    3000     506  3221.2 6033.82  502.56 6033.82 6222.04  506.74
Permanent Ineff=
       F       F       T
#Block Obstruct= 1 ,-1
 3335.23 4034.09     498
Bank Sta=3000,3200
XS Rating Curve= 0 ,0
Exp/Cntr=0.3,0.1

Type RM Length L Ch R = 1 ,196621  ,551,751,451
BEGIN DESCRIPTION:
This cross section corresponds to cross section 196680 of the non-georeferenced CDC model which was the source of this model.
ROB updated with Halff Survey & 2009 TNRIS LiDAR
END DESCRIPTION:
XS GIS Cut Line= 4
   2350459.27714   6970863.80901   2350010.07593   6968659.57294
   2349045.13003   6966159.15996 2348846.7584696 6964144.5914655
#Sta/Elev= 30
    1000     511    1041   505.8    2235   500.7    2605   501.3    2810   510.4
    3808   499.1    3829   486.3    3856   486.8    3895   465.5    3930   463.8
    3945   464.5    3947     471    4004   501.9 4198.79  499.45 4290.71  480.59
 4391.66  476.52 4504.75  479.51 4604.34  497.11 4770.88  499.11 5742.08  500.96
 5758.21     511 5778.32     514 6344.68     516 6402.86  501.32 6643.71  502.34
 6712.02  499.49 7107.86  510.84 7544.96  506.36 7986.24  511.78  8011.3  515.76
#Mann= 7 ,-1,0
    1000     .25       0    3808    .055       0    4004    .075       0
 4770.88     .18       0 5742.08     .07       0 6402.86     .18       0
 6643.71     .07       0
#XS Ineff= 2 , 0
       0    3808   499.1 4030.27       0  502.37
Permanent Ineff=
       F       F
#Block Obstruct= 1 ,-1
 4166.67 4666.67     498
Bank Sta=3808,4004
XS Rating Curve= 0 ,0
Exp/Cntr=0.3,0.1

Type RM Length L Ch R = 1 ,195870  ,250,404,400
BEGIN DESCRIPTION:
This cross section corresponds to cross section 195930 of the non-georeferenced CDC model which was the source of this model.
ROB updated with Halff Survey & 2009 TNRIS LiDAR
END DESCRIPTION:
XS GIS Cut Line= 6
  2350799.201946 6971111.4184422 2350474.2049269 6967822.7110932
 2349433.4176384 6966219.7402178 2349358.1369491 6964961.4776425
 2349325.0781095 6964408.9229156 2349305.9669784 6964089.4941056
#Sta/Elev= 30
    1000     510    1050     506    1200   504.8    2700     504    2950   507.2
    3470     508    3730     504    3780     496    3950   493.5    4370     500
    4400     470    4450     464    4500     470    4600     500 4723.58  500.52
 4951.34  495.52 5231.25  499.19  5838.8  497.49 6080.13  500.69 6102.97  502.21
 6122.73  510.33 6136.62  511.58  6648.4  509.56 6666.56  501.72 7032.26  500.26
 7083.97  504.29  7203.4  504.27 7250.21  509.48 7435.83  507.77  7550.7  512.07
#Mann= 6 ,-1,0
    1000     .18       0    3730     .09       0    4370    .055       0
    4600     .15       0 6080.13     .07       0 6666.56     .15       0
#XS Ineff= 2 , 0
       0    4370     500 4643.21       0  501.49
Permanent Ineff=
       F       F
#Block Obstruct= 2 , 0
                            6100             508
Bank Sta=4370,4600
XS Rating Curve= 0 ,0
Exp/Cntr=0.3,0.1

Type RM Length L Ch R = 1 ,195470  ,500,434,700
BEGIN DESCRIPTION:
This cross section corresponds to cross section 195526 of the non-georeferenced CDC model which was the source of this model.
END DESCRIPTION:
XS GIS Cut Line= 5
  2351105.088864  6971198.753877   2351105.06685   6971198.53111
   2350748.60005   6967591.37494   2349972.41984   6966325.86402
   2349864.37806   6964083.99515
#Sta/Elev= 30
    1000   510.3    1033   504.9    1317   504.3    2666   503.2    3091   508.5
    3461   503.5    3632   505.7    3650   504.6    3720     520    4210     520
    4260   504.1    4545   504.1    4815   498.5    4836   491.7    4864   474.3
    4885   470.8    4893   465.5    4928   464.5    4945     465    4962   470.8
    4999   500.4    5700   497.9    7283     505    7367   506.2    7396   510.7
    8213   510.5    8235     514    8310     512    8322     517    8354   517.9
#Mann= 7 ,-1,0
    1000     .18       0    3632     .09       0    4545      .1       0
    4815    .055       0    4999     .12       0    8213     .04       0
    8322     .12       0
#XS Ineff= 2 , 0
            4815   498.5    4999           500.4
Permanent Ineff=
       F       F
Bank Sta=4815,4999
XS Rating Curve= 0 ,0
Exp/Cntr=0.3,0.1