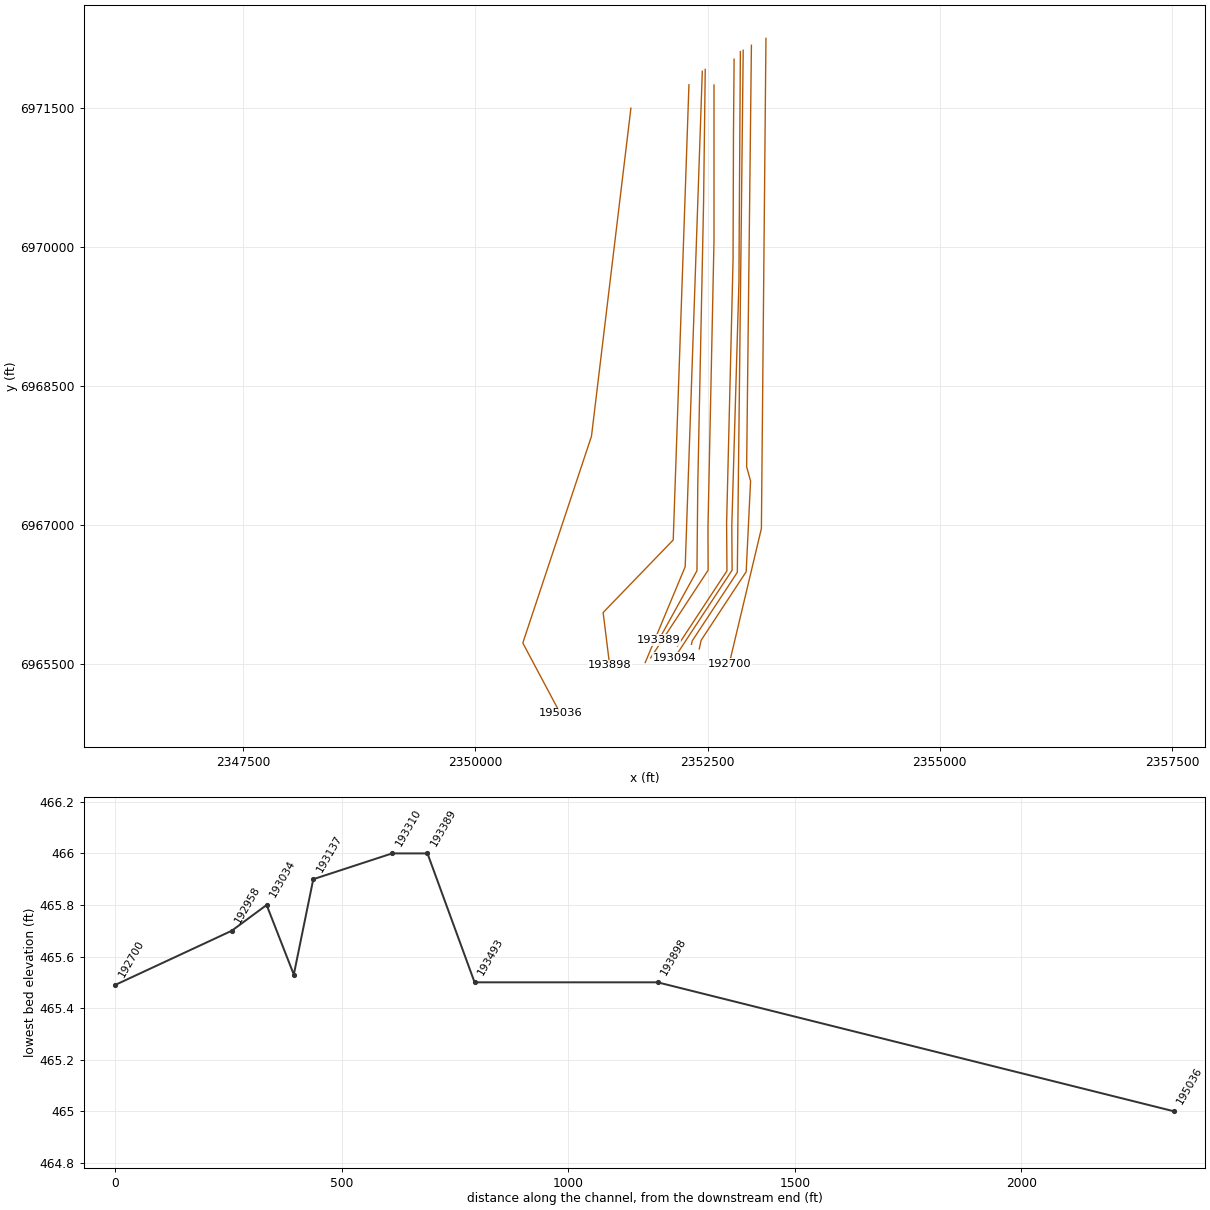
HEC-RAS study CDC_Consolidated_Model.prj: Upper Trinity CDC Consolidated Model

--- CDC_Consolidated_Model.g04 (geometry) --- (continued)

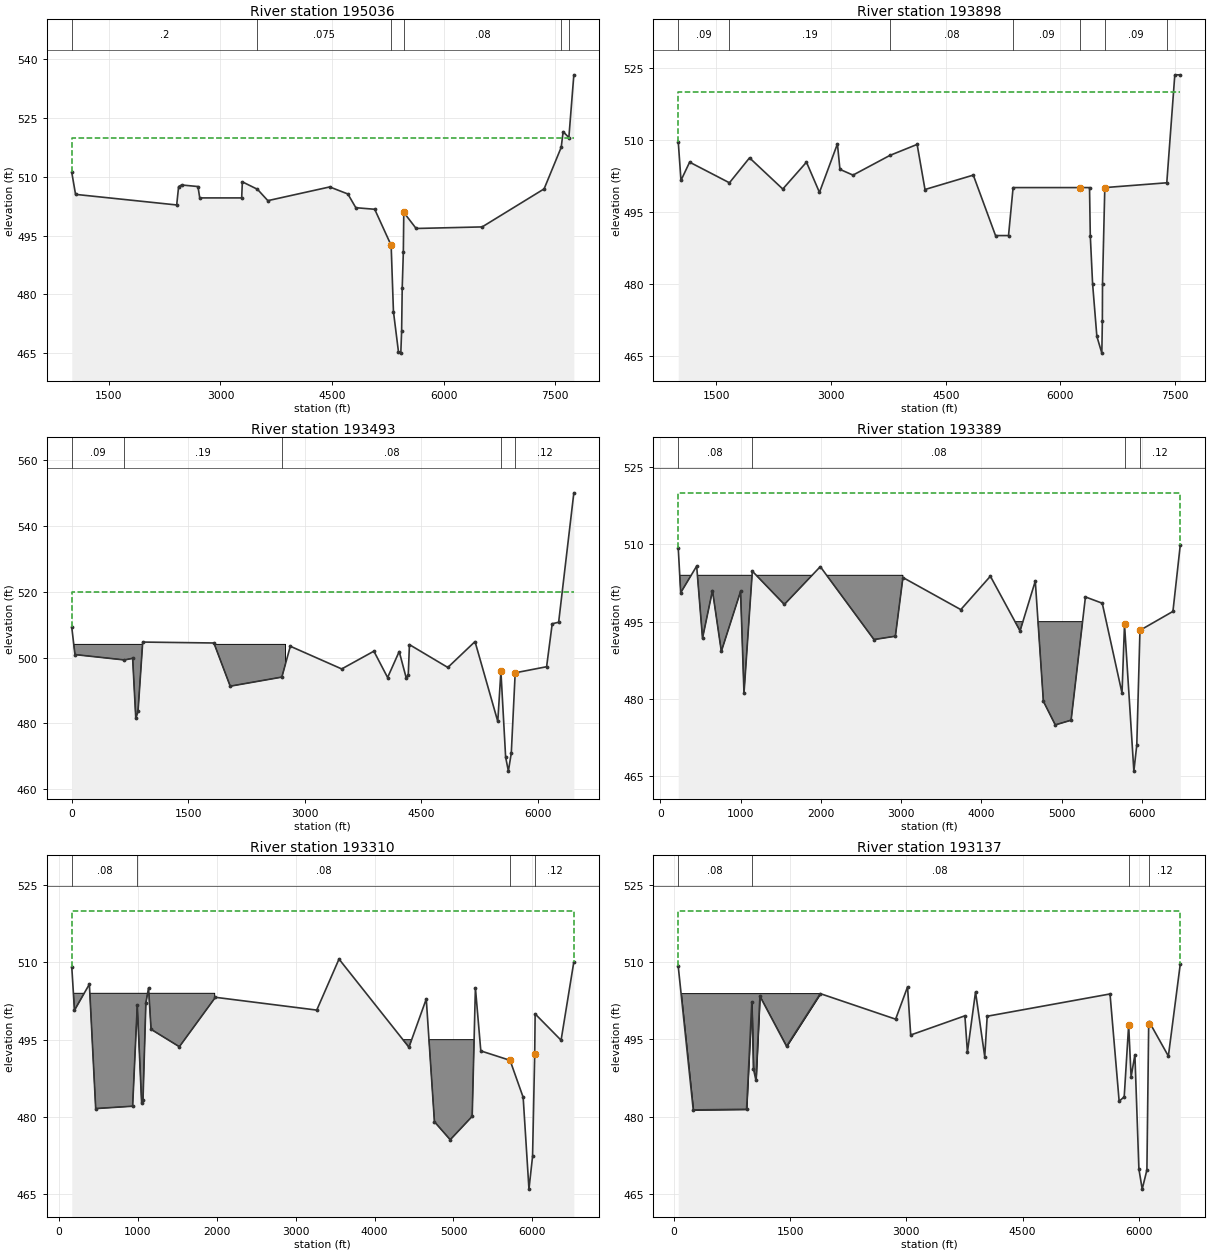
Type RM Length L Ch R = 1 ,195036  ,1140,1139,827
BEGIN DESCRIPTION:
This cross section corresponds to cross section 195089 of the non-georeferenced CDC model which was the source of this model.
END DESCRIPTION:
XS GIS Cut Line= 6
   2351674.21992   6971493.79496   2351249.84084   6967958.91883
   2350512.53293   6965737.03055   2350512.53293   6965726.17985
   2350695.08309   6965382.96893   2350913.68502   6964971.97598
#Sta/Elev= 30
    1000   511.1    1051   505.5    2411   502.8    2437   507.5    2476   507.9
    2697   507.5    2721   504.6    3285   504.6    3294   508.7    3497   506.8
    3637   503.9    4469   507.4    4713   505.6    4820   502.1    5074   501.7
    5295   492.5    5326   475.6    5393   465.4    5425     465    5436   470.7
    5444   481.7    5459   490.8    5465   500.9    5631   496.8    6519   497.2
    7352   506.9    7582   517.5    7608   521.5    7685     520    7752     536
#Mann= 6 ,-1,0
    1000      .2       0    3497    .075       0    5295     .05       0
    5465     .08       0    7582     .04       0    7685     .08       0
#XS Ineff= 3 ,-1
    1000    5295   492.5     999    1000     520    5465    7752   500.9
Permanent Ineff=
       F       F       F
Bank Sta=5295,5465
XS Rating Curve= 0 ,0
Exp/Cntr=0.3,0.1

Type RM Length L Ch R = 1 ,193898  ,158,404,739
BEGIN DESCRIPTION:
This cross section corresponds to cross section 193960 of the non-georeferenced CDC model which was the source of this model.
END DESCRIPTION:
XS GIS Cut Line= 6
  2352299.126757 6971745.9850765 2352208.5338073 6969120.7800194
 2352129.8380986 6966840.8078733 2351752.5311104 6966449.8037341
 2351375.2149359 6966058.8038599  2351445.887498 6965487.9918045
#Sta/Elev= 30
    1000   509.6    1036   501.5    1149   505.3    1670     501    1933   506.2
    2368   499.7    2678   505.3    2848     499    3083   509.1    3116   503.8
    3287   502.6    3769   506.7    4126     509    4229   499.6    4861   502.6
    5152     490    5322     490    5382     500    6262     500    6382     500
    6392     490    6422     480    6478     469    6543   465.5    6550   472.2
    6552     480    6582     500    7393     501    7498   523.5    7570   523.5
#Mann= 7 ,-1,0
    1000     .09       0    1670     .19       0    3769     .08       0
    5382     .09       0    6262    .055       0    6582     .09       0
    7393     .04       0
#XS Ineff= 3 ,-1
    1000    6262     500    6582    7570     500     999    1000     520
Permanent Ineff=
       F       F       F
Bank Sta=6262,6582
XS Rating Curve= 0 ,0
Exp/Cntr=0.3,0.1

Type RM Length L Ch R = 1 ,193493  ,106,104,61
BEGIN DESCRIPTION:
This cross section corresponds to cross section 193550 of the non-georeferenced CDC model which was the source of this model.
END DESCRIPTION:
XS GIS Cut Line= 3
  2352443.025935 6971891.6115285 2352258.7703713  6966552.700172
 2351828.4115221 6965519.1106147
#Sta/Elev= 30
       0  509.18   41.13   500.9  677.13  499.27  783.58  499.76  824.05  481.51
  852.93  483.73  912.97   504.7 1829.18  504.42 2039.15   491.3 2703.93  494.06
  2812.7  503.43 3474.17  496.54 3888.24  501.93 4064.79  493.93 4214.01  501.83
 4304.49  493.79 4330.97   494.8 4345.66  503.93 4839.83  496.99 5189.74  504.85
 5482.76  480.59 5522.98  495.82 5583.86  469.74 5619.12   465.5 5656.59  470.97
 5706.85  495.36 6111.13  497.21 6183.22  510.26 6266.13  510.73  6461.7  550.03
#Mann= 5 ,-1,0
       0     .09       0  677.13     .19       0 2703.93     .08       0
 5522.98    .055       0 5706.85     .12       0
#XS Ineff= 2 , 0
       0       0     520               0
Permanent Ineff=
       F       F
#Block Obstruct= 1 ,-1
       0    2751     504
Bank Sta=5522.98,5706.85
XS Rating Curve= 0 ,0
Exp/Cntr=0.3,0.1

Type RM Length L Ch R = 1 ,193389  ,122,78,51
BEGIN DESCRIPTION:
This cross section corresponds to cross section 193445 of the non-georeferenced CDC model which was the source of this model.
END DESCRIPTION:
XS GIS Cut Line= 6
2352474.617988956971912.11832126  2352471.779015 6971686.2161615
 2352456.5881012 6970477.4485659 2352394.3050893 6967434.9139686
 2352385.2775483 6966508.8721855 2351974.1408146  6965763.491814
#Sta/Elev= 30
  224.08  509.32  254.81  500.62  453.74  505.78   526.7  491.79  650.64  501.03
  761.17  489.23  1000.6  500.87 1043.32  481.13 1147.23   504.8 1546.14  498.34
 1994.09  505.68 2662.67  491.53 2929.41  492.18 3023.46  503.57 3744.55  497.34
 4112.99  503.82 4482.76  493.21 4672.53  502.87 4773.32  479.55 4921.56  474.97
 5118.77  475.88 5297.32   499.8 5506.87  498.58  5753.1  481.14 5784.16  494.47
 5900.72     466 5937.01  471.06 5976.78  493.32 6387.44  496.99 6479.37  509.94
#Mann= 4 ,-1,0
  224.08     .08       0 1147.23     .08       0 5784.16    .055       0
 5976.78     .12       0
#XS Ineff= 2 , 0
       0  224.08     520 6479.37       0     520
Permanent Ineff=
       F       F
#Block Obstruct= 2 ,-1
    4194    5273     495       0    3023     504
Bank Sta=5784.16,5976.78
XS Rating Curve= 0 ,0
Exp/Cntr=0.3,0.1

Type RM Length L Ch R = 1 ,193310  ,205,174,200
BEGIN DESCRIPTION:
This cross section corresponds to cross section 193367 of the non-georeferenced CDC model which was the source of this model.
END DESCRIPTION:
XS GIS Cut Line= 5
2352568.827706016971743.13759569 2352568.8277062 6970066.9018148
 2352503.7235057 6966965.3394484 2352505.5683183  6966515.035559
 2351886.8615504 6965570.2654669
#Sta/Elev= 30
  166.21  509.13  200.37   500.7  389.26  505.77  469.18  481.63  936.98  482.09
  995.79  501.69 1050.82  482.71 1068.34  483.31 1104.48  502.09 1138.52  505.03
 1170.41  497.01 1528.56  493.63 1985.19  503.22 3268.55  500.74 3550.35  510.64
 4436.17  493.53 4655.42  502.89 4759.06  479.07  4958.8  475.58 5237.04  480.12
 5277.69  505.07 5346.19  492.82 5716.61  490.99 5882.44  483.82 5955.94     466
 6001.45  472.34 6028.73   492.3 6034.24     500 6362.69  494.89 6524.33  510.11
#Mann= 4 ,-1,0
  166.21     .08       0  995.79     .08       0 5716.61    .055       0
 6034.24     .12       0
#XS Ineff= 2 , 0
       0  166.21     520 6524.33       0     520
Permanent Ineff=
       F       F
#Block Obstruct= 2 ,-1
    4287    5277     495       0    1976     504
Bank Sta=5716.61,6028.73
XS Rating Curve= 0 ,0
Exp/Cntr=0.3,0.1

Type RM Length L Ch R = 1 ,193137  ,57,43,48
BEGIN DESCRIPTION:
This cross section corresponds to cross section 193191 of the non-georeferenced CDC model which was the source of this model.
END DESCRIPTION:
XS GIS Cut Line= 6
 2352785.36338596972022.06525592 2352778.4631137 6971204.4018364
 2352774.1228992 6969863.2558966 2352704.7654264 6967023.4121669
 2352708.2375323 6966507.4401017 2352176.3939033 6965698.3965122
#Sta/Elev= 30
   53.99  509.21  247.89   481.3  936.48  481.42 1004.48   502.3 1024.63   489.3
 1057.99  487.03 1108.82   503.4 1452.78  493.66  1889.3   503.9 2861.37  498.94
 3015.24  505.21 3055.94  495.86 3755.73  499.59  3788.4  492.53 3893.22  504.23
 4012.21  491.64 4043.83  499.51 5630.05  503.84  5747.9  482.99 5813.19  483.84
 5870.72  497.81 5902.14  487.69 5951.19  492.03 6002.89  469.82 6045.64   465.9
 6106.29  469.63 6129.35  498.03 6137.41  498.39 6383.54  491.76 6537.71  509.71
#Mann= 4 ,-1,0
   53.99     .08       0 1004.48     .08       0 5870.72    .055       0
 6137.41     .12       0
#XS Ineff= 2 , 0
       0   53.99     520 6537.71       0     520
Permanent Ineff=
       F       F
#Block Obstruct= 1 ,-1
       0    1889     504
Bank Sta=5870.72,6129.35
XS Rating Curve= 0 ,0
Exp/Cntr=0.3,0.1

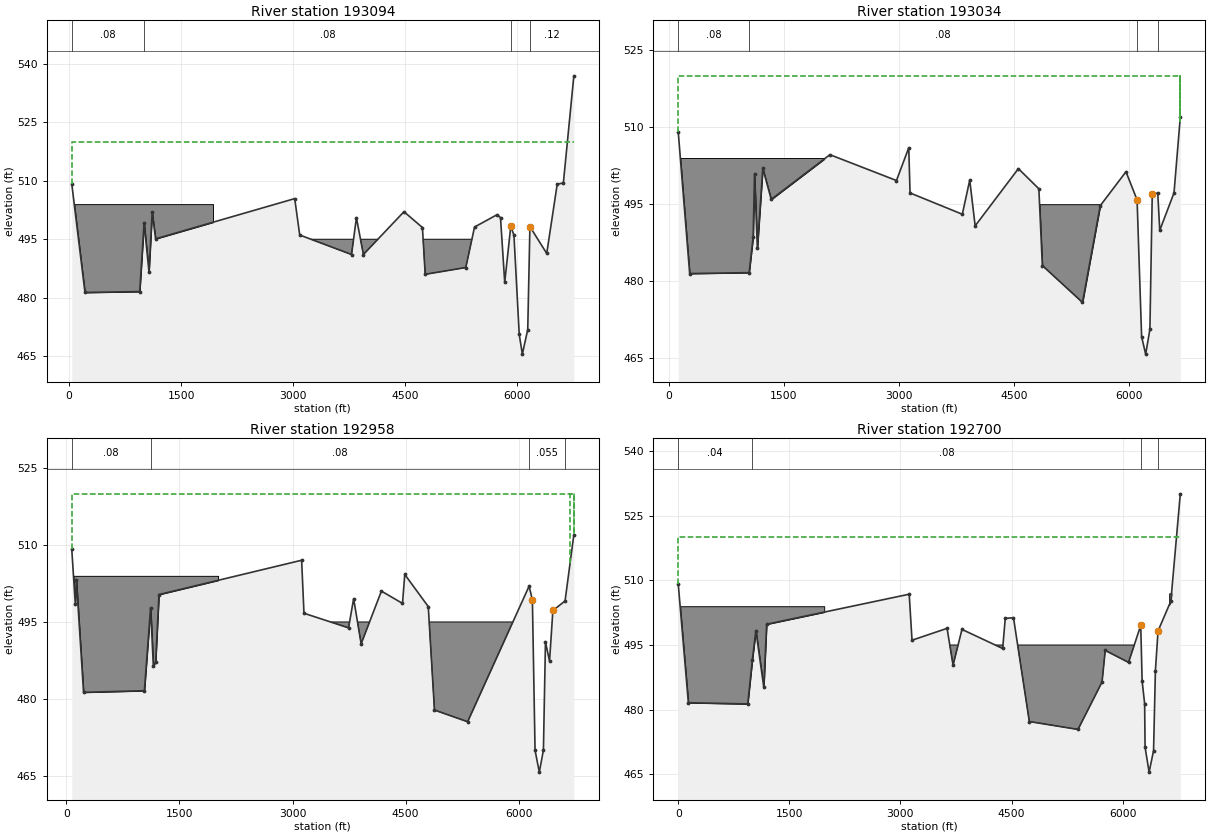
Type RM Length L Ch R = 1 ,193094  ,60,60,66
BEGIN DESCRIPTION:
This cross section corresponds to cross section 193150 of the non-georeferenced CDC model which was the source of this model.
END DESCRIPTION:
XS GIS Cut Line= 6
 2352852.87840286972104.08080362 2352840.5612366 6970218.7025511
 2352837.4241144 6969621.6036281 2352760.3903363  6966987.815267
 2352764.1084071  6966515.620283 2352143.1905934   6965569.92899
#Sta/Elev= 30
   35.86   509.2  212.61  481.34  945.59  481.57 1004.06  499.15 1069.66  486.64
 1112.03   501.9 1158.23   495.1 3020.37  505.42 3087.22  496.08 3780.94  491.08
 3846.26  500.52 3939.83  491.08 4482.74  502.06    4730     498    4767     486
 5310.69  487.74 5427.39  498.13 5728.71  501.29 5775.07  500.54 5831.45  483.94
 5912.64  498.34 5955.03  496.02 6025.82  470.57 6067.43  465.53 6139.66  471.83
 6168.79  498.23 6393.85  491.35 6534.23  509.12 6616.55  509.43 6756.83  536.91
#Mann= 4 ,-1,0
   35.86     .08       0 1004.06     .08       0 5912.64    .055       0
 6168.79     .12       0
#XS Ineff= 2 , 0
       0   35.86     520               0
Permanent Ineff=
       F       F
#Block Obstruct= 2 ,-1
    3029    5483     495       0    1927     504
Bank Sta=5912.64,6168.79
XS Rating Curve= 0 ,0
Exp/Cntr=0.3,0.1

Type RM Length L Ch R = 1 ,193034  ,123,77,86
BEGIN DESCRIPTION:
This cross section corresponds to cross section 193090 of the non-georeferenced CDC model which was the source of this model.
END DESCRIPTION:
XS GIS Cut Line= 5
      2352883.33      6972118.35 2352820.0121124 6966491.7834846
 2352334.5736959 6965753.6684197 2352327.35962016965720.95626289
2352326.231097676965715.83898887
#Sta/Elev= 30
   120.9  509.08  270.24  481.49 1046.04  481.67 1098.25   488.6 1115.99  500.87
 1153.14  486.41 1223.99  501.96 1334.13  495.93 2099.58  504.64  2967.5  499.61
 3127.86  505.99 3144.69  497.19 3826.58  493.04 3923.29   499.7 3993.92  490.78
  4557.8  501.92    4825     498 4870.25  483.06 5394.06  475.87 5625.78  494.71
 5961.22  501.32 6106.15  495.83 6165.19  469.18    6218   465.8 6273.41  470.62
 6304.06  497.07 6375.99  497.14 6401.74  489.91 6587.76   497.2    6670     512
#Mann= 4 ,-1,0
   120.9     .08       0 1046.04     .08       0 6106.15    .055       0
 6375.99     .12       0
#XS Ineff= 2 , 0
       0   120.9     520 6664.76       0     520
Permanent Ineff=
       F       F
#Block Obstruct= 2 ,-1
    4778    5940     495       0    2024     504
Bank Sta=6106.15,6304.06
XS Rating Curve= 0 ,0
Exp/Cntr=0.3,0.1

Type RM Length L Ch R = 1 ,192958  ,130,257,335
BEGIN DESCRIPTION:
This cross section corresponds to cross section 193010 of the non-georeferenced CDC model which was the source of this model.
END DESCRIPTION:
XS GIS Cut Line= 6
 2352971.71732316972172.17847792 2352920.2764783 6967629.3866767
 2352962.6376141 6967475.2199903 2352915.2525382  6966498.299372
 2352430.4598727 6965760.04428682352410.057336856965666.74295198
#Sta/Elev= 30
   71.23  509.17  117.97  498.57  132.87  503.14  227.51  481.27 1034.38  481.58
 1117.05  497.77 1153.08  486.43 1183.83  487.18    1228  500.35 3120.14  507.04
 3151.34   496.7 3742.62  493.85 3810.14  499.54 3909.82  490.74 4178.56  501.02
  4458.1  498.62 4488.22  504.27    4800     498 4882.31  477.81 5322.27  475.53
 6137.45  501.98 6181.08   499.3 6216.49  469.96 6273.04   465.7 6327.41  469.99
 6354.58   491.1 6408.59  487.36 6452.91  497.24 6614.36  499.09    6731     512
#Mann= 4 ,-1,0
   71.23     .08       0 1117.05     .08       0 6137.45    .055       0
 6614.36     .12       0
#XS Ineff= 2 , 0
       0   71.23     520 6681.76       0     520
Permanent Ineff=
       F       F
#Block Obstruct= 2 ,-1
    3136    6169     495       0    2012     504
Bank Sta=6181.08,6452.91
XS Rating Curve= 0 ,0
Exp/Cntr=0.3,0.1

Type RM Length L Ch R = 1 ,192700  ,607,1131,666
BEGIN DESCRIPTION:
This cross section corresponds to cross section 192756 of the non-georeferenced CDC model which was the source of this model.
-------------------------------------------
CDC FW121411-01 Goodman A Gas Well Site Pad
Cross-section 192756 - 193191
Project located in LOB.
-------------------------------------------
END DESCRIPTION:
XS GIS Cut Line= 3
 2353128.2404482 6972246.6721883 2353079.1993948 6966964.3987254
 2352733.0660952 6965508.0504607
#Sta/Elev= 30
       0  509.18  136.61   481.6  938.54  481.32 1000.06  491.43 1048.26  498.35
 1155.25  485.19 1193.84  499.82 3118.81  506.79  3156.6  496.11 3629.96  498.86
 3711.19  490.33 3831.21  498.62 4380.82  494.19 4415.66  501.17 4526.84  501.34
 4740.87  477.23 5398.19   475.4 5722.52   486.4 5765.83  493.74 6080.24  490.96
 6245.12  499.56 6263.85  486.66 6297.54   481.4 6303.81  471.25 6358.17  465.49
 6418.16  470.47 6443.12  489.03 6478.67  498.26 6651.54  505.18 6779.42  530.09
#Mann= 4 ,-1,0
       0     .04       0 1000.06     .08       0 6245.12    .055       0
 6478.67     .07       0
#XS Ineff= 2 , 0
       0       0     520               0
Permanent Ineff=
       F       F
#Block Obstruct= 3 ,-1
    3128    6172     495    6629    6662     507       0    1971     504
Bank Sta=6245.12,6478.67
XS Rating Curve= 0 ,0
Exp/Cntr=0.3,0.1