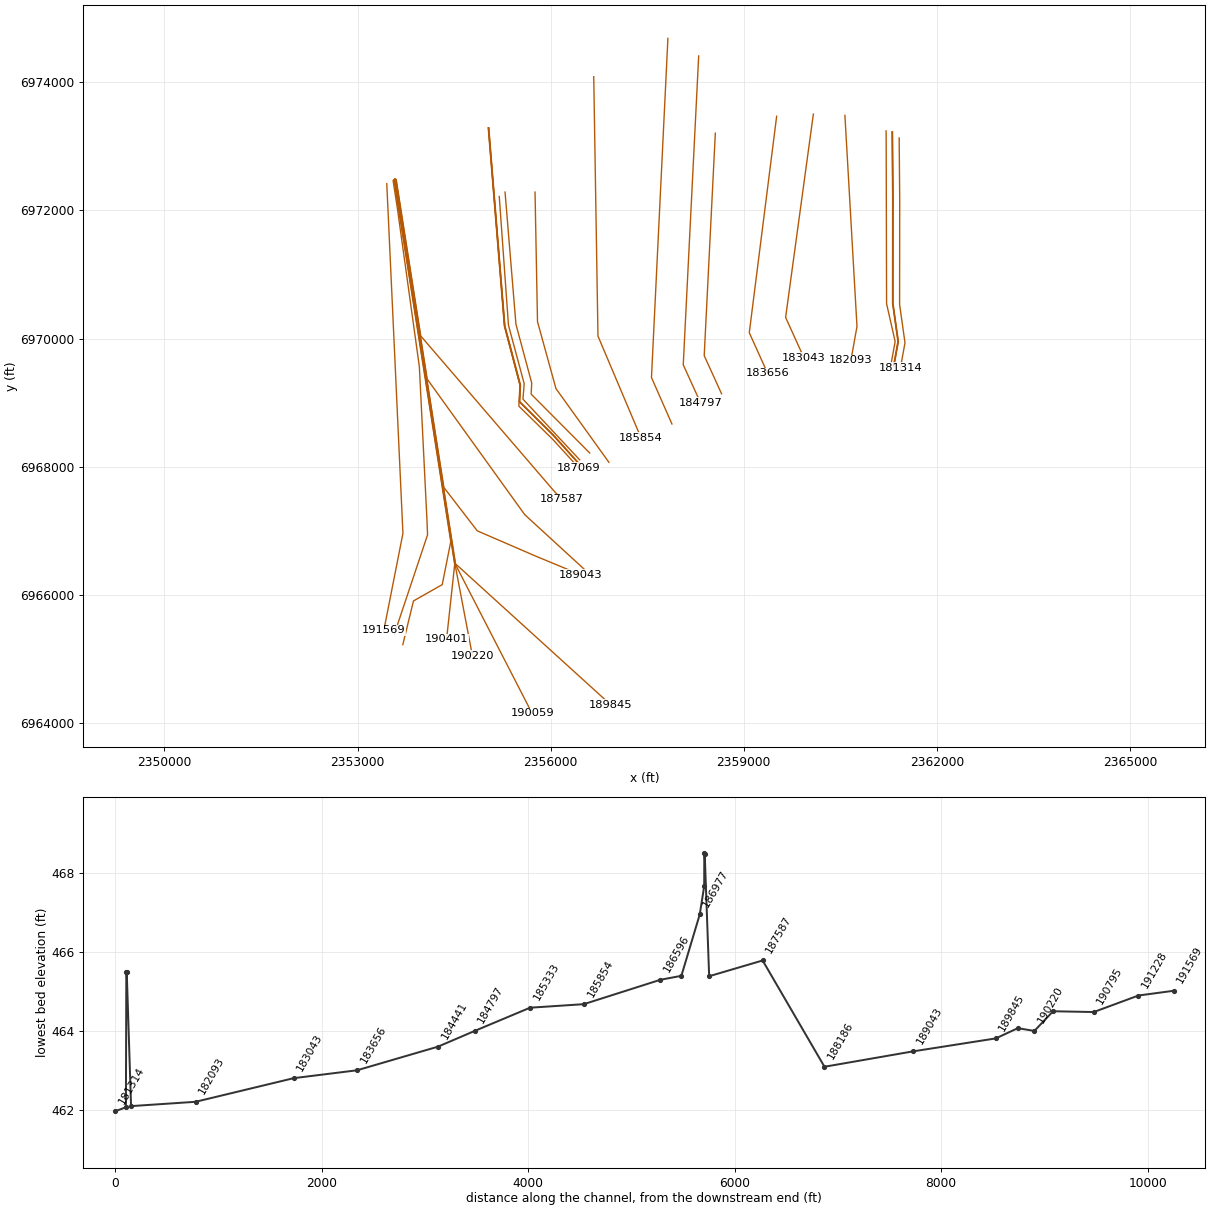
HEC-RAS study CDC_Consolidated_Model.prj: Upper Trinity CDC Consolidated Model

--- CDC_Consolidated_Model.g04 (geometry) --- (continued)

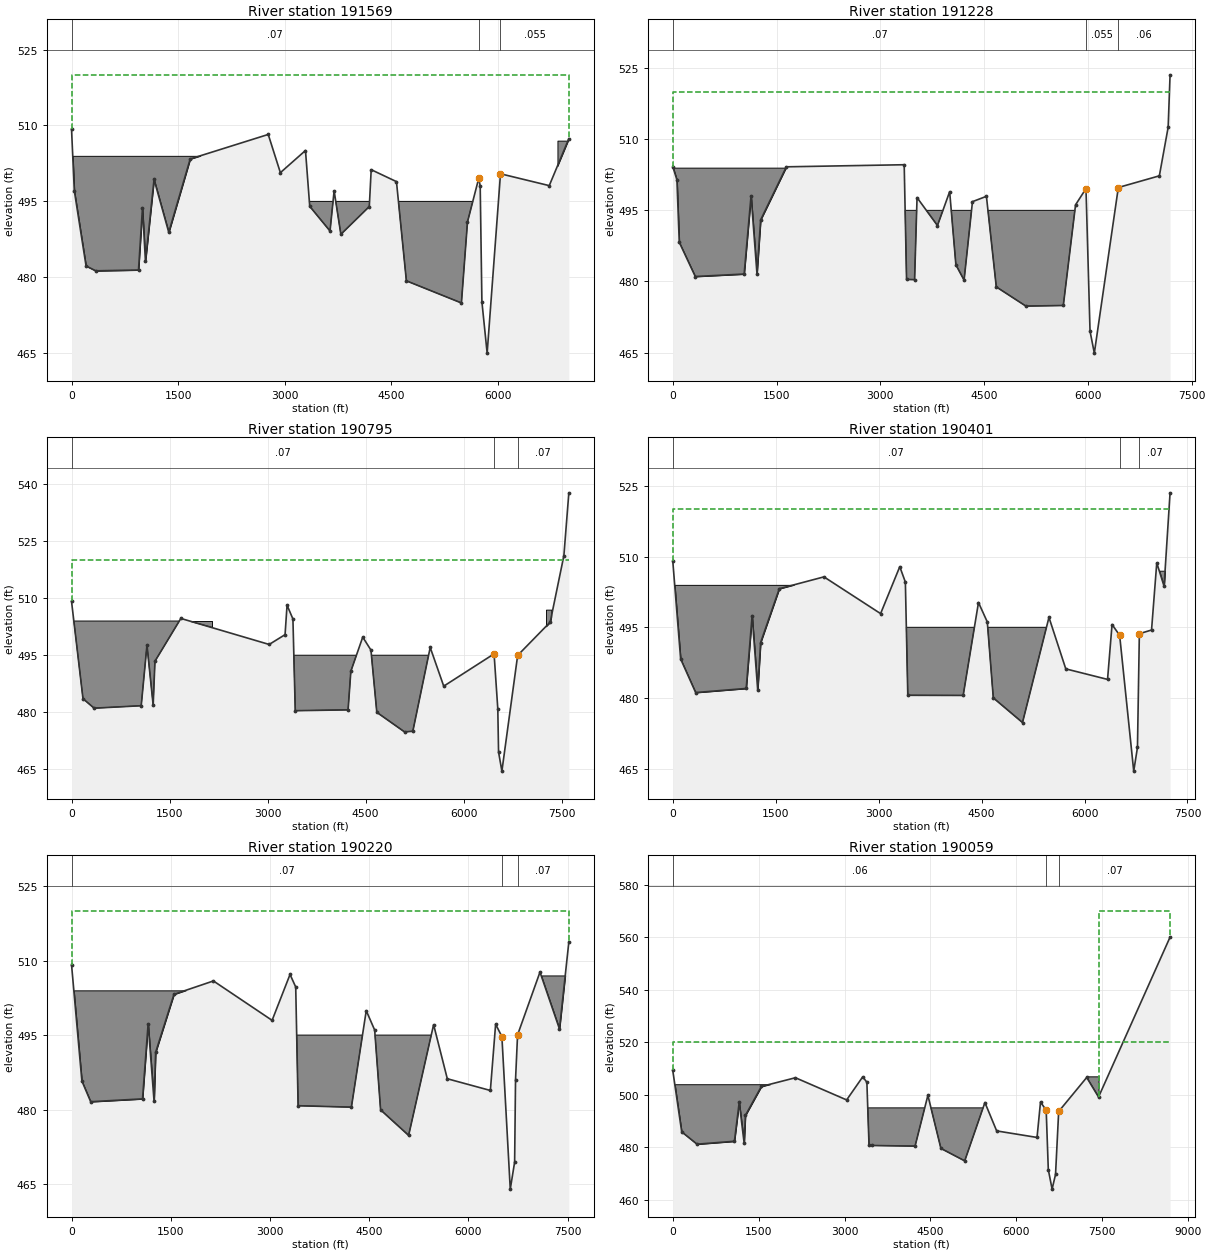
Type RM Length L Ch R = 1 ,191569  ,400,341,222
BEGIN DESCRIPTION:
This cross section corresponds to cross section 191625 of the non-georeferenced CDC model which was the source of this model.
END DESCRIPTION:
XS GIS Cut Line= 3
 2353454.1551259 6972415.7538811  2353705.260242 6966962.8503038
 2353408.5971956  6965451.957321
#Sta/Elev= 30
       0  509.26      39  497.12   204.5  482.24  340.91  481.28  942.64  481.44
  998.62  493.66 1040.32  483.14 1161.26  499.33 1368.44  488.88  1670.2  503.38
 2768.11  508.22 2938.86  500.67  3292.2  505.05 3352.13  494.02 3637.63  489.14
 3695.25  497.09 3790.16  488.49 4190.42  493.98    4217  501.26 4572.67   498.9
 4712.12   479.3 5486.61  474.93 5572.24  490.94 5732.33  499.66 5751.04  497.95
 5774.91  475.17 5848.65  465.02 6036.57  500.45 6722.72  498.11 6998.43  507.39
#Mann= 3 ,-1,0
       0     .07       0 5732.33    .055       0 6036.57    .055       0
#XS Ineff= 2 , 0
       0       0     520 6998.43       0     520
Permanent Ineff=
       F       F
#Block Obstruct= 3 ,-1
    3305    5693     495    6838    6998     507       0    2106     504
Bank Sta=5732.33,6036.57
XS Rating Curve= 0 ,0
Exp/Cntr=0.3,0.1

Type RM Length L Ch R = 1 ,191228  ,284,433,141
BEGIN DESCRIPTION:
This cross section corresponds to cross section 191291 of the non-georeferenced CDC model which was the source of this model.
END DESCRIPTION:
XS GIS Cut Line= 6
  2353552.599145 6972462.9669784 2353620.0158925 6972021.9690989
 2353960.6323372 6969558.7702851 2354079.3820998  6967149.916179
 2354087.7157445 6966940.5412697 2353571.0487988 6965390.5410888
#Sta/Elev= 30
       0  504.23   60.11  501.43   94.05  488.26  325.34  481.05 1031.92  481.57
 1131.88  498.08 1217.34  481.61 1270.59  492.99 1642.22  504.17 3345.13  504.61
 3379.14  480.43  3495.4  480.39 3530.82  497.68 3825.93  491.79 4002.17  498.93
 4092.24  483.51 4210.62  480.29 4331.85  496.83 4533.62  497.95  4676.1  478.86
 5103.96  474.81  5644.9  474.94 5821.76  496.16 5972.63  499.58 6031.15  469.52
  6093.2   464.9 6440.01  499.81 7033.03  502.27 7160.27  512.52 7187.94  523.56
#Mann= 3 ,-1,0
       0     .07       0 5972.63    .055       0 6440.01     .06       0
#XS Ineff= 2 , 0
       0       0     520               0
Permanent Ineff=
       F       F
#Block Obstruct= 2 ,-1
    3343    5836     495       0    2088     504
Bank Sta=5972.63,6440.01
XS Rating Curve= 0 ,0
Exp/Cntr=0.3,0.1

Type RM Length L Ch R = 1 ,190795  ,5,394,616
BEGIN DESCRIPTION:
This cross section corresponds to cross section 190850 of the non-georeferenced CDC model which was the source of this model.
END DESCRIPTION:
XS GIS Cut Line= 6
 2353565.9566837 6972477.4829845 2354046.7762485 6969402.5125301
 2354448.1848144 6966835.3648757 2354315.9538162   6966164.24788
 2353868.8366297 6965909.4975494 2353703.2560966 6965227.3501749
#Sta/Elev= 30
       0  509.16  175.37  483.55  345.87  481.05 1066.59   481.7 1154.68  497.65
 1249.49  481.85 1276.82  493.41 1673.24  504.68 3024.75  497.83 3268.02  500.41
 3298.54  508.16 3388.31  504.54 3424.13  480.39 4232.66  480.61 4274.88  490.77
 4456.81  499.76 4582.46  496.35 4672.22  479.96 5097.04   474.8 5223.47  474.98
  5489.5  497.04 5696.43  486.85 6466.94  495.36 6523.81  480.92 6535.53   469.5
 6586.55  464.48 6827.82  494.95 7326.43  503.73 7535.27  521.21 7611.25  537.75
#Mann= 3 ,0,0
       0     .07       0 6466.94     .05       0 6827.82     .07       0
#XS Ineff= 2 , 0
       0       0     520               0
Permanent Ineff=
       F       F
#Block Obstruct= 3 ,-1
    3399    5489     495    7262    7342     507       0    2144     504
Bank Sta=6466.94,6827.82
XS Rating Curve= 0 ,0
Exp/Cntr=0.3,0.1

Type RM Length L Ch R = 1 ,190401  ,1,181,319
BEGIN DESCRIPTION:
This cross section corresponds to cross section 190456 of the non-georeferenced CDC model which was the source of this model.
END DESCRIPTION:
XS GIS Cut Line= 6
 2353570.8966569 6972478.2554258 2354051.7162213 6969403.2849736
 2354317.7046715 6967702.1903658 2354448.8880042 6966863.2331041
 2354508.9223442 6966479.2914287  2354382.983564 6965311.0014349
#Sta/Elev= 30
       0   509.1  115.02  488.27  333.58  481.16 1070.24  482.03 1156.45  497.47
 1238.06  481.67 1280.55  491.77 1552.48  503.18 2203.02  505.69  3028.6   497.9
 3308.18  507.85 3389.58  504.58 3425.07  480.58 4232.14  480.55 4454.99  500.25
 4583.56  496.13 4670.93  480.03 5096.61   474.8 5482.09   497.1 5727.24  486.18
 6335.81  483.95 6401.47  495.59 6512.03   493.3 6717.22   464.5 6771.75  469.52
 6799.31  493.64 6976.88  494.42    7053  508.67 7159.46   503.7 7246.92  523.51
#Mann= 3 ,0,0
       0     .07       0 6512.03     .05       0 6799.31     .07       0
#XS Ineff= 2 , 0
       0       0     520               0
Permanent Ineff=
       F       F
#Block Obstruct= 3 ,-1
    3398    5482     495    7053    7199     507       0    2140     504
Bank Sta=6512.03,6799.31
XS Rating Curve= 0 ,0
Exp/Cntr=0.3,0.1

Type RM Length L Ch R = 1 ,190220  ,1,161,285
BEGIN DESCRIPTION:
This cross section corresponds to cross section 190275 of the non-georeferenced CDC model which was the source of this model.
-------------------------------
CDC FW021297-1 Randol Mill Road
Located in ROB.
Cross-sections 190275 - 205240
-------------------------------
END DESCRIPTION:
XS GIS Cut Line= 6
 2353575.8366299 6972479.0278671  2354056.656194 6969404.0574172
 2354322.6446458 6967702.9627996 2354453.8279779 6966864.0055417
 2354510.9875144 6966498.4492909 2354783.9703103 6965058.0982749
#Sta/Elev= 30
       0  509.18  156.65  485.75  289.52  481.59 1073.51  482.16 1158.47  497.29
  1248.1  481.67  1271.9  491.53 1548.96   503.2  2145.3  505.89 3032.45  497.96
  3303.7   507.2 3389.61  504.67    3426  480.78  4231.6  480.49 4455.97  499.91
 4583.31  496.01 4672.98  479.95 5096.75  474.81 5474.35  497.09 5681.61  486.21
 6332.68  483.85 6412.19  497.19 6506.91  494.69 6633.52     464 6699.51  469.43
 6713.28  486.03 6743.96  495.03 7082.81  507.67 7377.54  496.23 7519.24  513.74
#Mann= 3 ,-1,0
       0     .07       0 6506.91     .05       0 6743.96     .07       0
#XS Ineff= 2 , 0
       0       0     520               0
Permanent Ineff=
       F       F
#Block Obstruct= 3 ,-1
    3398    5474     495    7082    7471     507       0    2145     504
Bank Sta=6506.91,6743.96
XS Rating Curve= 0 ,0
Exp/Cntr=0.3,0.1

Type RM Length L Ch R = 1 ,190059  ,1,213,381
BEGIN DESCRIPTION:
This cross section corresponds to cross section 190115 of the non-georeferenced CDC model which was the source of this model.
END DESCRIPTION:
XS GIS Cut Line= 6
 2353580.7766031 6972479.8003084 2354061.5961679 6969404.8298539
 2354327.5846207 6967703.7352294 2354458.7679521 6966864.7779757
 2354518.2680876 6966484.25273452355711.847711056964156.86448458
#Sta/Elev= 30
       0  509.27  156.15  485.88  423.91  481.18 1076.79  482.29 1160.49  497.11
 1246.54  481.62 1268.72  492.12 1547.06  503.14  2142.1  506.47  3036.3  498.02
 3316.84   506.8 3389.63  504.77 3426.94  480.97 3473.23  480.68 4231.08  480.43
  4455.1  499.77 4682.52  479.56 5098.08  474.82 5450.68  497.03  5656.1  486.23
    6361  483.74 6421.42  497.21 6520.72  494.14 6557.71   471.5 6623.91  464.07
 6683.91  469.66  6738.8  493.62 7228.24  506.57 7434.86  499.13    8684     560
#Mann= 3 ,0,0
       0     .06       0 6520.72     .05       0  6738.8     .07       0
#XS Ineff= 2 , 0
       0       0     520 7434.86       0     570
Permanent Ineff=
       F       F
#Block Obstruct= 3 ,-1
    3399    5467     495    7228 7434.86     507       0    2142     504
Bank Sta=6520.72,6738.8
XS Rating Curve= 0 ,0
Exp/Cntr=0.3,0.1

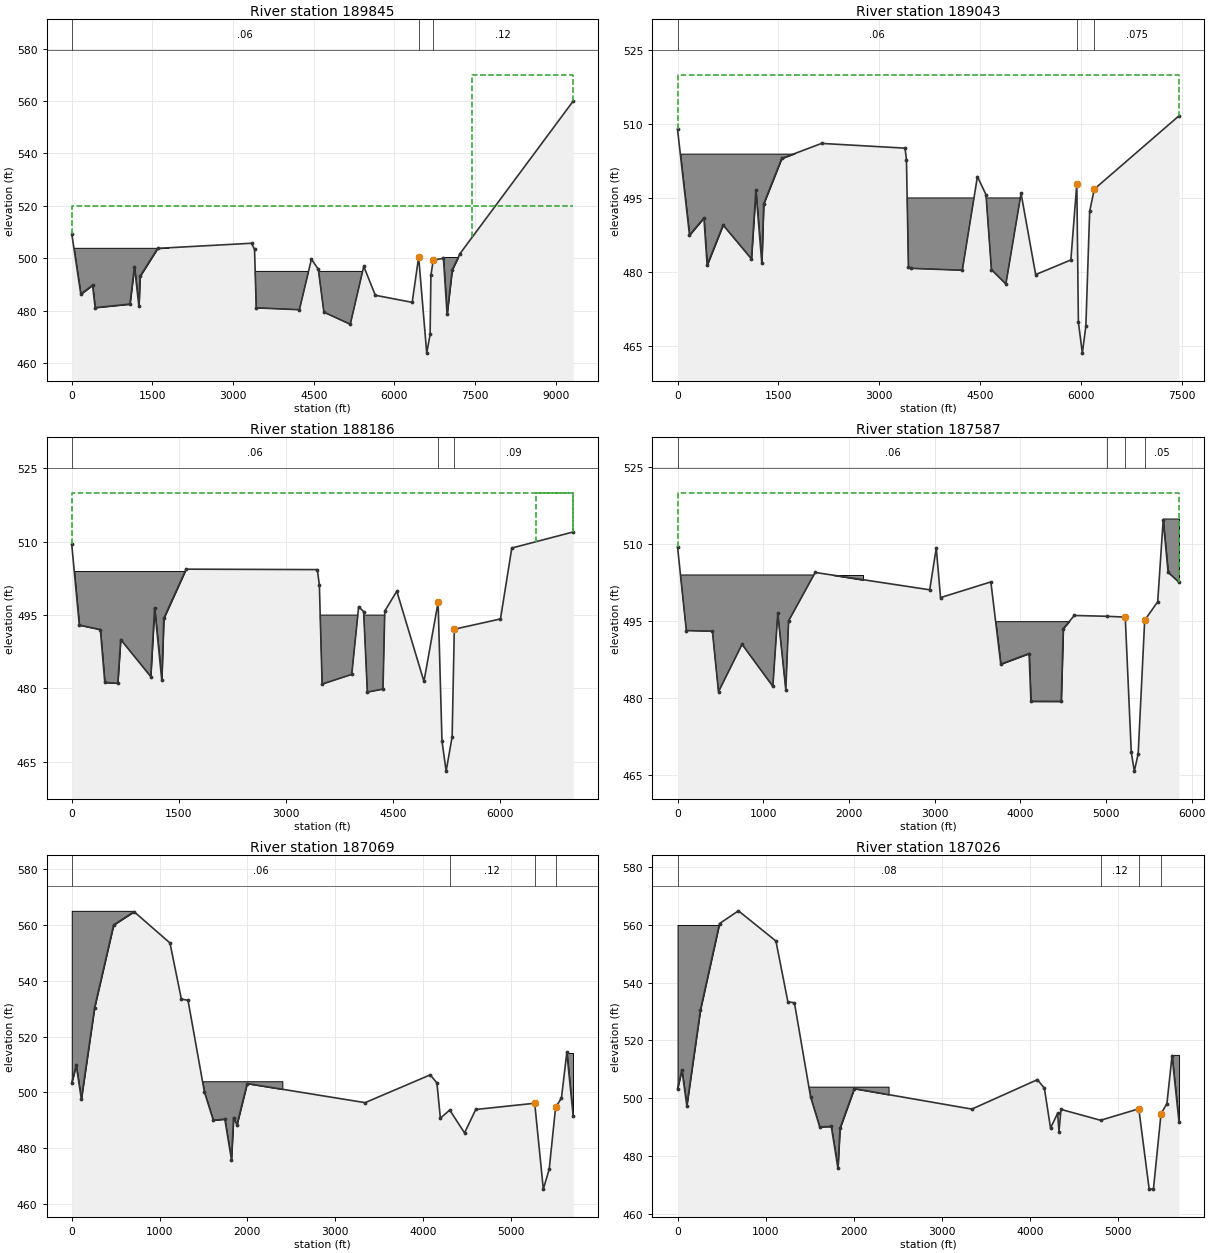
Type RM Length L Ch R = 1 ,189845  ,1,803,909
BEGIN DESCRIPTION:
This cross section corresponds to cross section 189901 of the non-georeferenced CDC model which was the source of this model.
END DESCRIPTION:
XS GIS Cut Line= 6
 2353582.5178905 6972482.2357489 2353586.2020718 6972477.4678726
 2354066.5361417 6969405.6022906 2354332.5245957 6967704.5076593
 2354522.7915073 6966487.68918842356929.134977186964294.15155086
#Sta/Elev= 30
       0   509.4   168.6  486.31  387.15  489.74  434.83  481.18  1082.1  482.52
 1166.09  496.83 1249.35  481.64 1270.99  493.16 1597.54  503.78 3342.72  505.74
 3399.29  503.39 3430.76  481.08 4233.43  480.37 4456.98  499.67 4585.68  495.78
 4688.84  479.43 5179.28  474.82 5430.01  496.91 5644.99  485.89 6330.29  483.18
 6451.17  500.51 6600.84  463.81 6663.77  470.97 6678.48  493.45 6722.35  499.35
 6911.75     500 6979.17  478.61 7073.91  495.56 7218.78  501.75 9324.67     560
#Mann= 3 ,0,0
       0     .06       0 6451.17     .05       0 6722.35     .12       0
#XS Ineff= 2 , 0
       0       0     520 7443.67       0     570
Permanent Ineff=
       F       F
#Block Obstruct= 3 ,-1
    3300    5430     495    6898    7218   500.5       0    2074     504
Bank Sta=6451.17,6722.35
XS Rating Curve= 0 ,0
Exp/Cntr=0.3,0.1

Type RM Length L Ch R = 1 ,189043  ,739,856,528
BEGIN DESCRIPTION:
This cross section corresponds to cross section 189097 of the non-georeferenced CDC model which was the source of this model.
END DESCRIPTION:
XS GIS Cut Line= 6
 2353583.9913032 6972482.6603119 2353590.8445572 6972480.1428294
 2354341.7134457 6967678.1069597 2354860.0492788 6967002.4654647
 2355765.3872703 6966609.4866348  2356461.301574 6966320.0472803
#Sta/Elev= 30
       0  508.92  177.87  487.46  392.64  490.94  440.08  481.34  677.63   489.5
 1098.92  482.62 1165.15  496.57 1253.87  481.72 1281.94   493.8 1549.34  503.01
 2142.02  506.07 3383.74  505.11 3405.36   502.8 3434.92  481.03 3468.25   480.7
  4236.1  480.31 4461.13  499.34 4588.63  495.66 4669.68  480.44 4884.29  477.52
 5110.34  495.92 5327.62  479.43 5851.01   482.4 5939.63  497.83 5963.16  469.77
 6021.95  463.48 6074.14  468.98 6130.96  492.31 6200.58   496.8 7459.91  511.68
#Mann= 3 ,0,0
       0     .06       0 5939.63     .05       0 6200.58    .075       0
#XS Ineff= 2 , 0
       0       0     520               0
Permanent Ineff=
       F       F
#Block Obstruct= 2 ,-1
    3410    5110     495       0    2078     504
Bank Sta=5939.63,6200.58
XS Rating Curve= 0 ,0
Exp/Cntr=0.3,0.1

Type RM Length L Ch R = 1 ,188186  ,510,599,593
BEGIN DESCRIPTION:
This cross section corresponds to cross section 188241 of the non-georeferenced CDC model which was the source of this model.
END DESCRIPTION:
XS GIS Cut Line= 6
 2353581.7955356 6972484.7269168 2353595.8144979   6972480.72362
  2353971.235672 6970079.8026428 2354082.5483857 6969367.9295718
 2355596.2065314 6967255.89486392356522.372424766966403.34221972
#Sta/Elev= 30
       0  509.45     106  492.96  400.85  492.04  462.83  481.23  644.41  481.06
  685.35     490 1106.09  482.43 1160.58  496.49 1260.87   481.7 1289.47  494.35
  1601.1  504.39 3438.74   504.3 3467.57  501.17  3506.5  480.88 3921.21  482.87
 4017.81  496.72  4088.1  495.71 4139.76  479.24 4358.53  479.86  4383.9  495.83
 4552.26  499.88 4932.25  481.44 5130.54  497.61 5184.75  469.27 5242.88  463.09
 5326.84  470.11 5357.36  492.11 6003.91  494.21 6162.45  508.71 7022.45     512
#Mann= 3 ,-1,0
       0     .06       0 5130.54     .05       0 5357.36     .09       0
#XS Ineff= 2 , 0
       0       0     520 6501.45       0     520
Permanent Ineff=
       F       F
#Block Obstruct= 2 ,-1
    3470    4606     495       0    2087     504
Bank Sta=5130.54,5357.36
XS Rating Curve= 0 ,0
Exp/Cntr=0.3,0.1

Type RM Length L Ch R = 1 ,187587  ,569,518,549
BEGIN DESCRIPTION:
This cross section corresponds to cross section 187647 of the non-georeferenced CDC model which was the source of this model.
END DESCRIPTION:
XS GIS Cut Line= 5
 2353580.5039075 6972486.0831262 2353600.7024976 6972481.8284456
 2353982.4950238  6970040.160931  2356037.893289 6967639.7841515
 2356174.1682879 6967492.6854555
#Sta/Elev= 30
       0  509.46  102.74  493.17   407.1  493.03  478.08  481.25  753.03  490.49
 1112.37   482.3 1170.07  496.54 1263.72  481.65 1296.32  495.06 1606.63  504.49
 2943.26  501.11 3019.47  509.24 3069.56  499.59 3656.78  502.65 3772.41  486.63
 4102.78   488.7 4124.08  479.39 4477.81  479.38 4501.99  493.57 4630.64  496.11
 5014.72  495.95 5225.24  495.79 5295.56  469.46  5331.3  465.79 5376.07  469.17
 5452.24  495.19 5603.94  498.78 5667.98   514.7 5725.35  504.53 5852.64  502.57
#Mann= 4 ,-1,0
       0     .06       0 5014.72     .09       0 5225.24    .035       0
 5452.24     .05       0
#XS Ineff= 2 , 0
       0       0     520               0
Permanent Ineff=
       F       F
#Block Obstruct= 3 ,-1
    5667    5852     515    3694    5111     495       0    2159     504
Bank Sta=5225.24,5452.24
XS Rating Curve= 0 ,0
Exp/Cntr=0.3,0.1

Type RM Length L Ch R = 1 ,187069  ,43,43,43
BEGIN DESCRIPTION:
This cross section corresponds to cross section 187126 of the non-georeferenced CDC model which was the source of this model.
END DESCRIPTION:
XS GIS Cut Line= 6
 2355030.2006701 6973284.3490503 2355280.5893523 6970196.0734002
 2355522.6350467 6969272.7090083 2355505.8401202 6968946.4146536
 2356036.5789468 6968424.6031872 2356432.0792441  6967988.981145
#Sta/Elev= 30
       0  503.41   50.84  509.79  109.41   497.6  260.38  530.39  476.96  559.94
  709.88   564.7 1118.95   553.5 1248.57  533.42 1324.54  532.98 1511.29  500.15
 1612.46  490.04 1743.67  490.44 1819.25  475.95 1843.53  490.99 1881.54  488.39
 1998.17  503.18 3341.56  496.34  4083.6  506.29 4159.82   503.4 4199.24  490.79
  4305.7  493.69  4474.6  485.52 4602.23   493.9 5273.85  496.13 5371.85  465.39
 5439.07  472.53 5511.69  494.67 5578.13  497.94 5639.62  514.31 5712.37  491.52
#Mann= 4 ,-1,0
       0     .06       0  4305.7     .12       0 5273.85    .035       0
 5511.69     .08       0
#Block Obstruct= 3 ,-1
       0     704     565    5639    5712     514     704    2399     504
Bank Sta=5273.85,5511.69
XS Rating Curve= 0 ,0
Exp/Cntr=0.3,0.1

Type RM Length L Ch R = 1 ,187026  ,4,4,4
BEGIN DESCRIPTION:
This cross section corresponds to cross section 187080 of the non-georeferenced CDC model which was the source of this model.
END DESCRIPTION:
XS GIS Cut Line= 6
  2355034.187587 6973284.6722984 2355284.5478373  6970196.747333
 2355526.6616585 6969273.1230483 2355513.3928139  6969015.339526
 2356035.0545063 6968495.8877612 2356466.7776305 6968014.9053763
#Sta/Elev= 30
       0  503.24   49.53  509.82  105.24  497.43  260.12  530.62  476.48  560.48
  691.35  564.89 1116.93  554.44 1252.75  533.39 1327.21  533.04 1511.03  500.37
 1613.98  490.07 1745.62   490.2 1820.96  475.76 1844.45  489.57  2006.8   503.3
 3341.13  496.22 4085.83  506.41 4164.83  503.47 4235.12  489.66 4315.64  494.78
 4330.75  488.38  4353.4  496.12 4803.16  492.35 5237.14  496.32 5354.82   468.5
 5403.08   468.5 5489.58  494.65  5556.4  498.11 5614.38  514.71 5693.55  491.76
#Mann= 4 ,-1,0
       0     .08       0 4803.16     .12       0 5237.14    .035       0
 5489.58     .05       0
#Block Obstruct= 3 ,-1
       0     516     560    5614    5693     515     516    2396     504
Bank Sta=5237.14,5489.58
XS Rating Curve= 0 ,0
Exp/Cntr=0.3,0.1

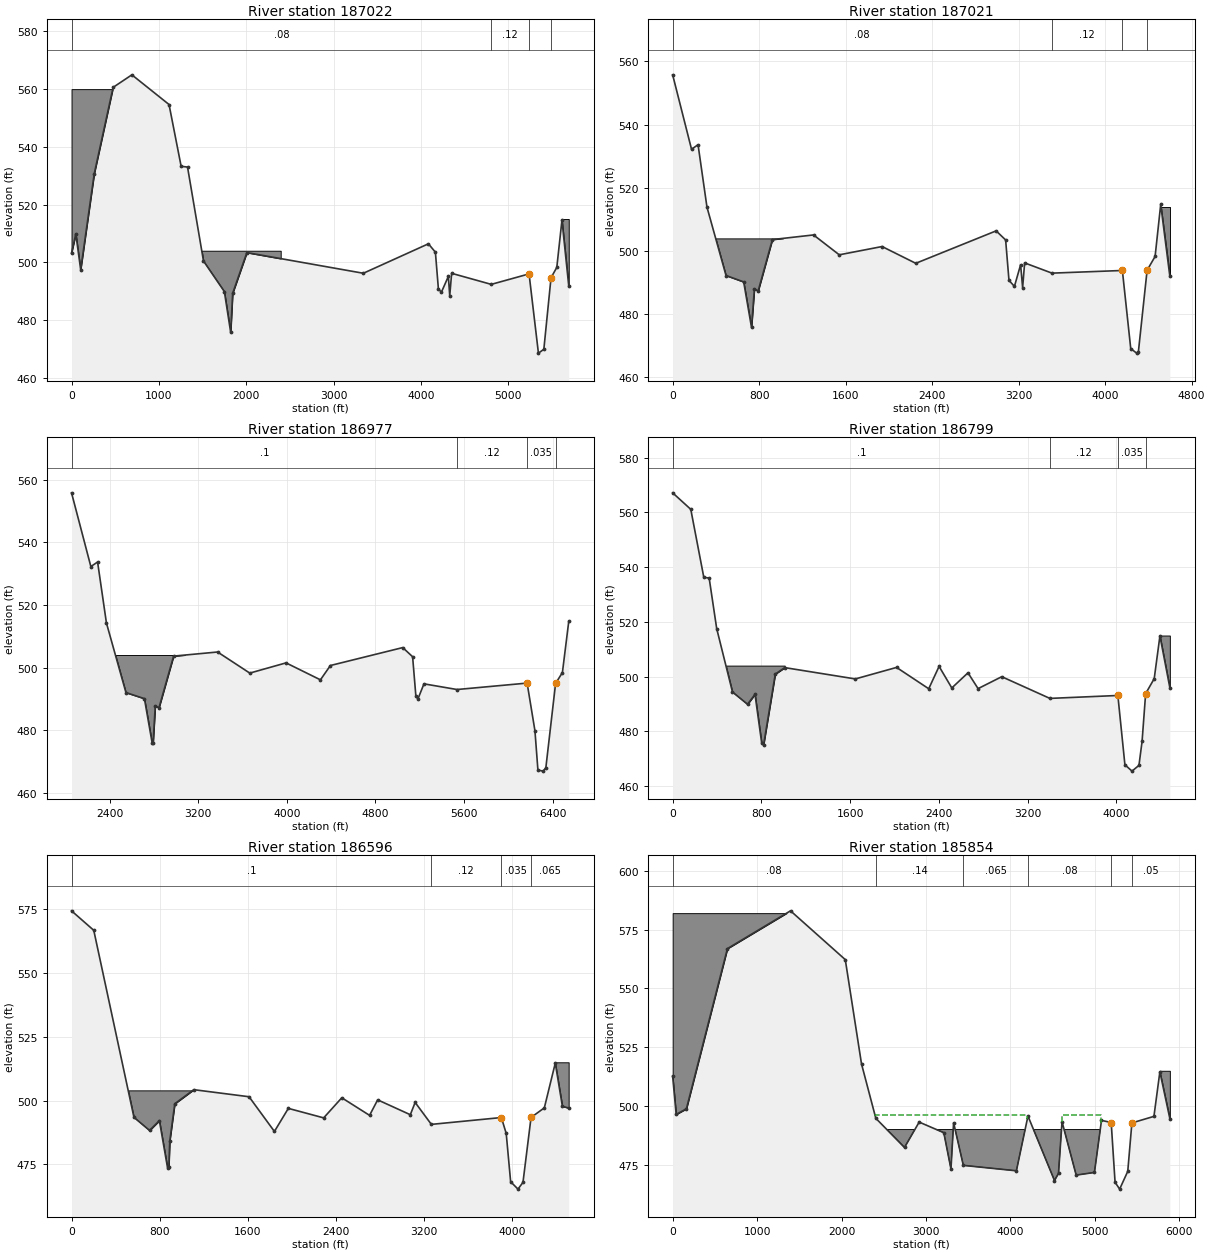
Type RM Length L Ch R = 1 ,187022  ,1,1,1
BEGIN DESCRIPTION:
This cross section corresponds to cross section 187076 of the non-georeferenced CDC model which was the source of this model.
END DESCRIPTION:
XS GIS Cut Line= 6
  2355035.184316 6973284.7531104 2355285.5374585 6970196.9158162
 2355527.6683105 6969273.2265619 2355514.4145365 6969015.7359138
 2356038.0448299 6968498.5444441 2356469.6945313 6968017.6424713
#Sta/Elev= 30
       0   503.2   49.21  509.83  104.83  497.43  260.06  530.68  476.36  560.62
  691.03  564.96 1116.42  554.67 1255.07  533.25 1328.19     533 1510.97  500.43
 1749.73  489.85 1822.09  475.76 1845.08  489.26 2007.47  503.35 3341.02  496.19
 4086.21   506.4 4166.09  503.49 4200.56  490.74  4235.2  489.65 4314.54   495.1
 4330.31  488.39  4352.1  496.17 4805.91  492.34 5238.52  495.97 5345.77  468.51
 5407.83  469.83 5490.04  494.64  5556.1  498.21 5615.22   514.6 5692.93  491.83
#Mann= 4 ,-1,0
       0     .08       0 4805.91     .12       0 5238.52    .035       0
 5490.04     .05       0
#Block Obstruct= 3 ,-1
       0     740     560     740    2395     504    5615 5692.93     515
Bank Sta=5238.52,5490.04
XS Rating Curve= 0 ,0
Exp/Cntr=0.3,0.1

Type RM Length L Ch R = 1 ,187021  ,43,43,43
BEGIN DESCRIPTION:
This cross section corresponds to cross section 187075 of the non-georeferenced CDC model which was the source of this model.
END DESCRIPTION:
XS GIS Cut Line= 6
  2355039.171234 6973285.0763584 2355289.4959434  6970197.589749
 2355531.6949215 6969273.6406049 2355518.5014268 6969017.3214648
 2356038.8417115 6968499.1848483 2356470.4237565 6968018.3267451
#Sta/Elev= 30
       0  555.77  174.51  532.21  234.91  533.65  317.32   513.9  493.54  492.25
  656.89  490.22  729.26  475.85   756.2  488.05  790.39   487.3  922.41  503.62
 1303.07  505.09 1540.76   498.8  1936.9  501.42 2248.44  496.11 2991.78  506.38
 3079.52   503.5 3110.52   490.7 3160.91  488.81 3217.99  495.65 3236.73  488.42
 3255.28  496.24    3508     493 4159.15  493.84 4236.47  469.14 4290.62  467.68
 4307.57  468.18 4387.91  493.91 4461.84  498.28 4513.72  514.73 4598.45  491.96
#Mann= 4 ,-1,0
       0     .08       0    3508     .12       0 4159.15    .035       0
 4387.91    .065       0
#Block Obstruct= 2 ,-1
       0    1303     504    4513 4598.45     514
Bank Sta=4159.15,4387.91
XS Rating Curve= 0 ,0
Exp/Cntr=0.3,0.1

Type RM Length L Ch R = 1 ,186977  ,176,178,178
BEGIN DESCRIPTION:
This cross section corresponds to cross section 187025 of the non-georeferenced CDC model which was the source of this model.
END DESCRIPTION:
XS GIS Cut Line= 6
  2355201.526031 6972215.7832028      2355279.36      6971122.88
      2355344.47      6970208.64      2355588.63      6969297.12
      2355569.64      6969055.67  2356449.925915 6968110.2180641
#Sta/Elev= 30
    2056  555.76 2230.47  532.24 2291.39  533.68 2371.23  514.22 2547.28  492.03
 2714.14  490.09 2784.76  475.83 2792.64  475.94 2812.17  487.74 2845.76  487.19
 2977.72  503.66  3374.9  504.97 3665.66  498.24    3993   501.5 4303.61  496.09
 4393.71  500.66 5046.75  506.38 5135.99  503.46 5165.48   490.9 5184.14     490
  5238.5  494.81    5537     493 6170.02  495.05  6240.6  479.85 6267.54   467.3
  6314.8  466.96 6339.24  468.06  6427.1  494.93  6488.7  498.42 6545.89  514.71
#Mann= 4 ,-1,0
    2056      .1       0    5537     .12       0 6170.02    .035       0
  6427.1    .065       0
#Block Obstruct= 1 ,-1
    2056    3361     504
Bank Sta=6170.02,6427.1
XS Rating Curve= 0 ,0
Exp/Cntr=0.3,0.1

Type RM Length L Ch R = 1 ,186799  ,199,203,207
BEGIN DESCRIPTION:
This cross section corresponds to cross section 186871 of the non-georeferenced CDC model which was the source of this model.
END DESCRIPTION:
XS GIS Cut Line= 6
  2355291.337509 6972284.4097219  2355368.410033 6971345.3615282
 2355460.4239571 6970224.2679699 2355705.2154622 6969308.0352223
 2355696.9690877 6969133.9899667 2356606.2966653 6968216.7076806
#Sta/Elev= 30
       0  567.19  163.41  561.15   280.8  536.28  329.12  536.01  397.01  517.52
  539.14  494.35  674.96  489.85  742.19   493.5  802.67  475.63  819.61  474.99
  924.84  500.89 1010.44  503.26 1646.52  499.12 2018.03  503.33 2307.97  495.53
 2401.24  503.71 2515.92  495.82 2661.76  501.36 2752.78  495.58 2966.05  499.94
    3400     492  4012.5  493.07 4076.07  467.73    4140   465.4 4202.74  467.51
 4230.74  476.24 4262.89  493.74 4340.25  499.23 4391.71  514.86  4481.3  495.89
#Mann= 4 ,-1,0
       0      .1       0    3400     .12       0  4012.5    .035       0
 4262.89     .06       0
#Block Obstruct= 2 ,-1
     476    1010     504    4391    4481     515
Bank Sta=4012.5,4262.89
XS Rating Curve= 0 ,0
Exp/Cntr=0.3,0.1

Type RM Length L Ch R = 1 ,186596  ,891,742,673
BEGIN DESCRIPTION:
This cross section corresponds to cross section 186691 of the non-georeferenced CDC model which was the source of this model.
END DESCRIPTION:
XS GIS Cut Line= 6
   2355757.17558 6972283.8549662     2355775.952     6971293.699
     2355795.483     6970263.751     2356081.942     6969220.782
 2356631.1696476 6968453.2608311  2356904.680669 6968071.0413639
#Sta/Elev= 30
       0  574.35  201.97  566.71  566.98  493.44  708.77  488.29  797.94  492.16
  871.79  473.73  883.72  474.02  892.38  484.18  937.86  498.76 1110.26  504.27
 1612.38   501.5 1842.68   487.9 1969.13  496.94 2289.95  493.22 2454.63  501.09
 2706.86  494.21 2780.51  500.28 3076.98  494.46 3120.84  499.27 3268.03  490.67
 3903.97  493.35 3947.96  487.11 3988.07   468.2    4055   465.3 4100.25  467.97
 4173.45  493.38 4294.17  497.15 4393.54  514.67 4458.17  497.75 4515.85  497.08
#Mann= 4 ,-1,0
       0      .1       0 3268.03     .12       0 3903.97    .035       0
 4173.45    .065       0
#Block Obstruct= 2 ,-1
     497    1118     504    4393    4515     515
Bank Sta=3903.97,4173.45
XS Rating Curve= 0 ,0
Exp/Cntr=0.3,0.1

Type RM Length L Ch R = 1 ,185854  ,521,521,521
BEGIN DESCRIPTION:
This cross section corresponds to cross section 185909 of the non-georeferenced CDC model which was the source of this model.
END DESCRIPTION:
XS GIS Cut Line= 3
  2356668.949034 6974083.7043535 2356734.6034293 6970039.7026307
 2357403.7955759 6968451.8970062
#Sta/Elev= 30
       0  512.68    41.7  496.44  162.98  498.85  648.47  566.92 1395.66  582.99
 2044.07  562.24 2236.28  517.89 2405.72  494.78 2745.42  482.39 2918.87  493.18
 3210.55  488.67 3295.37  473.26 3326.57  492.91 3441.88  474.78 4070.08  472.47
 4207.08  495.74 4521.23  468.33 4568.79  471.36 4610.48  493.34 4778.03  470.64
 4994.26  471.77 5077.71  493.91 5192.58     493 5238.41   467.6 5292.67  464.68
 5388.76  472.25 5437.64  492.82 5698.67  495.61 5768.94  514.56 5887.35  494.64
#Mann= 6 ,-1,0
       0     .08       0 2405.72     .14       0 3441.88    .065       0
 4207.08     .08       0 5192.58    .035       0 5437.64     .05       0
#XS Ineff= 2 ,-1
    4610    5072     496    2400    4200     496
Permanent Ineff=
       T       T
#Block Obstruct= 3 ,-1
    2340    5134     490    5769    5887     515       0    1374     582
Bank Sta=5192.58,5437.64
XS Rating Curve= 0 ,0
Exp/Cntr=0.3,0.1

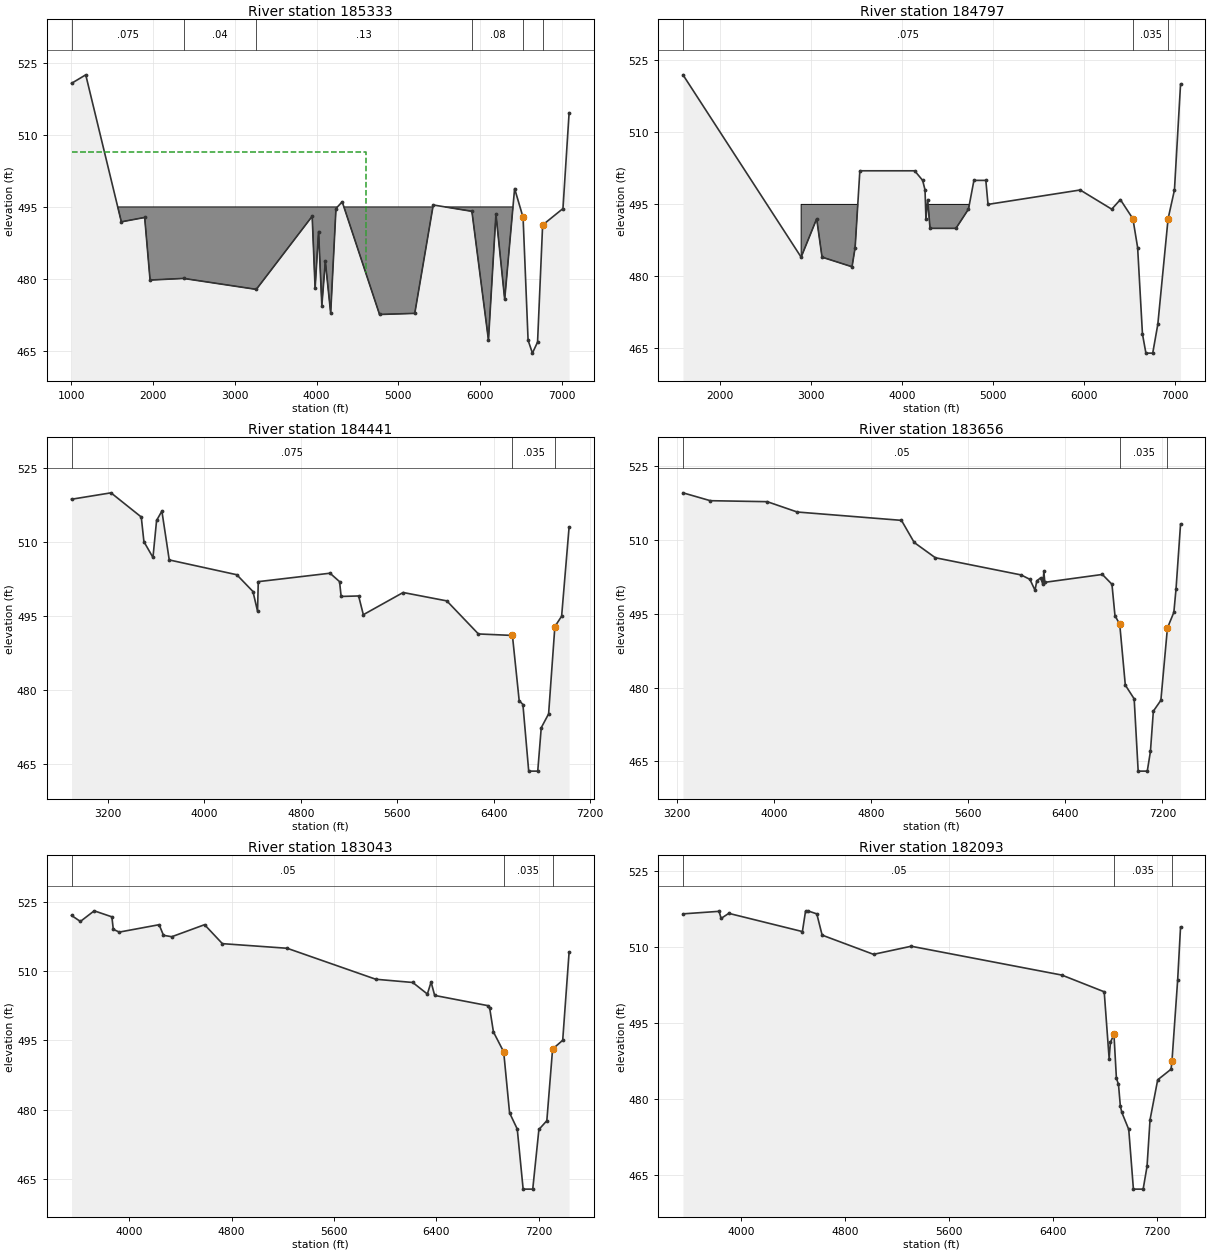
Type RM Length L Ch R = 1 ,185333  ,540,536,538
BEGIN DESCRIPTION:
This cross section corresponds to cross section 185387 of the non-georeferenced CDC model which was the source of this model.
END DESCRIPTION:
XS GIS Cut Line= 3
  2357821.113347 6974681.1771784 2357565.7954685 6969393.2217677
 2357883.3374445 6968669.2273831
#Sta/Elev= 30
    1004  520.71 1177.57  522.48 1612.87   491.9 1898.34  492.81 1964.31  479.79
 2373.91  480.13 3263.54  477.85 3946.72  493.06 3982.57  478.05 4024.87  489.88
 4064.86  474.49 4107.54  483.67 4172.94  472.89 4237.71  494.67 4313.92  496.07
 4770.52  472.63 5201.29  472.86 5427.11  495.41 5899.92  494.09 6102.38  467.32
 6193.95   493.5 6300.93  475.77 6422.26  498.82 6525.76  492.82 6587.08  467.27
 6640.06  464.59 6702.88  466.89 6764.86  491.24 7013.56  494.66 7088.69  514.58
#Mann= 6 ,-1,0
    1004    .075       0 2373.91     .04       0 3263.54     .13       0
 5899.92     .08       0 6525.76    .035       0 6764.86     .05       0
#XS Ineff= 2 , 0
       0    4604   506.5               0
Permanent Ineff=
       F       F
#Block Obstruct= 2 , 0
       0    6482     495               0
Bank Sta=6525.76,6764.86
XS Rating Curve= 0 ,0
Exp/Cntr=0.3,0.1

Type RM Length L Ch R = 1 ,184797  ,356,356,356
BEGIN DESCRIPTION:
This cross section corresponds to cross section 184850 of the non-georeferenced CDC model which was the source of this model.
END DESCRIPTION:
XS GIS Cut Line= 4
2358299.041962376974406.54958828  2358234.391604 6973108.1581484
 2358059.2944155  6969591.631768 2358328.8555562 6968996.7379447
#Sta/Elev= 30
    1591     522    2891     484    3062     492    3121     484    3451     482
    3485     486    3537     502    4140     502    4228     500    4254     498
    4264     492    4283     496    4309     490    4594     490    4732     494
    4792     500    4923     500    4947     495    5961     498    6308     494
    6403     496    6541     492    6593     486    6646     468    6684     464
    6759     464    6815     470    6928     492    6998     498    7065     520
#Mann= 3 ,0,0
    1591    .075       0    6541    .035       0    6928     .05       0
#Block Obstruct= 2 ,-1
                         2891.01    6180     495
Bank Sta=6541,6928
XS Rating Curve= 0 ,0
Exp/Cntr=0.3,0.1

Type RM Length L Ch R = 1 ,184441  ,784,784,784
BEGIN DESCRIPTION:
This cross section corresponds to cross section 184495 of the non-georeferenced CDC model which was the source of this model.
END DESCRIPTION:
XS GIS Cut Line= 3
  2358557.588317  6973201.966854   2358384.92795   6969734.37984
   2358654.48909   6969139.48602
#Sta/Elev= 30
    2900   518.7    3227     520    3478   515.1    3500   510.1    3575   506.9
    3605   514.4    3649   516.3    3710   506.4    4270   503.4    4404     500
    4442     496    4448     502    5043  503.71    5122     502    5135     499
    5280   499.1    5319   495.3    5649   499.8    6011   498.1    6273   491.4
    6555   491.1    6611   477.9    6642   477.1    6690   463.6    6765   463.6
    6794   472.4    6855   475.2    6907   492.9    6963     495    7025   513.1
#Mann= 3 ,0,0
    2900    .075       0    6555    .035       0    6907     .05       0
Bank Sta=6555,6907
XS Rating Curve= 0 ,0
Exp/Cntr=0.3,0.1

Type RM Length L Ch R = 1 ,183656  ,613,613,613
BEGIN DESCRIPTION:
This cross section corresponds to cross section 183709 of the non-georeferenced CDC model which was the source of this model.
--------------------------------------------
CDC FW050103-01 Riverbend West Trussway Site
Cross-section 183709 - 185387
--------------------------------------------
END DESCRIPTION:
XS GIS Cut Line= 3
  2359510.333965 6973466.7569936     2359085.044   6970092.03694
   2359371.13201   6969455.81216
#Sta/Elev= 30
    3250   519.6    3475     518    3944   517.8    4191   515.7    5050     514
    5155   509.5    5329   506.4    6036   502.9    6108     502    6150   499.8
    6165   501.7    6196   502.3    6215     501    6223   503.6    6231   501.4
    6705     503    6784     501    6809   494.6    6848   492.9    6894   480.5
    6967   477.7    7000     463    7075     463    7101     467    7125   475.2
    7187   477.4    7241   492.1    7294   495.3    7312   500.1    7349   513.2
#Mann= 3 ,0,0
    3250     .05       0    6848    .035       0    7241     .05       0
Bank Sta=6848,7241
XS Rating Curve= 0 ,0
Exp/Cntr=0.3,0.1

Type RM Length L Ch R = 1 ,183043  ,1050,950,900
BEGIN DESCRIPTION:
This cross section corresponds to cross section 183096 of the non-georeferenced CDC model which was the source of this model.
END DESCRIPTION:
XS GIS Cut Line= 3
  2360080.302205 6973499.7483181   2359649.32404   6970330.62602
   2359932.37499   6969703.87006
#Sta/Elev= 30
    3550     522    3619   520.7    3727     523    3865   521.7    3876     519
    3923   518.4    4234     520    4268   517.7    4333   517.4    4589     520
    4728   515.9    5234   514.9    5926   508.2    6215   507.5    6329     505
    6358   507.6    6386   504.7    6800   502.5    6816   501.9    6845   496.8
    6925   492.5    6971   479.3    7031   475.8    7077   462.8    7152   462.8
    7200   475.7    7262   477.6    7307   493.1    7386     495    7436   514.1
#Mann= 3 ,0,0
    3550     .05       0    6925    .035       0    7307     .05       0
Bank Sta=6925,7307
XS Rating Curve= 0 ,0
Exp/Cntr=0.3,0.1

Type RM Length L Ch R = 1 ,182093  ,610,625,625
BEGIN DESCRIPTION:
This cross section corresponds to cross section 182146 of the non-georeferenced CDC model which was the source of this model.
END DESCRIPTION:
XS GIS Cut Line= 3
   2360570.38532  6973481.139121   2360758.00785   6970189.29297
   2360664.02707   6969661.78812
#Sta/Elev= 30
    3550   516.6    3828   517.1    3844   515.7    3903   516.7    4470   513.1
    4494   517.1    4511   517.2    4581   516.6    4622   512.4    5018   508.6
    5308   510.2    6469   504.5    6795   501.2    6833     488    6843   491.2
    6870   492.8    6889   484.1    6905   482.9    6919   478.7    6930   477.4
    6984     474    7020   462.2    7095   462.2    7125   466.7    7148   475.9
    7207   483.8    7310   485.9    7317   487.5    7361   503.6    7383     514
#Mann= 3 ,0,0
    3550     .05       0    6870    .035       0    7317     .05       0
Bank Sta=6870,7317
XS Rating Curve= 0 ,0
Exp/Cntr=0.3,0.1

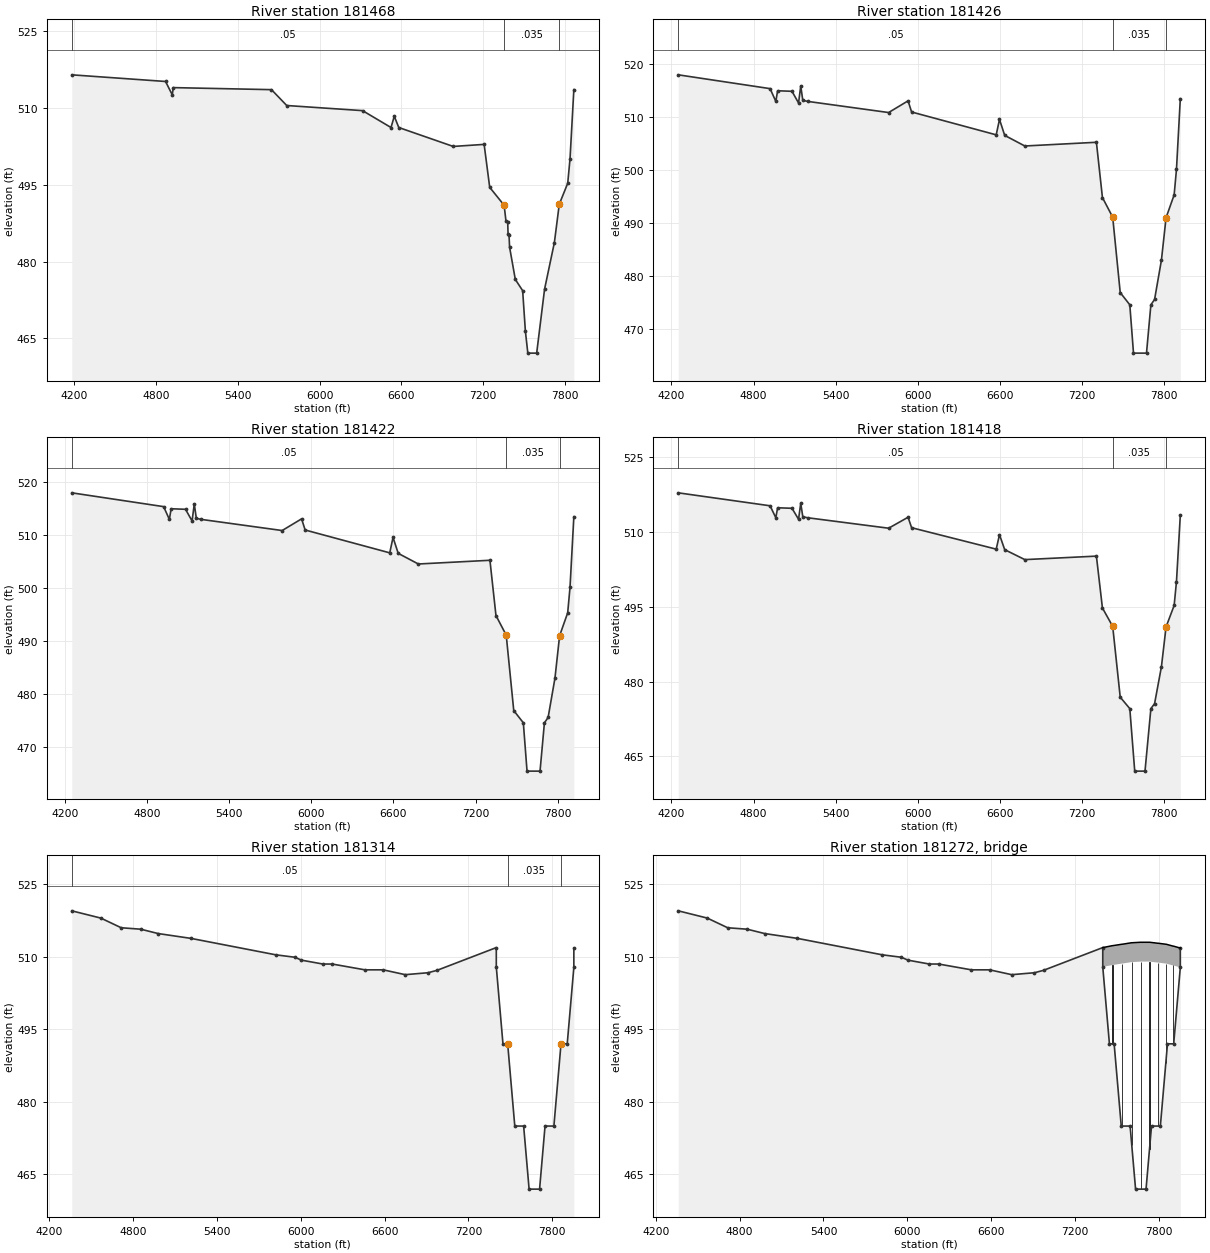
Type RM Length L Ch R = 1 ,181468  ,42,42,42
BEGIN DESCRIPTION:
This cross section corresponds to cross section 181521 of the non-georeferenced CDC model which was the source of this model.
END DESCRIPTION:
XS GIS Cut Line= 6
  2361210.029294 6973237.9957154  2361210.029294 6973237.9957154
   2361211.53516   6973077.56016   2361217.59715   6970543.71713
   2361350.82294   6969954.61497   2361281.10589   6969571.17315
#Sta/Elev= 30
    4180   516.5    4869   515.2    4918   512.6    4926     514    5647   513.6
    5759   510.5    6316   509.5    6525   506.2    6549   508.4    6582   506.2
    6982   502.5    7209   502.9    7250   494.5    7356     491    7369     488
    7382   487.8    7385   485.3    7392   485.1    7396   482.8    7438   476.5
    7492   474.3    7512   466.4    7530  462.09    7595  462.09    7653   474.6
    7725   483.7    7761   491.2    7823   495.3    7840   500.1    7868   513.6
#Mann= 3 ,0,0
    4180     .05       0    7356    .035       0    7761     .05       0
Bank Sta=7356,7761
XS Rating Curve= 0 ,0
Exp/Cntr=0.3,0.1

Type RM Length L Ch R = 1 ,181426  ,4,4,4
BEGIN DESCRIPTION:
This cross section corresponds to cross section 181479 of the non-georeferenced CDC model which was the source of this model.
END DESCRIPTION:
XS GIS Cut Line= 5
  2361302.493278 6973221.8763323 2361311.6129613 6972207.4595381
 2361309.9459713 6970552.1327981 2361393.7978313 6969955.0716581
 2361323.0847213 6969566.1537981
#Sta/Elev= 30
    4250   517.9    4921   515.3    4963   512.9    4976   514.9    5081   514.8
    5129   512.6    5145   515.8    5160   513.1    5195   512.9    5787   510.8
    5929     513    5955   510.9    6573   506.6    6597   509.5    6635   506.5
    6782   504.5    7305   505.2    7349   494.8    7424   491.1    7479   476.9
    7549   474.6    7576   465.5    7671   465.5    7703   474.6    7730   475.6
    7780     483    7814     491    7873   495.3    7890   500.1    7918   513.4
#Mann= 3 ,0,0
    4250     .05       0    7424    .035       0    7814     .05       0
Bank Sta=7424,7814
XS Rating Curve= 0 ,0
Exp/Cntr=0.3,0.1

Type RM Length L Ch R = 1 ,181422  ,4,4,4
BEGIN DESCRIPTION:
This cross section corresponds to cross section 181475 of the non-georeferenced CDC model which was the source of this model.
END DESCRIPTION:
XS GIS Cut Line= 5
  2361306.421067 6973221.1185436 2361315.5407504 6972206.7017494
 2361313.8737604 6970551.3750094 2361397.7256204 6969954.3138694
 2361327.0125104 6969565.3960094
#Sta/Elev= 30
    4250   517.9    4921   515.3    4963   512.9    4976   514.9    5081   514.8
    5129   512.6    5145   515.8    5160   513.1    5195   512.9    5787   510.8
    5929     513    5955   510.9    6573   506.6    6597   509.5    6635   506.5
    6782   504.5    7305   505.2    7349   494.8    7424   491.1    7479   476.9
    7549   474.6    7576   465.5    7671   465.5    7703   474.6    7730   475.6
    7780     483    7814     491    7873   495.3    7890   500.1    7918   513.4
#Mann= 3 ,0,0
    4250     .05       0    7424    .035       0    7814     .05       0
Bank Sta=7424,7814
XS Rating Curve= 0 ,0
Exp/Cntr=0.3,0.1

Type RM Length L Ch R = 1 ,181418  ,104,104,104
BEGIN DESCRIPTION:
This cross section corresponds to cross section 181471 of the non-georeferenced CDC model which was the source of this model.
END DESCRIPTION:
XS GIS Cut Line= 5
  2361310.152467 6973220.3986442   2361319.27215   6972205.98185
   2361317.60516   6970550.65511   2361401.45702   6969953.59397
   2361330.74391   6969564.67611
#Sta/Elev= 30
    4250   517.9    4921   515.3    4963   512.9    4976   514.9    5081   514.8
    5129   512.6    5145   515.8    5160   513.1    5195   512.9    5787   510.8
    5929     513    5955   510.9    6573   506.6    6597   509.5    6635   506.5
    6782   504.5    7305   505.2    7349   494.8    7424   491.1    7479   476.9
    7549   474.6    7585  462.06    7660  462.06    7703   474.6    7730   475.6
    7780     483    7814     491    7873   495.3    7890   500.1    7918   513.4
#Mann= 3 ,0,0
    4250     .05       0    7424    .035       0    7814     .05       0
Bank Sta=7424,7814
XS Rating Curve= 0 ,0
Exp/Cntr=0.3,0.1

Type RM Length L Ch R = 1 ,181314  ,82,82,82
BEGIN DESCRIPTION:
This cross section corresponds to cross section 181367 of the non-georeferenced CDC model which was the source of this model.
END DESCRIPTION:
XS GIS Cut Line= 5
  2361413.135029 6973127.9692752 2361421.6012506 6972186.2394851
 2361419.9342606 6970530.9127451 2361503.7861206 6969933.8516051
 2361433.0730106 6969544.9337451
#Sta/Elev= 30
    4360   519.5    4568     518    4714     516    4854   515.7    4979   514.8
    5214   513.8    5822   510.4    5958   509.9    6005   509.3    6158   508.5
    6225   508.5    6459   507.3    6590   507.3    6748   506.3    6911   506.7
    6976   507.2    7400   511.9    7400   507.9  7447.7     492 7481.43     492
 7532.43     475 7595.81     475 7634.93  461.96 7709.93  461.96 7749.05     475
 7812.43     475 7863.43     492 7907.91     492 7955.31   507.8 7955.31   511.8
#Mann= 3 ,0,0
    4360     .05       0 7481.43    .035       0 7863.43     .05       0
Bank Sta=7481.43,7863.43
XS Rating Curve= 0 ,0
Exp/Cntr=0.5,0.3

Type RM Length L Ch R = 3 ,181272  ,,,
BEGIN DESCRIPTION:
Handley-Ederville Road
END DESCRIPTION:
Node Name=Handley-Edervill
Bridge Culvert--1,0,-1,-1, 0
Deck Dist Width WeirC Skew NumUp NumDn MinLoCord MaxHiCord MaxSubmerge Is_Ogee
1,80,2.6,0, 18, 18, , , 0.95, 0, ,,,
    7400 7469.53 7472.03 7538.75 7541.25  7606.1  7608.6 7671.18 7673.68  7733.8
  7736.3 7793.67 7796.17 7850.51 7853.01 7903.99 7906.49 7955.31
   511.9   512.3   512.3   512.6   512.6   512.9   512.9     513     513     513
     513   512.8   512.8   512.6   512.6   512.2   512.2   511.8
   507.9   508.3   508.3   508.6   508.6   508.9   508.9     509     509     509
     509   508.8   508.8   508.6   508.6   508.2   508.2   507.8
    7400 7469.53 7472.03 7538.75 7541.25  7606.1  7608.6 7671.18 7673.68  7733.8
  7736.3 7793.67 7796.17 7850.51 7853.01 7903.99 7906.49 7955.31
   511.9   512.3   512.3   512.6   512.6   512.9   512.9     513     513     513
     513   512.8   512.8   512.6   512.6   512.2   512.2   511.8
   507.9   508.3   508.3   508.6   508.6   508.9   508.9     509     509     509
     509   508.8   508.8   508.6   508.6   508.2   508.2   507.8
Pier Skew, UpSta & Num, DnSta & Num=  ,7470.78, 2 ,7470.78, 2 , 0 , 0 , 0 ,,
     2.5     2.5
     450     510
     2.5     2.5
     450     510
Pier Skew, UpSta & Num, DnSta & Num=  ,7540, 2 ,7540, 2 , 0 , 0 , 0 ,,
     2.5     2.5
     450     510
     2.5     2.5
     450     510
Pier Skew, UpSta & Num, DnSta & Num=  ,7607.35, 2 ,7607.35, 2 , 0 , 0 , 0 ,,
     2.5     2.5
     450     510
     2.5     2.5
     450     510
Pier Skew, UpSta & Num, DnSta & Num=  ,7672.43, 2 ,7672.43, 2 , 0 , 0 , 0 ,,
     2.5     2.5
     450     510
     2.5     2.5
     450     510
Pier Skew, UpSta & Num, DnSta & Num=  ,7735.05, 2 ,7735.05, 2 , 0 , 0 , 0 ,,
     2.5     2.5
     450     510
     2.5     2.5
     450     510
Pier Skew, UpSta & Num, DnSta & Num=  ,7794.92, 2 ,7794.92, 2 , 0 , 0 , 0 ,,
     2.5     2.5
     450     510
     2.5     2.5
     450     510
Pier Skew, UpSta & Num, DnSta & Num=  ,7851.76, 2 ,7851.76, 2 , 0 , 0 , 0 ,,
     2.5     2.5
     450     510
     2.5     2.5
     450     510
Pier Skew, UpSta & Num, DnSta & Num=  ,7905.24, 2 ,7905.24, 2 , 0 , 0 , 0 ,,
     2.5     2.5
     450     510
     2.5     2.5
     450     510
BR Coef= 1 , 0 , 0 ,1.05, 0 ,,,0.8,-1,0.5,1,
WSPro=,,,, 1 ,,,, 0 ,,,, 0 ,,,,-1 ,-1 ,-1 , 0 , 0 , 0 , 0 , 0
BC Design=,, 0 ,, 0 ,,,,,,
BC HTab HWMax=519.5
BC Use User HTab Curves=0
BC User HTab FreeFlow(D)= 0