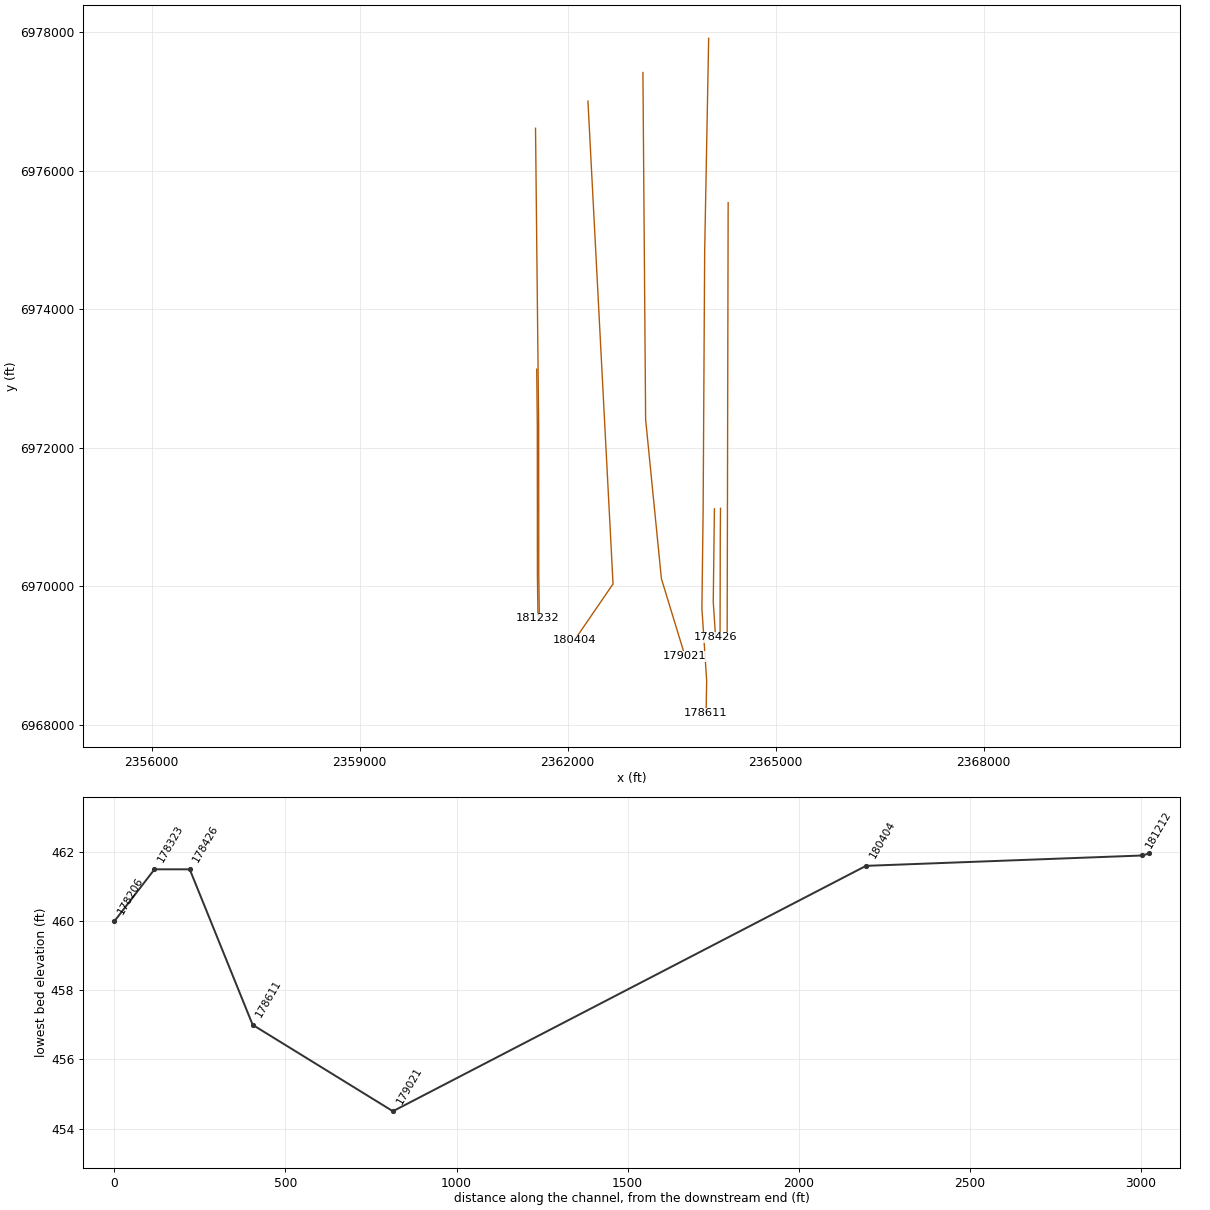
HEC-RAS study CDC_Consolidated_Model.prj: Upper Trinity CDC Consolidated Model

--- CDC_Consolidated_Model.g04 (geometry) --- (continued)

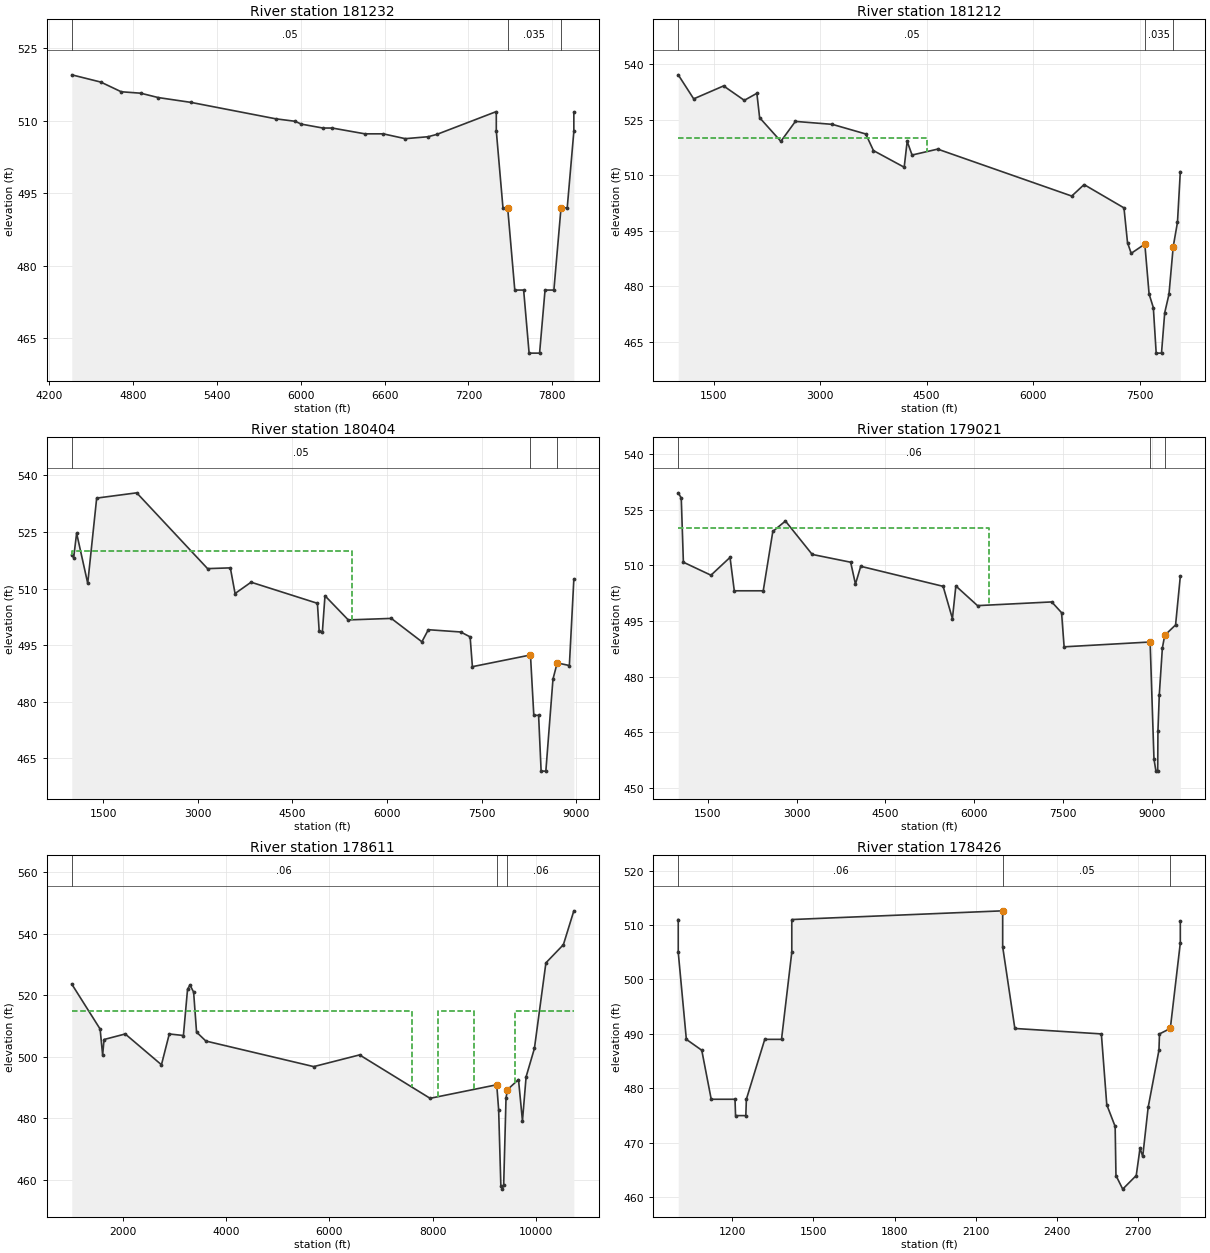
Type RM Length L Ch R = 1 ,181232  ,20,20,20
BEGIN DESCRIPTION:
This cross section corresponds to cross section 181285 of the non-georeferenced CDC model which was the source of this model.
END DESCRIPTION:
XS GIS Cut Line= 5
  2361552.884858 6973134.1526615 2361561.6402378 6972306.8421715
 2361562.8780978 6970179.9373115 2361564.3869478 6970066.7462615
 2361571.1129878 6969538.9422015
#Sta/Elev= 30
    4360   519.5    4568     518    4714     516    4854   515.7    4979   514.8
    5214   513.8    5822   510.4    5958   509.9    6005   509.3    6158   508.5
    6225   508.5    6459   507.3    6590   507.3    6748   506.3    6911   506.7
    6976   507.2    7400   511.9    7400   507.9  7447.7     492 7481.43     492
 7532.43     475 7595.81     475 7634.93  461.96 7709.93  461.96 7749.05     475
 7812.43     475 7863.43     492 7907.91     492 7955.31   507.8 7955.31   511.8
#Mann= 3 ,0,0
    4360     .05       0 7481.43    .035       0 7863.43     .05       0
Bank Sta=7481.43,7863.43
XS Rating Curve= 0 ,0
Exp/Cntr=0.3,0.1

Type RM Length L Ch R = 1 ,181212  ,928,808,728
BEGIN DESCRIPTION:
This cross section corresponds to cross section 181265 of the non-georeferenced CDC model which was the source of this model.
END DESCRIPTION:
XS GIS Cut Line= 6
  2361535.702464 6976609.8584375   2361535.70413   6976609.70107
   2361581.28114   6972303.05285     2361582.519   6970176.14799
   2361584.02785   6970062.95694   2361590.75389   6969535.15288
#Sta/Elev= 30
    1000   537.2    1218   530.7    1639   534.2    1931   530.3    2108   532.2
    2147   525.6    2446   519.2    2651   524.6    3171   523.8    3642   521.2
    3751   516.7    4184   512.2    4226   519.2    4295   515.5    4656   517.1
    6545   504.4    6719   507.5    7281   501.2    7331   491.8    7383   488.9
    7575   491.4    7635   477.9    7695   474.2    7735   461.9    7810   461.9
    7855   472.8    7915   477.8    7975   490.7    8035   497.3    8075     511
#Mann= 3 ,0,0
    1000     .05       0    7575    .035       0    7975     .05       0
#XS Ineff= 2 , 0
       0    4500     520               0
Permanent Ineff=
       F       F
Bank Sta=7575,7975
XS Rating Curve= 0 ,0
Exp/Cntr=0.3,0.1

Type RM Length L Ch R = 1 ,180404  ,852,1383,1553
BEGIN DESCRIPTION:
This cross section corresponds to cross section 180455 of the non-georeferenced CDC model which was the source of this model.
END DESCRIPTION:
XS GIS Cut Line= 3
   2362291.77906   6977002.08906   2362653.95485   6970036.21093
 2362095.2733342 6969221.6854017
#Sta/Elev= 30
    1000     519    1030   518.2    1077   524.7    1253   511.4    1395     534
    2030   535.4    3154   515.3    3515   515.5    3590   508.7    3844   511.7
    4896   506.1    4924   498.7    4975   498.6    5016   508.1    5385   501.7
    6068   502.1    6553   495.9    6655   499.1    7168   498.5    7318   497.2
    7354   489.3    8275   492.4    8328   476.4    8404   476.4    8444   461.6
    8519   461.6    8632     486    8699   490.3    8892   489.6    8963   512.5
#Mann= 3 ,0,0
    1000     .05       0    8275    .035       0    8699     .08       0
#XS Ineff= 2 , 0
       0    5450     520               0
Permanent Ineff=
       F       F
Bank Sta=8275,8699
XS Rating Curve= 0 ,0
Exp/Cntr=0.3,0.1

Type RM Length L Ch R = 1 ,179021  ,499,410,399
BEGIN DESCRIPTION:
This cross section corresponds to cross section 179075 of the non-georeferenced CDC model which was the source of this model.
END DESCRIPTION:
XS GIS Cut Line= 4
   2363085.04585     6977414.061   2363124.02904   6972410.30002
   2363351.58403   6970112.34989 2363692.7487769 6968994.3479177
#Sta/Elev= 30
    1000   529.5    1051   528.1    1087   510.8    1553   507.3    1875   512.1
    1947   503.1    2436   503.1    2598   519.1    2811   521.9    3263   512.9
    3913   510.8    3994   504.9    4083   509.7    5475   504.3    5632   495.6
    5690   504.4    6056   499.1    7310   500.1    7476   497.2    7519     488
    8972   489.3    9037   457.8    9070   454.5    9100   454.5    9104   465.3
    9127   475.1    9179   487.7    9219   491.1    9402   493.9    9482     507
#Mann= 3 ,0,0
    1000     .06       0    8972     .05       0    9219     .08       0
#XS Ineff= 2 , 0
       0    6250     520               0
Permanent Ineff=
       F       F
Bank Sta=8972,9219
XS Rating Curve= 0 ,0
Exp/Cntr=0.3,0.1

Type RM Length L Ch R = 1 ,178611  ,184,184,184
BEGIN DESCRIPTION:
This cross section corresponds to cross section 178664 of the non-georeferenced CDC model which was the source of this model.
END DESCRIPTION:
XS GIS Cut Line= 6
   2364033.43601   6977907.19585   2363975.63396    6974825.7299
   2363953.58414   6971103.01195   2363935.88207   6969681.06794
   2364004.40195   6968639.90204   2363996.04402    6968169.2081
#Sta/Elev= 30
    1000   523.6    1550     509    1599   500.5    1626   505.6    2037   507.4
    2740   497.4    2892   507.4    3166   506.9    3246   521.9    3293   523.3
    3364     521    3421     508    3602   505.1    5694   496.8    6584   500.6
    7952   486.5    9245   490.9    9282   482.8    9325     458    9355     457
    9380   458.5    9425   486.5    9452   489.3    9667   492.6    9744   479.2
    9815   493.5    9976   502.7   10199   530.5   10538   536.4   10741   547.4
#Mann= 3 ,0,0
    1000     .06       0    9245     .05       0    9452     .06       0
#XS Ineff= 3 ,-1
    1000    7600     515    8100    8800     515    9600   10741     515
Permanent Ineff=
       F       F       F
Bank Sta=9245,9452
XS Rating Curve= 0 ,0
Exp/Cntr=0.3,0.1

Type RM Length L Ch R = 1 ,178426  ,103,103,103
BEGIN DESCRIPTION:
This cross section corresponds to cross section 178479 of the non-georeferenced CDC model which was the source of this model.
END DESCRIPTION:
XS GIS Cut Line= 3
  2364116.307598 6971119.6475117     2364099.592     6969776.937
 2364133.3579617 6969263.8614388
#Sta/Elev= 30
    1000     511    1000     505    1030     489    1087     487    1122     478
    1210     478    1212     475    1250     475    1252     478    1320     489
    1382     489    1420     505    1420     511    2200   512.6    2200     506
    2245     491    2565     490    2585     477    2616     473    2619     464
    2644   461.5    2694     464    2708     469    2718   467.5    2738   476.5
    2778     487    2780     490    2820     491    2857   506.7    2857   510.7
#Mann= 3 ,0,0
    1000     .06       0    2200     .05       0    2820     .06       0
Bank Sta=2200,2820
XS Rating Curve= 0 ,0
Exp/Cntr=0.5,0.3

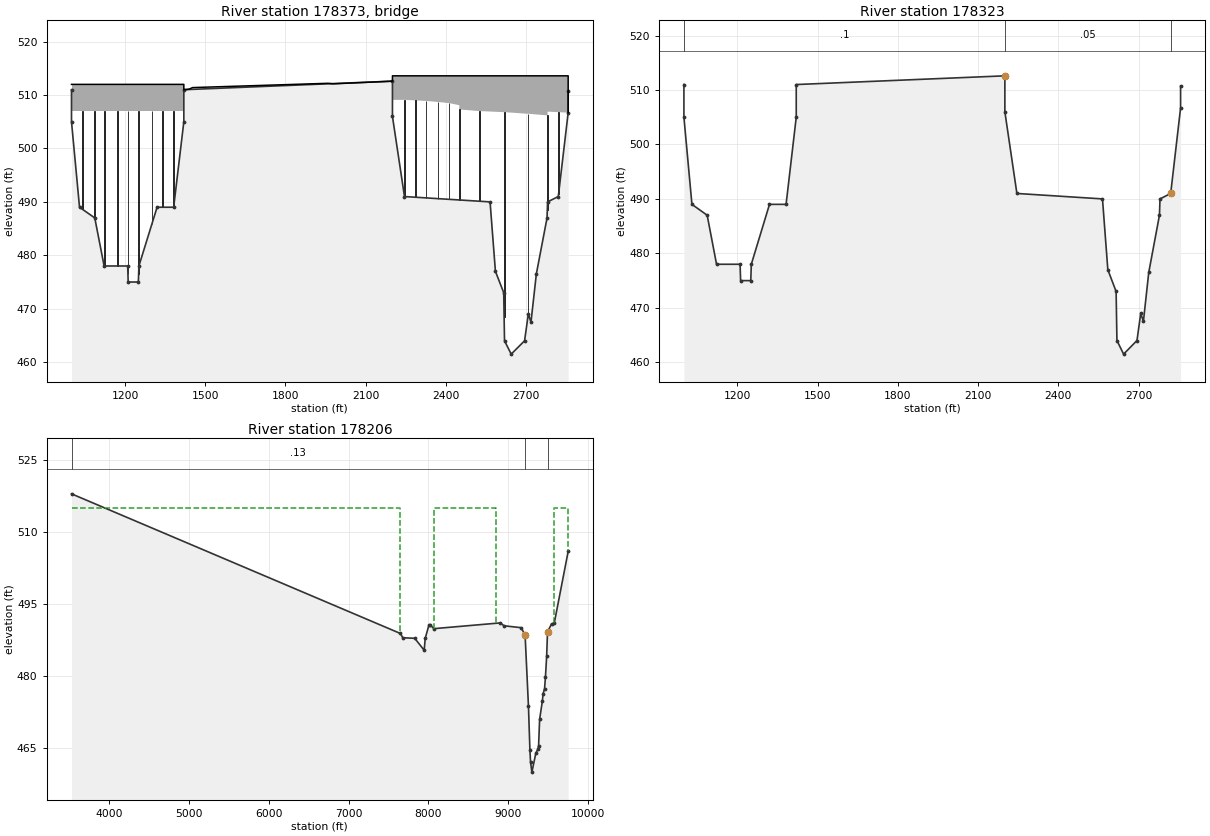
Type RM Length L Ch R = 3 ,178373  ,,,
BEGIN DESCRIPTION:
I.H. 820
END DESCRIPTION:
Node Name=IH 820
Bridge Culvert--1,0,-1,-1, 0
Deck Dist Width WeirC Skew NumUp NumDn MinLoCord MaxHiCord MaxSubmerge Is_Ogee
1,100,2.6,0, 36, 36, , , 0.95, 0, ,,,
    1000    1420    1420    1439    1453    1959    1978    2200    2200    2245
    2247    2285    2287    2325    2327    2370    2372    2410    2412    2450
    2450    2452    2525    2528    2616    2619    2705    2708    2778    2780
    2780    2820    2820    2822    2857    2857
     512     512     511   511.1   511.4   512.2   512.1   512.6   513.6   513.6
   513.6   513.6   513.6   513.6   513.6   513.6   513.6   513.6   513.6   513.6
   513.6   513.6   513.6   513.6   513.6   513.6   513.6   513.6   513.6   513.6
   513.6   513.6   513.6   513.6   513.6   506.7
     507     507     511   511.1   511.4   512.2   512.1   512.6   509.1   509.1
   509.1     509     509   508.9   508.9   508.7   508.7   508.5   508.5   508.1
   507.3   507.3     507     507   506.8   506.8   506.5   506.5   506.2   506.2
   506.9   506.8   506.8   506.8   506.7   506.7
    1000    1420    1420    1439    1453    1959    1978    2200    2200    2245
    2247    2285    2287    2325    2327    2370    2372    2410    2412    2450
    2450    2452    2525    2528    2616    2619    2705    2708    2778    2780
    2780    2820    2820    2822    2857    2857
     512     512     511   511.1   511.4   512.2   512.1   512.6   513.6   513.6
   513.6   513.6   513.6   513.6   513.6   513.6   513.6   513.6   513.6   513.6
   513.6   513.6   513.6   513.6   513.6   513.6   513.6   513.6   513.6   513.6
   513.6   513.6   513.6   513.6   513.6   506.7
     507     507     511   511.1   511.4   512.2   512.1   512.6   509.1   509.1
   509.1     509     509   508.9   508.9   508.7   508.7   508.5   508.5   508.1
   507.3   507.3     507     507   506.8   506.8   506.5   506.5   506.2   506.2
   506.9   506.8   506.8   506.8   506.7   506.7
Pier Skew, UpSta & Num, DnSta & Num=  ,1041, 2 ,1041, 2 , 0 , 0 , 0 ,,
       2       2
     475     510
       2       2
     475     510
Pier Skew, UpSta & Num, DnSta & Num=  ,1086, 2 ,1086, 2 , 0 , 0 , 0 ,,
       2       2
     475     510
       2       2
     475     510
Pier Skew, UpSta & Num, DnSta & Num=  ,1123, 2 ,1123, 2 , 0 , 0 , 0 ,,
       2       2
     475     510
       2       2
     475     510
Pier Skew, UpSta & Num, DnSta & Num=  ,1171, 2 ,1171, 2 , 0 , 0 , 0 ,,
       2       2
     475     510
       2       2
     475     510
Pier Skew, UpSta & Num, DnSta & Num=  ,1211, 2 ,1211, 2 , 0 , 0 , 0 ,,
       2       2
     475     510
       2       2
     475     510
Pier Skew, UpSta & Num, DnSta & Num=  ,1251, 2 ,1251, 2 , 0 , 0 , 0 ,,
       2       2
     475     510
       2       2
     475     510
Pier Skew, UpSta & Num, DnSta & Num=  ,1301, 2 ,1301, 2 , 0 , 0 , 0 ,,
       2       2
     475     510
       2       2
     475     510
Pier Skew, UpSta & Num, DnSta & Num=  ,1341, 2 ,1341, 2 , 0 , 0 , 0 ,,
       2       2
     475     510
       2       2
     475     510
Pier Skew, UpSta & Num, DnSta & Num=  ,1381, 2 ,1381, 2 , 0 , 0 , 0 ,,
       2       2
     475     510
       2       2
     475     510
Pier Skew, UpSta & Num, DnSta & Num=  ,2246, 2 ,2246, 2 , 0 , 0 , 0 ,,
       2       2
     465     510
       2       2
     465     510
Pier Skew, UpSta & Num, DnSta & Num=  ,2286, 2 ,2286, 2 , 0 , 0 , 0 ,,
       2       2
     465     510
       2       2
     465     510
Pier Skew, UpSta & Num, DnSta & Num=  ,2326, 2 ,2326, 2 , 0 , 0 , 0 ,,
       2       2
     465     510
       2       2
     465     510
Pier Skew, UpSta & Num, DnSta & Num=  ,2371, 2 ,2371, 2 , 0 , 0 , 0 ,,
       2       2
     465     510
       2       2
     465     510
Pier Skew, UpSta & Num, DnSta & Num=  ,2411, 2 ,2411, 2 , 0 , 0 , 0 ,,
       2       2
     465     510
       2       2
     465     510
Pier Skew, UpSta & Num, DnSta & Num=  ,2451, 2 ,2451, 2 , 0 , 0 , 0 ,,
       2       2
     465     510
       2       2
     465     510
Pier Skew, UpSta & Num, DnSta & Num=  ,2526.5, 2 ,2526.5, 2 , 0 , 0 , 0 ,,
       3       3
     465     510
       3       3
     465     510
Pier Skew, UpSta & Num, DnSta & Num=  ,2617.5, 2 ,2617.5, 2 , 0 , 0 , 0 ,,
       3       3
     465     510
       3       3
     465     510
Pier Skew, UpSta & Num, DnSta & Num=  ,2706.5, 2 ,2706.5, 2 , 0 , 0 , 0 ,,
       3       3
     465     510
       3       3
     465     510
Pier Skew, UpSta & Num, DnSta & Num=  ,2779, 2 ,2779, 2 , 0 , 0 , 0 ,,
       2       2
     465     510
       2       2
     465     510
Pier Skew, UpSta & Num, DnSta & Num=  ,2821, 2 ,2821, 2 , 0 , 0 , 0 ,,
       2       2
     465     510
       2       2
     465     510
BR Coef= 1 , 0 , 0 ,1.05, 0 ,,,0.8,-1,0.5,1,
WSPro=,,,, 1 ,,,, 0 ,,,, 0 ,,,,-1 ,-1 ,-1 , 0 , 0 , 0 , 0 , 0
BC Design=,, 0 ,, 0 ,,,,,,
BC HTab HWMax=512.6
BC Use User HTab Curves=0
BC User HTab FreeFlow(D)= 0

Type RM Length L Ch R = 1 ,178323  ,117,117,117
BEGIN DESCRIPTION:
This cross section corresponds to cross section 178377 of the non-georeferenced CDC model which was the source of this model.
END DESCRIPTION:
XS GIS Cut Line= 3
  2364204.325923 6971127.7267668      2364201.01     6970750.951
 2364197.5843205  6969270.745322
#Sta/Elev= 30
    1000     511    1000     505    1030     489    1087     487    1122     478
    1210     478    1212     475    1250     475    1252     478    1320     489
    1382     489    1420     505    1420     511    2200   512.6    2200     506
    2245     491    2565     490    2585     477    2616     473    2619     464
    2644   461.5    2694     464    2708     469    2718   467.5    2738   476.5
    2778     487    2780     490    2820     491    2857   506.7    2857   510.7
#Mann= 3 ,0,0
    1000      .1       0    2200     .05       0    2820     .08       0
Bank Sta=2200,2820
XS Rating Curve= 0 ,0
Exp/Cntr=0.3,0.1

Type RM Length L Ch R = 1 ,178206  ,748,776,848
BEGIN DESCRIPTION:
This cross section corresponds to cross section 178263 of the non-georeferenced CDC model which was the source of this model.
END DESCRIPTION:
XS GIS Cut Line= 6
     2364314.499     6975536.584       2364313.4     6975061.585
     2364311.085     6974061.588     2364304.952     6971411.595
     2364302.291     6970261.598      2364300.08     6969306.601
#Sta/Elev= 30
    3525     518    7650   488.9    7681     488    7830   487.9    7949   485.4
    7962   487.9    8008   490.6    8024   490.7    8070   489.9    8904   491.1
    8950   490.5    9167   490.1    9215   488.5    9257   473.7    9275   464.7
    9283   462.1    9300     460    9350     464    9376   464.8    9384   465.5
    9397     471    9432   474.9    9440   476.3    9459   477.4    9470   479.8
    9485   484.1    9496   489.2    9546   490.9    9580     491    9755     506
#Mann= 3 ,0,0
    3525     .13       0    9215     .05       0    9496     .08       0
#XS Ineff= 3 ,-1
    8070    8850     515    9580    9755     515    3525    7650     515
Permanent Ineff=
       F       F       F
Bank Sta=9215,9496
XS Rating Curve= 0 ,0
Exp/Cntr=0.3,0.1