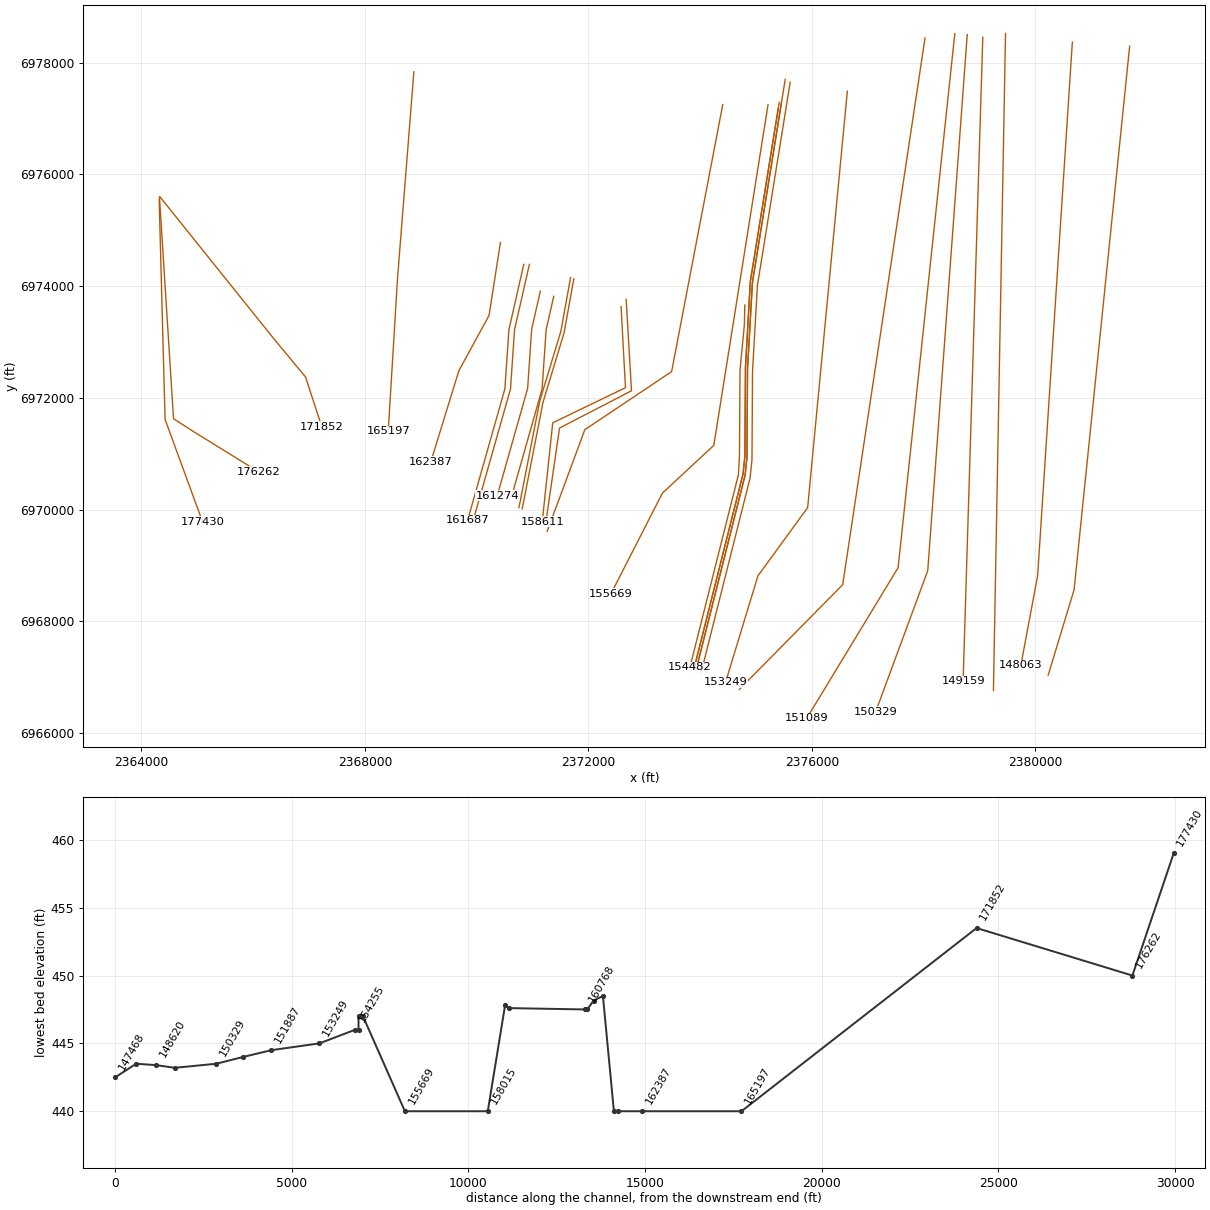
HEC-RAS study CDC_Consolidated_Model.prj: Upper Trinity CDC Consolidated Model

--- CDC_Consolidated_Model.g04 (geometry) --- (continued)

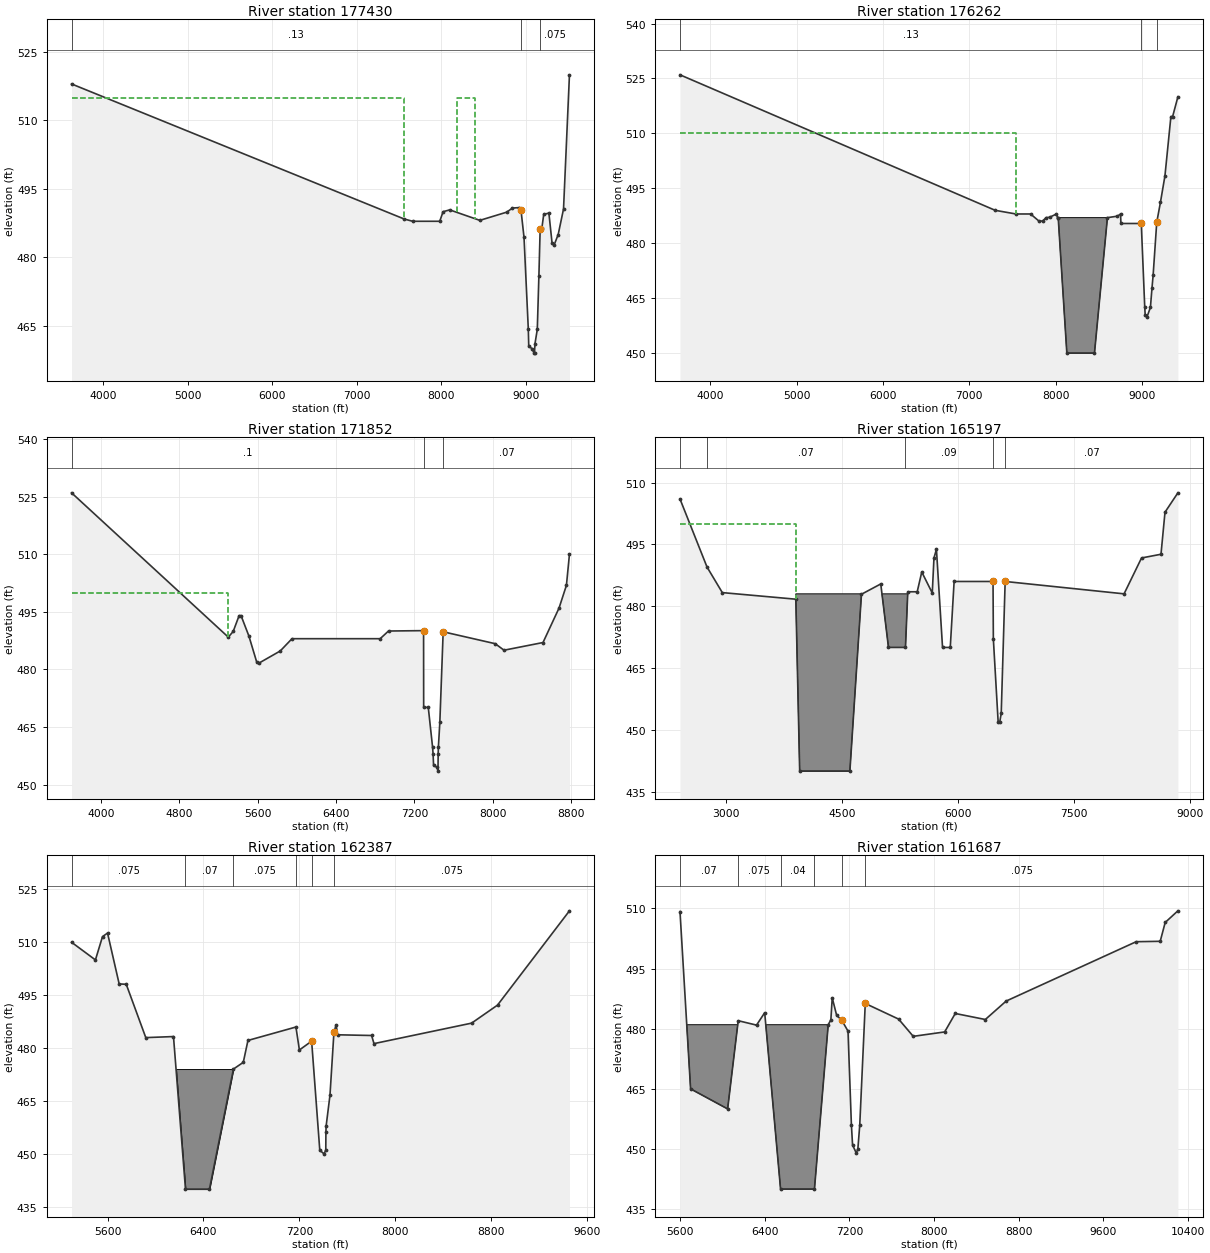
Type RM Length L Ch R = 1 ,177430  ,698,1168,1246
BEGIN DESCRIPTION:
This cross section corresponds to cross section 177485 of the non-georeferenced CDC model which was the source of this model.
END DESCRIPTION:
XS GIS Cut Line= 4
     2364318.534     6975544.511     2364424.556     6971615.942
     2364615.612     6971093.029     2365095.148      6969781.68
#Sta/Elev= 30
    3630     518    7560   488.4    7660   487.9    7980   487.9    8020     490
    8098   490.4    8454   488.1    8772   489.9    8839   490.8    8922   490.9
    8931   490.2    8940   490.4    8976   484.4    9027   464.2    9032   460.5
    9070     460    9095     459    9100     459    9105     461    9133   464.2
    9152     476    9167   486.3    9187   486.4    9209   489.4    9270   489.7
    9307   483.2    9334   482.8    9380     485    9443   490.6    9513     520
#Mann= 3 ,0,0
    3630     .13       0    8940     .05       0    9167    .075       0
#XS Ineff= 2 ,-1
    8180    8400     515    3630    7560     515
Permanent Ineff=
       F       F
#Block Obstruct= 2 , 0
       0                    9270       0   489.7
Bank Sta=8940,9167
XS Rating Curve= 0 ,0
Exp/Cntr=0.3,0.1

Type RM Length L Ch R = 1 ,176262  ,2498,4410,1799
BEGIN DESCRIPTION:
This cross section corresponds to cross section 176313 of the non-georeferenced CDC model which was the source of this model.
END DESCRIPTION:
XS GIS Cut Line= 5
     2364323.523      6975598.92      2364324.42      6975584.78
      2364575.42      6971628.24     2364925.289     6971402.707
     2366091.574     6970682.309
#Sta/Elev= 30
 3650.24     526    7300     489    7540     488    7710     488    7810     486
    7850   486.1    7890     487    7930   487.1    8010     488    8023   486.9
    8030     487    8130     450    8450     450    8600     487    8716   487.4
    8752     488    8756   485.4    8992   485.4    9032   462.6    9037   460.5
    9060     460    9098   462.5    9116   467.8    9129   471.2    9171   485.7
    9214   491.2    9266   498.4    9335   514.6    9355   514.6    9416     520
#Mann= 3 ,0,0
 3650.24     .13       0    8992    .065       0    9171    .075       0
#XS Ineff= 2 , 0
       0    7540     510               0
Permanent Ineff=
       F       F
#Block Obstruct= 2 ,-1
                            8010    8600     487
Bank Sta=8992,9171
XS Rating Curve= 0 ,0
Exp/Cntr=0.3,0.1

Type RM Length L Ch R = 1 ,171852  ,3799,6655,1500
BEGIN DESCRIPTION:
This cross section corresponds to cross section 171900 of the non-georeferenced CDC model which was the source of this model.
END DESCRIPTION:
XS GIS Cut Line= 6
      2364335.62     6975595.769     2365304.911     6974387.828
      2366385.73     6973040.899     2366385.835     6973040.772
     2366938.192     6972375.978     2367230.553     6971480.706
#Sta/Elev= 30
    3700     526    5300   488.4    5350   489.9    5410     494    5430     494
    5510   488.7    5590   481.9    5610   481.6    5830   484.8    5950     488
    6850     488    6935     490    7293   490.1    7294   470.1    7341   470.1
    7385   459.7    7390     458    7395     455    7430   454.5    7440   453.5
    7442     458    7444   459.7    7459   466.2    7493   489.8    8024   486.7
    8114     485    8512     487    8676     496    8751   501.9    8782     510
#Mann= 3 ,0,0
    3700      .1       0    7293    .065       0    7493     .07       0
#XS Ineff= 2 , 0
       0    5300     500               0
Permanent Ineff=
       F       F
Bank Sta=7293,7493
XS Rating Curve= 0 ,0
Exp/Cntr=0.3,0.1

Type RM Length L Ch R = 1 ,165197  ,2402,2810,1151
BEGIN DESCRIPTION:
This cross section corresponds to cross section 165243 of the non-georeferenced CDC model which was the source of this model.
END DESCRIPTION:
XS GIS Cut Line= 5
 2368877.65286136977838.04796955  2368850.022491 6977489.1402989
  2368841.654436 6977383.4711187   2368586.11687   6974156.62297
 2368418.6193932  6971406.669799
#Sta/Elev= 30
    2400     506    2750   489.5    2948   483.3    3900   481.7    3950     440
    4600     440    4750   482.9    5000   485.4    5100     470    5320     470
    5350   483.5    5472   483.5    5531   488.3    5667   483.2    5689   491.7
    5721   493.8    5800     470    5900     470    5950     486    6454     486
    6458   472.1    6520     452    6540   451.8    6560     454    6611     486
    8151     483    8377   491.7    8629   492.6    8681   502.8    8848   507.5
#Mann= 5 ,-1,0
    2400     .07       0    2750     .07       0    5320     .09       0
    6454    .055       0    6611     .07       0
#XS Ineff= 2 , 0
       0    3900     500               0
Permanent Ineff=
       F       F
#Block Obstruct= 2 ,-1
                         3900.01    5350     483
Bank Sta=6454,6611
XS Rating Curve= 0 ,0
Exp/Cntr=0.3,0.1

Type RM Length L Ch R = 1 ,162387  ,409,699,898
BEGIN DESCRIPTION:
This cross section corresponds to cross section 162435 of the non-georeferenced CDC model which was the source of this model.
END DESCRIPTION:
XS GIS Cut Line= 5
  2370426.727748 6974782.1451209  2370394.404979 6974574.6475581
   2370223.44003    6973477.1299   2369682.57891   6972486.03904
  2369181.567299  6970859.262461
#Sta/Elev= 30
    5300   509.9    5499   504.9    5558   511.5    5600   512.5    5697   498.1
    5756     498    5919   482.9    6150   483.2    6250     440    6450     440
    6650     474    6732   475.9    6771   482.1    7171   485.9    7200   479.4
    7302   481.9    7370     451    7405     450    7420     451    7421   456.2
    7423   457.9    7455   466.6    7488   484.4    7506   486.5    7519   483.7
    7802   483.5    7822   481.2    8636     487    8852   492.1    9452   518.8
#Mann= 6 ,-1,0
    5300    .075       0    6250     .07       0    6650    .075       0
    7171     .12       0    7302    .055       0    7488    .075       0
#Block Obstruct= 2 , 0
       0    6650     474               0
Bank Sta=7302,7488
XS Rating Curve= 0 ,0
Exp/Cntr=0.3,0.1

Type RM Length L Ch R = 1 ,161687  ,102,102,102
BEGIN DESCRIPTION:
This cross section corresponds to cross section 161734 of the non-georeferenced CDC model which was the source of this model.
Copied geometry from XS 161634
END DESCRIPTION:
XS GIS Cut Line= 4
  2370844.741162 6974390.6193323 2370578.9524015 6973223.3172414
 2370506.4023515 6972160.9483014 2369840.2425915 6969812.6291814
#Sta/Elev= 30
    5600   509.2    5700     465    6050     460    6150     482    6323   480.9
    6400     484    6550     440    6870     440    7000     481    7025   482.2
    7038   487.7    7080   483.3    7126   482.2    7187   479.4    7219     456
    7230     451    7265     449    7280     450    7298     456    7350   486.3
    7665   482.4    7803   478.1    8100   479.2    8200   483.8    8484   482.3
    8681   486.9    9909   501.7   10136   501.8   10183   506.5   10303   509.4
#Mann= 6 ,-1,0
    5600     .07       0    6150    .075       0    6550     .04       0
    6870     .12       0    7126    .055       0    7350    .075       0
#Block Obstruct= 2 , 0
       0    7000     481               0
Bank Sta=7126,7350
XS Rating Curve= 0 ,0
Exp/Cntr=0.3,0.1

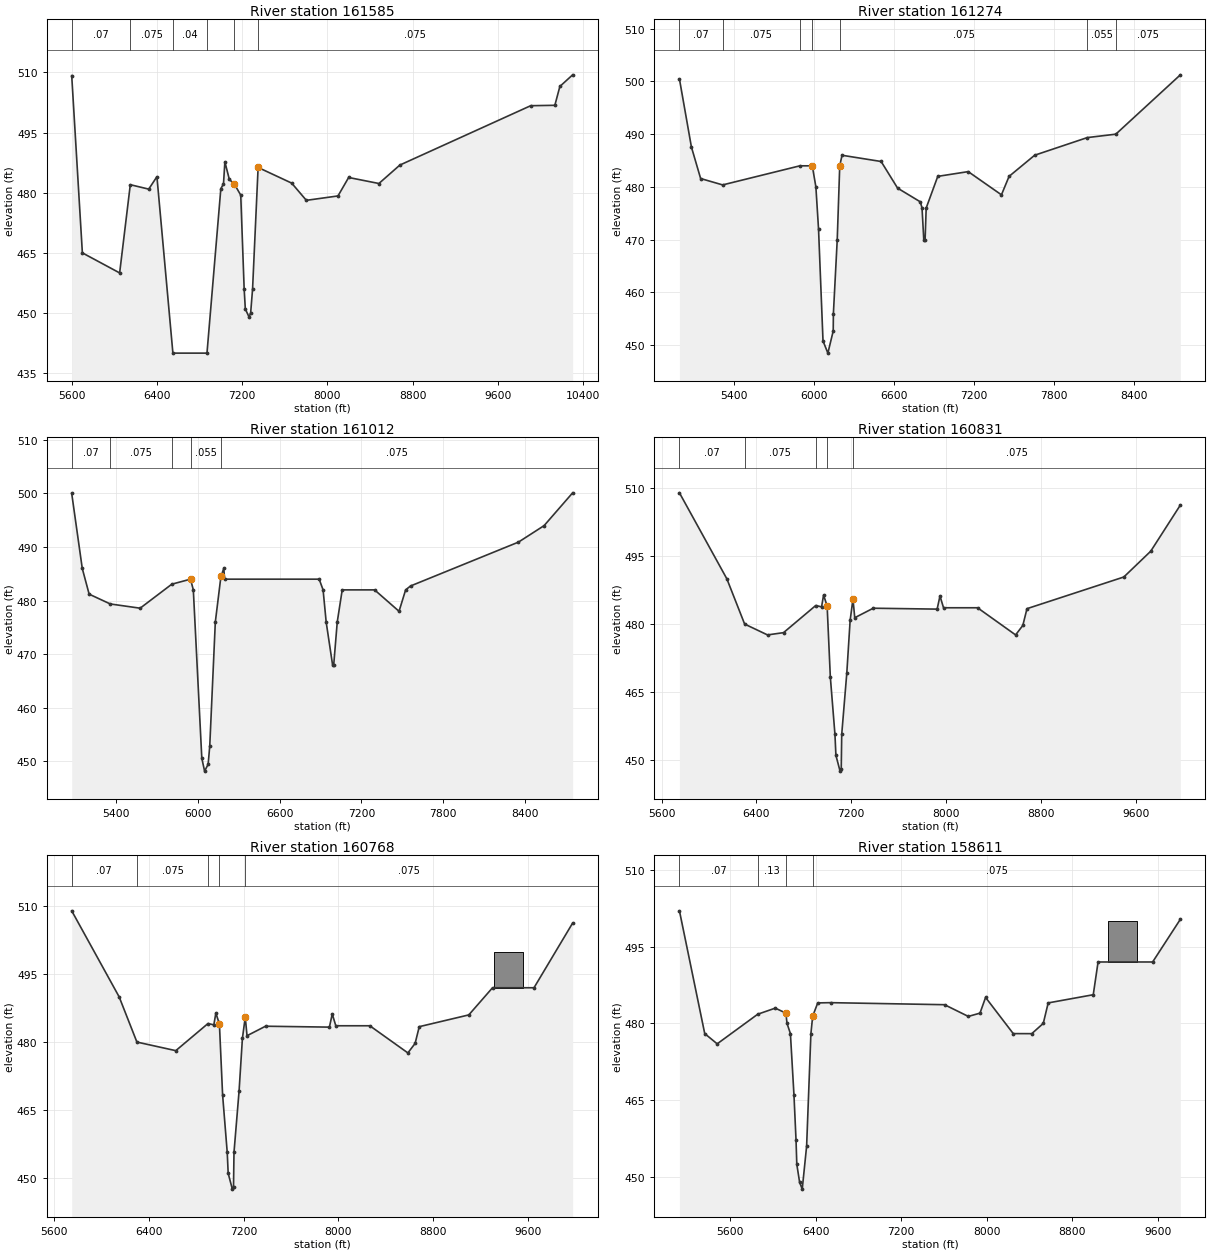
Type RM Length L Ch R = 1 ,161585  ,294,311,209
BEGIN DESCRIPTION:
This cross section corresponds to cross section 161634 of the non-georeferenced CDC model which was the source of this model.
END DESCRIPTION:
XS GIS Cut Line= 4
  2370945.508721 6974390.7510709   2370679.71996   6973223.44898
   2370607.16991   6972161.08004   2369941.01015   6969812.76092
#Sta/Elev= 30
    5600   509.2    5700     465    6050     460    6150     482    6323   480.9
    6400     484    6550     440    6870     440    7000     481    7025   482.2
    7038   487.7    7080   483.3    7126   482.2    7187   479.4    7219     456
    7230     451    7265     449    7280     450    7298     456    7350   486.3
    7665   482.4    7803   478.1    8100   479.2    8200   483.8    8484   482.3
    8681   486.9    9909   501.7   10136   501.8   10183   506.5   10303   509.4
#Mann= 6 ,-1,0
    5600     .07       0    6150    .075       0    6550     .04       0
    6870     .12       0    7126    .055       0    7350    .075       0
#Block Obstruct= 2 , 0
            7000     481
Bank Sta=7126,7350
XS Rating Curve= 0 ,0
Exp/Cntr=0.3,0.1

Type RM Length L Ch R = 1 ,161274  ,294,263,204
BEGIN DESCRIPTION:
This cross section corresponds to cross section 161322 of the non-georeferenced CDC model which was the source of this model.
XS Added - GeoRas
END DESCRIPTION:
XS GIS Cut Line= 5
  2371141.137944 6973911.8172809  2371041.232307  6973473.047565
 2370986.2134367 6973231.4134114 2370913.6633867 6972169.0444714
  2370370.311757 6970253.6435459
#Sta/Elev= 30
 4994.13  500.46 5083.83  487.57 5152.95  481.59 5317.95  480.38 5896.74     484
 5989.66     484 6016.54     480 6036.48     472 6069.98   450.8 6106.45  448.49
 6146.49  452.69 6147.77     456 6176.58     470 6195.34     484 6212.49     486
 6505.46  484.82 6628.92  479.77 6799.09  477.17 6811.98     476 6825.03     470
 6834.98     470 6843.11     476 6929.92     482 7157.98   482.9 7407.05   478.5
 7464.19     482 7656.11  486.01    8050  489.35    8264     490 8747.77  501.25
#Mann= 7 ,-1,0
 4994.13     .07       0 5317.95    .075       0 5896.74     .13       0
 5989.66    .055       0 6195.34    .075       0    8050    .055       0
    8264    .075       0
#XS Ineff= 2 , 0
       0 5989.66     484 6195.34       0     484
Permanent Ineff=
       F       F
Bank Sta=5989.66,6195.34
XS Rating Curve= 0 ,0
Exp/Cntr=0.3,0.1

Type RM Length L Ch R = 1 ,161012  ,210,180,216
BEGIN DESCRIPTION:
This cross section corresponds to cross section 161058 of the non-georeferenced CDC model which was the source of this model.
XS Added - GeoRas
END DESCRIPTION:
XS GIS Cut Line= 5
  2371381.326327 6973819.5147058 2371281.4206906 6973380.7449899
 2371245.0484877 6973221.0040425 2371172.4984377 6972158.6351025
  2370629.146808  6970243.234177
#Sta/Elev= 30
 5077.54     500 5154.87     486 5205.27   481.2 5360.23  479.37 5578.87  478.58
 5810.58  483.06  5947.8     484 5968.42     482 6030.53  450.58 6050.93  448.16
 6076.94  449.43 6088.79  452.85 6129.57     476 6170.58   484.5 6191.54     486
 6197.76     484 6890.25     484 6919.07     482 6941.59     476 6988.54     468
 6996.87     468 7022.73     476 7059.18     482 7296.28     482 7475.44     478
 7523.71     482 7559.85  482.73 8350.35  490.92 8538.28     494 8747.19  500.12
#Mann= 5 ,-1,0
 5077.54     .07       0 5360.23    .075       0 5810.58     .13       0
  5947.8    .055       0 6170.58    .075       0
Bank Sta=5947.8,6170.58
XS Rating Curve= 0 ,0
Exp/Cntr=0.3,0.1

Type RM Length L Ch R = 1 ,160831  ,63,63,69
BEGIN DESCRIPTION:
This cross section corresponds to cross section 160878 of the non-georeferenced CDC model which was the source of this model.
END DESCRIPTION:
XS GIS Cut Line= 5
  2371682.359361 6974154.7699653 2371638.0012066 6973908.7367275
   2371508.76916   6973191.94904    2371131.2499   6971946.14904
 2370758.0835277 6970036.3538995
#Sta/Elev= 30
    5750     509    6150     490    6300     480    6493   477.6    6628   478.1
    6900   484.1    6949   483.8    6966   486.4    6996     484    7023   468.3
    7062   455.6    7070     451    7105   447.5    7115     448    7119   455.6
    7162   469.2    7190   480.8    7214   485.5    7229   481.4    7385   483.5
    7924   483.3    7948   486.2    7978   483.6    8265   483.6    8586   477.6
    8647   479.7    8682   483.4    9499   490.4    9726   496.1    9976   506.3
#Mann= 5 ,-1,0
    5750     .07       0    6300    .075       0    6900     .13       0
    6996    .055       0    7214    .075       0
Bank Sta=6996,7214
XS Rating Curve= 0 ,0
Exp/Cntr=0.3,0.1

Type RM Length L Ch R = 1 ,160768  ,819,2158,215
BEGIN DESCRIPTION:
This cross section corresponds to cross section 160778 of the non-georeferenced CDC model which was the source of this model.
Copied geometry from XS 160878
END DESCRIPTION:
XS GIS Cut Line= 5
  2371740.543566 6974131.6257075 2371696.1854117 6973885.5924697
 2371566.9533651 6973168.8047822 2371189.4341051 6971923.0047822
 2370816.2677328 6970013.2096417
#Sta/Elev= 30
    5750     509    6150     490    6300     480    6628   478.1    6900   484.1
    6949   483.8    6966   486.4    6996     484    7023   468.3    7062   455.6
    7070     451    7105   447.5    7115     448    7119   455.6    7162   469.2
    7190   480.8    7214   485.5    7229   481.4    7385   483.5    7924   483.3
    7948   486.2    7978   483.6    8265   483.6    8586   477.6    8647   479.7
    8682   483.4    9100     486    9300     492    9650     492    9976   506.3
#Mann= 5 ,-1,0
    5750     .07       0    6300    .075       0    6900     .13       0
    6996    .055       0    7214    .075       0
#XS Ineff= 2 , 0
       0    6996     484    7214       0   485.5
Permanent Ineff=
       F       F
#Block Obstruct= 1 ,-1
    9312    9555     500
Bank Sta=6996,7214
XS Rating Curve= 0 ,0
Exp/Cntr=0.3,0.1

Type RM Length L Ch R = 1 ,158611  ,116,106,126
BEGIN DESCRIPTION:
This cross section corresponds to cross section 158671 of the non-georeferenced CDC model which was the source of this model.
XS Added - GeoRas
END DESCRIPTION:
XS GIS Cut Line= 6
  2372586.090192 6973634.5653238  2372593.003609 6973507.8235619
      2372644.42     6972565.221     2372665.254     6972183.277
      2371363.17     6971554.804 2371175.1656432 6969781.7211204
#Sta/Elev= 30
 5126.93     502 5363.42     478 5479.76     476 5858.78  481.79 6022.87  482.98
 6122.02     482 6132.39     480 6164.25     478 6197.42     466 6216.78  457.17
 6223.95  452.45 6250.53  448.91 6274.73   447.6 6315.75     456  6355.8     478
 6372.34   481.4 6419.68     484 6540.09  484.05 7604.86  483.65 7827.09  481.36
 7936.19     482 7988.46  485.07 8247.14     478 8420.19  477.99 8527.93     480
 8573.68     484    8995   485.6    9040     492    9550     492 9809.22  500.35
#Mann= 4 ,-1,0
 5126.93     .07       0 5858.78     .13       0 6122.02    .055       0
 6372.34    .075       0
#XS Ineff= 2 , 0
       0 6122.02     482 6372.34       0   481.4
Permanent Ineff=
       F       F
#Block Obstruct= 1 ,-1
    9130    9405     500
Bank Sta=6122.02,6372.34
XS Rating Curve= 0 ,0
Exp/Cntr=0.3,0.1

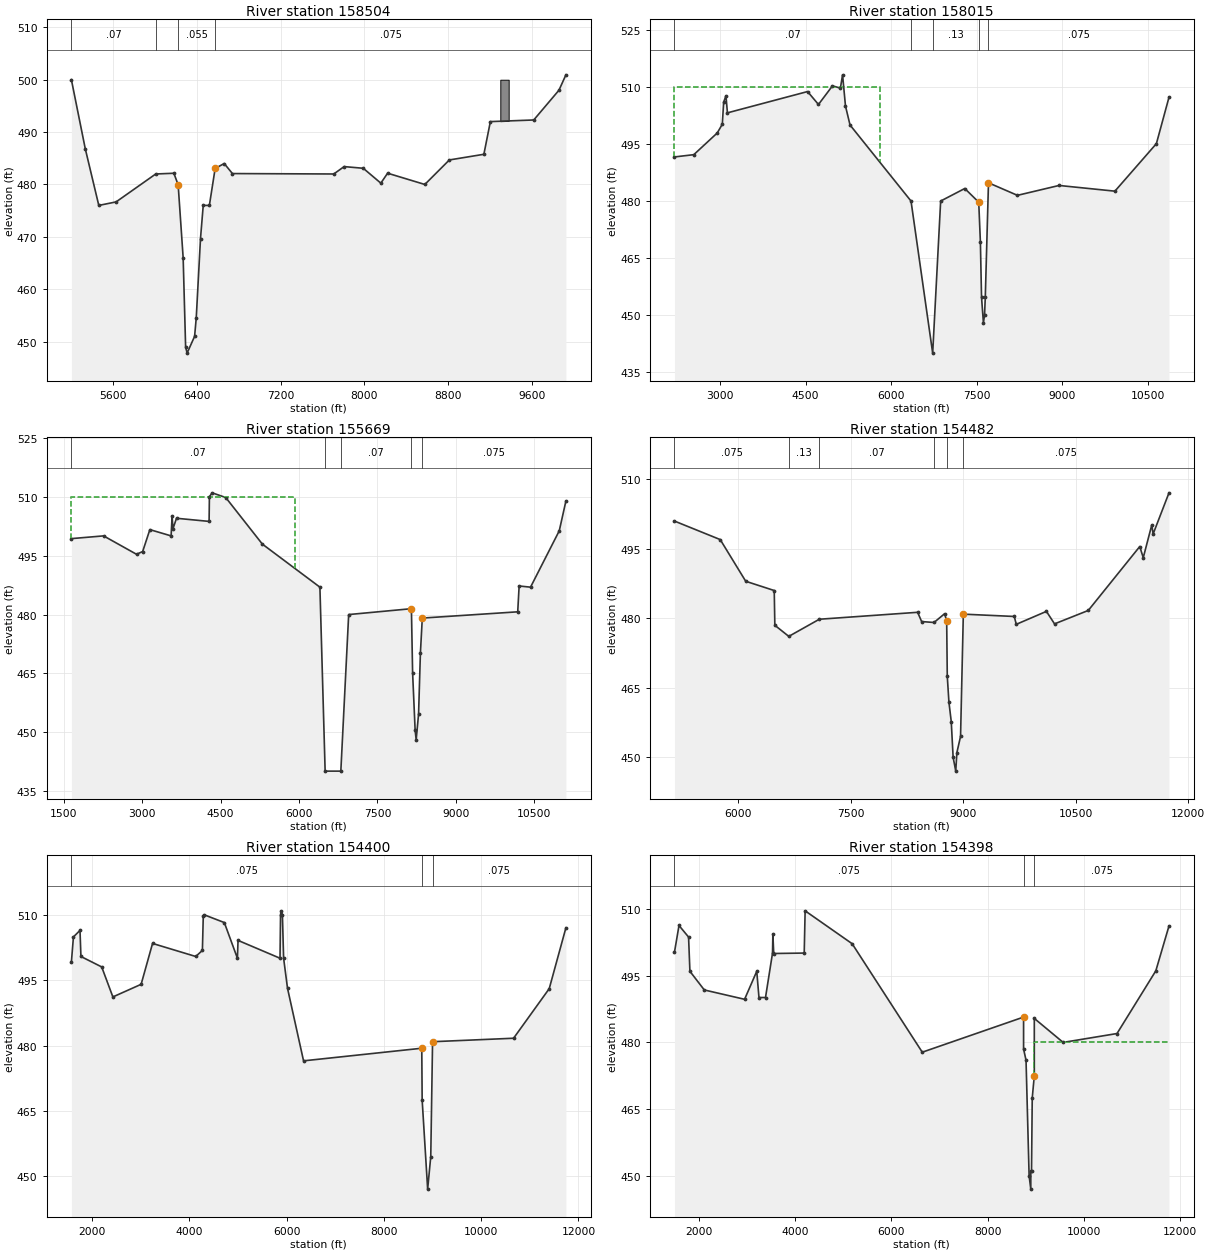
Type RM Length L Ch R = 1 ,158504  ,1106,489,372
BEGIN DESCRIPTION:
This cross section corresponds to cross section 158561 of the non-georeferenced CDC model which was the source of this model.
XS Added - GeoRas
END DESCRIPTION:
XS GIS Cut Line= 6
  2372677.284238 6973766.6996845  2372688.846856 6973568.4868423
     2372748.587     6972544.388     2372772.893     6972127.721
     2371484.698     6971461.054 2371249.3614863 6969841.5680821
#Sta/Elev= 30
 5198.55     500 5331.68  486.78 5460.59     476 5626.01  476.67 6005.02     482
 6178.59  482.14 6219.46  479.93 6267.26     466 6290.82     449 6304.96   447.8
 6376.68     451 6392.39   454.5 6433.14  469.68 6459.26     476 6517.93     476
 6573.23  483.05 6659.85     484 6738.42  482.08 7707.49     482 7806.75  483.41
 7989.45  483.09 8157.59  480.25 8222.28  482.15 8578.14     480 8812.84  484.68
 9142.82  485.76    9205     492 9619.74  492.31 9861.11     498 9927.29  500.93
#Mann= 4 ,-1,0
 5198.55     .07       0 6005.02     .13       0 6219.46    .055       0
 6573.23    .075       0
#XS Ineff= 2 , 0
       0 6219.46  479.93 6573.23       0  483.05
Permanent Ineff=
       F       F
#Block Obstruct= 1 ,-1
    9300    9380     500
Bank Sta=6219.46,6573.23
XS Rating Curve= 0 ,0
Exp/Cntr=0.3,0.1

Type RM Length L Ch R = 1 ,158015  ,1000,2346,1699
BEGIN DESCRIPTION:
This cross section corresponds to cross section 158061 of the non-georeferenced CDC model which was the source of this model.
-------------------------------------------------
CDC FW022307-01 Rocking River M Equestrian Center
Cross-section 158061 - 161734
Located in ROB.
-------------------------------------------------
END DESCRIPTION:
XS GIS Cut Line= 5
  2374406.594046 6977251.9090106 2374375.1860997 6977087.8890701
   2373491.15988   6972471.28907   2371937.53995   6971431.67894
 2371264.0377802  6969613.238869
#Sta/Elev= 30
    2200   491.6    2539   492.2    2950   497.9    3039   500.2    3063     506
    3103   507.7    3129   503.2    4535   508.8    4726   505.4    4972   510.3
    5111   509.7    5149   513.2    5200     505    5280     500    6350     480
    6730     440    6870     480    7293   483.3    7538   479.7    7567   469.2
    7587   454.7    7620     448    7640     450    7653   454.7    7709   484.8
    8217   481.5    8947   484.1    9927   482.6   10655   495.1   10876   507.3
#Mann= 5 ,-1,0
    2200     .07       0    6350     .06       0    6730     .13       0
    7538    .055       0    7709    .075       0
#XS Ineff= 2 , 0
       0    5800     510               0
Permanent Ineff=
       F       F
#Block Obstruct= 2 , 0
            6870     480
Bank Sta=7538,7709
XS Rating Curve= 0 ,0
Exp/Cntr=0.3,0.1

Type RM Length L Ch R = 1 ,155669  ,350,1187,1499
BEGIN DESCRIPTION:
This cross section corresponds to cross section 155714 of the non-georeferenced CDC model which was the source of this model.
END DESCRIPTION:
XS GIS Cut Line= 4
  2375216.900499 6977247.5845485   2374246.14885   6971151.04991
   2373326.55916   6970296.25897   2372405.52196   6968494.91907
#Sta/Elev= 30
    1650   499.4    2265   500.1    2895   495.4    3012   496.1    3150   501.7
    3556   500.1    3575   505.1    3591   501.9    3659   504.6    4282   503.8
    4288   510.1    4340   511.1    4600   509.9    5300     498    6400     487
    6500     440    6800     440    6950     480    8149   481.5    8172   465.1
    8220   450.5    8240     448    8286   454.6    8321   470.2    8357   479.1
   10181   480.7   10208   487.3   10426     487   10975   501.4   11102     509
#Mann= 5 ,-1,0
    1650     .07       0    6500     .04       0    6800     .07       0
    8149    .055       0    8357    .075       0
#XS Ineff= 2 , 0
       0    5933     510    8357       0   479.1
Permanent Ineff=
       F       F
#Block Obstruct= 2 , 0
            6950     480
Bank Sta=8149,8357
XS Rating Curve= 0 ,0
Exp/Cntr=0.3,0.1

Type RM Length L Ch R = 1 ,154482  ,83,83,83
BEGIN DESCRIPTION:
This cross section corresponds to cross section 154527 of the non-georeferenced CDC model which was the source of this model.
END DESCRIPTION:
XS GIS Cut Line= 6
  2374800.699271 6973662.8791966   2374793.20189    6973308.0141
   2374715.41793     6972496.144   2374705.69485   6970969.63393
   2374686.24902   6970624.46796   2373819.26716     6967181.798
#Sta/Elev= 30
    5150     501    5760     497    6100     488    6480     486    6488   478.5
    6674   476.1    7081   479.8    8392   481.3    8445   479.3    8610   479.1
    8752     481    8779   479.4    8787   467.5    8809   461.9    8840   457.7
    8865     450    8900     447    8915     451    8964   454.5    9001   480.9
    9680   480.4    9707   478.7   10109   481.5   10217   478.8   10667   481.7
   11353   495.5   11400   493.1   11514   500.2   11531   498.2   11743   507.1
#Mann= 6 ,-1,0
    5150    .075       0    6674     .13       0    7081     .07       0
    8610     .13       0    8779    .055       0    9001    .075       0
#XS Ineff= 2 , 0
            8779   479.4    9001           480.9
Permanent Ineff=
       F       F
#Block Obstruct= 2 , 0
       0    5900                       0
Bank Sta=8779,9001
XS Rating Curve= 0 ,0
Exp/Cntr=0.3,0.1

Type RM Length L Ch R = 1 ,154400  ,1,1,1
BEGIN DESCRIPTION:
This cross section corresponds to cross section 154445 of the non-georeferenced CDC model which was the source of this model.
END DESCRIPTION:
XS GIS Cut Line= 6
  2375398.244882 6977175.2932533 2374899.9057473 6974085.5876751
 2374812.3987045 6972549.3545271 2374802.6756268 6970964.5066469
 2374768.6455112 6970638.7868259 2373893.0406351 6967159.7826291
#Sta/Elev= 30
    1574   499.2    1616     505    1751   506.5    1770   500.5    2197   498.1
    2427   491.2    3008   494.1    3243   503.5    4131   500.5    4268   501.9
    4286   509.8    4302   510.1    4719   508.3    4988   500.1    5001   504.2
    5864   500.1    5875   510.1    5888     511    5913   510.1    5938   500.1
    6018   493.2    6348   476.5    8779   479.4    8787   467.5    8900     447
    8964   454.5    9001   480.9   10667   481.7   11400   493.1   11743   507.1
#Mann= 3 ,0,0
    1574    .075       0    8779    .055       0    9001    .075       0
#XS Ineff= 2 , 0
            8779   479.4    9001           480.9
Permanent Ineff=
       F       F
#Block Obstruct= 2 , 0
            5750     511
Bank Sta=8779,9001
XS Rating Curve= 0 ,0
Exp/Cntr=0.3,0.1

Type RM Length L Ch R = 1 ,154398  ,41,41,41
BEGIN DESCRIPTION:
This cross section corresponds to cross section 154444 of the non-georeferenced CDC model which was the source of this model.
END DESCRIPTION:
XS GIS Cut Line= 6
   2375417.43061 6977288.3246735 2374900.7797613 6974085.0863637
 2374813.2727185 6972548.8532157 2374803.5496408 6970964.0053356
 2374769.5195252 6970638.2855146 2373893.9146491 6967159.2813177
#Sta/Elev= 30
    1490   500.3    1584   506.3    1783   503.7    1811     496    2110   491.8
    2948   489.7    3201     496    3247   490.1    3383   490.1    3529   500.1
    3536   504.4    3554     500    4188   500.1    4207   509.6    5185   502.2
    6643   477.8    8750   485.7    8750   478.5    8801     476    8865     450
    8900     447    8900     451    8915     451    8930   467.5    8973   472.5
    8973   485.4    9573     480   10693     482   11500   496.1   11774   506.2
#Mann= 3 ,0,0
    1490    .075       0    8750    .055       0    8973    .075       0
#XS Ineff= 2 , 0
       0    8750   477.8    8973       0     480
Permanent Ineff=
       F       F
#Block Obstruct= 2 , 0
       0    5750                       0
Bank Sta=8750,8973
XS Rating Curve= 0 ,0
Exp/Cntr=0.3,0.1

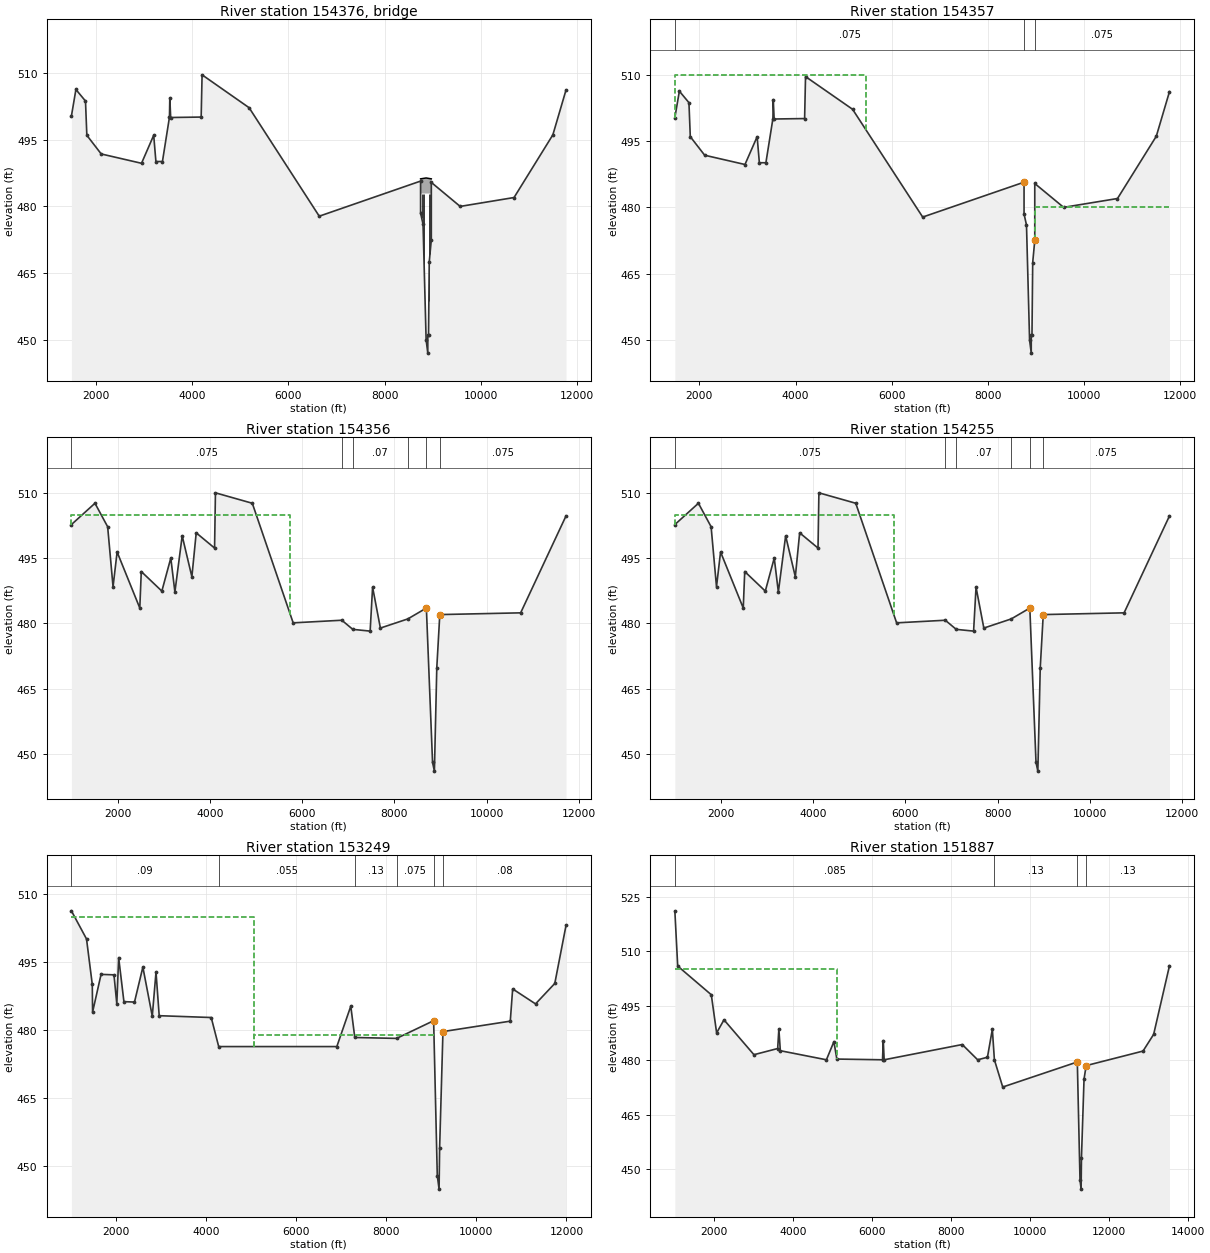
Type RM Length L Ch R = 3 ,154376  ,,,
BEGIN DESCRIPTION:
Precinct Line Road
END DESCRIPTION:
Node Name=Precinct Line Ro
Bridge Culvert--1,0,-1,-1, 0
Deck Dist Width WeirC Skew NumUp NumDn MinLoCord MaxHiCord MaxSubmerge Is_Ogee
1,38,2.6,0, 3, 3, , , 0.95, 0, ,,,
    8750    8865    8973
   486.2   486.4   486.2
   482.9   482.9   482.9
    8750    8865    8973
   486.2   486.4   486.2
   482.9   482.9   482.9
Pier Skew, UpSta & Num, DnSta & Num=  ,8771, 2 ,8771, 2 , 0 , 0 , 0 ,,
       2       2
     455     485
       2       2
     455     485
Pier Skew, UpSta & Num, DnSta & Num=  ,8799.5, 2 ,8799.5, 2 , 0 , 0 , 0 ,,
       3       3
     455     485
       3       3
     455     485
Pier Skew, UpSta & Num, DnSta & Num=  ,8823, 2 ,8823, 2 , 0 , 0 , 0 ,,
       4       4
     455     485
       4       4
     455     485
Pier Skew, UpSta & Num, DnSta & Num=  ,8922, 2 ,8922, 2 , 0 , 0 , 0 ,,
       4       4
     455     485
       4       4
     455     485
Pier Skew, UpSta & Num, DnSta & Num=  ,8946, 2 ,8946, 2 , 0 , 0 , 0 ,,
       2       2
     455     485
       2       2
     455     485
BR Coef= 1 , 0 , 0 ,1.05, 0 ,,,0.8,-1,0.5,1,
WSPro=,,,, 1 ,,,, 0 ,,,, 0 ,,,,-1 ,-1 ,-1 , 0 , 0 , 0 , 0 , 0
BC Design=,, 0 ,, 0 ,,,,,,
BC HTab HWMax=506.2
BC Use User HTab Curves=0
BC User HTab FreeFlow(D)= 0

Type RM Length L Ch R = 1 ,154357  ,1,1,1
BEGIN DESCRIPTION:
This cross section corresponds to cross section 154404 of the non-georeferenced CDC model which was the source of this model.
END DESCRIPTION:
XS GIS Cut Line= 6
  2375453.266234 6977267.7661527 2374936.6153862 6974064.5278488
 2374849.1083362 6972528.2946988 2374839.3852662 6970943.4468188
 2374805.3551462 6970617.7269988 2373929.7502662 6967138.7227988
#Sta/Elev= 30
    1490   500.3    1584   506.3    1783   503.7    1811     496    2110   491.8
    2948   489.7    3201     496    3247   490.1    3383   490.1    3529   500.1
    3536   504.4    3554     500    4188   500.1    4207   509.6    5185   502.2
    6643   477.8    8750   485.7    8750   478.5    8801     476    8865     450
    8900     447    8900     451    8915     451    8930   467.5    8973   472.5
    8973   485.4    9573     480   10693     482   11500   496.1   11774   506.2
#Mann= 3 ,0,0
    1490    .075       0    8750    .055       0    8973    .075       0
#XS Ineff= 2 , 0
       0    5466     510    8973       0     480
Permanent Ineff=
       F       F
#Block Obstruct= 2 , 0
       0    5750                       0
Bank Sta=8750,8973
XS Rating Curve= 0 ,0
Exp/Cntr=0.3,0.1

Type RM Length L Ch R = 1 ,154356  ,101,101,101
BEGIN DESCRIPTION:
This cross section corresponds to cross section 154403 of the non-georeferenced CDC model which was the source of this model.
END DESCRIPTION:
XS GIS Cut Line= 6
     2375524.327     6977702.037      2374937.62      6974064.48
      2374850.14      6972528.37      2374840.39      6970943.44
      2374806.35      6970617.86      2373930.66      6967138.23
#Sta/Elev= 30
    1000   502.7    1511   507.6    1786   502.2    1903   488.4    1991   496.4
    2483   483.5    2515   491.9    2961   487.4    3155     495    3244   487.2
    3402   500.1    3612   490.7    3706   500.8    4104   497.3    4123     510
    4922   507.6    5808   480.1    6863   480.7    7101   478.6    7477   478.2
    7530   488.3    7699   478.9    8293     481    8696   483.5    8830     448
    8870     446    8922   469.8    8987     482   10740   482.4   11724   504.7
#Mann= 6 ,-1,0
    1000    .075       0    6863     .13       0    7101     .07       0
    8293     .12       0    8696    .055       0    8987    .075       0
#XS Ineff= 3 ,-1
    1000    5750     505    5750    8696   480.1    8987   11724     482
Permanent Ineff=
       F       F       F
Bank Sta=8696,8987
XS Rating Curve= 0 ,0
Exp/Cntr=0.3,0.1

Type RM Length L Ch R = 1 ,154255  ,1198,1006,599
BEGIN DESCRIPTION:
This cross section corresponds to cross section 154301 of the non-georeferenced CDC model which was the source of this model.
END DESCRIPTION:
XS GIS Cut Line= 6
  2375613.267176 6977650.5554074   2375026.55412     6974012.931
   2374939.04707   6972476.69785     2374929.324   6970891.84997
   2374895.29388   6970566.13015     2374019.689   6967087.12595
#Sta/Elev= 30
    1000   502.7    1511   507.6    1786   502.2    1903   488.4    1991   496.4
    2483   483.5    2515   491.9    2961   487.4    3155     495    3244   487.2
    3402   500.1    3612   490.7    3706   500.8    4104   497.3    4123     510
    4922   507.6    5808   480.1    6863   480.7    7101   478.6    7477   478.2
    7530   488.3    7699   478.9    8293     481    8696   483.5    8830     448
    8870     446    8922   469.8    8987     482   10740   482.4   11724   504.7
#Mann= 6 ,-1,0
    1000    .075       0    6863     .13       0    7101     .07       0
    8293     .12       0    8696    .055       0    8987    .075       0
#XS Ineff= 3 ,-1
    1000    5750     505    5750    8696   480.1    8987   11724     482
Permanent Ineff=
       F       F       F
Bank Sta=8696,8987
XS Rating Curve= 0 ,0
Exp/Cntr=0.3,0.1

Type RM Length L Ch R = 1 ,153249  ,860,1362,950
BEGIN DESCRIPTION:
This cross section corresponds to cross section 153293 of the non-georeferenced CDC model which was the source of this model.
END DESCRIPTION:
XS GIS Cut Line= 5
  2376636.239987 6977489.8100756   2376636.19985   6977489.38894
   2375925.88992   6970036.66008    2375036.4291   6968815.61888
   2374455.51884   6966908.72014
#Sta/Elev= 30
    1000   506.3    1336   500.1    1464   490.1    1471     484    1659   492.3
    1946   492.2    2009   485.8    2050     496    2167   486.3    2402   486.2
    2588   493.9    2797   483.1    2880   492.8    2951   483.2    4107   482.8
    4273   476.4    6898   476.4    7208   485.3    7297   478.4    8226   478.2
    9049   482.1    9130     448    9170     445    9182     454    9256   479.7
   10752     482   10805   489.1   11313   485.8   11741   490.3   11991   503.1
#Mann= 6 ,-1,0
    1000     .09       0    4273    .055       0    7297     .13       0
    8226    .075       0    9049    .055       0    9256     .08       0
#XS Ineff= 3 ,-1
    1000    5050     505    5050    9049     479    9256   11991   479.7
Permanent Ineff=
       F       F       F
Bank Sta=9049,9256
XS Rating Curve= 0 ,0
Exp/Cntr=0.3,0.1

Type RM Length L Ch R = 1 ,151887  ,802,798,1053
BEGIN DESCRIPTION:
This cross section corresponds to cross section 151932 of the non-georeferenced CDC model which was the source of this model.
END DESCRIPTION:
XS GIS Cut Line= 3
   2378026.87631 6978442.6383771   2376553.11898   6968657.02012
   2374705.68993   6966785.11015
#Sta/Elev= 30
    1000   521.1    1072   505.9    1923     498    2058   487.5    2244   491.1
    3003   481.5    3604   483.2    3634   488.6    3671   482.6    4838   480.1
    5028   485.1    5102   480.3    6259   480.1    6278   485.4    6300   480.1
    8278   484.3    8668   480.1    8916   480.8    9040   488.5    9092   480.1
    9303   472.6   11192   479.5   11260     447   11288   444.5   11297   453.2
   11362   474.8   11416   478.5   12856   482.5   13125   487.1   13526     506
#Mann= 4 ,-1,0
    1000    .085       0    9092     .13       0   11192     .05       0
   11416     .13       0
#XS Ineff= 3 ,-1
    1000    5100     505    5100   11192   475.6   11416   13526   477.5
Permanent Ineff=
       F       F       F
Bank Sta=11192,11416
XS Rating Curve= 0 ,0
Exp/Cntr=0.3,0.1

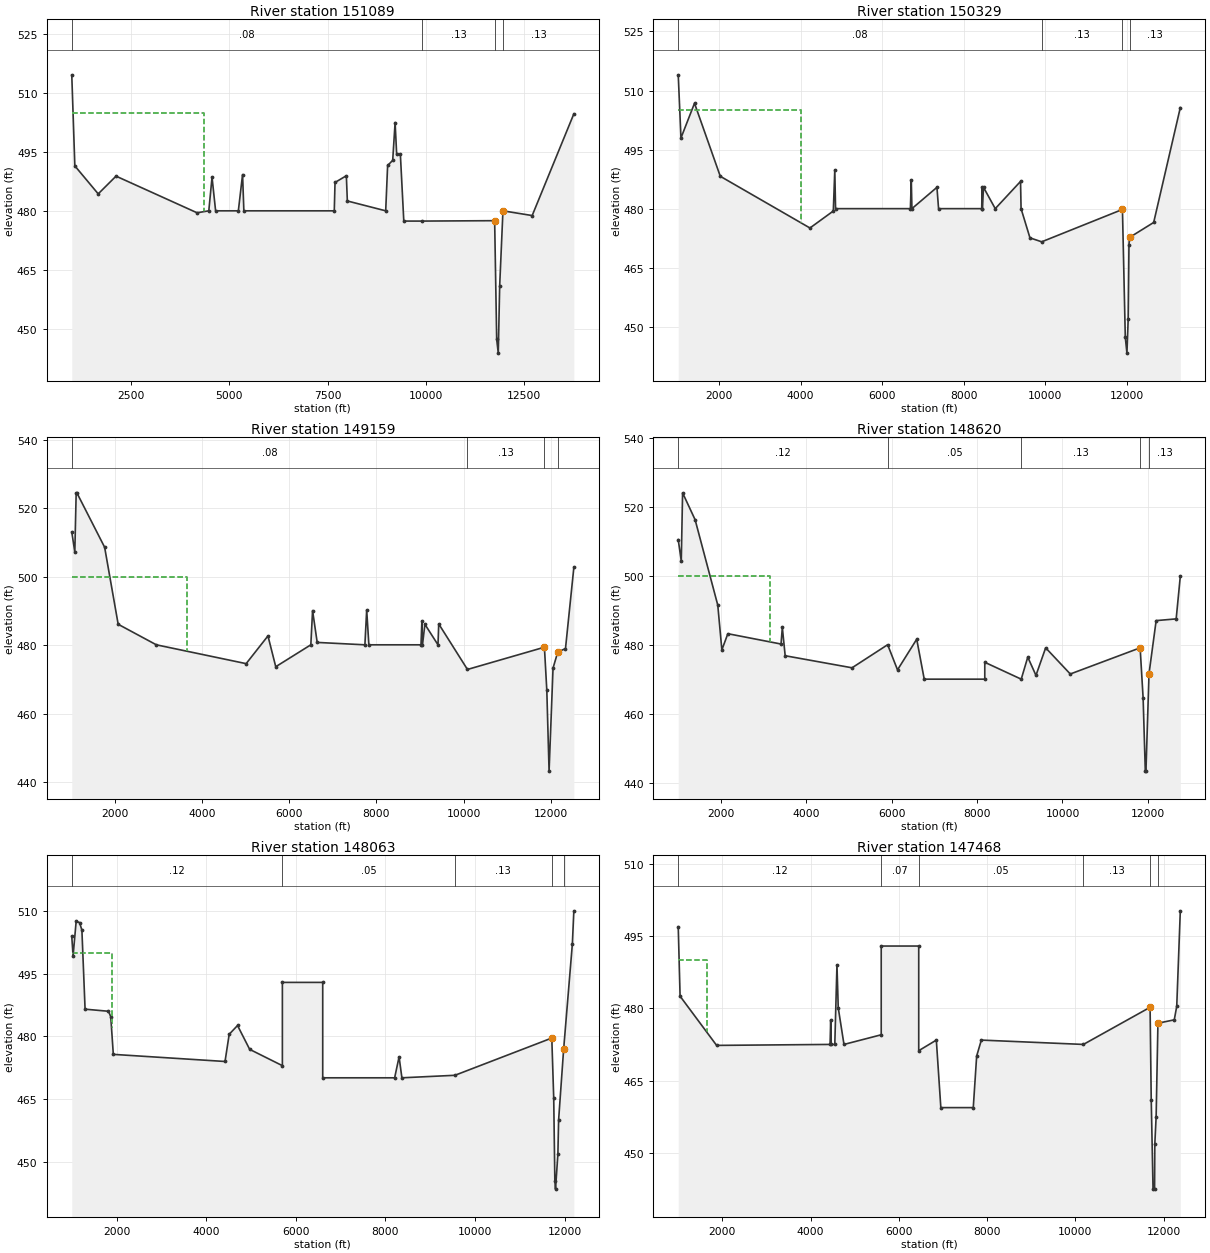
Type RM Length L Ch R = 1 ,151089  ,429,760,898
BEGIN DESCRIPTION:
This cross section corresponds to cross section 151136 of the non-georeferenced CDC model which was the source of this model.
END DESCRIPTION:
XS GIS Cut Line= 6
  2378559.604136 6978518.6939663 2378062.9548674 6973839.7476156
 2377819.8549599 6971550.0546884 2377544.9998666 6968961.7101276
 2376505.2814736 6967247.5255638 2375911.1061527 6966268.0068536
#Sta/Elev= 30
    1000   514.6    1078   491.5    1672   484.4    2125   488.9    4185   479.6
    4483   480.1    4565   488.6    4656   480.1    5234   480.1    5341   489.3
    5374   480.1    7672   480.1    7691   487.3    7979     489    8004   482.6
    8979   480.1    9028   491.6    9157   492.9    9218   502.5    9258   494.4
    9352   494.4    9439   477.5    9914   477.5   11748   477.6   11800   447.5
   11840     444   11876   461.1   11959   480.1   12702   478.9   13761   504.7
#Mann= 4 ,-1,0
    1000     .08       0    9914     .13       0   11748     .05       0
   11959     .13       0
#XS Ineff= 3 ,-1
    1000    4350     505    4350   11748     473   11959   13761   478.9
Permanent Ineff=
       F       F       F
Bank Sta=11748,11959
XS Rating Curve= 0 ,0
Exp/Cntr=0.3,0.1

Type RM Length L Ch R = 1 ,150329  ,549,1170,1358
BEGIN DESCRIPTION:
This cross section corresponds to cross section 150374 of the non-georeferenced CDC model which was the source of this model.
END DESCRIPTION:
XS GIS Cut Line= 3
   2378782.41111   6978502.98599   2378075.32886       6968907.1
 2377143.8019386 6966383.4347682
#Sta/Elev= 30
    1000     514    1067     498    1399   506.8    2031   488.3    4230   475.2
    4803   479.5    4839   489.9    4858   480.1    6693   480.1    6715   487.4
    6730   480.1    7344   485.5    7384   480.1    8442   480.1    8451   485.5
    8457   480.1    8486   485.5    8774   480.1    9394     487    9407   480.1
    9625   472.7    9913   471.7   11893   479.9   11963   447.5   12003   443.5
   12034   452.1   12053     471   12066   472.8   12659   476.6   13312   505.7
#Mann= 4 ,-1,0
    1000     .08       0    9913     .13       0   11893     .05       0
   12066     .13       0
#XS Ineff= 3 ,-1
    1000    4000     505    4000   11893     473   12066   13312   472.8
Permanent Ineff=
       F       F       F
Bank Sta=11893,12066
XS Rating Curve= 0 ,0
Exp/Cntr=0.3,0.1

Type RM Length L Ch R = 1 ,149159  ,480,539,550
BEGIN DESCRIPTION:
This cross section corresponds to cross section 149202 of the non-georeferenced CDC model which was the source of this model.
END DESCRIPTION:
XS GIS Cut Line= 2
  2379060.506912 6978457.0551653   2378708.55692   6966928.42614
#Sta/Elev= 30
    1000   513.1    1070   507.2    1101   524.4    1117   524.5    1755   508.6
    2066   486.1    2943   480.1    5006   474.6    5507   482.7    5686   473.7
    6492   480.1    6532   490.1    6638   480.8    7734   480.1    7775   490.3
    7825   480.1    9023   480.1    9043   487.1    9057   480.1    9112   486.1
    9413   480.1    9430   486.2   10090   472.9   11858   479.4   11913   466.8
   11965   443.2   12056   473.3   12165     478   12342     479   12534   502.7
#Mann= 4 ,-1,0
    1000     .08       0   10090     .13       0   11858     .05       0
   12165     .12       0
#XS Ineff= 3 ,-1
    1000    3650     500    3650   11858     473   12165   12534   476.5
Permanent Ineff=
       F       F       F
Bank Sta=11858,12165
XS Rating Curve= 0 ,0
Exp/Cntr=0.3,0.1

Type RM Length L Ch R = 1 ,148620  ,899,557,500
BEGIN DESCRIPTION:
This cross section corresponds to cross section 148663 of the non-georeferenced CDC model which was the source of this model.
END DESCRIPTION:
XS GIS Cut Line= 3
  2379467.410259 6978522.3299658   2379466.17516   6978455.19901
   2379251.08208   6966764.31984
#Sta/Elev= 30
    1000   510.6    1071   504.4    1102   524.2    1395   516.4    1926   491.6
    2022   478.6    2162   483.3    3408   480.3    3438   485.1    3505   476.9
    5071   473.4    5905   480.1    6136   472.8    6586   481.7    6762   470.1
    8180   470.1    8180     475    9034   470.1    9187   476.5    9379   471.2
    9606   479.2   10183   471.6   11819   479.2   11889   464.6   11940   443.4
   11955   443.4   12027   471.7   12194   487.1   12663   487.6   12760     500
#Mann= 5 ,-1,0
    1000     .12       0    5905     .05       0    9034     .13       0
   11819     .05       0   12027     .13       0
#XS Ineff= 3 ,-1
    1000    3150     500    3150   11819   473.1   12027   12760   471.7
Permanent Ineff=
       F       F       F
Bank Sta=11819,12027
XS Rating Curve= 0 ,0
Exp/Cntr=0.3,0.1

Type RM Length L Ch R = 1 ,148063  ,801,595,551
BEGIN DESCRIPTION:
This cross section corresponds to cross section 148106 of the non-georeferenced CDC model which was the source of this model.
END DESCRIPTION:
XS GIS Cut Line= 3
  2380663.686699 6978368.9249946   2380042.69008   6968821.25011
   2379742.11588   6967212.94492
#Sta/Elev= 30
    1000   503.9    1029   499.2    1098   507.5    1173   507.2    1226   505.4
    1297   486.5    1819     486    1870   484.7    1927   475.7    4420     474
    4513   480.5    4699   482.6    4970   476.9    5700     473    5700   492.9
    6600   492.9    6600   470.1    8205   470.1    8304   475.1    8367   470.1
    9550   470.7   11712   479.6   11755   465.2   11780   445.5   11795   443.5
   11848   451.9   11864     460   11976   476.9   12171   502.1   12204     510
#Mann= 5 ,-1,0
    1000     .12       0    5700     .05       0    9550     .13       0
   11712     .05       0   11976     .13       0
#XS Ineff= 2 , 0
       0    1887     500               0
Permanent Ineff=
       F       F
Bank Sta=11712,11976
XS Rating Curve= 0 ,0
Exp/Cntr=0.3,0.1

Type RM Length L Ch R = 1 ,147468  ,9,9,9
BEGIN DESCRIPTION:
This cross section corresponds to cross section 147512 of the non-georeferenced CDC model which was the source of this model.
END DESCRIPTION:
XS GIS Cut Line= 5
  2381689.690602 6978296.0682551   2381689.67596   6978295.92505
   2380694.93189   6968566.94484   2380231.07586   6967037.73793
  2380231.034075 6967037.6001762
#Sta/Elev= 30
    1000   496.9    1042   482.5    1870   472.3    4441   472.5    4455   477.5
    4468   472.5    4548   472.5    4597     489    4626   480.1    4756   472.5
    5600   474.5    5600   492.9    6450   492.9    6450   471.2    6849   473.4
    6951   459.4    7686   459.4    7763   470.1    7869   473.4   10182   472.5
   11693   480.2   11719     461   11760   442.5   11795   442.5   11800   451.8
   11830   457.5   11871   476.9   12241   477.6   12297   480.4   12378   500.2
#Mann= 6 ,-1,0
    1000     .12       0    5600     .07       0    6450     .05       0
   10182     .13       0   11693    .055       0   11871     .13       0
#XS Ineff= 2 , 0
       0    1650     490               0
Permanent Ineff=
       F       F
Bank Sta=11693,11871
XS Rating Curve= 0 ,0
Exp/Cntr=0.3,0.1