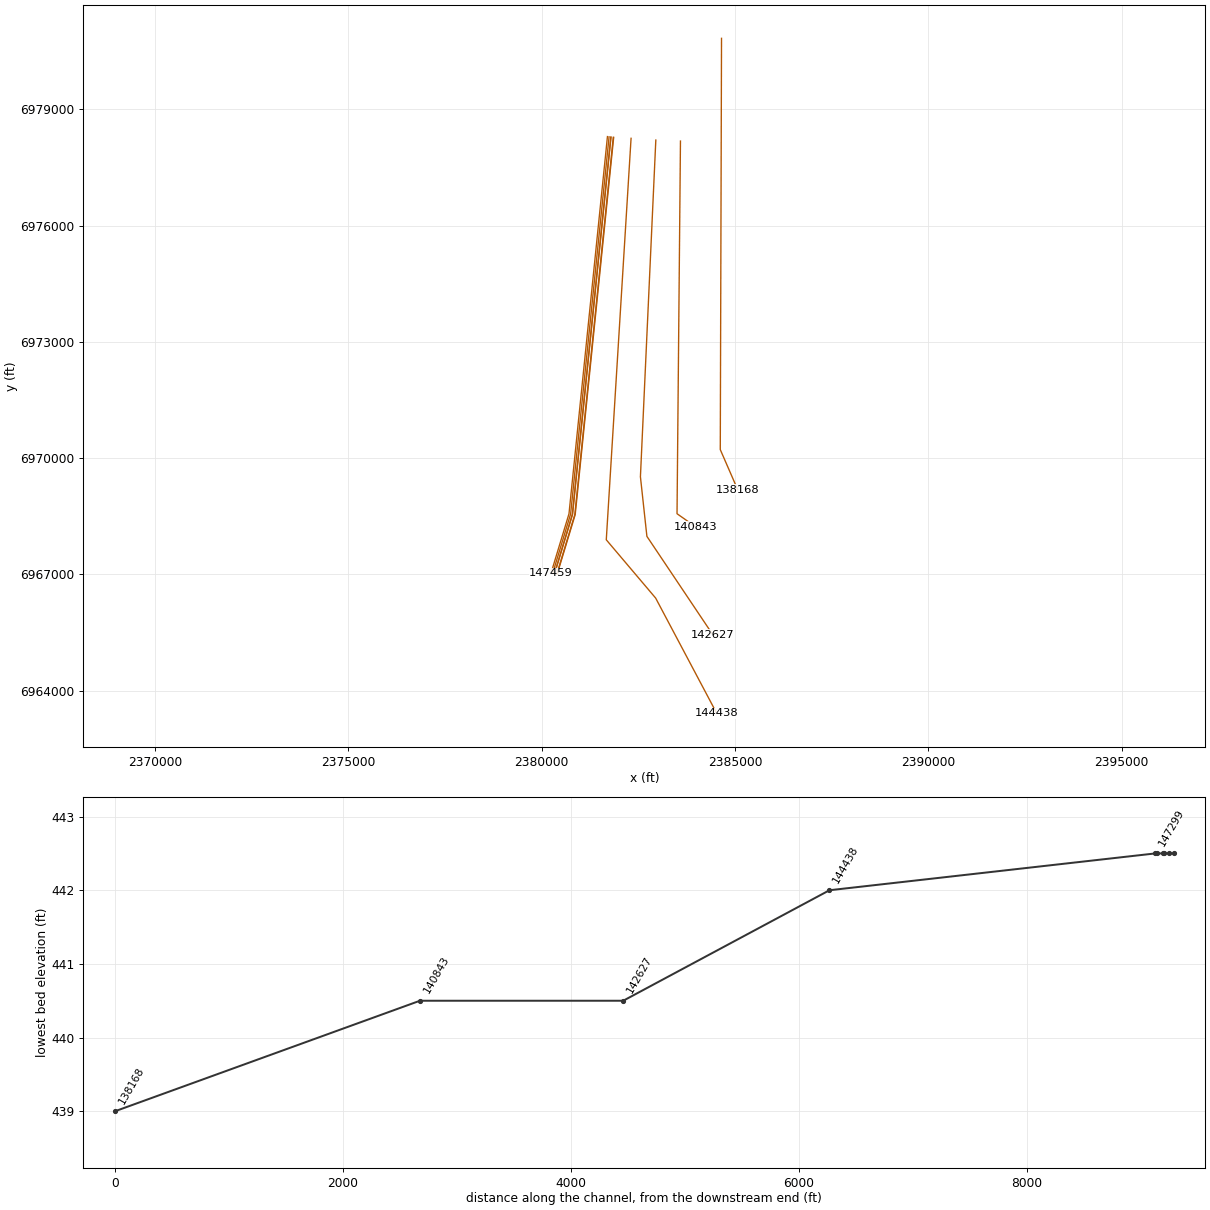
HEC-RAS study CDC_Consolidated_Model.prj: Upper Trinity CDC Consolidated Model

--- CDC_Consolidated_Model.g04 (geometry) --- (continued)

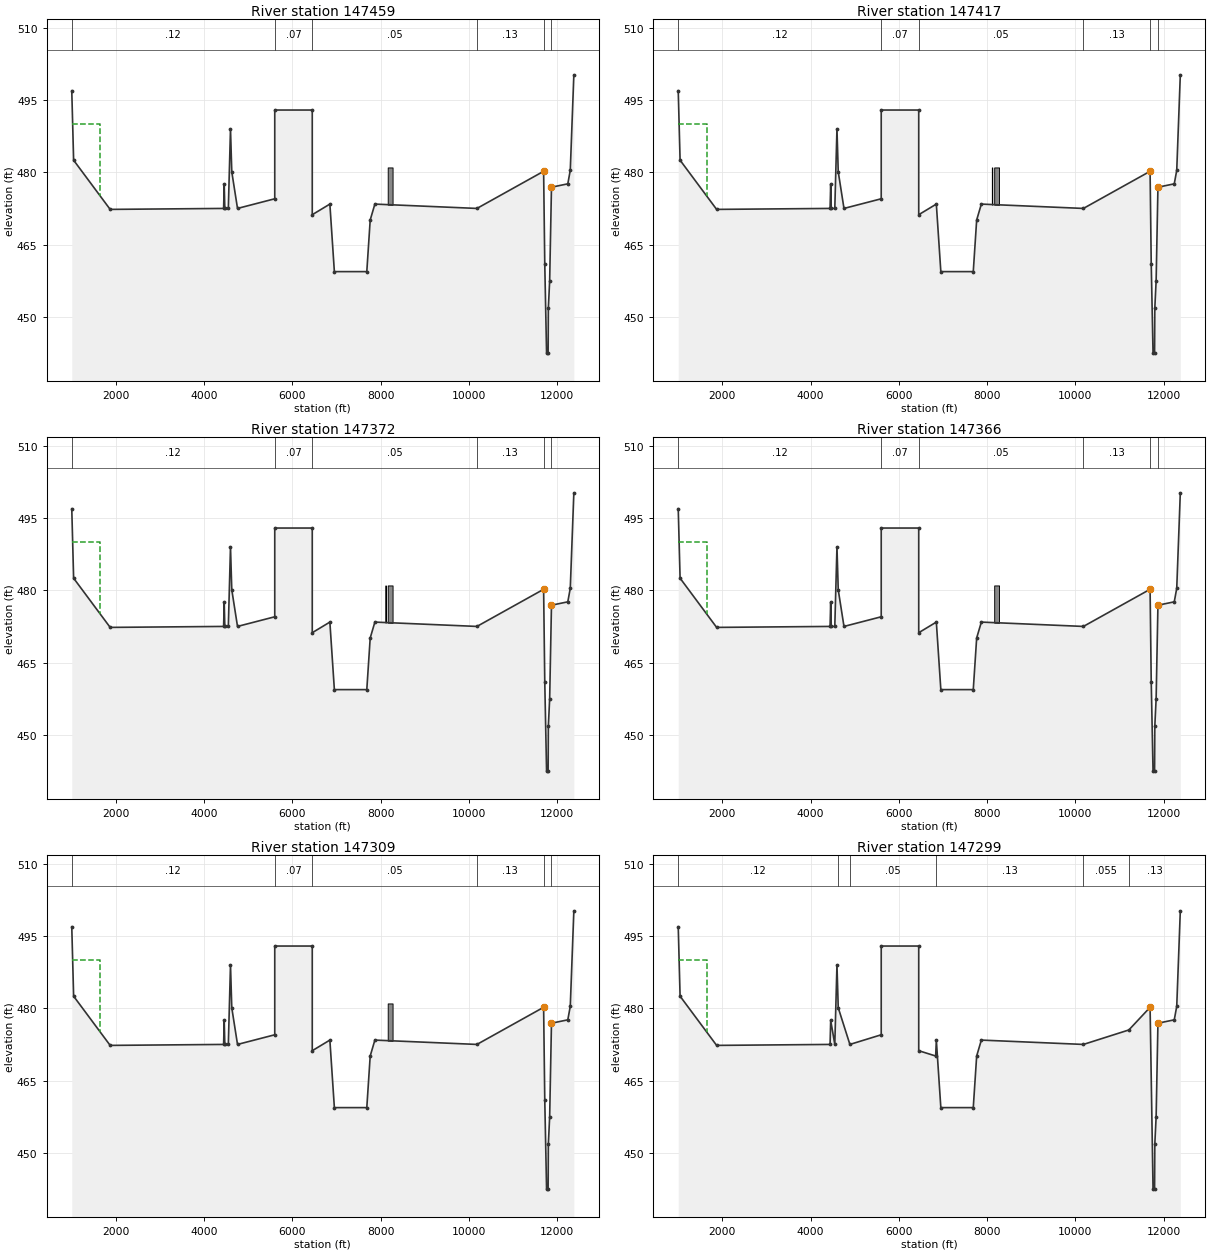
Type RM Length L Ch R = 1 ,147459  ,42,42,42
BEGIN DESCRIPTION:
This cross section corresponds to cross section 147496 of the non-georeferenced CDC model which was the source of this model.
THIS SECTION WAS COPIED FROM 1475+12
1) THE 110' BLOCKED OBSTRUCTION MODELS THE BERM THAT THE TANKS WILL BE ELEVATED ON
END DESCRIPTION:
XS GIS Cut Line= 5
  2381698.477657 6978294.5800697  2381698.463016 6978294.4368689
 2380703.7189428  6968565.456655 2380239.8629152 6967036.2497397
 2380239.8211315 6967036.1119901
#Sta/Elev= 30
    1000   496.9    1042   482.5    1870   472.3    4441   472.5    4455   477.5
    4468   472.5    4548   472.5    4597     489    4626   480.1    4756   472.5
    5600   474.5    5600   492.9    6450   492.9    6450   471.2    6849   473.4
    6951   459.4    7686   459.4    7763   470.1    7869   473.4   10182   472.5
   11693   480.2   11719     461   11760   442.5   11795   442.5   11800   451.8
   11830   457.5   11871   476.9   12241   477.6   12297   480.4   12378   500.2
#Mann= 6 ,-1,0
    1000     .12       0    5600     .07       0    6450     .05       0
   10182     .13       0   11693    .055       0   11871     .13       0
#XS Ineff= 2 , 0
       0    1650     490               0
Permanent Ineff=
       F       F
#Block Obstruct= 2 ,-1
                            8160    8270     481
Bank Sta=11693,11871
XS Rating Curve= 0 ,0
Exp/Cntr=0.3,0.1

Type RM Length L Ch R = 1 ,147417  ,45,45,45
BEGIN DESCRIPTION:
This cross section corresponds to cross section 147424 of the non-georeferenced CDC model which was the source of this model.
THIS SECTION WAS COPIED FROM 1475+12
1) THE 10'  BLOCKED OBSTRUCTION REPRESENTS THE GAS WELL HEAD
2) THE 110' BLOCKED OBSTRUCTION MODELS THE BERM THAT THE TANKS WILL BE ELEVATED ON
END DESCRIPTION:
XS GIS Cut Line= 5
  2381740.376851 6978287.4849395   2381740.36221 6978287.3417387
 2380745.6181372 6968558.3615248 2380281.7621096 6967029.1546095
 2380281.7203258 6967029.0168598
#Sta/Elev= 30
    1000   496.9    1042   482.5    1870   472.3    4441   472.5    4455   477.5
    4468   472.5    4548   472.5    4597     489    4626   480.1    4756   472.5
    5600   474.5    5600   492.9    6450   492.9    6450   471.2    6849   473.4
    6951   459.4    7686   459.4    7763   470.1    7869   473.4   10182   472.5
   11693   480.2   11719     461   11760   442.5   11795   442.5   11800   451.8
   11830   457.5   11871   476.9   12241   477.6   12297   480.4   12378   500.2
#Mann= 6 ,-1,0
    1000     .12       0    5600     .07       0    6450     .05       0
   10182     .13       0   11693    .055       0   11871     .13       0
#XS Ineff= 2 , 0
       0    1650     490               0
Permanent Ineff=
       F       F
#Block Obstruct= 3 ,-1
                            8107    8117     481    8160    8270     481
Bank Sta=11693,11871
XS Rating Curve= 0 ,0
Exp/Cntr=0.3,0.1

Type RM Length L Ch R = 1 ,147372  ,6,6,6
BEGIN DESCRIPTION:
This cross section corresponds to cross section 147414 of the non-georeferenced CDC model which was the source of this model.
THIS SECTION WAS COPIED FROM 1475+12
1) THE 10'  BLOCKED OBSTRUCTION REPRESENTS THE GAS WELL HEAD
2) THE 110' BLOCKED OBSTRUCTION MODELS THE BERM THAT THE TANKS WILL BE ELEVATED ON
END DESCRIPTION:
XS GIS Cut Line= 5
   2381785.09625  6978280.588956  2381785.081609 6978280.4457552
  2380790.337536 6968551.4655412 2380326.4815083 6967022.2586259
 2380326.4397246 6967022.1208763
#Sta/Elev= 30
    1000   496.9    1042   482.5    1870   472.3    4441   472.5    4455   477.5
    4468   472.5    4548   472.5    4597     489    4626   480.1    4756   472.5
    5600   474.5    5600   492.9    6450   492.9    6450   471.2    6849   473.4
    6951   459.4    7686   459.4    7763   470.1    7869   473.4   10182   472.5
   11693   480.2   11719     461   11760   442.5   11795   442.5   11800   451.8
   11830   457.5   11871   476.9   12241   477.6   12297   480.4   12378   500.2
#Mann= 6 ,-1,0
    1000     .12       0    5600     .07       0    6450     .05       0
   10182     .13       0   11693    .055       0   11871     .13       0
#XS Ineff= 2 , 0
       0    1650     490               0
Permanent Ineff=
       F       F
#Block Obstruct= 3 ,-1
                            8107    8117     481    8160    8270     481
Bank Sta=11693,11871
XS Rating Curve= 0 ,0
Exp/Cntr=0.3,0.1

Type RM Length L Ch R = 1 ,147366  ,57,57,57
BEGIN DESCRIPTION:
This cross section corresponds to cross section 147404 of the non-georeferenced CDC model which was the source of this model.
THIS SECTION WAS COPIED FROM 1475+12
1) THE 110' BLOCKED OBSTRUCTION MODELS THE BERM THAT THE TANKS WILL BE ELEVATED ON
END DESCRIPTION:
XS GIS Cut Line= 5
  2381790.800307 6978279.7418448  2381790.785666  6978279.598644
 2380796.0415928 6968550.6184301 2380332.1855652 6967021.4115147
 2380332.1437815 6967021.2737651
#Sta/Elev= 30
    1000   496.9    1042   482.5    1870   472.3    4441   472.5    4455   477.5
    4468   472.5    4548   472.5    4597     489    4626   480.1    4756   472.5
    5600   474.5    5600   492.9    6450   492.9    6450   471.2    6849   473.4
    6951   459.4    7686   459.4    7763   470.1    7869   473.4   10182   472.5
   11693   480.2   11719     461   11760   442.5   11795   442.5   11800   451.8
   11830   457.5   11871   476.9   12241   477.6   12297   480.4   12378   500.2
#Mann= 6 ,-1,0
    1000     .12       0    5600     .07       0    6450     .05       0
   10182     .13       0   11693    .055       0   11871     .13       0
#XS Ineff= 2 , 0
       0    1650     490               0
Permanent Ineff=
       F       F
#Block Obstruct= 2 ,-1
                            8160    8270     481
Bank Sta=11693,11871
XS Rating Curve= 0 ,0
Exp/Cntr=0.3,0.1

Type RM Length L Ch R = 1 ,147309  ,10,10,10
BEGIN DESCRIPTION:
This cross section corresponds to cross section 147346 of the non-georeferenced CDC model which was the source of this model.
THIS SECTION WAS COPIED FROM 1475+12
1) THE 110' BLOCKED OBSTRUCTION MODELS THE BERM THAT THE TANKS WILL BE ELEVATED UPON
END DESCRIPTION:
XS GIS Cut Line= 3
      2381848.81       6978274.3      2380854.37      6968545.83
       2380389.6      6967014.01
#Sta/Elev= 30
    1000   496.9    1042   482.5    1870   472.3    4441   472.5    4455   477.5
    4468   472.5    4548   472.5    4597     489    4626   480.1    4756   472.5
    5600   474.5    5600   492.9    6450   492.9    6450   471.2    6849   473.4
    6951   459.4    7686   459.4    7763   470.1    7869   473.4   10182   472.5
   11693   480.2   11719     461   11760   442.5   11795   442.5   11800   451.8
   11830   457.5   11871   476.9   12241   477.6   12297   480.4   12378   500.2
#Mann= 6 ,-1,0
    1000     .12       0    5600     .07       0    6450     .05       0
   10182     .13       0   11693    .055       0   11871     .13       0
#XS Ineff= 2 , 0
       0    1650     490               0
Permanent Ineff=
       F       F
#Block Obstruct= 2 ,-1
                            8160    8270     481
Bank Sta=11693,11871
XS Rating Curve= 0 ,0
Exp/Cntr=0.3,0.1

Type RM Length L Ch R = 1 ,147299  ,725,2861,2799
BEGIN DESCRIPTION:
This cross section corresponds to cross section 147336 of the non-georeferenced CDC model which was the source of this model.
THIS SECTION WAS COPIED FROM 1475+12 AND IT MODELS THE AREA 10'  DOWNSTREAM OF THE BLOCKED OBSTRUCTION
---------------------------------------
CDC FW122804-01 Gas Well Duck Lake No.1
Located in LOB.
Cross-sections 147336 - 147496
---------------------------------------
END DESCRIPTION:
XS GIS Cut Line= 3
       2381859.3      6978272.91       2380864.8      6968545.85
      2380399.76      6967012.49
#Sta/Elev= 30
    1000   496.9    1042   482.5    1870   472.3    4441   472.5    4455   477.5
    4548   472.5    4597     489    4626   480.1    4890   472.5    5600   474.5
    5600   492.9    6450   492.9    6450   471.2    6834   470.1    6849   473.4
    6951   459.4    7686   459.4    7763   470.1    7869   473.4   10182   472.5
   11212   475.5   11693   480.2   11760   442.5   11795   442.5   11800   451.8
   11830   457.5   11871   476.9   12241   477.6   12297   480.4   12378   500.2
#Mann= 6 ,-1,0
    1000     .12       0    4626     .07       0    4890     .05       0
    6834     .13       0   10182    .055       0   11212     .13       0
#XS Ineff= 2 , 0
       0    1650     490               0
Permanent Ineff=
       F       F
Bank Sta=11693,11871
XS Rating Curve= 0 ,0
Exp/Cntr=0.3,0.1

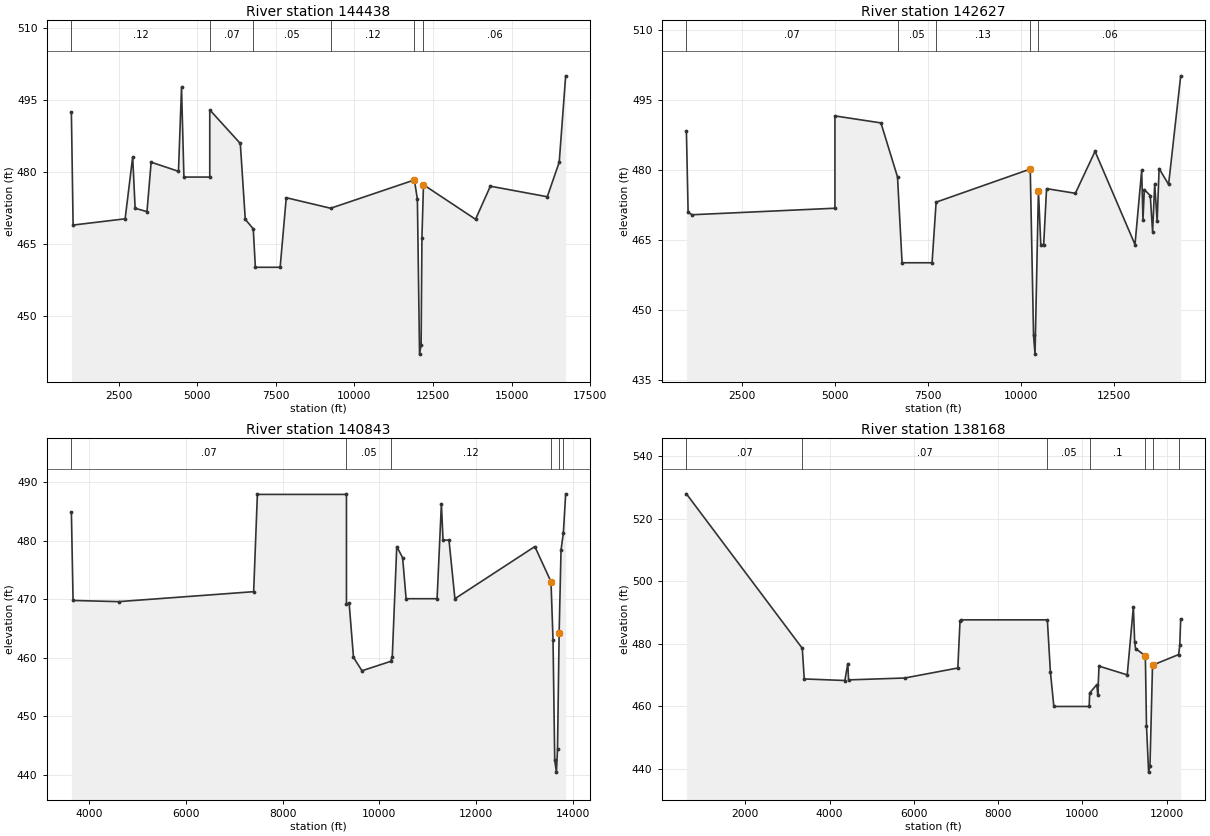
Type RM Length L Ch R = 1 ,144438  ,760,1810,760
BEGIN DESCRIPTION:
This cross section corresponds to cross section 144480 of the non-georeferenced CDC model which was the source of this model.
END DESCRIPTION:
XS GIS Cut Line= 5
   2382309.22295   6978250.58689   2381668.19011    6967894.5889
   2382944.88999   6966391.44886 2383077.2418921 6966142.4064883
2384525.465736686963417.32966443
#Sta/Elev= 30
    1000   492.4    1055   468.9    2709   470.2    2949   483.1    3027   472.4
    3404   471.7    3536     482    4405   480.1    4502   497.6    4578   478.9
    5400   478.9    5400   492.9    6371   485.9    6529   470.1    6783   468.1
    6850   460.1    7638   460.1    7832   474.6    9244   472.4   11906   478.3
   12001   474.3   12070     442   12120     444   12146   466.3   12195   477.3
   13851   470.1   14321     477   16131   474.8   16511     482   16716     500
#Mann= 6 ,-1,0
    1000     .12       0    5400     .07       0    6783     .05       0
    9244     .12       0   11906     .05       0   12195     .06       0
Bank Sta=11906,12195
XS Rating Curve= 0 ,0
Exp/Cntr=0.3,0.1

Type RM Length L Ch R = 1 ,142627  ,900,1784,1350
BEGIN DESCRIPTION:
This cross section corresponds to cross section 142669 of the non-georeferenced CDC model which was the source of this model.
-----------------------------------
CDC FW070799-01 Links at Waterchase
Cross-section 142669 - 144480
Located in ROB.
-----------------------------------
END DESCRIPTION:
XS GIS Cut Line= 5
   2382949.30894      6978204.69   2382551.17916   6969520.17915
   2382718.62994   6967983.55887 2383671.0259506 6966566.1621826
2384426.740487416965441.47532002
#Sta/Elev= 30
    1003   488.3    1049   470.9    1157   470.4    5000   471.8    5000   491.6
    6238   490.1    6684   478.5    6807   460.1    7614   460.1    7723   473.1
   10256   480.2   10345   444.5   10385   440.5   10476   475.6   10540     464
   10618     464   10695     476   11470     475   12000     484   13075     464
   13255   479.9   13290   469.3   13326   475.8   13486   474.5   13549   466.7
   13605     477   13671     469   13724   480.3   13979   476.9   14305   500.2
#Mann= 5 ,-1,0
    1003     .07       0    6684     .05       0    7723     .13       0
   10256    .055       0   10476     .06       0
Bank Sta=10256,10476
XS Rating Curve= 0 ,0
Exp/Cntr=0.3,0.1

Type RM Length L Ch R = 1 ,140843  ,1159,2676,2399
BEGIN DESCRIPTION:
This cross section corresponds to cross section 140885 of the non-georeferenced CDC model which was the source of this model.
---------------------------------
CDC FW121505-1 Bell Station Tract
This project is located between cross-sections 140885 - 147512 and within ineffective flow area, therefore the model was not changed.
---------------------------------
END DESCRIPTION:
XS GIS Cut Line= 4
  2383586.541063 6978179.0099156  2383585.266537 6978041.0158013
   2383497.76388   6968567.02686 2383987.5257072 6968224.5835066
#Sta/Elev= 30
    3638   484.9    3673   469.8    4615   469.6    7403   471.3    7480   487.9
    9320   487.9    9320   469.2    9376   469.3    9465   460.1    9640   457.8
   10231   459.4   10266   460.1   10359     479   10480   477.1   10552   470.1
   11192   470.1   11281   486.3   11315   480.1   11438   480.1   11560   470.1
   13211     479   13545     473   13587     463   13622   442.5   13657   440.5
   13680   444.5   13713   464.2   13752   478.4   13800   481.3   13848     488
#Mann= 6 ,-1,0
    3638     .07       0    9320     .05       0   10231     .12       0
   13545    .055       0   13713     .12       0   13800     .03       0
Bank Sta=13545,13713
XS Rating Curve= 0 ,0
Exp/Cntr=0.3,0.1

Type RM Length L Ch R = 1 ,138168  ,580,1278,800
BEGIN DESCRIPTION:
This cross section corresponds to cross section 138208 of the non-georeferenced CDC model which was the source of this model.
END DESCRIPTION:
XS GIS Cut Line= 5
2384648.456770356980829.01652966  2384640.097359 6978079.0292351
 2384637.8479174  6977339.032654   2384616.20915   6970220.55013
 2385065.8238786 6969190.9559315
#Sta/Elev= 30
     602     528    3352   478.6    3399   468.8    4363   468.3    4433   473.7
    4450   468.5    5785   469.1    7044   472.3    7096   487.3    7116   487.7
    9169   487.7    9241   471.1    9323     460   10162     460   10173   464.3
   10344     467   10366   463.6   10395   472.9   11065   470.1   11211   491.9
   11241   480.6   11263   478.5   11495   476.2   11522   453.9   11572     439
   11605     441   11665   473.2   12285   476.6   12312   479.6   12334     488
#Mann= 7 ,-1,0
     602     .07       0    3352     .07       0    9169     .05       0
   10173      .1       0   11495     .05       0   11665     .08       0
   12285     .03       0
Bank Sta=11495,11665
XS Rating Curve= 0 ,0
Exp/Cntr=0.3,0.1