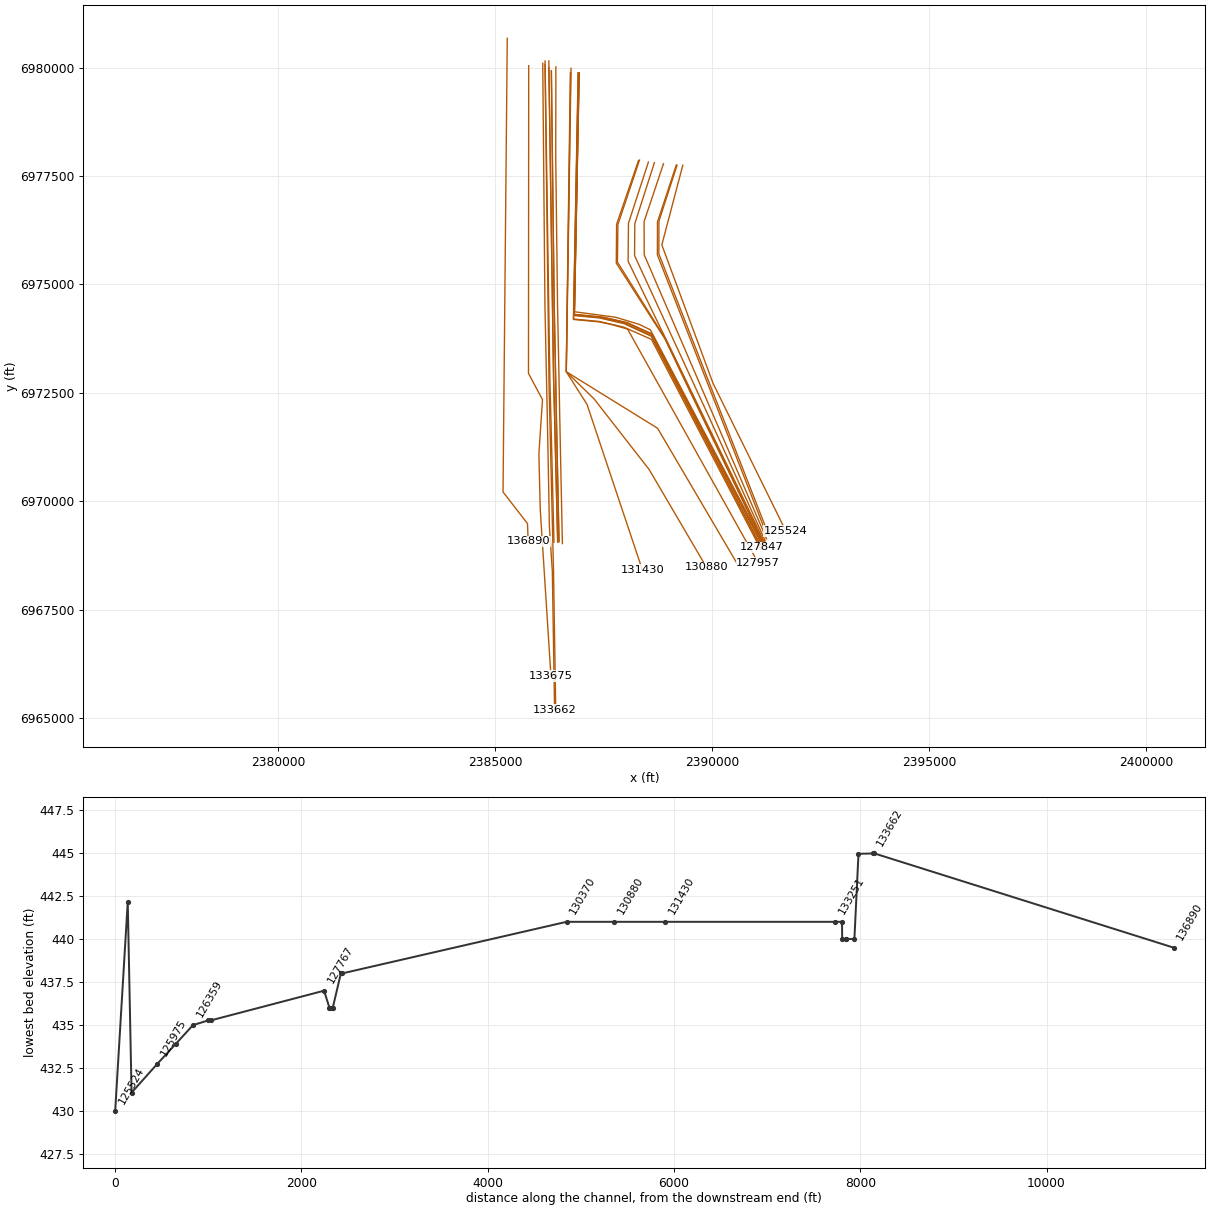
HEC-RAS study CDC_Consolidated_Model.prj: Upper Trinity CDC Consolidated Model

--- CDC_Consolidated_Model.g04 (geometry) --- (continued)

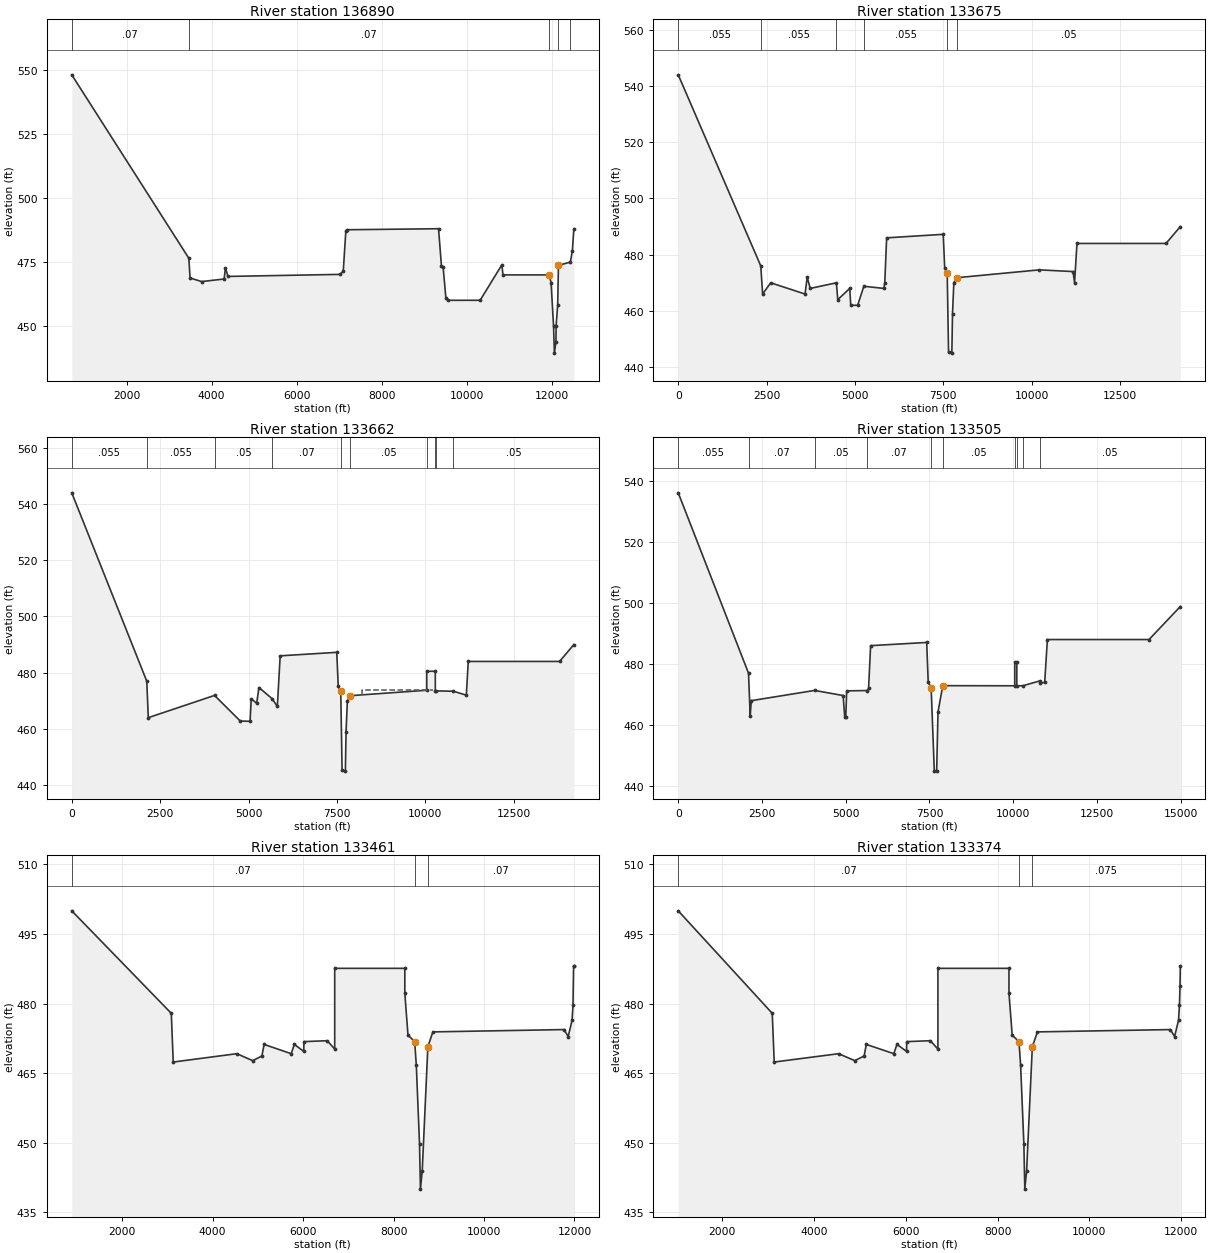
Type RM Length L Ch R = 1 ,136890  ,822,3214,163
BEGIN DESCRIPTION:
This cross section corresponds to cross section 136930 of the non-georeferenced CDC model which was the source of this model.
---------------------------------
CDC FW020400-01 Lakeview Addition
Cross-sections 136930 - 138208
---------------------------------
Project located in LOB outside of effective flow limits, therefore not included in model.
END DESCRIPTION:
XS GIS Cut Line= 6
2385275.657724186980676.42565839    2385250.0178 6977926.5451893
 2385249.1693516 6977835.5491447   2385178.10894      6970214.33
   2385741.97002   6969485.02896 2385756.7620401 6969072.7010796
#Sta/Elev= 30
     713     548    3463   476.5    3493   468.8    3765   467.4    4293   468.4
    4324   472.8    4382   469.4    7016   470.2    7092   471.4    7153   487.2
    7177   487.6    9331     488    9400   473.3    9439   472.9    9503   461.1
    9544   460.1   10308   460.1   10818   473.9   10845     470   11932     470
   11975     467   12033   450.1   12053   439.5   12090     444   12093   450.1
   12130   458.2   12148   473.7   12428     475   12476   479.5   12510     488
#Mann= 5 ,-1,0
     713     .07       0    3463     .07       0   11932    .055       0
   12148    .075       0   12428     .03       0
Bank Sta=11932,12148
XS Rating Curve= 0 ,0
Exp/Cntr=0.3,0.1

Type RM Length L Ch R = 1 ,133675  ,13,13,51
BEGIN DESCRIPTION:
This cross section corresponds to cross section 133780 of the non-georeferenced CDC model which was the source of this model.
END DESCRIPTION:
XS GIS Cut Line= 6
2385769.793706786980045.92876009     2385764.762     6972948.171
     2386087.679     6972344.004     2386004.346     6971094.004
     2386035.596     6969812.754 2386281.8520441 6965971.1535652
#Sta/Elev= 30
    .415     5442334.997     4762386.968     4662616.108     4703586.739     466
3647.913     4723733.838     4684474.462     4704511.788     4644851.551     468
4880.327     462 5074.39     462    5250 468.7645814.548     4685841.647     470
5895.139     486 7495.41 487.245 7537.46  475.13 7607.93 473.446 7645.97 445.307
 7739.03 444.973 7757.61  458.89 7795.31 469.982 7883.29 471.817 10210.8   474.6
 11167.2     47411209.74     470 11278.1     48413796.99     48414200.95     490
#Mann= 6 ,-1,0
    .415    .055       02334.997    .055       04474.462     .07       0
    5250    .055       0 7607.93     .05       0 7883.29     .05       0
Bank Sta=7607.93,7883.29
XS Rating Curve= 0 ,0
Exp/Cntr=0.3,0.1

Type RM Length L Ch R = 1 ,133662  ,150,157,245
BEGIN DESCRIPTION:
This cross section corresponds to cross section 133770 of the non-georeferenced CDC model which was the source of this model.
----------------------------------------------------
CDC FW121713-1 Revised West Village Creek Quicksilver Pad Site. Cross-section 133537 - 133770.  Modification of CDC FW022811-1
LOMR 17-06-2291P
END DESCRIPTION:
XS GIS Cut Line= 6
  2386093.242911 6980100.0657095 2386143.5895918 6974532.8513565
 2386214.9862062 6971139.0165475 2386246.2321702 6969415.2808641
 2386313.9411517 6968384.0209919  2386365.507642 6965190.8051483
#Sta/Elev= 30
     .41     544 2121.03     477 2165.14     464  4038.3  471.91 4765.89   462.8
 5043.55   462.7 5076.88   470.7 5230.58  469.12  5293.6  474.72 5666.69  470.76
 5814.55     468 5895.14     486 7495.41  487.24 7537.46  475.13 7607.93  473.45
 7645.97  445.31 7739.03  444.97 7757.61  458.89 7795.31  469.98 7883.29  471.82
10040.44  473.7510040.45   480.510282.75   480.510282.76  473.56   10297  473.52
   10795   473.411159.66     47211214.69     48413796.99     48414200.95     490
#Mann= 10 ,-1,0
     .41    .055       0 2121.03    .055       0  4038.3     .05       0
 5666.69     .07       0 7607.93     .05       0 7883.29     .05       0
10040.44    .023       010282.76    .045       0   10297    .023       0
   10795     .05       0
#XS Ineff= 2 ,-1
    8210 10210.9  473.75    4300    5100     468
Permanent Ineff=
       T       T
Bank Sta=7607.93,7883.29
XS Rating Curve= 0 ,0
Exp/Cntr=0.3,0.1

Type RM Length L Ch R = 1 ,133505  ,261,44,24
BEGIN DESCRIPTION:
This cross section corresponds to cross section 133537 of the non-georeferenced CDC model which was the source of this model.
----------------------------------------------------
CDC FW121713-1 Revised West Village Creek Quicksilver Pad Site. Cross-section 133537 - 133770.  Modification of CDC FW022811-1
LOMR 17-06-2291P
END DESCRIPTION:
XS GIS Cut Line= 4
  2386145.723066 6980069.9637047  2386239.473066 6972601.4307186
 2386341.4695938  6968393.531413 2386393.5529271 6965107.9411353
#Sta/Elev= 30
     .35     536 2098.35     477 2148.92     463 2180.87     468  4069.8  471.35
 4923.96  469.68 4970.97  462.59 5002.53  462.77 5029.26   471.2 5639.77  471.32
 5682.87     472 5744.07     486 7417.95  487.05 7462.83  474.12 7551.79  472.05
 7645.48  444.97 7715.47  444.95 7756.01  464.27 7897.13  472.91 10048.5  472.87
10048.51   480.5 10108.5   480.510108.51  472.85   10293   472.9   10805  474.49
   10805   473.710941.07     47411021.15     48814055.12     48814989.83   498.8
#Mann= 10 ,-1,0
     .35    .055       0 2098.35     .07       0  4069.8     .05       0
 5639.77     .07       0 7551.79     .05       0 7897.13     .05       0
 10048.5    .023       010108.51    .045       0   10293    .023       0
   10805     .05       0
#XS Ineff= 1 ,-1
    4900    5050     468
Permanent Ineff=
       T
Bank Sta=7551.79,7897.13
XS Rating Curve= 0 ,0
Exp/Cntr=0.3,0.1

Type RM Length L Ch R = 1 ,133461  ,87,87,87
BEGIN DESCRIPTION:
This cross section corresponds to cross section 133499 of the non-georeferenced CDC model which was the source of this model.
END DESCRIPTION:
XS GIS Cut Line= 6
2386146.418972256980152.44936526   2386231.66688   6974492.05996
   2386256.92109   6972842.08393   2386282.17596   6971882.40311
   2386349.52196   6969146.47288 2386351.0024642 6969056.4576885
#Sta/Elev= 30
     888     500    3088   477.9    3131   467.4    4536   469.2    4886   467.7
    5091   468.7    5139   471.2    5738   469.2    5808   471.2    6016   469.7
    6020   471.8    6535     472    6700   470.2    6700   487.6    8250   487.6
    8250   482.2    8320   473.2    8468   471.8    8504   466.7    8575   449.7
    8595     440    8635     444    8759   470.7    8870   473.9   11770   474.4
   11861   472.9   11947   476.4   11967   479.6   11980     488   11986     488
#Mann= 3 ,0,0
     888     .07       0    8468     .05       0    8759     .07       0
Bank Sta=8468,8759
XS Rating Curve= 0 ,0
Exp/Cntr=0.3,0.1

Type RM Length L Ch R = 1 ,133374  ,1,1,1
BEGIN DESCRIPTION:
This cross section corresponds to cross section 133413 of the non-georeferenced CDC model which was the source of this model.
END DESCRIPTION:
XS GIS Cut Line= 6
 2386234.19991786980007.39418702 2386317.1890151 6974496.9877709
 2386342.4432297 6972847.0117402 2386367.6981004 6971887.3309167
 2386435.0440943 6969151.4006931 2386436.5245987 6969061.3855018
#Sta/Elev= 30
    1038     500    3088   477.9    3131   467.4    4536   469.2    4886   467.7
    5091   468.7    5139   471.2    5738   469.2    5808   471.2    6016   469.7
    6020   471.8    6535     472    6700   470.2    6700   487.6    8250   487.6
    8250   482.2    8320   473.2    8468   471.8    8504   466.7    8575   449.7
    8595     440    8635     444    8759   470.7    8870   473.9   11770   474.4
   11861   472.9   11947   476.4   11967   479.6   11980   483.8   11986     488
#Mann= 3 ,0,0
    1038     .07       0    8468    .055       0    8759    .075       0
Bank Sta=8468,8759
XS Rating Curve= 0 ,0
Exp/Cntr=0.3,0.1

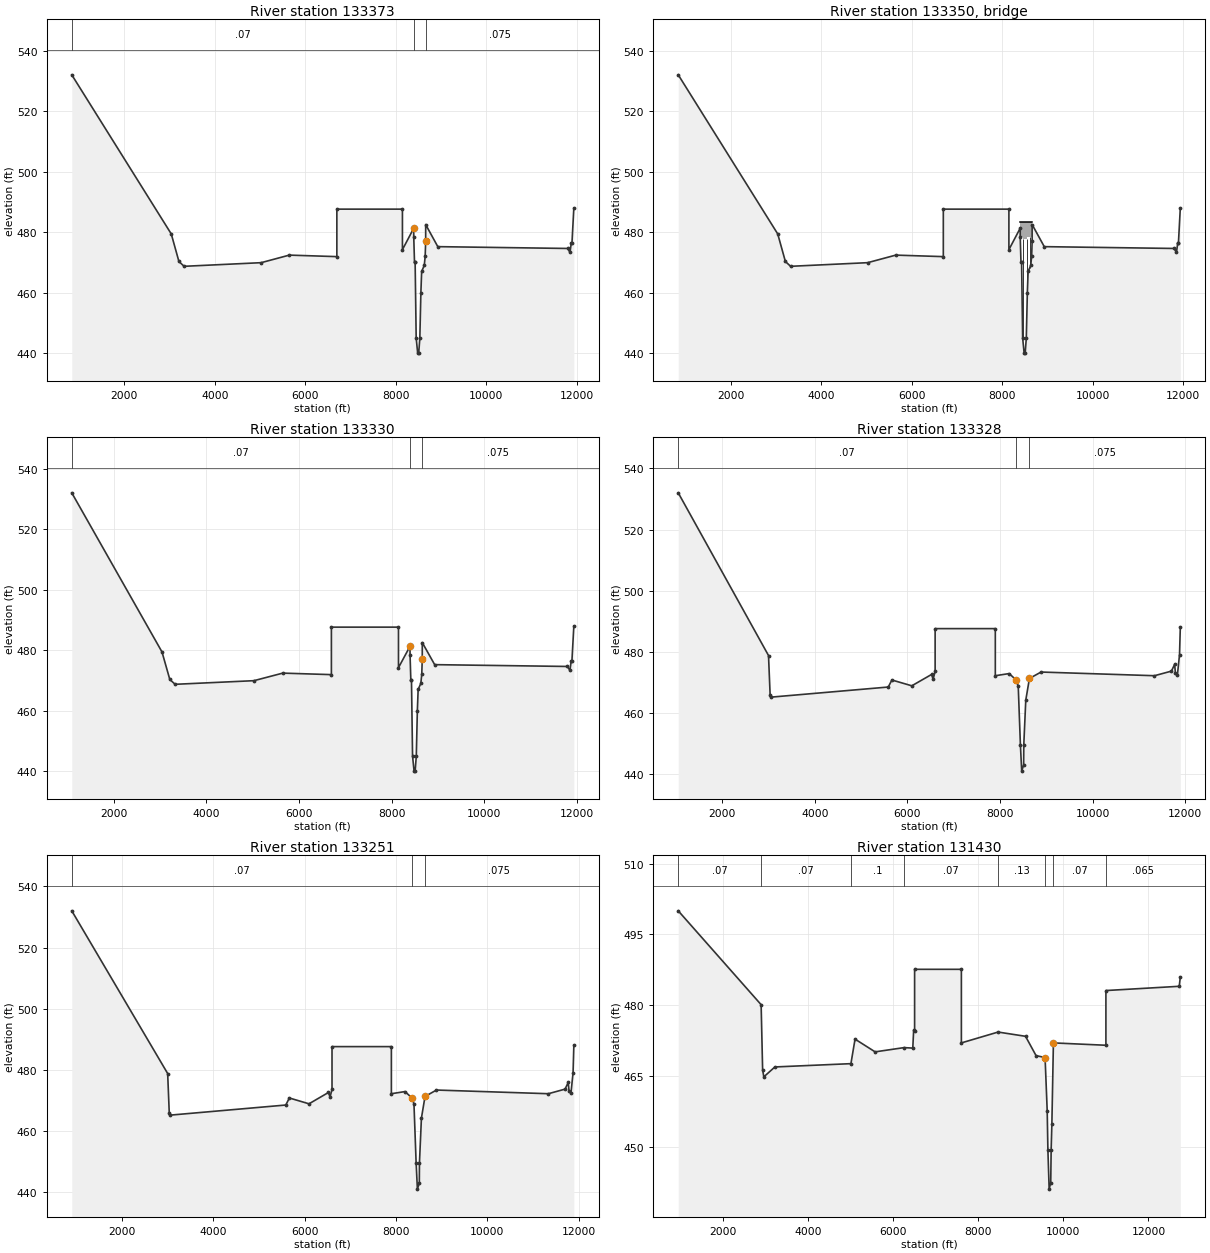
Type RM Length L Ch R = 1 ,133373  ,43,43,43
BEGIN DESCRIPTION:
This cross section corresponds to cross section 133412 of the non-georeferenced CDC model which was the source of this model.
END DESCRIPTION:
XS GIS Cut Line= 6
 2386232.96956946980154.93454859 2386318.1798267 6974497.0448574
 2386343.4340413 6972847.0688267 2386368.6889121 6971887.3880032
  2386436.034906 6969151.4577796 2386437.6058582  6969055.943332
#Sta/Elev= 30
     839     532    3039   479.4    3208   470.3    3323   468.7    5026   469.9
    5649   472.4    6700   471.9    6700   487.6    8150   487.6    8150   474.2
    8400   481.3    8400   478.5    8417     470    8431     470    8454     445
    8487     440    8510     440    8535     445    8558     460    8575     467
    8633     469    8653     472    8664     477    8664   482.5    8932   475.2
   11802   474.6   11855   473.3   11883   476.4   11898   476.3   11940     488
#Mann= 3 ,0,0
     839     .07       0    8400    .055       0    8664    .075       0
Bank Sta=8400,8664
XS Rating Curve= 0 ,0
Exp/Cntr=0.3,0.1

Type RM Length L Ch R = 3 ,133350  ,,,
BEGIN DESCRIPTION:
Arlington-Bedford Road
END DESCRIPTION:
Node Name=Arl. Bedford Roa
Bridge Culvert--1,0,-1,-1, 0
Deck Dist Width WeirC Skew NumUp NumDn MinLoCord MaxHiCord MaxSubmerge Is_Ogee
1,40,2.6,0, 11, 11, , , 0.95, 0, ,,,
    8400    8454    8454    8457    8487    8535    8555    8558    8558    8610
    8664
   483.3   483.3   483.3   483.3   483.3   483.3   483.3   483.3   483.3   483.3
   483.3
   478.5   478.5   477.6   477.6   477.6   477.6   477.6   477.6   478.5   478.5
   478.5
    8400    8454    8454    8457    8487    8535    8555    8558    8558    8610
    8664
   483.3   483.3   483.3   483.3   483.3   483.3   483.3   483.3   483.3   483.3
   483.3
   478.5   478.5   477.6   477.6   477.6   477.6   477.6   477.6   478.5   478.5
   478.5
Pier Skew, UpSta & Num, DnSta & Num=  ,8456.5, 2 ,8456.5, 2 , 0 , 0 , 0 ,,
       3       3
     440     480
       3       3
     440     480
Pier Skew, UpSta & Num, DnSta & Num=  ,8556.5, 2 ,8556.5, 2 , 0 , 0 , 0 ,,
       3       3
     440     480
       3       3
     440     480
Pier Skew, UpSta & Num, DnSta & Num=  ,8612.5, 2 ,8612.5, 2 , 0 , 0 , 0 ,,
       3       3
     440     480
       3       3
     440     480
BR Coef= 1 , 0 , 0 ,1.05, 0 ,,,0.8,-1,0.5,1,
WSPro=,,,, 1 ,,,, 0 ,,,, 0 ,,,,-1 ,-1 ,-1 , 0 , 0 , 0 , 0 , 0
BC Design=,, 0 ,, 0 ,,,,,,
BC HTab HWMax=488
BC Use User HTab Curves=0
BC User HTab FreeFlow(D)= 0

Type RM Length L Ch R = 1 ,133330  ,2,2,2
BEGIN DESCRIPTION:
This cross section corresponds to cross section 133370 of the non-georeferenced CDC model which was the source of this model.
END DESCRIPTION:
XS GIS Cut Line= 6
2386290.552566956979930.75752952 2386321.7441241 6977273.9897628
 2386355.4159727 6974529.6409208 2386389.0891337 6972845.9907448
 2386405.9260423 6971962.0748617 2386466.3023447  6969081.276845
#Sta/Elev= 30
    1089     532    3039   479.4    3208   470.3    3323   468.7    5026   469.9
    5649   472.4    6700   471.9    6700   487.6    8150   487.6    8150   474.2
    8400   481.3    8400   478.5    8417     470    8431     470    8454     445
    8487     440    8510     440    8535     445    8558     460    8575     467
    8633     469    8653     472    8664     477    8664   482.5    8932   475.2
   11802   474.6   11855   473.3   11883   476.4   11898   476.3   11940     488
#Mann= 3 ,0,0
    1089     .07       0    8400    .055       0    8664    .075       0
Bank Sta=8400,8664
XS Rating Curve= 0 ,0
Exp/Cntr=0.3,0.1

Type RM Length L Ch R = 1 ,133328  ,76,76,76
BEGIN DESCRIPTION:
This cross section corresponds to cross section 133369 of the non-georeferenced CDC model which was the source of this model.
END DESCRIPTION:
XS GIS Cut Line= 6
     2386292.894     6979908.412     2386323.827     6977273.643
     2386357.499     6974529.294     2386391.172     6972845.644
     2386408.009     6971961.728     2386468.556      6969064.93
#Sta/Elev= 30
    1051     532    3001   478.8    3036   465.9    3060   465.2    5588   468.5
    5666   470.8    6096   468.9    6522   472.6    6557   471.1    6600   473.6
    6600   487.6    7900   487.6    7900   472.2    8199   472.9    8351   470.8
    8395   468.8    8442   449.6    8470     441    8512     443    8515   449.6
    8558   464.2    8637   471.3    8888   473.4   11338   472.2   11704   473.7
   11773   475.9   11790   473.2   11833   472.4   11879   479.1   11896     488
#Mann= 3 ,0,0
    1051     .07       0    8351    .055       0    8637    .075       0
Bank Sta=8351,8637
XS Rating Curve= 0 ,0
Exp/Cntr=0.3,0.1

Type RM Length L Ch R = 1 ,133251  ,250,1822,1239
BEGIN DESCRIPTION:
This cross section corresponds to cross section 133290 of the non-georeferenced CDC model which was the source of this model.
END DESCRIPTION:
XS GIS Cut Line= 6
      2386395.58        6980019.   2386392.53101  6977917.407739
   2386433.70387   6974534.15207   2386467.37703   6972850.50189
   2386484.21394   6971966.58601 2386545.6356243 6969023.7965306
#Sta/Elev= 30
     901     532    3001   478.8    3036   465.9    3060   465.2    5588   468.5
    5666   470.8    6096   468.9    6522   472.6    6557   471.1    6600   473.6
    6600   487.6    7900   487.6    7900   472.2    8199   472.9    8351   470.8
    8395   468.8    8442   449.6    8470     441    8512     443    8515   449.6
    8558   464.2    8637   471.3    8888   473.4   11338   472.2   11704   473.7
   11773   475.9   11790   473.2   11833   472.4   11879   479.1   11896     488
#Mann= 3 ,0,0
     901     .07       0    8351    .055       0    8637    .075       0
Bank Sta=8351,8637
XS Rating Curve= 0 ,0
Exp/Cntr=0.3,0.1

Type RM Length L Ch R = 1 ,131430  ,1,549,721
BEGIN DESCRIPTION:
This cross section corresponds to cross section 131467 of the non-georeferenced CDC model which was the source of this model.
CDC ARL021511-1 GREENMAN GAS WELL SITE
LOCATED ADJACENT TO VILLAGE CREEK STP IN INEFFECTIVE FLOW AREA.  SITE LOCATED BETWEEN
CROSS-SECTION 131467 AND 133290.
----------------------------------------
CDC ARL071405-1 SVC Park Highlands, LTD.
In ROB beyond eff. flow line - storage mitigation area d/s SH 360 d/s cross-sect 78083.
----------------------------------------
END DESCRIPTION:
XS GIS Cut Line= 6
2386728.967360536979883.18641281      2386702.21      6977933.37
   2386634.33897   6972987.58889   2387112.96203   6972235.61303
 2388136.8534676 6969169.68392532388387.094605446968420.36465227
#Sta/Elev= 30
     940     500    2890   480.1    2925   466.3    2953   464.8    3213   466.9
    5002   467.6    5099   472.8    5571   470.1    6252     471    6457   470.9
    6478   474.7    6500   474.5    6500   487.6    7600   487.6    7600     472
    8464   474.3    9109   473.4    9357   469.3    9569   468.9    9619   457.6
    9635   449.4    9665     441    9702   442.4    9712   449.4    9729   454.9
    9765     472   11000   471.5   11000   483.1   12725     484   12750     486
#Mann= 8 ,-1,0
     940     .07       0    2890     .07       0    5002      .1       0
    6252     .07       0    8464     .13       0    9569     .05       0
    9765     .07       0   11000    .065       0
#XS Ineff= 2 , 0
       0                   12725       0
Permanent Ineff=
       F       F
Bank Sta=9569,9765
XS Rating Curve= 0 ,0
Exp/Cntr=0.3,0.1

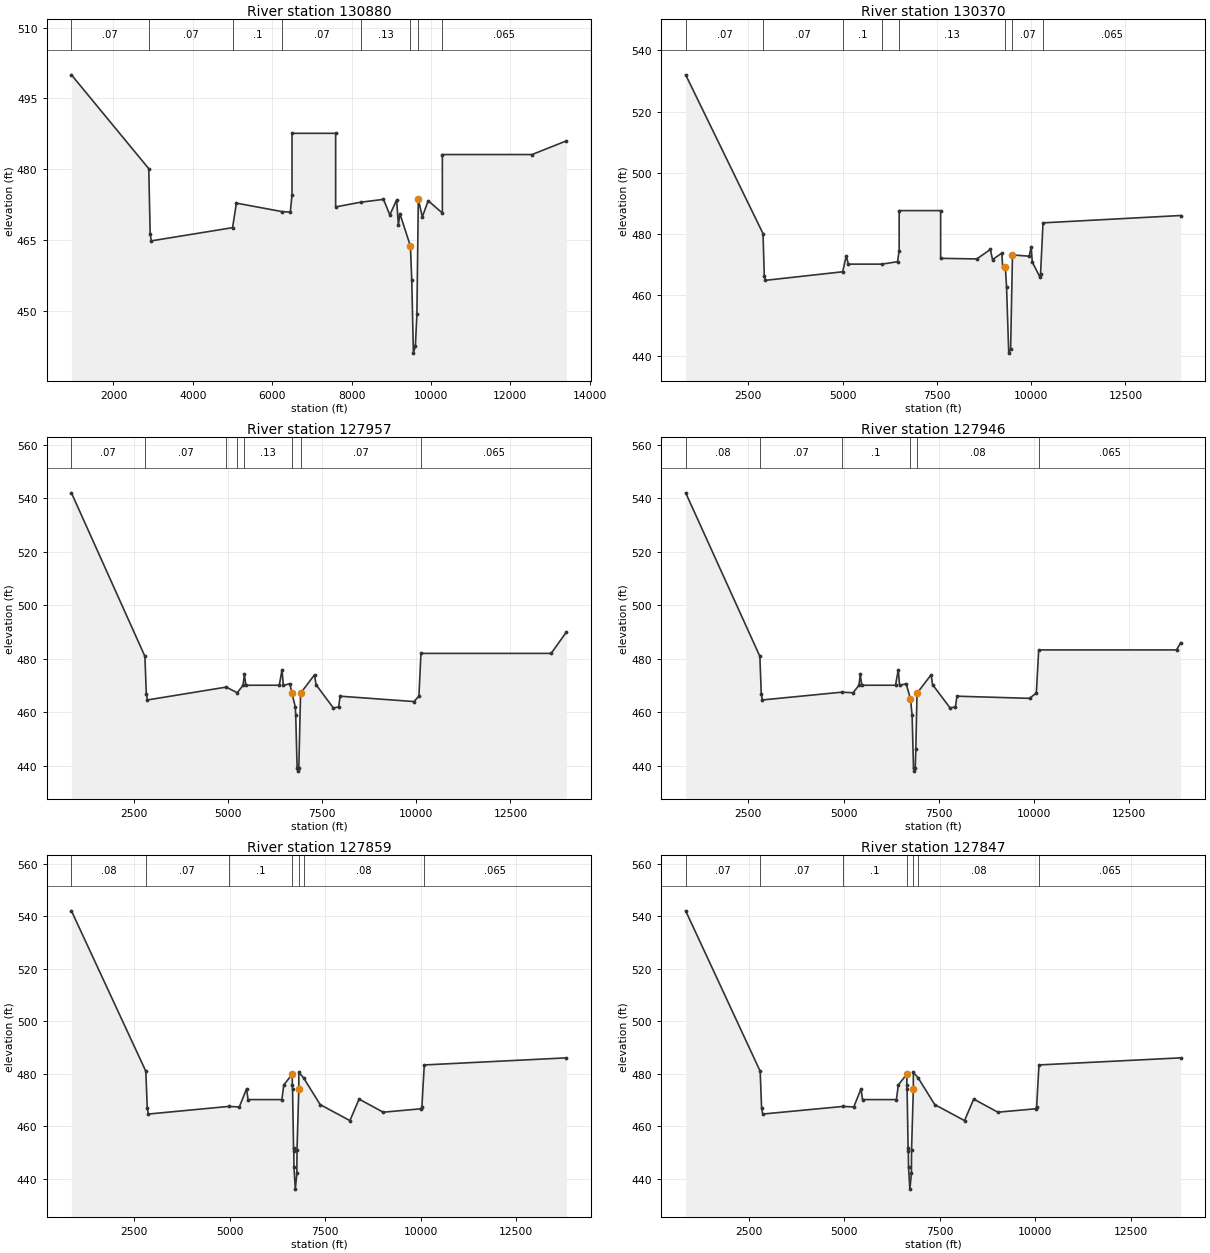
Type RM Length L Ch R = 1 ,130880  ,1,510,699
BEGIN DESCRIPTION:
This cross section corresponds to cross section 130918 of the non-georeferenced CDC model which was the source of this model.
END DESCRIPTION:
XS GIS Cut Line= 6
2386737.563770176979884.22088967      2386634.99      6972987.54
   2387277.15396   6972359.02584    2388545.9339   6970729.97595
   2389430.32091   6969220.875952389868.684603556968472.86106233
#Sta/Elev= 30
     940     500    2890   480.1    2925   466.3    2953   464.8    5002   467.6
    5099   472.8    6252     471    6457   470.9    6500   474.5    6500   487.6
    7600   487.6    7600     472    8235     473    8806   473.6    8966   470.3
    9138   473.5    9182   468.1    9218   470.6    9485   463.7    9519   456.4
    9560     441    9610   442.5    9648   449.2    9684   473.6    9785   469.9
    9934   473.3   10290   470.7   10290   483.1   12550   483.1   13417     486
#Mann= 8 ,-1,0
     940     .07       0    2890     .07       0    5002      .1       0
    6252     .07       0    8235     .13       0    9485     .05       0
    9684     .07       0   10290    .065       0
#XS Ineff= 2 , 0
       0                   12550       0
Permanent Ineff=
       F       F
Bank Sta=9485,9684
XS Rating Curve= 0 ,0
Exp/Cntr=0.3,0.1

Type RM Length L Ch R = 1 ,130370  ,170,2413,1045
BEGIN DESCRIPTION:
This cross section corresponds to cross section 130407 of the non-georeferenced CDC model which was the source of this model.
END DESCRIPTION:
XS GIS Cut Line= 6
2386745.252862386979985.05101815  2386713.211418 6977935.3014369
      2386635.87      6972987.63    2388739.7511   6971682.79392
   2390208.02999   6969181.893092390587.243143516968535.98413031
#Sta/Elev= 30
     840     532    2890   480.1    2925   466.3    2953   464.8    5002   467.6
    5099   472.8    5153   470.1    6047   470.1    6457   470.9    6500   474.5
    6500   487.6    7600   487.6    7600     472    8558   471.8    8918   474.9
    8975   471.6    9223   473.7    9245     469    9315   469.3    9347   462.7
    9405     441    9455   442.5    9504   473.1    9949   472.7   10000   475.8
   10029   470.8   10226     466   10249     467   10314   483.6   13963     486
#Mann= 8 ,-1,0
     840     .07       0    2890     .07       0    5002      .1       0
    6047     .07       0    6500     .13       0    9315    .055       0
    9504     .07       0   10314    .065       0
#XS Ineff= 2 , 0
       0                   13214       0
Permanent Ineff=
       F       F
Bank Sta=9315,9504
XS Rating Curve= 0 ,0
Exp/Cntr=0.3,0.1

Type RM Length L Ch R = 1 ,127957  ,11,11,384
BEGIN DESCRIPTION:
This cross section corresponds to cross section 127999 of the non-georeferenced CDC model which was the source of this model.
END DESCRIPTION:
XS GIS Cut Line= 6
2386908.972737256979877.95741094   2386799.79894   6974193.06089
   2387388.91489   6974137.69387   2387682.10492   6974075.23107
      2388048.19      6973970.41 2391057.2090427 6968578.4097208
#Sta/Elev= 30
     852     542    2802   480.9    2839   466.9    2869   464.6    4958   469.4
    5252   467.3    5407   470.1    5441   474.2    5481   470.1    6367   470.1
    6440   475.9    6474     470    6647   470.7    6702   467.2    6790   462.1
    6803     459    6840     439    6860     438    6885     439    6932   467.1
    7302     474    7342   470.3    7802   461.6    7942     462    7982     466
    9940     464   10071     466   10126     482 13580.5     482   13985     490
#Mann= 8 ,-1,0
     852     .07       0    2802     .07       0    4958      .1       0
    5252     .07       0    5441     .13       0    6702    .055       0
    6932     .07       0   10126    .065       0
Bank Sta=6702,6932
XS Rating Curve= 0 ,0
Exp/Cntr=0.3,0.1

Type RM Length L Ch R = 1 ,127946  ,1,87,87
BEGIN DESCRIPTION:
This cross section corresponds to cross section 127989 of the non-georeferenced CDC model which was the source of this model.
END DESCRIPTION:
XS GIS Cut Line= 6
2386912.371899496979877.78530247 2386803.0685215  6974202.068684
 2387392.1844715  6974146.701664 2387957.8024315  6974016.957834
 2388597.7926215  6973733.1178442391117.582931756968891.08217855
#Sta/Elev= 30
     852     542    2802   480.9    2839   466.9    2869   464.6    4950   467.5
    5252   467.3    5407   470.1    5441   474.2    5481   470.1    6367   470.1
    6440   475.9    6474     470    6647   470.7    6760   464.9    6803     459
    6840     439    6860     438    6885     439    6901   446.3    6932   467.1
    7302     474    7342   470.3    7802   461.6    7942     462    7982     466
    9890   465.2   10068   467.2   10130   483.3   13752   483.3   13861     486
#Mann= 6 ,-1,0
     852     .08       0    2802     .07       0    4950      .1       0
    6760     .05       0    6932     .08       0   10130    .065       0
#XS Ineff= 2 , 0
       0                   13752       0
Permanent Ineff=
       F       F
Bank Sta=6760,6932
XS Rating Curve= 0 ,0
Exp/Cntr=0.3,0.1

Type RM Length L Ch R = 1 ,127859  ,12,12,12
BEGIN DESCRIPTION:
This cross section corresponds to cross section 127889 of the non-georeferenced CDC model which was the source of this model.
END DESCRIPTION:
XS GIS Cut Line= 6
2386915.380638786979877.47995426 2386808.3232034 6974283.3612296
 2387397.4391512 6974227.9942144 2387963.0571144 6974098.2503794
      2388593.48      6973807.732391132.398256476968920.98900988
#Sta/Elev= 30
     852     542    2802   480.9    2839   466.9    2869   464.6    4970   467.5
    5252   467.3    5441   474.2    5481   470.1    6367   470.1    6417   475.7
    6640   479.8    6640   475.5    6647     474    6673   451.5    6680   450.5
  6683.5   444.5    6719     436    6760     442  6763.5     451    6810     474
    6810   480.5    6935   478.4    7370   468.2    8150   462.1    8390   470.3
    9022   465.3   10011   466.6   10036   467.2   10098   483.3   13823     486
#Mann= 7 ,-1,0
     852     .08       0    2802     .07       0    4970      .1       0
    6640    .055       0    6810     .13       0    6935     .08       0
   10098    .065       0
#XS Ineff= 2 , 0
       0                   13720       0
Permanent Ineff=
       F       F
Bank Sta=6640,6810
XS Rating Curve= 0 ,0
Exp/Cntr=0.3,0.1

Type RM Length L Ch R = 1 ,127847  ,1,14,14
BEGIN DESCRIPTION:
This cross section corresponds to cross section 127888 of the non-georeferenced CDC model which was the source of this model.
END DESCRIPTION:
XS GIS Cut Line= 6
2386925.189568136979877.72399945 2386818.9094683 6974293.7191486
 2387408.0254161 6974238.3521333 2387973.6433793 6974108.6082983
      2388600.73      6973817.032391137.621004666968934.45215315
#Sta/Elev= 30
     852     542    2802   480.9    2839   466.9    2869   464.6    4970   467.5
    5252   467.3    5441   474.2    5481   470.1    6367   470.1    6417   475.7
    6640   479.8    6640   475.5    6647     474    6673   451.5    6680   450.5
  6683.5   444.5    6719     436    6760     442  6763.5     451    6810     474
    6810   480.5    6935   478.4    7370   468.2    8150   462.1    8390   470.3
    9022   465.3   10011   466.6   10036   467.2   10098   483.3   13806     486
#Mann= 7 ,-1,0
     852     .07       0    2802     .07       0    4970      .1       0
    6640    .055       0    6810     .13       0    6935     .08       0
   10098    .065       0
#XS Ineff= 2 , 0
       0                   13720       0
Permanent Ineff=
       F       F
Bank Sta=6640,6810
XS Rating Curve= 0 ,0
Exp/Cntr=0.3,0.1

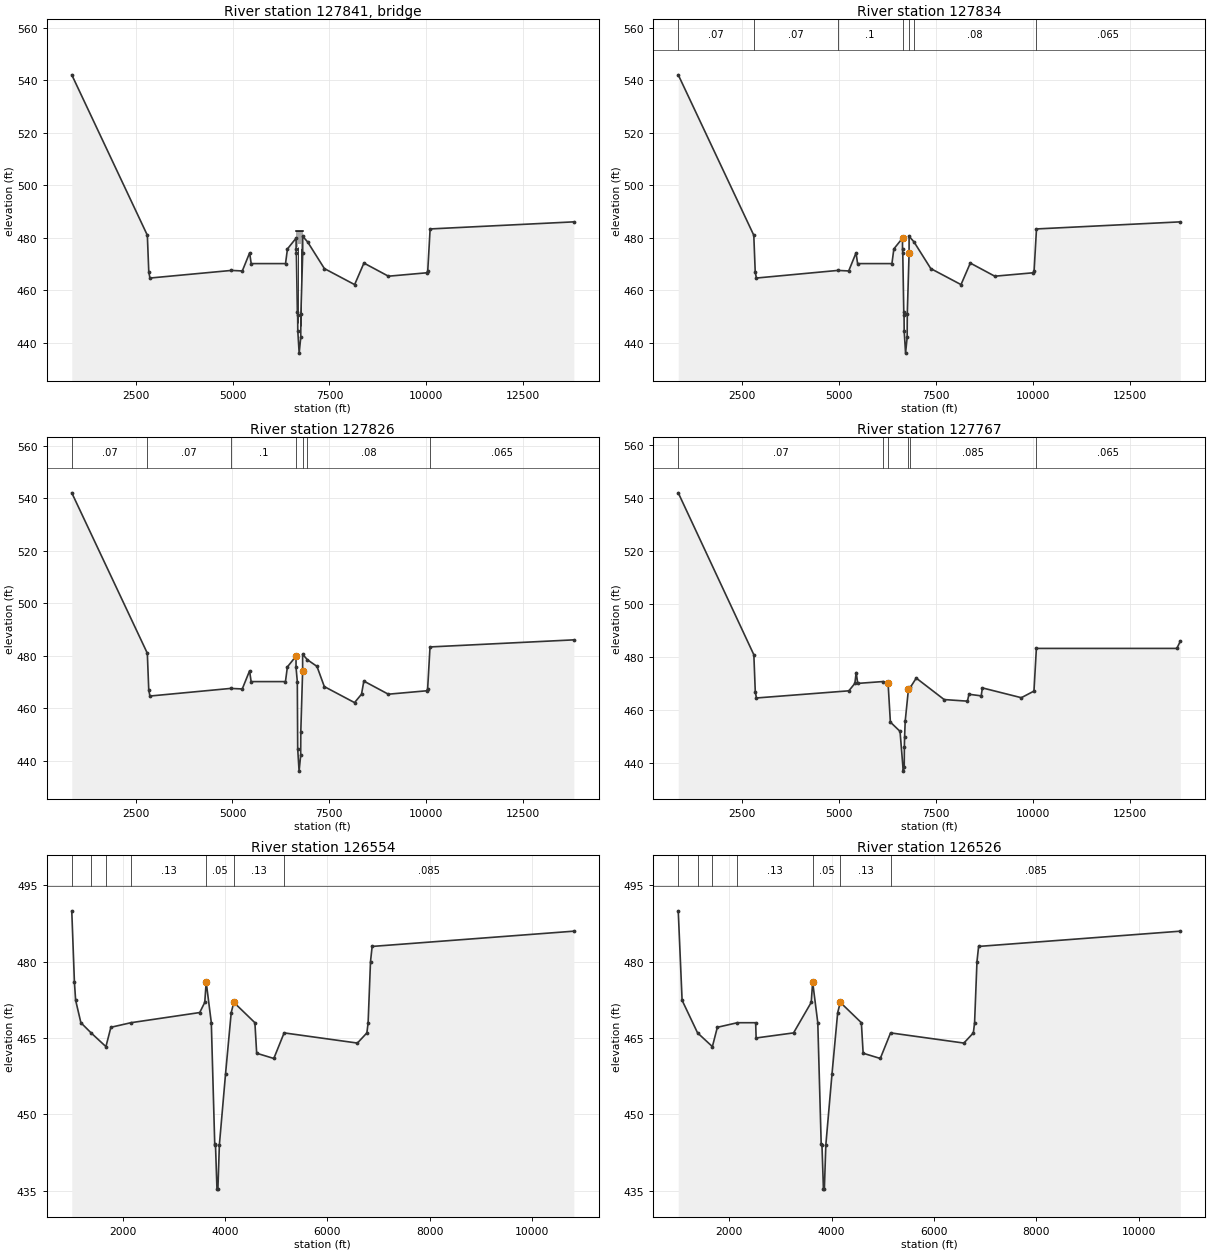
Type RM Length L Ch R = 3 ,127841  ,,,
BEGIN DESCRIPTION:
Trammel-Davis Road
END DESCRIPTION:
Node Name=Trammel-Davis Ro
Bridge Culvert--1,0,-1,-1, 0
Deck Dist Width WeirC Skew NumUp NumDn MinLoCord MaxHiCord MaxSubmerge Is_Ogee
0.5,13,2.6,0, 8, 8, , , 0.95, 0, ,,,
    6640    6680  6683.5  6683.5    6760    6760  6763.5    6810
   482.7   482.7   482.7   482.7   482.7   482.7   482.7   482.7
   476.4   476.4   476.4   477.5   477.5   476.1   476.1   476.1
    6640    6680  6683.5  6683.5    6760    6760  6763.5    6810
   482.7   482.7   482.7   482.7   482.7   482.7   482.7   482.7
   476.4   476.4   476.4   477.5   477.5   476.1   476.1   476.1
Pier Skew, UpSta & Num, DnSta & Num=  ,6681.75, 2 ,6681.75, 2 , 0 , 0 , 0 ,,
     3.5     3.5
     440     480
     3.5     3.5
     440     480
Pier Skew, UpSta & Num, DnSta & Num=  ,6761.75, 2 ,6761.75, 2 , 0 , 0 , 0 ,,
     3.5     3.5
     440     480
     3.5     3.5
     440     480
BR Coef= 1 , 0 , 0 ,1.05, 0 ,,,0.8,-1,0.5,1,
WSPro=,,,, 1 ,,,, 0 ,,,, 0 ,,,,-1 ,-1 ,-1 , 0 , 0 , 0 , 0 , 0
BC Design=,, 0 ,, 0 ,,,,,,
BC HTab HWMax=483.3
BC Use User HTab Curves=0
BC User HTab FreeFlow(D)= 0

Type RM Length L Ch R = 1 ,127834  ,9,9,9
BEGIN DESCRIPTION:
This cross section corresponds to cross section 127873 of the non-georeferenced CDC model which was the source of this model.
END DESCRIPTION:
XS GIS Cut Line= 6
2386929.299360276979877.70600843      2386820.11      6974303.42
  2387483.115489 6974238.5142065 2388039.0025006 6974110.8425458
       2388605.3      6973847.922391163.201214666968959.24545689
#Sta/Elev= 30
     852     542    2802   480.9    2839   466.9    2869   464.6    4970   467.5
    5252   467.3    5441   474.2    5481   470.1    6367   470.1    6417   475.7
    6640   479.8    6640   475.5    6647     474    6673   451.5    6680   450.5
  6683.5   444.5    6719     436    6760     442  6763.5     451    6810     474
    6810   480.5    6935   478.4    7370   468.2    8150   462.1    8390   470.3
    9022   465.3   10011   466.6   10036   467.2   10098   483.3   13810     486
#Mann= 7 ,-1,0
     852     .07       0    2802     .07       0    4970      .1       0
    6640    .055       0    6810     .13       0    6935     .08       0
   10098    .065       0
#XS Ineff= 2 , 0
       0                   13720       0
Permanent Ineff=
       F       F
Bank Sta=6640,6810
XS Rating Curve= 0 ,0
Exp/Cntr=0.3,0.1

Type RM Length L Ch R = 1 ,127826  ,1,58,58
BEGIN DESCRIPTION:
This cross section corresponds to cross section 127872 of the non-georeferenced CDC model which was the source of this model.
END DESCRIPTION:
XS GIS Cut Line= 6
2386932.10906372 6979877.4587316      2386822.04      6974312.16
 2387484.9901572 6974247.1218008 2388040.8771687 6974119.4501402
      2388609.57      6973861.052391175.968853386968965.81475918
#Sta/Elev= 30
     852     542    2802   480.9    2839   466.9    2869   464.6    4950   467.5
    5252   467.3    5441   474.2    5481   470.1    6367   470.1    6417   475.7
    6640   479.8    6640   475.5    6673   470.1    6683   444.5    6719     436
    6760     442    6763     451    6810     474    6810   480.5    6935   478.4
    7180   475.9    7370   468.2    8150   462.1    8330   465.3    8390   470.3
    9022   465.3   10011   466.6   10036   467.2   10098   483.3   13810     486
#Mann= 7 ,-1,0
     852     .07       0    2802     .07       0    4950      .1       0
    6640     .05       0    6810     .13       0    6935     .08       0
   10098    .065       0
#XS Ineff= 2 , 0
       0                   13720       0
Permanent Ineff=
       F       F
Bank Sta=6640,6810
XS Rating Curve= 0 ,0
Exp/Cntr=0.3,0.1

Type RM Length L Ch R = 1 ,127767  ,1017,1213,31
BEGIN DESCRIPTION:
This cross section corresponds to cross section 127781 of the non-georeferenced CDC model which was the source of this model.
END DESCRIPTION:
XS GIS Cut Line= 6
2386931.618928986979877.45992418  2386824.310376 6974370.2773944
 2387769.0867018 6974245.0112407 2388318.2667058 6974078.9124916
 2388571.9568152 6973954.1630691 2391195.19937176968974.98647491
#Sta/Elev= 30
     852     542    2802   480.9    2839   466.9    2869   464.6    5252   467.3
    5407   470.1    5441   474.2    5481   470.1    6135   470.8    6264   470.1
    6323   455.5    6572     452    6655     437    6680   438.5    6684   446.1
    6689   449.7    6705   455.8    6790   468.1    6838   468.6    6990   472.1
    7710     464    8310   463.4    8350     466    8665   465.4    8696   468.4
    9700   464.7   10026   467.2   10088   483.3   13710   483.3   13800     486
#Mann= 6 ,-1,0
     852     .07       0    6135     .13       0    6264     .05       0
    6790     .13       0    6838    .085       0   10088    .065       0
#XS Ineff= 2 , 0
       0                   13710       0
Permanent Ineff=
       F       F
Bank Sta=6264,6790
XS Rating Curve= 0 ,0
Exp/Cntr=0.3,0.1

Type RM Length L Ch R = 1 ,126554  ,28,28,28
BEGIN DESCRIPTION:
This cross section corresponds to cross section 126600 of the non-georeferenced CDC model which was the source of this model.
END DESCRIPTION:
XS GIS Cut Line= 6
  2388299.036303 6977858.0265513 2387794.7766111 6976387.3957355
 2387787.2940145 6975492.7790864 2388906.0437455 6973749.0292931
      2389487.45      6972528.08      2391201.25      6968972.53
#Sta/Elev= 30
    1000     490 1051.69     476 1075.57  472.41 1178.35     468 1378.09     466
 1667.97   463.3 1764.61   467.1 2155.82     468 3501.74     470  3600.6     472
 3628.33     476 3728.64     468 3795.53  444.11 3810.14     444  3839.2  435.28
  3857.2  435.28 3886.29     444 4007.36     458 4117.83     470 4169.13     472
 4580.92     468 4615.57     462 4950.74  460.97 5152.15     466 6585.31     464
 6770.58     466 6794.69     468  6841.3     480 6873.42     48310817.42     486
#Mann= 7 ,-1,0
    1000     .13       0 1378.09     .04       0 1667.97     .07       0
 2155.82     .13       0 3628.33     .05       0 4169.13     .13       0
 5152.15    .085       0
#XS Ineff= 2 , 0
       0                 6873.42       0
Permanent Ineff=
       F       F
Bank Sta=3628.33,4169.13
XS Rating Curve= 0 ,0
Exp/Cntr=0.3,0.1

Type RM Length L Ch R = 1 ,126526  ,167,167,167
BEGIN DESCRIPTION:
This cross section corresponds to cross section 126590 of the non-georeferenced CDC model which was the source of this model.
END DESCRIPTION:
XS GIS Cut Line= 6
  2388322.501575 6977868.8919064  2387824.984884 6976382.9902325
 2387813.5528202 6975516.0424913 2388931.2175797 6973731.4945512
      2389503.27      6972526.64      2391214.25      6968969.47
#Sta/Elev= 30
    1000     490 1075.57  472.41 1378.09     466 1667.97   463.3 1764.61   467.1
 2155.82     468    2514     468    2523     465    3255     466  3600.6     472
 3628.33     476 3728.64     468 3795.53  444.11 3810.14     444  3839.2  435.28
  3857.2  435.28 3886.29     444 4007.36     458 4117.83     470 4169.13     472
 4580.92     468 4615.57     462 4950.74  460.97 5152.15     466 6585.31     464
 6770.58     466 6794.69     468  6841.3     480 6873.42     48310817.42     486
#Mann= 7 ,-1,0
    1000     .13       0 1378.09     .04       0 1667.97     .07       0
 2155.82     .13       0 3628.33     .05       0 4169.13     .13       0
 5152.15    .085       0
#XS Ineff= 2 , 0
       0                 6873.42       0
Permanent Ineff=
       F       F
Bank Sta=3628.33,4169.13
XS Rating Curve= 0 ,0
Exp/Cntr=0.3,0.1

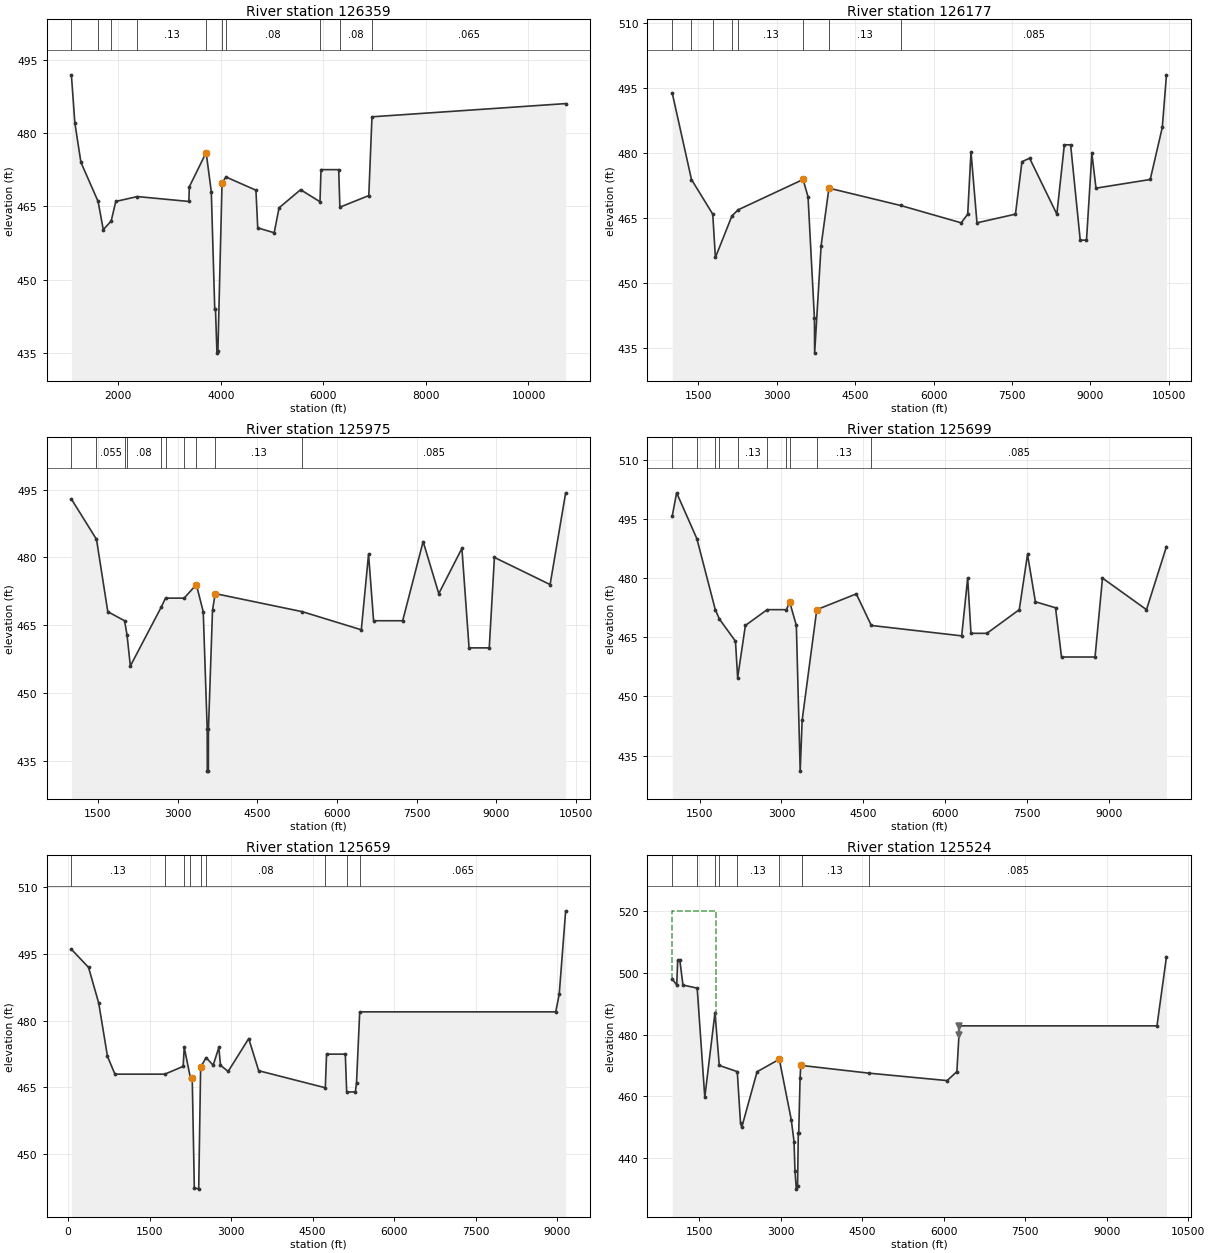
Type RM Length L Ch R = 1 ,126359  ,269,181,140
BEGIN DESCRIPTION:
This cross section corresponds to cross section 126400 of the non-georeferenced CDC model which was the source of this model.
END DESCRIPTION:
XS GIS Cut Line= 5
     2388527.595     6977823.304     2388068.022     6976412.168
     2388060.395     6975534.975 2391168.6798068 6969126.0675065
2391236.318686276968986.60431428
#Sta/Elev= 30
  1085.8  491.88 1154.19     482 1271.87     474 1606.85     466 1707.85  460.24
 1862.07     462  1951.6     466  2370.8     467  3376.8     466  3385.8     469
 3714.13     476 3814.44     468 3881.33  444.11 3895.94     444    3925     435
    3943   435.4    4024   469.8    4101     471    4685   468.3    4720   460.6
    5041   459.6    5136   464.7    5556   468.4 5934.31  465.94 5953.99   472.5
 6298.99   472.5    6322  464.83    6886   467.2    6948   483.3   10725     486
#Mann= 10 ,-1,0
  1085.8     .13       0 1606.85     .04       0 1862.07     .07       0
  2370.8     .13       0 3714.13     .05       0    4024     .13       0
    4101     .08       0 5934.31    .023       0    6322     .08       0
    6948    .065       0
#XS Ineff= 2 , 0
       0                   10570       0
Permanent Ineff=
       F       F
Bank Sta=3714.13,4024
XS Rating Curve= 0 ,0
Exp/Cntr=0.3,0.1

Type RM Length L Ch R = 1 ,126177  ,202,202,202
BEGIN DESCRIPTION:
This cross section corresponds to cross section 126217 of the non-georeferenced CDC model which was the source of this model.
END DESCRIPTION:
XS GIS Cut Line= 5
  2388665.624278 6977808.5402029 2388214.2354178 6976402.2900627
 2388209.0270949 6975666.1790021 2389854.8604174 6972092.9151512
      2391219.69      6969087.67
#Sta/Elev= 30
    1000     494  1368.7  473.99 1775.74     466 1826.27     456 2142.74  465.61
    2261     467    3503     474    3598     470 3720.07     442 3724.24  433.93
 3847.75   458.7 3997.76     472 5368.98     468 6526.97     464 6651.85     466
 6714.22   480.4    6829     464 7564.98     466 7689.44   478.1 7835.41  478.91
 8356.56     466 8499.93     482 8620.16     482 8803.73     460 8923.64     460
 9026.94     480 9105.03     47210142.62     47410373.07     48610453.25  498.15
#Mann= 8 ,-1,0
    1000     .08       0  1368.7    .055       0 1775.74     .04       0
 2142.74     .08       0    2261     .13       0    3503     .05       0
 3997.76     .13       0 5368.98    .085       0
Bank Sta=3503,3997.76
XS Rating Curve= 0 ,0
Exp/Cntr=0.3,0.1

Type RM Length L Ch R = 1 ,125975  ,276,276,276
BEGIN DESCRIPTION:
This cross section corresponds to cross section 126020 of the non-georeferenced CDC model which was the source of this model.
END DESCRIPTION:
XS GIS Cut Line= 5
  2388874.970316 6977784.8132162 2388428.3557245 6976450.1777622
   2388430.96005 6975684.5529811 2390177.4877249 6971625.0909556
 2391249.2213574 6969134.0557175
#Sta/Elev= 30
    1000  492.91 1472.77     484 1685.46     468 2001.02     466 2046.58  462.94
 2110.24     456    2691     469    2772     471    3123     471    3352     474
 3482.03     468 3556.67     442 3558.44  432.75 3578.44  432.75  3580.2     442
  3656.7  468.36 3707.28     472 5347.81     468 6457.58     464 6593.87  480.72
 6688.92     466  7236.3     466 7621.13  483.51 7915.76     472 8351.17     482
 8485.75     460 8865.87     460 8962.86     480 10011.3     47410304.04  494.28
#Mann= 10 ,-1,0
    1000     .08       0 1472.77    .055       0 2001.02     .04       0
 2046.58     .08       0    2691     .13       0    2772     .06       0
    3123     .13       0    3352     .05       0 3707.28     .13       0
 5347.81    .085       0
Bank Sta=3352,3707.28
XS Rating Curve= 0 ,0
Exp/Cntr=0.3,0.1

Type RM Length L Ch R = 1 ,125699  ,41,41,41
BEGIN DESCRIPTION:
This cross section corresponds to cross section 125742 of the non-georeferenced CDC model which was the source of this model.
----------------------------------------------------
CDC FW041812-01 XTO-BASS ARLINGTON PAD SITE
CROSS-SECTION 125742 - 126600
LOCATED IN LOB.
----------------------------------------------------
END DESCRIPTION:
XS GIS Cut Line= 5
  2389170.543216 6977755.9504131 2388736.5155413 6976439.7611163
   2388734.34527 6975682.3827098 2390466.1160847 6971246.6189436
 2391245.1213645 6969251.2721202
#Sta/Elev= 30
    1000  495.67 1081.02  501.61 1451.33     490 1788.79     472 1865.14   469.6
 2158.22     464 2198.04  454.75 2339.61     468    2738     472    3092     472
    3149     474 3272.48     468 3342.83  431.08 3378.71     444 3646.36     472
 4369.45     476 4644.66     468 6298.87  465.36 6408.27     480 6468.96     466
 6759.63     466 7352.94     472 7503.87     486 7647.94     474 8016.48  472.48
 8125.92     460 8739.59     460 8875.92     480 9681.33     47210047.14     488
#Mann= 10 ,-1,0
    1000     .08       0 1451.33    .055       0 1788.79     .04       0
 1865.14     .08       0 2198.04     .13       0    2738     .06       0
    3092     .13       0    3149     .05       0 3646.36     .13       0
 4644.66    .085       0
Bank Sta=3149,3646.36
XS Rating Curve= 0 ,0
Exp/Cntr=0.3,0.1

Type RM Length L Ch R = 1 ,125659  ,218,135,58
BEGIN DESCRIPTION:
This cross section corresponds to cross section 125701 of the non-georeferenced CDC model which was the source of this model.
----------------------------------------------------
CDC FW022811-01 QUICKSILVER EAST AND WEST VILLAGE CREEK PAD SITES
CROSS-SECTION 125701 - 133770
DOWNSTREAM END
----------------------------------------------------
END DESCRIPTION:
XS GIS Cut Line= 6
       2389187.7      6977750.24 2388770.6871038 6976462.3259077
 2388768.5168325 6975704.9475012 2390500.2876472  6971269.183735
 2391295.0475516 6969233.4829617 2391306.4841294 6969204.1892718
#Sta/Elev= 30
   63.22  496.07  378.73     492   565.6     484  727.09     472  864.14     468
 1781.81     468 2119.09469.7464 2138.73 474.001 2252.39467.1733 2285.66467.2199
 2324.26442.4988 2405.04442.1572 2440.27469.5142 2540.09471.7369 2670.93     470
 2775.19     474 2805.71     470 2946.22  468.61  3324.9     476 3507.86  468.77
  4733.4  464.94 4756.08   472.5 5101.08   472.5 5126.58     464    5286     464
    5307     466    5366     482 8971.49     482 9035.63     486 9153.68  504.71
#Mann= 9 ,-1,0
   63.22     .13       0 1781.81     .07       0 2138.73     .13       0
 2252.39     .05       0 2440.27     .13       0 2540.09     .08       0
  4733.4    .023       0 5126.58     .08       0    5366    .065       0
Bank Sta=2285.66,2440.27
XS Rating Curve= 0 ,0
Exp/Cntr=0.3,0.1

Type RM Length L Ch R = 1 ,125524  ,229,290,259
BEGIN DESCRIPTION:
This cross section corresponds to cross section 125562 of the non-georeferenced CDC model which was the source of this model.
----------------------------------
CDC ARL021910-1 ARLINGTON LANDFILL
CROSS-SECTION 116053-125562
UPSTREAM END
----------------------------------
END DESCRIPTION:
XS GIS Cut Line= 4
   2389320.42513   6977750.35397   2388837.06685   6975913.59485
   2390016.65209   6972720.08614   2391693.30097    6969314.4381
#Sta/Elev= 30
    1000     498 1083.35     496 1100.88     504 1140.48     504 1198.36     496
    1460     495    1600   459.7    1788  487.11  1866.4     470 2198.02     468
 2257.54  451.46 2280.55     450 2562.57  467.96 2971.77     472 3192.28  452.43
    3243   445.4    3260     436    3285     430    3308     431 3321.39     448
 3329.01     448 3354.51     466 3366.58     470  3380.8     470    4624   467.5
    6061   465.1    6241     468    6289   482.8  9924.7   482.810099.69  505.15
#Mann= 8 ,-1,0
    1000     .08       0    1460    .055       0    1788     .04       0
  1866.4     .08       0 2198.02     .13       0 2971.77     .05       0
  3380.8     .13       0    4624    .085       0
Levee=0,,,-1,6289,480,,
#XS Ineff= 1 ,-1
    1000    1798     520
Permanent Ineff=
       T
Bank Sta=2971.77,3366.58
XS Rating Curve= 0 ,0
Exp/Cntr=0.3,0.1