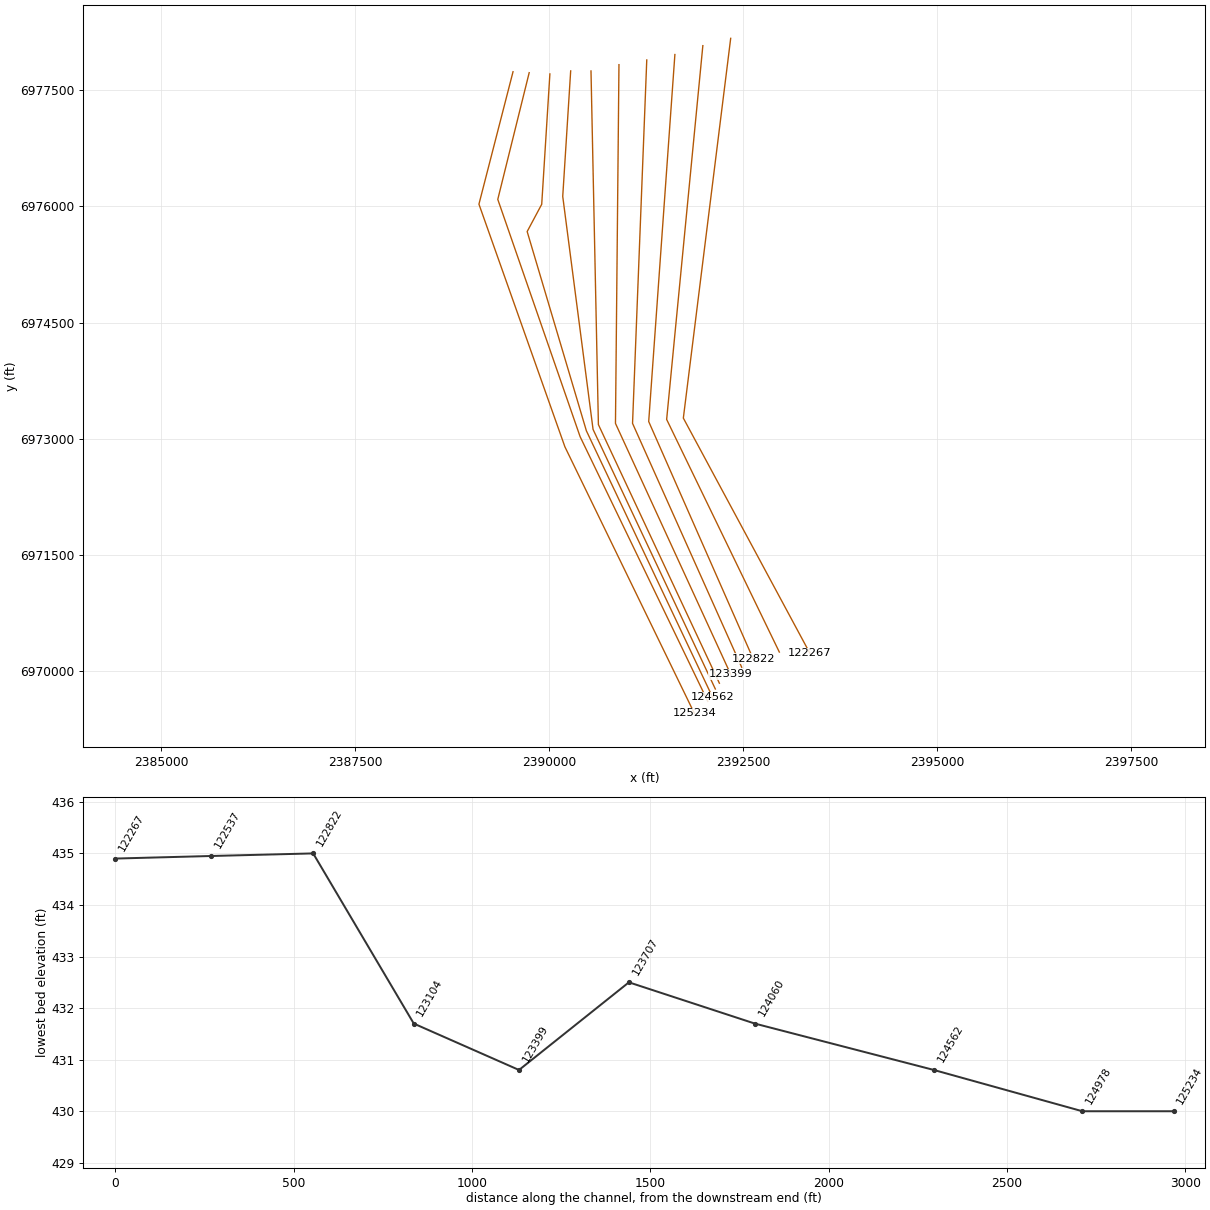
HEC-RAS study CDC_Consolidated_Model.prj: Upper Trinity CDC Consolidated Model

--- CDC_Consolidated_Model.g04 (geometry) --- (continued)

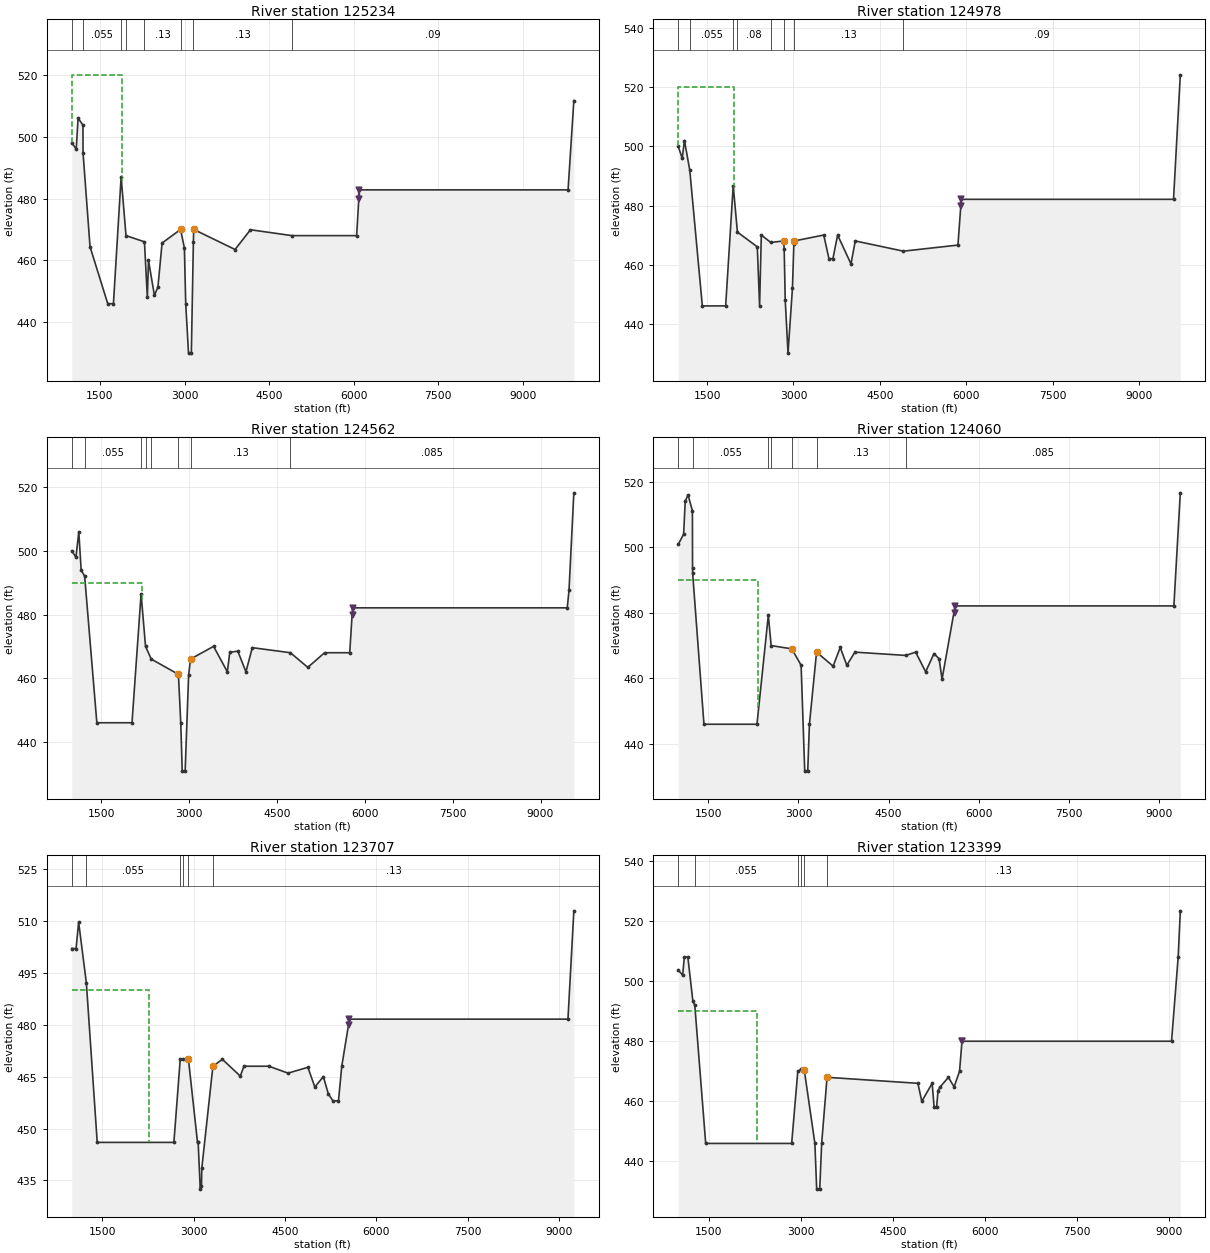
Type RM Length L Ch R = 1 ,125234  ,210,256,240
BEGIN DESCRIPTION:
This cross section corresponds to cross section 125286 of the non-georeferenced CDC model which was the source of this model.
END DESCRIPTION:
XS GIS Cut Line= 5
  2389532.435209 6977736.3198749  2389093.198883 6976027.9866774
 2390200.8377438 6972897.7780428 2391837.9906375 6969522.7782311
 2391868.7784544 6969459.3089751
#Sta/Elev= 30
    1000     498 1079.56     496 1111.79     506 1198.18  503.74    1200  494.75
    1324   464.4    1638     446    1739     446  1875.5  486.96 1961.84     468
 2289.23     466 2340.82     448 2360.83     460 2465.96  448.67 2528.22  451.38
 2601.92   465.6 2930.17     470 2997.66     464 3021.26     446    3071     430
    3121     430 3157.25     466 3163.15     470 3896.61  463.51  4169.9   469.9
    4905     468    6053     468    6101   482.8 9803.53   482.8 9905.96  511.66
#Mann= 8 ,-1,0
    1000     .08       0    1200    .055       0  1875.5     .04       0
 1961.84     .08       0 2289.23     .13       0 2930.17     .05       0
 3157.25     .13       0    4905     .09       0
Levee=0,,,-1,6101,480,,
#XS Ineff= 1 ,-1
    1000  1885.5     520
Permanent Ineff=
       T
Bank Sta=2930.17,3163.15
XS Rating Curve= 0 ,0
Exp/Cntr=0.3,0.1

Type RM Length L Ch R = 1 ,124978  ,311,416,173
BEGIN DESCRIPTION:
This cross section corresponds to cross section 125016 of the non-georeferenced CDC model which was the source of this model.
END DESCRIPTION:
XS GIS Cut Line= 4
   2389740.61786   6977723.96393   2389335.93396   6976089.66602
   2390396.79011   6973028.61111   2392041.61687   6969614.79084
#Sta/Elev= 30
    1000     500  1069.3     496 1107.65     502    1200     492    1418     446
    1823     446    1954  486.75    2027     471 2371.99     466 2411.78     446
 2441.59     470 2605.96  467.49 2829.58     468 2838.51  465.16 2856.52     448
    2905     430 2982.01     452 3006.03  466.86 3014.16     468 3525.19     470
 3615.41     462 3684.32     462 3765.78     470  3997.8  460.22 4072.17     468
 4906.75  464.54    5854   466.6    5912   482.1 9595.03   482.1 9712.74  524.27
#Mann= 8 ,-1,0
    1000     .08       0    1200    .055       0    1954     .04       0
    2027     .08       0 2605.96     .13       0 2838.51     .05       0
 3006.03     .13       0 4906.75     .09       0
Levee=0,,,-1,5912,480,,
#XS Ineff= 1 ,-1
    1000    1964     520
Permanent Ineff=
       T
Bank Sta=2829.58,3014.16
XS Rating Curve= 0 ,0
Exp/Cntr=0.3,0.1

Type RM Length L Ch R = 1 ,124562  ,362,502,201
BEGIN DESCRIPTION:
This cross section corresponds to cross section 124600 of the non-georeferenced CDC model which was the source of this model.
END DESCRIPTION:
XS GIS Cut Line= 6
  2390007.276951 6977707.8241858   2390003.57239 6977648.6461657
 2389902.0099294 6976026.2504604 2389714.5096482 6975674.6878433
   2390477.53076 6973104.3753987 2392104.4494757 6969665.3599211
#Sta/Elev= 30
    1000  500.02  1071.3     498 1120.11     506 1160.02     494    1220     492
    1428     446    2028     446    2183  486.48  2258.9     470 2356.09     466
 2820.15  461.21    2860     446    2885   430.8    2935   430.8 2994.24  460.96
  3026.5     466 3420.17     470 3655.25     462 3696.98  468.15 3834.14  468.48
 3972.35     462 4081.23  469.59 4730.99     468 5028.45   463.4  5315.1     468
    5744     468    5792   482.1 9456.37   482.1 9486.23  487.57 9568.91  518.23
#Mann= 8 ,-1,0
    1000     .08       0    1220    .055       0    2183     .04       0
  2258.9     .08       0 2356.09     .13       0 2820.15     .05       0
  3026.5     .13       0 4730.99    .085       0
Levee=0,,,-1,5792,480,,
#XS Ineff= 1 ,-1
    1000    2193     490
Permanent Ineff=
       T
Bank Sta=2820.15,3026.5
XS Rating Curve= 0 ,0
Exp/Cntr=0.3,0.1

Type RM Length L Ch R = 1 ,124060  ,401,353,223
BEGIN DESCRIPTION:
This cross section corresponds to cross section 124110 of the non-georeferenced CDC model which was the source of this model.
END DESCRIPTION:
XS GIS Cut Line= 5
  2390275.190328 6977746.9998931   2390274.40551 6977734.5836579
 2390172.8430492 6976127.8129213 2390563.4682522 6973122.6046929
 2392138.9890513 6969773.6461677
#Sta/Elev= 30
    1000  500.86  1089.7     504 1115.98  513.99  1162.2     516 1235.94  511.14
    1238  493.61    1240     492    1428     446    2310     446    2499  479.28
  2546.1     470 2889.38     469 3044.48     464  3104.7   431.7  3154.7   431.7
 3182.63     446 3301.52     468 3576.77  463.72 3695.91  469.43 3804.58     464
 3939.78     468    4785     467 4950.58     468 5116.51     462 5255.23  467.54
 5340.02     466 5389.68  459.76    5607   482.1 9246.82   482.1 9353.96   516.6
#Mann= 7 ,-1,0
    1000     .08       0    1240    .055       0    2499     .04       0
  2546.1     .13       0 2889.38     .05       0 3301.52     .13       0
    4785    .085       0
Levee=0,,,-1,5607,480,,
#XS Ineff= 1 ,-1
    1000    2331     490
Permanent Ineff=
       T
Bank Sta=2889.38,3301.52
XS Rating Curve= 0 ,0
Exp/Cntr=0.3,0.1

Type RM Length L Ch R = 1 ,123707  ,311,308,243
BEGIN DESCRIPTION:
This cross section corresponds to cross section 123744 of the non-georeferenced CDC model which was the source of this model.
END DESCRIPTION:
XS GIS Cut Line= 4
  2390536.929823 6977746.1725683   2390536.92992   6977746.16795
   2390632.39889   6973184.36704   2392191.04111   6969848.53184
#Sta/Elev= 30
    1000     502 1070.69     502 1112.73  509.64    1240     492    1418     446
    2677     446    2781     470    2831     470    2916     470 3064.72     446
 3075.36     446    3110   432.5    3130   433.5    3135   438.5 3317.83     468
 3473.31     470    3767  465.15 3828.25     468 4237.24     468 4551.27     466
 4877.43  467.69 4991.06     462 5131.87     465 5212.93     460 5289.21     458
 5379.95     458 5433.71     468    5560   481.6 9148.12   481.6 9244.81  512.89
#Mann= 6 ,-1,0
    1000     .09       0    1240    .055       0    2781     .04       0
    2831     .09       0    2916     .05       0 3317.83     .13       0
Levee=0,,,-1,5560,480,,
#XS Ineff= 1 ,-1
       0    2269     490
Permanent Ineff=
       T
Bank Sta=2916,3317.83
XS Rating Curve= 0 ,0
Exp/Cntr=0.3,0.1

Type RM Length L Ch R = 1 ,123399  ,335,295,261
BEGIN DESCRIPTION:
This cross section corresponds to cross section 123437 of the non-georeferenced CDC model which was the source of this model.
END DESCRIPTION:
XS GIS Cut Line= 4
   2390897.30131 6977827.4877882  2390897.203477 6977817.4279804
 2390852.2960866 6973199.8007327 2392336.8275663 6969963.2035314
#Sta/Elev= 30
    1000  503.64  1072.2     502 1099.39     508  1156.4     508 1238.93  493.34
    1270     492    1448     446    2850     446    2950     470  3005.4  470.65
  3054.8  470.54 3228.73     446    3258   430.8    3308   430.8 3339.01     446
 3427.18     468 4908.99     466 4972.34     460 5141.47     466  5173.9     458
 5213.76     458 5237.26  463.59 5267.44  464.69 5406.68     468 5499.29  464.81
    5588     470    5628     480 9045.75     480 9153.99     508 9188.72  523.38
#Mann= 6 ,-1,0
    1000     .09       0    1270    .055       0    2950     .04       0
  3005.4     .09       0  3054.8     .05       0 3427.18     .13       0
Levee=0,,,-1,5628,480,,
#XS Ineff= 1 ,-1
    1000    2285     490
Permanent Ineff=
       T
Bank Sta=3054.8,3427.18
XS Rating Curve= 0 ,0
Exp/Cntr=0.3,0.1

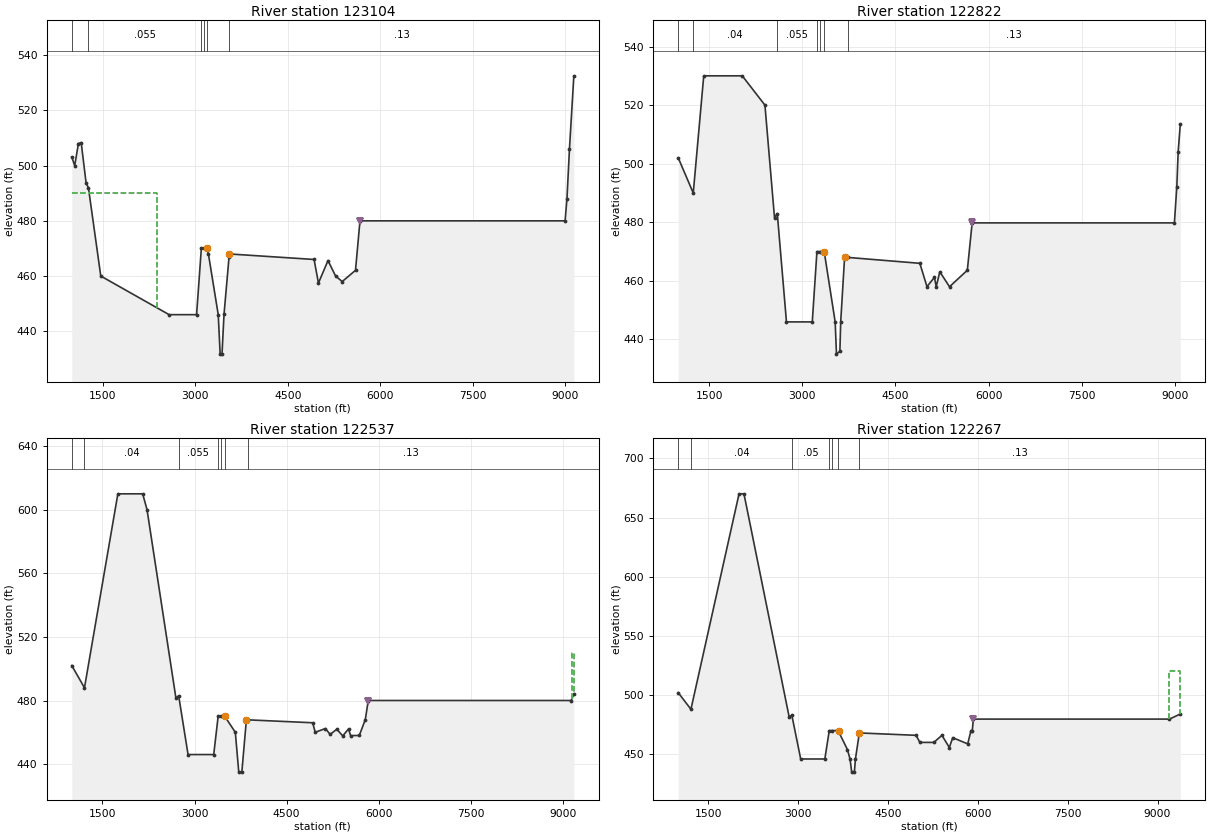
Type RM Length L Ch R = 1 ,123104  ,313,282,245
BEGIN DESCRIPTION:
This cross section corresponds to cross section 123144 of the non-georeferenced CDC model which was the source of this model.
END DESCRIPTION:
XS GIS Cut Line= 4
  2391255.473889 6977888.0837214  2391253.685047 6977842.3124451
 2391072.2615259 6973200.2114931 2392478.5116662 6970054.3782178
#Sta/Elev= 30
    1000  503.15 1047.68     500 1107.55     508 1152.74  508.37 1232.27   493.7
    1270     492    1470     460    2578     446    3023     446    3100     470
    3150     470  3187.4     470 3214.54     468 3373.82     446    3405   431.7
    3435   431.7  3467.5   446.1 3548.83  466.85 3553.36     468 4927.28     466
 4997.89  457.45 5152.81  465.61 5275.74     460 5383.05     458  5598.6  462.07
    5671     480 8995.42     480 9025.77     488 9066.15     506 9137.29  532.55
#Mann= 6 ,-1,0
    1000     .09       0    1270    .055       0    3100     .04       0
    3150     .09       0  3187.4     .05       0 3548.83     .13       0
Levee=0,,,-1,5671,480,,
#XS Ineff= 1 ,-1
    1000    2388     490
Permanent Ineff=
       T
Bank Sta=3187.4,3553.36
XS Rating Curve= 0 ,0
Exp/Cntr=0.3,0.1

Type RM Length L Ch R = 1 ,122822  ,302,285,227
BEGIN DESCRIPTION:
This cross section corresponds to cross section 122858 of the non-georeferenced CDC model which was the source of this model.
END DESCRIPTION:
XS GIS Cut Line= 3
   2391617.86411   6977958.18787   2391280.48289   6973223.82103
   2392626.45002   6970162.66015
#Sta/Elev= 30
    1000     502    1242     490    1411     530    2032     530    2397     520
 2551.58   481.5    2596     483    2744     446    3160     446    3235     470
    3285     470 3352.13     470  3528.8     446    3550     435    3605     436
 3618.01     446 3680.43     468 3739.37     468 4893.27     466 5007.89  458.04
  5128.7  461.21 5157.14     458 5215.15  463.11 5371.34     458 5658.63  463.64
    5736   479.8 8995.25   479.8 9033.55     492  9055.7     504 9090.37  513.58
#Mann= 7 ,-1,0
    1000     .09       0    1242     .04       0    2596    .055       0
    3235     .04       0    3285     .13       0 3352.13     .05       0
 3739.37     .13       0
Levee=0,,,-1,5736,480,,
Bank Sta=3352.13,3680.43
XS Rating Curve= 0 ,0
Exp/Cntr=0.3,0.1

Type RM Length L Ch R = 1 ,122537  ,299,270,224
BEGIN DESCRIPTION:
This cross section corresponds to cross section 122578 of the non-georeferenced CDC model which was the source of this model.
END DESCRIPTION:
XS GIS Cut Line= 5
  2391978.100513 6978072.7867457  2391977.137012  6978062.827424
 2391511.6422088  6973251.195315 2392947.2613848 6970283.5450823
2392963.282608246970250.42669807
#Sta/Elev= 30
    1000     502    1207     488    1751     610    2155     610    2226     600
 2696.58   481.5    2741     483    2894     446    3312     446    3384     470
    3434     470 3492.52     470 3663.85     460    3720  434.95    3770  434.95
 3844.38     468 3865.82  467.84 4924.04     466 4965.29     460 5130.79  462.38
 5208.98  458.67 5316.36  461.93  5413.7  457.75 5508.21  462.12 5541.14  457.94
 5682.84     458    5781     468    5829     480 9133.24     480 9177.55     484
#Mann= 7 ,-1,0
    1000     .09       0    1207     .04       0    2741    .055       0
    3384     .04       0    3434     .09       0 3492.52     .05       0
 3865.82     .13       0
Levee=0,,,-1,5829,480,,
#XS Ineff= 2 ,-1
       0    2500   479.1 9140.76 9177.55     510
Permanent Ineff=
       T       F
Bank Sta=3492.52,3844.38
XS Rating Curve= 0 ,0
Exp/Cntr=0.3,0.1

Type RM Length L Ch R = 1 ,122267  ,539,422,405
BEGIN DESCRIPTION:
This cross section corresponds to cross section 122304 of the non-georeferenced CDC model which was the source of this model.
END DESCRIPTION:
XS GIS Cut Line= 4
   2392336.84397   6978167.12807   2391726.70805   6973268.33111
   2393271.58488   6970394.219072393357.279874226970234.79081665
#Sta/Elev= 30
    1000     502    1212     488    2015     670    2097     670 2851.58   481.5
    2896     483    3044     446    3447     446    3521     470    3571     470
 3665.77     470 3675.17  469.31 3823.93     454 3867.94     446    3895     435
    3940   434.9 3957.83     446 4023.01     468 4969.97     466 5033.93     460
  5266.5     460 5401.55     466 5524.94   455.7 5582.02     464 5832.03  458.76
 5886.82     470 5908.76  470.01    5926   479.7 9199.65   479.7 9380.65     484
#Mann= 7 ,-1,0
    1000     .09       0    1212     .04       0    2896     .05       0
    3521     .04       0    3571     .09       0 3665.77     .05       0
 4023.01     .13       0
Levee=0,,,-1,5926,480,,
#XS Ineff= 2 ,-1
       0    2500  478.99 9199.65 9380.65     520
Permanent Ineff=
       T       F
Bank Sta=3675.17,4023.01
XS Rating Curve= 0 ,0
Exp/Cntr=0.3,0.1