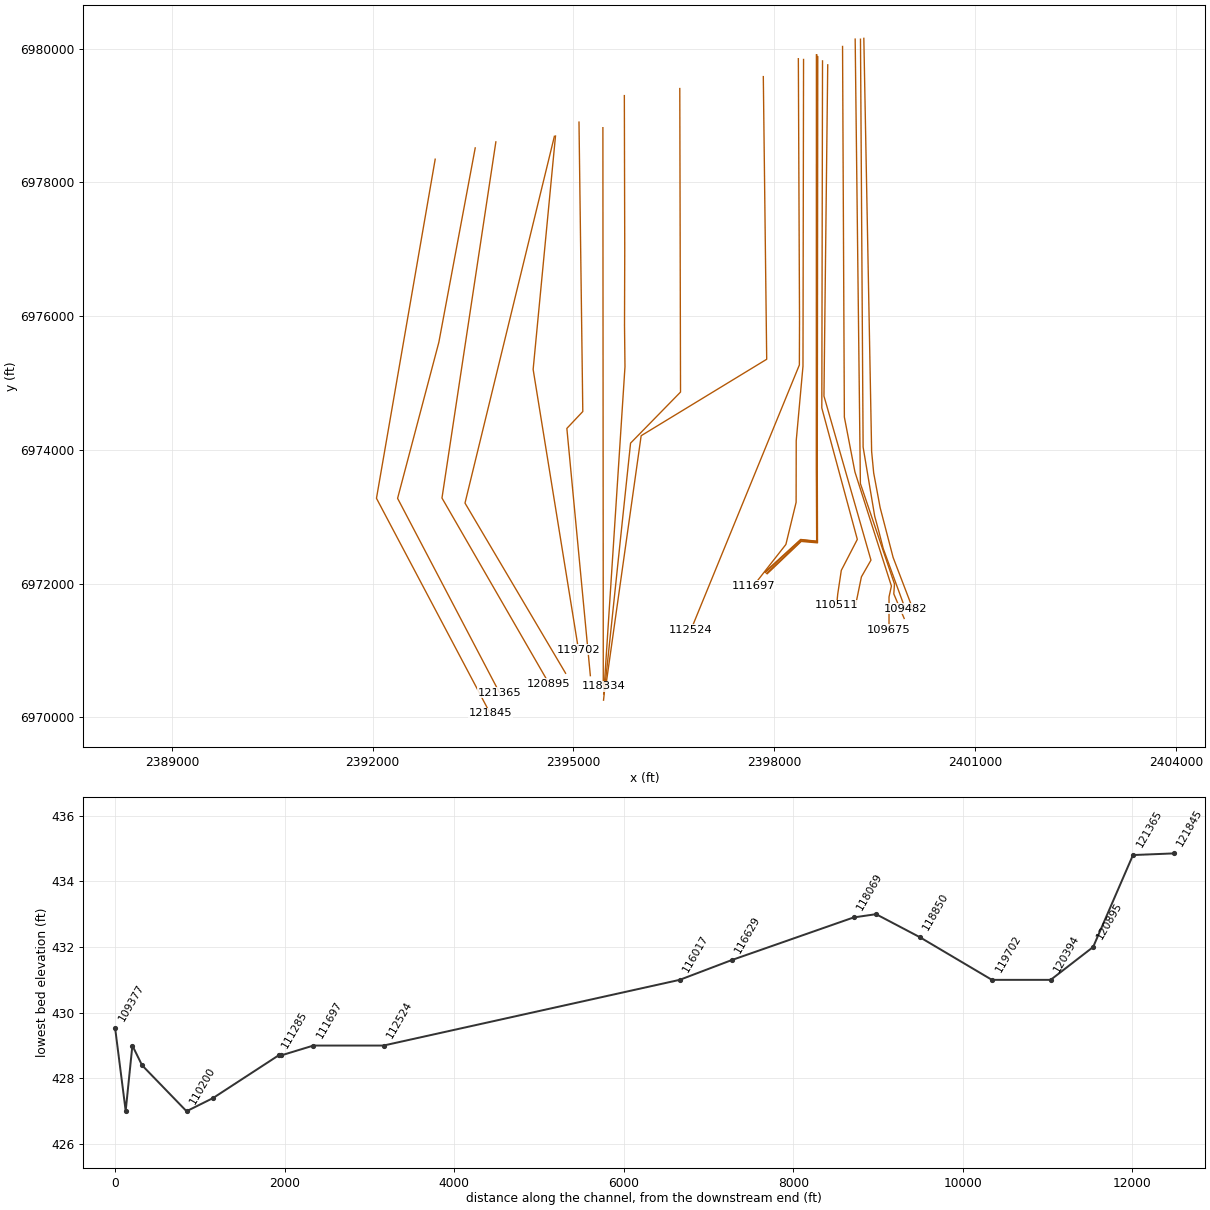
HEC-RAS study CDC_Consolidated_Model.prj: Upper Trinity CDC Consolidated Model

--- CDC_Consolidated_Model.g04 (geometry) --- (continued)

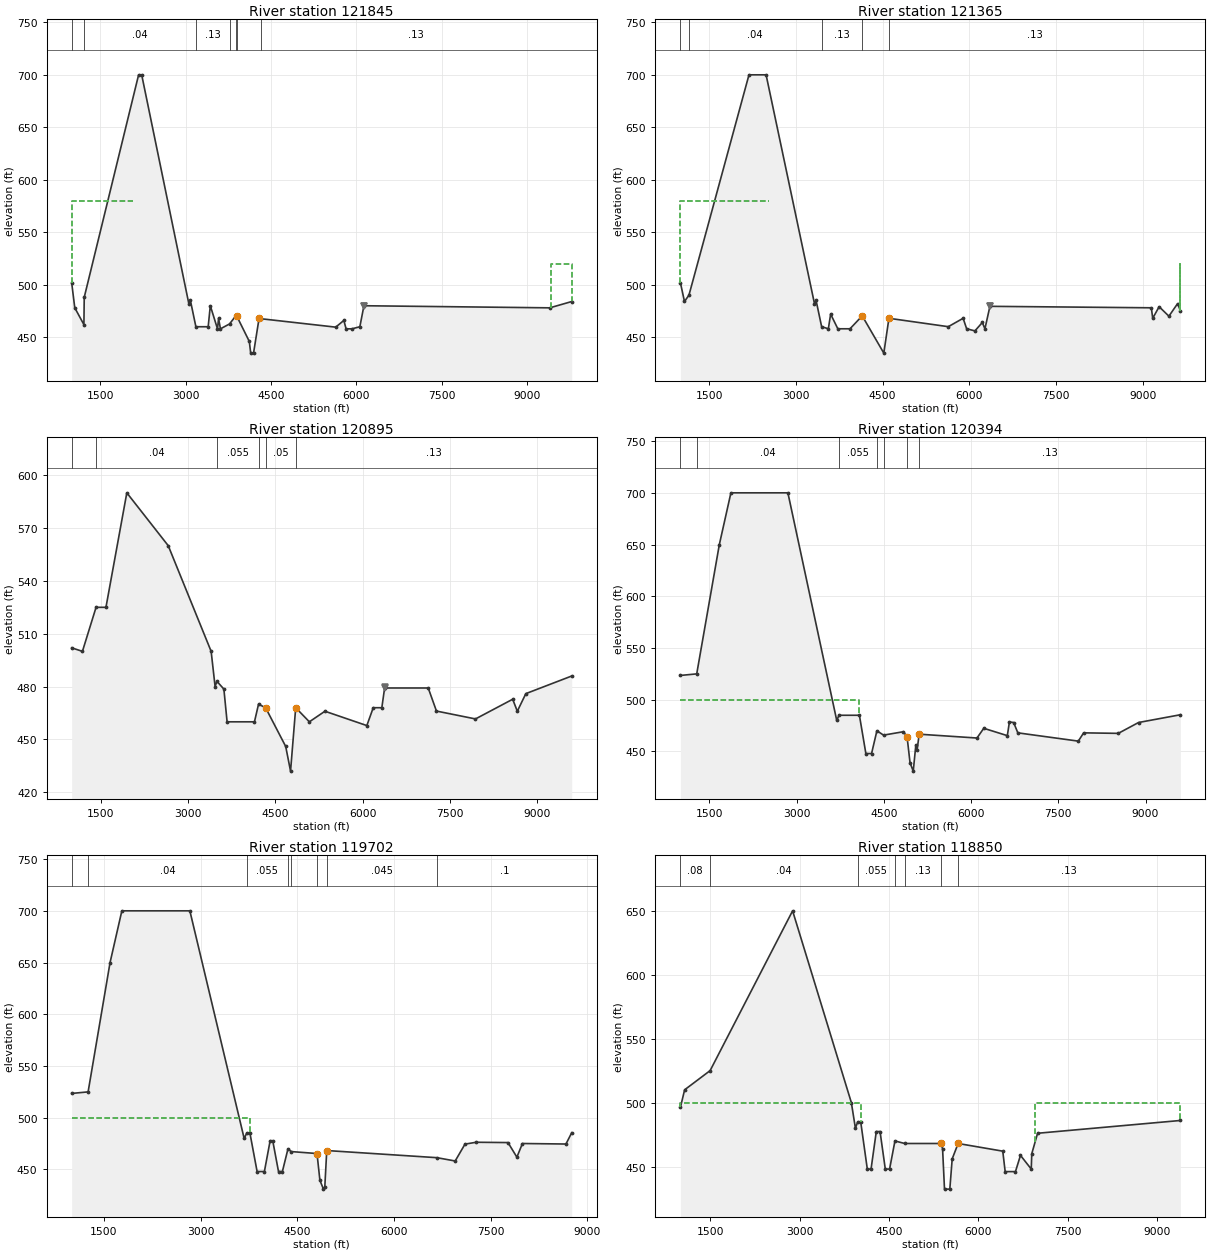
Type RM Length L Ch R = 1 ,121845  ,460,480,345
BEGIN DESCRIPTION:
This cross section corresponds to cross section 121885 of the non-georeferenced CDC model which was the source of this model.
END DESCRIPTION:
XS GIS Cut Line= 5
  2392934.922293 6978346.7119413   2392933.73418 6978339.8455707
 2392057.4321277 6973275.5010407 2393585.4271033 6970382.4887821
 2393756.10261766970059.34219915
#Sta/Elev= 30
    1000     502 1054.54  478.03 1215.04     462  1220.7     488    2176     700
    2230     700    3058     482    3086     485    3182     460 3398.05     460
 3435.39     480 3561.52     458 3580.61     468 3613.07     458 3773.31  462.65
 3878.42     470  3901.4     470  4120.4     446    4145  434.85    4195  434.85
 4292.05     468 4323.75  467.63 5638.54   459.6 5781.26     466 5820.54     458
 5924.02     458 6062.45     460    6134     480 9398.97     478 9783.76     484
#Mann= 7 ,-1,0
    1000     .09       0  1220.7     .04       0    3182     .13       0
 3773.31     .09       0 3878.42     .13       0  3901.4     .05       0
 4323.75     .13       0
Levee=0,,,-1,6134,480,,
#XS Ineff= 2 ,-1
       0 2081.01     580 9418.31 9783.76     520
Permanent Ineff=
       F       F
Bank Sta=3901.4,4292.05
XS Rating Curve= 0 ,0
Exp/Cntr=0.3,0.1

Type RM Length L Ch R = 1 ,121365  ,389,470,599
BEGIN DESCRIPTION:
This cross section corresponds to cross section 121401 of the non-georeferenced CDC model which was the source of this model.
END DESCRIPTION:
XS GIS Cut Line= 4
   2393532.90785   6978515.49187   2392989.30887   6975608.10005
   2392373.15394   6973274.88293   2393895.63514   6970368.50784
#Sta/Elev= 30
    1000     502 1070.87     484  1147.9     490    2187     700    2483     700
    3320     482    3348     485    3444     460 3560.38     458  3599.8     472
 3724.17     458 3934.87     458 4140.99     470 4149.42     470    4520   434.8
 4605.47  466.89 4608.69     468 5635.51     460 5892.36     468 5953.27     458
 6096.46     456 6224.52     464 6269.53     458    6356   479.4 9148.57     478
  9172.7     468 9283.87  479.04 9452.94     470 9603.19     482 9651.98  475.13
#Mann= 5 ,-1,0
    1000     .09       0  1147.9     .04       0    3444     .13       0
 4140.99     .05       0 4605.47     .13       0
Levee=0,,,-1,6356,480,,
#XS Ineff= 2 ,-1
       0 2540.01     580 9637.74 9651.98     520
Permanent Ineff=
       F       F
Bank Sta=4149.42,4608.69
XS Rating Curve= 0 ,0
Exp/Cntr=0.3,0.1

Type RM Length L Ch R = 1 ,120895  ,599,501,399
BEGIN DESCRIPTION:
This cross section corresponds to cross section 120930 of the non-georeferenced CDC model which was the source of this model.
END DESCRIPTION:
XS GIS Cut Line= 5
   2393841.16806   6978605.57207   2393036.23594   6973279.50694
   2394241.37297   6971189.000952394511.087914816970721.13655476
2394635.946686996970504.54872728
#Sta/Elev= 30
    1000     502    1185     500    1419     525    1589     525  1947.4     590
 2658.72     560    3396     500    3464     480    3495     483  3614.8  478.56
    3670     460    4140     460    4210     470 4331.52     468  4676.8     446
    4760     432 4848.52     468 5083.05     460 5350.68     466 6070.55  457.86
 6180.38     468    6328     468    6376   479.2    7125   479.2  7266.5   466.1
 7936.78  461.63 8575.89  472.81 8655.56     466  8801.8     476  9589.6     486
#Mann= 6 ,-1,0
    1000     .09       0    1419     .04       0    3495    .055       0
    4210     .13       0 4331.52     .05       0 4848.52     .13       0
Levee=0,,,-1,6376,480,,
#XS Ineff= 1 ,-1
    1000    3400  478.56
Permanent Ineff=
       T
Bank Sta=4331.52,4848.52
XS Rating Curve= 0 ,0
Exp/Cntr=0.3,0.1

Type RM Length L Ch R = 1 ,120394  ,453,693,1087
BEGIN DESCRIPTION:
This cross section corresponds to cross section 120428 of the non-georeferenced CDC model which was the source of this model.
END DESCRIPTION:
XS GIS Cut Line= 6
      2394715.55       6978688.4      2393380.09     6973203.916
     2394405.682     6971467.403  2394425.264383  6971434.246479
2394755.913786516970874.397154682394882.945671486970659.30916658
#Sta/Elev= 30
    1000  523.49    1281     525    1670     650    1869     700    2849     700
  3689.1     480 3728.15     485    4079     485 4190.18     448    4288     448
    4380     470    4494   465.8    4837   469.1    4899   464.1    4950     439
    5005     431    5050   456.5    5072   451.7    5107   466.7    6101     463
    6218   472.4    6623   465.3    6659   478.5  6731.8     478  6803.8     468
  7843.9     460  7935.8     468  8531.4   467.5  8880.2     478    9600   485.5
#Mann= 7 ,-1,0
    1000     .09       0    1281     .04       0 3728.15    .055       0
    4380     .09       0    4494     .13       0    4899    .055       0
    5107     .13       0
#XS Ineff= 1 ,-1
    1000    4079     500
Permanent Ineff=
       T
Bank Sta=4899,5107
XS Rating Curve= 0 ,0
Exp/Cntr=0.3,0.1

Type RM Length L Ch R = 1 ,119702  ,559,851,527
BEGIN DESCRIPTION:
This cross section corresponds to cross section 119740 of the non-georeferenced CDC model which was the source of this model.
END DESCRIPTION:
XS GIS Cut Line= 4
   2394732.16201   6978693.19165   2394398.25553   6975203.13695
 2394812.1052536 6972642.35400672395076.144963936971008.55229555
#Sta/Elev= 30
    1000  523.49    1255     525  1595.4     650  1778.4     700  2832.9     700
  3675.2     480  3714.2     485    3765     485    3876     448    3989     448
    4078  477.76 4118.51  477.76 4207.78     448    4268     448    4355     470
    4405   467.3    4805   465.4    4850   439.5    4905     431    4926   433.2
    4956   468.3    6664   461.4    6948   458.2    7100   474.5    7274   476.3
    7767     476    7905   461.9    7991   475.1    8666   474.6    8755   485.5
#Mann= 8 ,-1,0
    1000     .08       0    1255     .04       0  3714.2    .055       0
    4355     .08       0    4405     .13       0    4805    .055       0
    4956    .045       0    6664      .1       0
#XS Ineff= 1 ,-1
    1000    3765     500
Permanent Ineff=
       T
Bank Sta=4805,4956
XS Rating Curve= 0 ,0
Exp/Cntr=0.3,0.1

Type RM Length L Ch R = 1 ,118850  ,338,516,320
BEGIN DESCRIPTION:
This cross section corresponds to cross section 118883 of the non-georeferenced CDC model which was the source of this model.
END DESCRIPTION:
XS GIS Cut Line= 5
  2395083.250572  6978901.396929  2395083.604225 6978874.4376774
 2395140.0276686 6974573.2221985 2394901.8765701  6974320.704987
 2395252.8748838 6970623.5696647
#Sta/Elev= 30
    1000  496.19 1071.41     510 1498.73     525  2882.8     650  3868.4     500
  3936.4     480  3975.6     485 4025.26     485 4136.26     448    4199     448
    4287  477.34    4350  477.34    4438     448    4510     448    4600     470
 4763.26     468    5370     468    5399     464 5431.33   432.3 5520.52   432.3
 5560.42     456 5660.13     468 6408.77     462 6449.24     446 6621.78     446
 6706.18   458.7 6886.76     448 6895.43     460 6993.17     476 9389.41     486
#Mann= 7 ,-1,0
    1000     .08       0 1498.73     .04       0  3975.6    .055       0
    4600     .08       0 4763.26     .13       0    5370     .06       0
 5660.13     .13       0
#XS Ineff= 3 ,-1
    1000 4025.26     500                            6951 9389.41     500
Permanent Ineff=
       F       F       T
#Block Obstruct= 2 , 0
       0                    6000       0   464.8
Bank Sta=5370,5660.13
XS Rating Curve= 0 ,0
Exp/Cntr=0.3,0.1

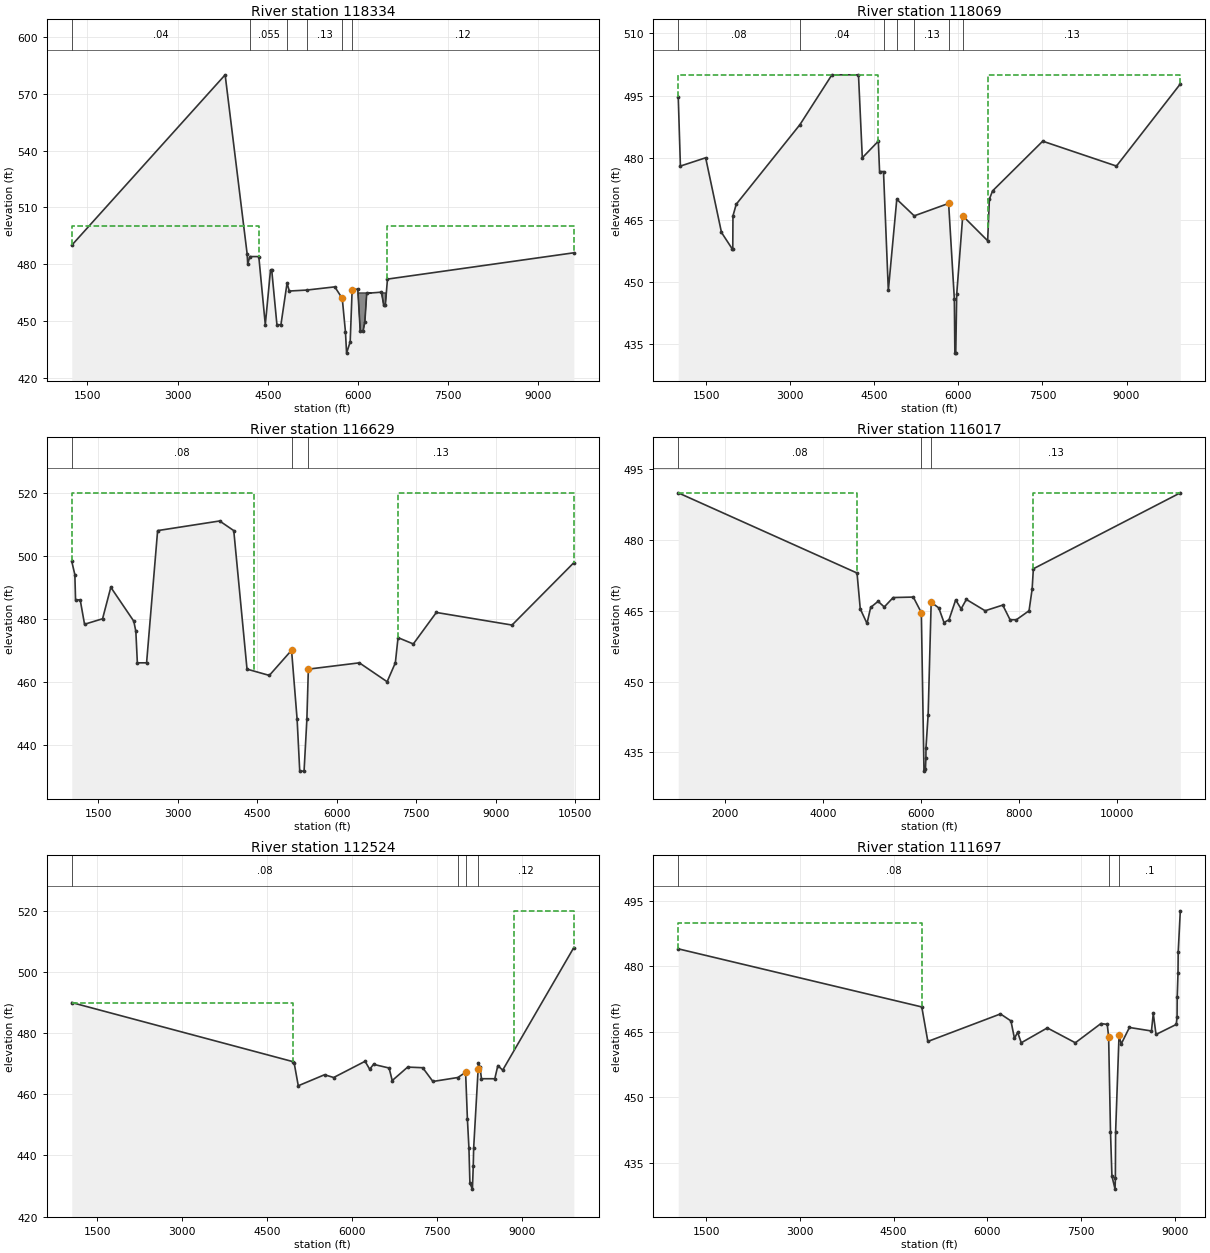
Type RM Length L Ch R = 1 ,118334  ,257,265,61
BEGIN DESCRIPTION:
This cross section corresponds to cross section 118369 of the non-georeferenced CDC model which was the source of this model.
END DESCRIPTION:
XS GIS Cut Line= 6
  2395440.313041 6978817.8179206 2395443.7717583 6973819.8191173
 2395443.8824815 6973659.8191556 2395443.8963219 6973639.8191604
 2395443.9032421 6973629.81916282395446.092103376970466.81992018
#Sta/Elev= 30
    1239     490    3790     580  4155.6   485.5  4165.6     480 4200.75     484
 4349.89     484 4457.89     448 4544.62  476.91 4564.62  476.91  4651.4     448
    4718     448    4820     470    4857   465.8    5144   466.3    5614     468
    5738   461.9    5791   444.3    5810     433    5870     439    5902   466.1
    5996   466.9    6037   444.6    6085   444.7    6114   449.6    6145   464.6
    6390   465.2    6428   458.2    6454   458.2    6490   472.1    9590     486
#Mann= 6 ,-1,0
    1239     .04       0 4200.75    .055       0    4820     .08       0
    5144     .13       0    5738     .06       0    5902     .12       0
#XS Ineff= 2 ,-1
    1000 4349.89     500    6490    9590     500
Permanent Ineff=
       T       F
#Block Obstruct= 1 ,-1
    5996 6489.99   464.8
Bank Sta=5738,5902
XS Rating Curve= 0 ,0
Exp/Cntr=0.3,0.1

Type RM Length L Ch R = 1 ,118069  ,1399,1440,330
BEGIN DESCRIPTION:
This cross section corresponds to cross section 118100 of the non-georeferenced CDC model which was the source of this model.
END DESCRIPTION:
XS GIS Cut Line= 6
  2395760.713111 6979297.4298475 2395766.7639479 6976982.2934958
 2395763.2915139 6975860.7658832 2395770.2360538 6975242.7103608
 2395463.3783998 6970504.2119638      2395452.19      6970348.02
#Sta/Elev= 30
    1000  494.75 1038.75     478 1489.33     480 1771.69     462 1965.04     458
 1973.14     458 1976.69     466 2035.09   468.8  3172.3     488  3742.2     500
  4216.6     500  4284.6     480  4570.7     484 4592.66  476.68  4662.9  476.68
    4749     448    4900     470    5211     466    5825     469 5927.01     446
 5936.54   432.9 5952.36   432.9 5969.27  447.08 6076.95     466  6521.7     460
 6552.17     470 6608.18     472    7504     484 8820.07     478 9959.48   497.8
#Mann= 7 ,-1,0
    1000     .08       0  3172.3     .04       0  4662.9    .055       0
    4900     .08       0    5211     .13       0    5825     .06       0
 6076.95     .13       0
#XS Ineff= 2 ,-1
    1000    4565     500    6531 9959.48     500
Permanent Ineff=
       T       T
Bank Sta=5825,6076.95
XS Rating Curve= 0 ,0
Exp/Cntr=0.3,0.1

Type RM Length L Ch R = 1 ,116629  ,595,612,140
BEGIN DESCRIPTION:
This cross section corresponds to cross section 116664 of the non-georeferenced CDC model which was the source of this model.
END DESCRIPTION:
XS GIS Cut Line= 5
  2396589.089219 6979403.0000038  2396589.255085  6979334.663463
 2396600.1057852 6974864.1773252 2395853.5780788 6974100.2884331
 2395449.8452904 6970257.0592429
#Sta/Elev= 30
    1000  498.22 1058.29     494 1071.33     486 1159.07     486 1240.91  478.25
 1581.06     480  1736.4     490 2170.07  479.22 2208.81     476 2237.19     466
 2411.38     466 2619.58     508 3789.23  511.06 4055.85     508 4305.89     464
 4726.63     462 5146.23     470 5251.18     448 5300.52   431.6 5382.09   431.6
    5435     448    5463     464    6425     466    6949     460 7104.06     466
 7154.89     474 7443.08     472 7877.16     482 9305.03     47810471.31  497.81
#Mann= 3 ,-1,0
    1000     .08       0 5146.23     .06       0    5463     .13       0
#XS Ineff= 2 ,-1
    1000    4430     520    716310471.31     520
Permanent Ineff=
       T       T
Bank Sta=5146.23,5463
XS Rating Curve= 0 ,0
Exp/Cntr=0.3,0.1

Type RM Length L Ch R = 1 ,116017  ,1064,3493,1757
BEGIN DESCRIPTION:
This cross section corresponds to cross section 116053 of the non-georeferenced CDC model which was the source of this model.
----------------------------------
CDC ARL021910-1 ARLINGTON LANDFILL
CROSS-SECTION 116053-125562
DOWNSTREAM END
----------------------------------
END DESCRIPTION:
XS GIS Cut Line= 6
2397836.890235056979581.69371645  2397880.702198 6975931.9566695
   2397887.63011   6975354.82989   2396011.94784   6974211.57791
 2395930.1309836  6973631.1198982395477.915836636970422.83352345
#Sta/Elev= 30
    1050     490    4700     473    4766   465.4    4904   462.3    4978   465.7
    5130     467    5256   465.8    5438   467.8    5849   467.9    6013   464.6
    6067     431    6097   431.4    6106   433.7    6108     436    6152     443
    6214   466.8    6369   465.6    6476   462.5    6578   463.1    6714   467.3
    6825   465.4    6932   467.4    7315     465    7675   466.2    7824   463.1
    7954   463.1    8212     465    8275   469.6    8300   473.9   11300     490
#Mann= 3 ,0,0
    1050     .08       0    6013    .055       0    6214     .13       0
#XS Ineff= 2 ,-1
    1050    4700     490    8300   11300     490
Permanent Ineff=
       F       F
Bank Sta=6013,6214
XS Rating Curve= 0 ,0
Exp/Cntr=0.3,0.1

Type RM Length L Ch R = 1 ,112524  ,139,827,888
BEGIN DESCRIPTION:
This cross section corresponds to cross section 112574 of the non-georeferenced CDC model which was the source of this model.
Cross Section Truncated due to Ineffective Flow Areas
END DESCRIPTION:
XS GIS Cut Line= 6
      2398360.36      6979849.11      2398377.95      6975948.18
     2398375.625     6975269.703 2397355.0711938 6972774.1297082
 2397228.1415286 6972463.7469723  2396754.994459 6971306.7543835
#Sta/Elev= 30
    1050     490    4950   470.7    4976   470.1    5047   462.8    5510   466.4
    5672   465.5    6226   470.8    6307   468.2    6375   469.8    6650   468.6
    6705   464.5    6977   468.9    7243   468.7    7423   464.2    7863   465.5
    8000   467.2    8032   451.8    8059   442.3    8076   430.9    8120     429
    8135   436.6    8142   442.4    8221   468.2    8225   470.3    8253   468.9
    8280   465.1    8515   465.1    8569   469.4    8654   467.9    9910     508
#Mann= 4 ,-1,0
    1050     .08       0    7863     .12       0    8000     .05       0
    8221     .12       0
#XS Ineff= 2 ,-1
    1050    4950     490    8860    9910     520
Permanent Ineff=
       F       F
Bank Sta=8000,8221
XS Rating Curve= 0 ,0
Exp/Cntr=0.3,0.1

Type RM Length L Ch R = 1 ,111697  ,118,381,189
BEGIN DESCRIPTION:
This cross section corresponds to cross section 111679 of the non-georeferenced CDC model which was the source of this model.
END DESCRIPTION:
XS GIS Cut Line= 6
     2398438.216     6979837.937     2398429.536     6975250.264
     2398328.751     6974137.508     2398326.893     6973214.789
     2398174.252     6972585.482      2397691.47     6971969.229
#Sta/Elev= 30
    1050     484    4950   470.7    5047   462.8    6210   469.1    6378   467.5
    6434   463.5    6485   464.9    6543   462.5    6960   465.9    7409   462.5
    7819   466.9    7920   466.7    7942   463.9    7972   442.1    7995     432
    8045     429    8050   431.5    8054   442.1    8109   464.3    8143   462.2
    8275     466    8628   465.2    8657   469.2    8701   464.4    9026   466.7
    9038   468.3    9040   472.9    9053   478.4    9056   483.2    9090   492.7
#Mann= 3 ,0,0
    1050     .08       0    7942     .05       0    8109      .1       0
#XS Ineff= 1 ,-1
    1050    4950     490
Permanent Ineff=
       F
Bank Sta=7942,8109
XS Rating Curve= 0 ,0
Exp/Cntr=0.3,0.1

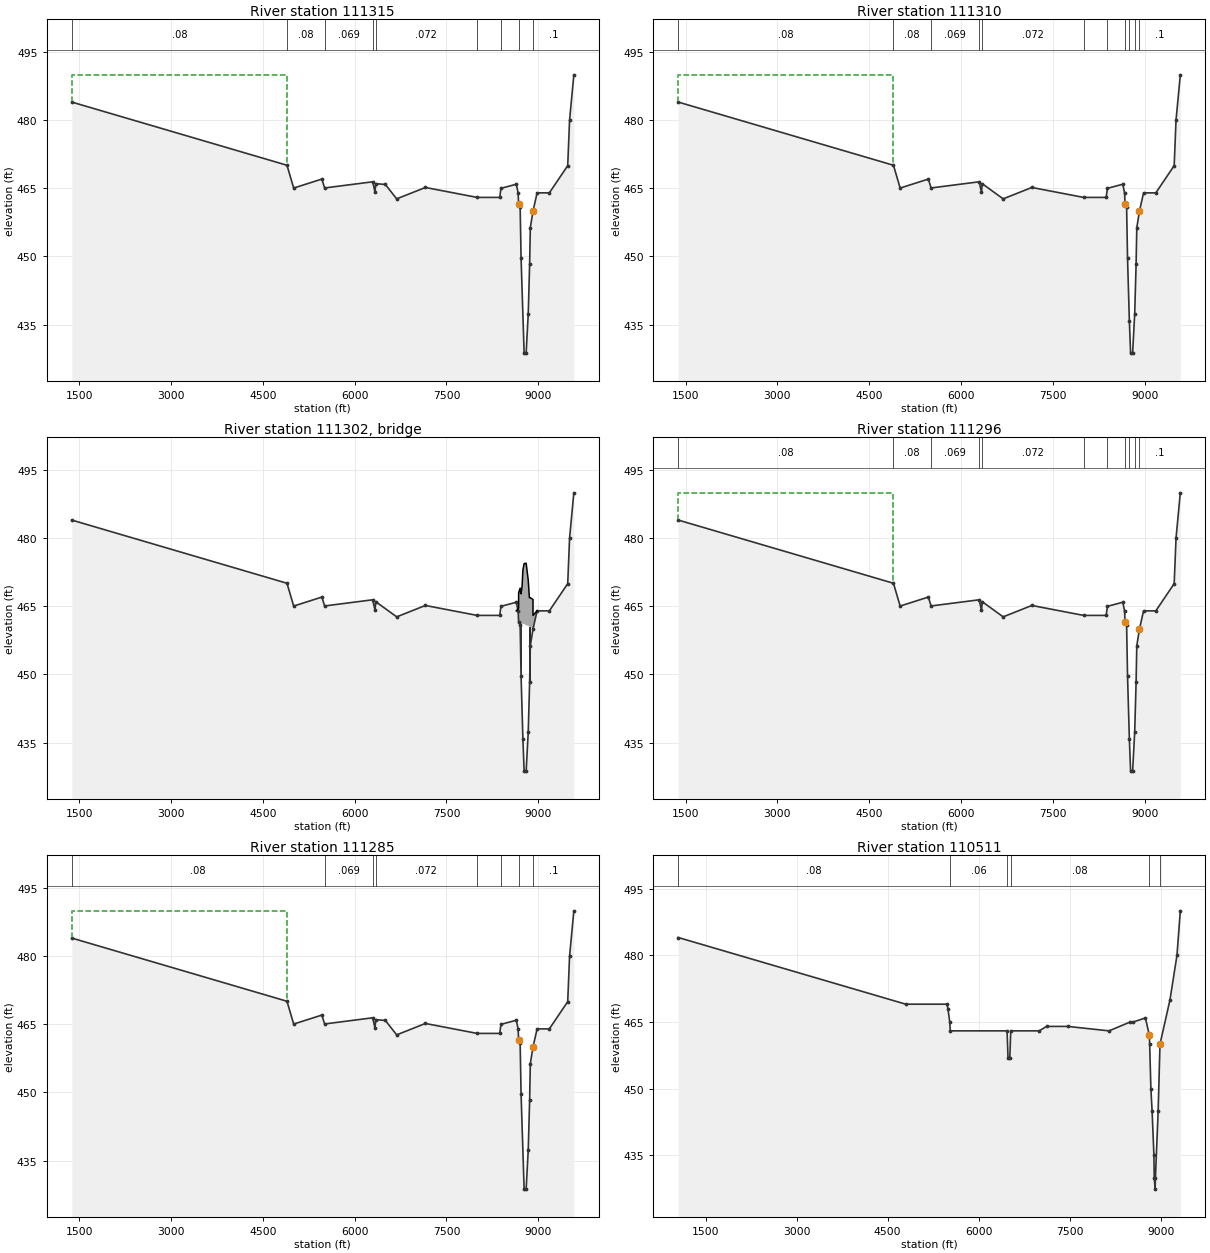
Type RM Length L Ch R = 1 ,111315  ,6,6,6
BEGIN DESCRIPTION:
This cross section corresponds to cross section 111255 of the non-georeferenced CDC model which was the source of this model.
END DESCRIPTION:
XS GIS Cut Line= 5
     2398630.233      6979908.03     2398629.332     6973733.511
     2398633.939     6972634.264      2398394.66     6972660.029
     2397863.089     6972175.199
#Sta/Elev= 30
 1380.36     484 4895.36  470.08 5004.44  465.06 5465.21  467.04 5509.63  465.08
 6294.85  466.44 6332.56  464.16 6345.13  466.02 6501.21  465.86 6686.76  462.68
  7155.7  465.19    8000     463    8369     463    8390     465    8640   465.9
    8670     464    8678   461.5    8703   460.9    8718   449.7    8768   428.7
    8801   428.7    8835   437.3    8858   448.3    8869   456.3    8913     460
    8980     464    9180     464    9480     470    9510     480    9580     490
#Mann= 9 ,-1,0
 1380.36     .08       0 4895.36     .08       0 5509.63    .069       0
 6294.85    .063       0 6345.13    .072       0    8000     .08       0
    8390     .08       0    8678     .05       0    8913      .1       0
#XS Ineff= 1 ,-1
 1380.36 4895.36     490
Permanent Ineff=
       F
Bank Sta=8678,8913
XS Rating Curve= 0 ,0
Exp/Cntr=0.3,0.1

Type RM Length L Ch R = 1 ,111310  ,14,14,14
BEGIN DESCRIPTION:
This cross section corresponds to cross section 111250 of the non-georeferenced CDC model which was the source of this model.
END DESCRIPTION:
XS GIS Cut Line= 5
     2398634.507     6979908.253     2398633.369     6973729.605
     2398637.975     6972630.358     2398397.013     6972653.605
     2397867.326     6972166.018
#Sta/Elev= 30
 1380.36     484 4895.36  470.08 5004.44  465.06 5465.21  467.04 5509.63  465.08
 6294.85  466.44 6332.56  464.16 6345.13  466.02 6686.76  462.68  7155.7  465.19
    8000     463    8369     463    8390     465    8640   465.9    8670     464
    8678   461.5    8703   460.9    8718   449.7    8748   435.8    8768   428.7
    8801   428.7    8835   437.3    8858   448.3    8869   456.3    8913     460
    8980     464    9180     464    9480     470    9510     480    9580     490
#Mann= 11 ,-1,0
 1380.36     .08       0 4895.36     .08       0 5509.63    .069       0
 6294.85    .063       0 6345.13    .072       0    8000     .08       0
    8390     .08       0    8678     .03       0    8748     .05       0
    8835     .03       0    8913      .1       0
#XS Ineff= 1 ,-1
 1380.36 4895.36     490
Permanent Ineff=
       F
Bank Sta=8678,8913
XS Rating Curve= 0 ,0
Exp/Cntr=0.3,0.1

Type RM Length L Ch R = 3 ,111302  ,,,
BEGIN DESCRIPTION:
River Legacy Parks Pedestrian Bridge
END DESCRIPTION:
Node Name=River Legacy Par
Bridge Culvert--1,0,-1,-1, 0
Deck Dist Width WeirC Skew NumUp NumDn MinLoCord MaxHiCord MaxSubmerge Is_Ogee
0.5,12,2.6,0, 16, 16, , , 0.95, 0, 0,0,,
    8640    8678  8678.1    8703    8712    8718    8735    8748    8768    8801
    8835    8854    8869    8913    8913    8980
     464   464.6     468     469   467.8  467.75   469.5     473   474.4   474.5
   470.8   466.9   466.9   466.5     463     464
     464   461.6   461.6   461.5   461.4   461.4  461.25  461.15   461.1   460.8
   460.7   460.5   460.4   460.1   460.1     464
    8640    8678  8678.1    8703    8712    8718    8735    8748    8768    8801
    8835    8854    8869    8913    8913    8980
     464   464.6     468     469   467.8  467.75   469.5     473   474.4   474.5
   470.8   466.9   466.9   466.5     463     464
     464   461.6   461.6   461.5   461.4   461.4  461.25  461.15   461.1   460.8
   460.7   460.5   460.4   460.1   460.1     464
Pier Skew, UpSta & Num, DnSta & Num=  ,8718, 2 ,8718, 2 , 0 , 0 , 0 ,,
       5       5
     454   461.4
       5       5
     454   461.4
Pier Skew, UpSta & Num, DnSta & Num=  ,8858, 2 ,8858, 2 , 0 , 0 , 0 ,,
       5       5
   448.3   463.4
       5       5
   448.3   463.4
BR Coef=-1 , 0 , 0 ,, 0 ,,,0.8,-1,,0,
WSPro=,,,, 1 ,,,, 0 ,,,, 0 ,,,,-1 ,-1 ,-1 , 0 , 0 , 0 , 0 , 0
BC Design=,, 0 ,, 0 ,,,,,,
BC Use User HTab Curves=0
BC User HTab FreeFlow(D)= 0

Type RM Length L Ch R = 1 ,111296  ,11,11,11
BEGIN DESCRIPTION:
This cross section corresponds to cross section 111210 of the non-georeferenced CDC model which was the source of this model.
END DESCRIPTION:
XS GIS Cut Line= 5
     2398643.801     6979883.872     2398636.207     6973725.329
     2398640.156     6972620.358     2398401.527     6972639.716
     2397886.857     6972152.997
#Sta/Elev= 30
 1380.36     484 4895.36  470.08 5004.44  465.06 5465.21  467.04 5509.63  465.08
 6294.85  466.44 6332.56  464.16 6345.13  466.02 6686.76  462.68  7155.7  465.19
    8000     463    8369     463    8390     465    8640   465.9    8670     464
    8678   461.5    8703   460.9    8718   449.7    8748   435.8    8768   428.7
    8801   428.7    8835   437.3    8858   448.3    8869   456.3    8913     460
    8980     464    9180     464    9480     470    9510     480    9580     490
#Mann= 11 ,-1,0
 1380.36     .08       0 4895.36     .08       0 5509.63    .069       0
 6294.85    .063       0 6345.13    .072       0    8000     .08       0
    8390     .08       0    8678     .03       0    8748     .05       0
    8835     .03       0    8913      .1       0
#XS Ineff= 1 ,-1
 1380.36 4895.36     490
Permanent Ineff=
       F
Bank Sta=8678,8913
XS Rating Curve= 0 ,0
Exp/Cntr=0.3,0.1

Type RM Length L Ch R = 1 ,111285  ,512,773,736
BEGIN DESCRIPTION:
This cross section corresponds to cross section 111205 of the non-georeferenced CDC model which was the source of this model.
END DESCRIPTION:
XS GIS Cut Line= 5
     2398650.654     6979878.201     2398643.082      6973699.94
     2398646.483     6972609.438      2398403.35     6972630.775
     2397895.972     6972147.789
#Sta/Elev= 30
 1380.36     484 4895.36  470.08 5004.44  465.06 5465.21  467.04 5509.63  465.08
 6294.85  466.44 6332.56  464.16 6345.13  466.02 6501.21  465.86 6686.76  462.68
  7155.7  465.19    8000     463    8369     463    8390     465    8640   465.9
    8670     464    8678   461.5    8703   460.9    8718   449.7    8768   428.7
    8801   428.7    8835   437.3    8858   448.3    8869   456.3    8913     460
    8980     464    9180     464    9480     470    9510     480    9580     490
#Mann= 8 ,-1,0
 1380.36     .08       0 5509.63    .069       0 6294.85    .063       0
 6345.13    .072       0    8000     .08       0    8390     .08       0
    8678     .05       0    8913      .1       0
#XS Ineff= 1 ,-1
 1380.36 4895.36     490
Permanent Ineff=
       F
Bank Sta=8678,8913
XS Rating Curve= 0 ,0
Exp/Cntr=0.3,0.1

Type RM Length L Ch R = 1 ,110511  ,102,312,306
BEGIN DESCRIPTION:
This cross section corresponds to cross section 110515 of the non-georeferenced CDC model which was the source of this model.
Old roadway embankment lowered to 463.  Far LOB of Section based on 2006 topography.
END DESCRIPTION:
XS GIS Cut Line= 6
2398721.547929446979816.53625506      2398710.94      6974626.13
 2399241.3734685 6972661.1961669 2399001.9766376 6972197.6829863
 2398948.6267588 6971842.0358703       2398931.7      6971674.89
#Sta/Elev= 30
    1050     484    4800     469    5480     469    5495     468    5525     465
    5533     463    6470     463    6485     457    6515     457    6530     463
    7000     463    7120     464    7470     464    8150     463    8500     465
    8550     465    8750   465.9    8815     462    8820     460    8840     450
    8860     445    8890     435    8895     430    8910   427.4    8915     430
    8960     445    8990     460    9155     470    9270     480    9325     490
#Mann= 6 ,-1,0
    1050     .08       0    5533     .06       0    6470    .055       0
    6530     .08       0    8815     .05       0    8990      .1       0
#Block Obstruct= 2 , 0
       0    4860                       0
Bank Sta=8815,8990
XS Rating Curve= 0 ,0
Exp/Cntr=0.5,0.3

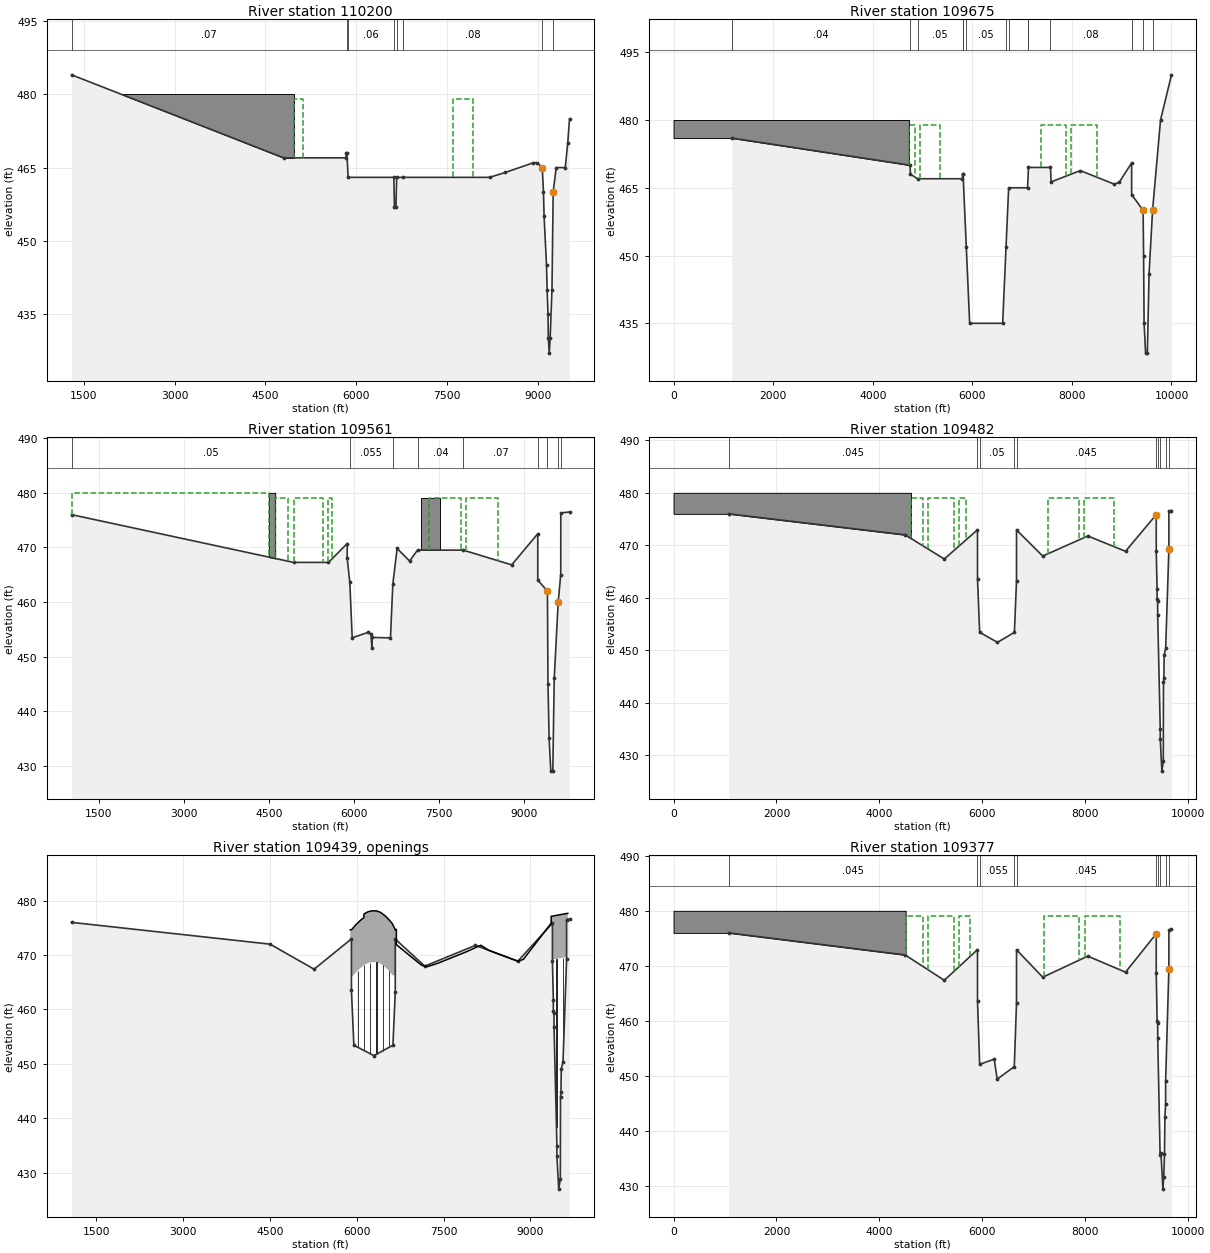
Type RM Length L Ch R = 1 ,110200  ,286,525,510
BEGIN DESCRIPTION:
This cross section corresponds to cross section 110210 of the non-georeferenced CDC model which was the source of this model.
Proposed fill on LOB.  Old roadway embankment lowered to 463.  END RELIEF CHANNEL CUT  X-SECTION BASED ON 1991 SURVEY DATA
END DESCRIPTION:
XS GIS Cut Line= 6
2398799.416713486979757.82384049        2398743.      6974804.24
  2399292.334293  6972885.222883  2399445.115187 6972350.4894392
 2399302.4960497 6972100.9056208 2399216.6191972  6971683.232204
#Sta/Elev= 30
    1300     484    4800     467    5831     467    5835     468    5845     468
    5865     463    6619     463    6630     457    6655     457    6666     463
    6766     463    8200     463    8460     464    8925     466    8990     466
    9070     465    9090     460    9100     455    9140     445    9150     440
    9165     435    9170     430    9185     427    9200     430    9230     440
    9250     460    9300     465    9450     465    9490     470    9520     475
#Mann= 8 ,-1,0
    1300     .07       0    5845     .08       0    5865     .06       0
    6619    .055       0    6666     .06       0    6766     .08       0
    9070     .05       0    9250      .1       0
#XS Ineff= 2 ,-1
    4970    5115     479    7595    7930     479
Permanent Ineff=
       T       T
#Block Obstruct= 2 , 0
       0    4970     480               0
Bank Sta=9070,9250
XS Rating Curve= 0 ,0
Exp/Cntr=0.5,0.3

Type RM Length L Ch R = 1 ,109675  ,242,114,186
BEGIN DESCRIPTION:
This cross section corresponds to cross section 109695 of the non-georeferenced CDC model which was the source of this model.
Proposed fill & lake on LOB.  X-SECTION BASED ON 1991 SURVEY DATA
END DESCRIPTION:
XS GIS Cut Line= 6
2399020.781517296980032.40315107 2399047.8184094 6974489.7801082
 2399205.7186842 6973669.7187562 2399750.7284209 6971963.3799772
 2399715.0733085 6971800.3862087 2399715.0733085 6971306.3120657
#Sta/Elev= 30
    1170     476    4750     470    4758     468    4900     467    5801     467
    5805     468    5815     468    5879     452    5947     435    6610     435
    6678     452    6730     465    7110     465    7128   469.5    7570   469.5
    7582   466.3    8170   468.8    8850   465.8    8950   466.2    9200   470.5
    9200   463.5    9430     460    9440     450    9450     435    9480   428.4
    9515   428.4    9550     446    9620     460    9780     480   10000     490
#Mann= 14 ,-1,0
    1170     .04       0    4750     .07       0    4900     .05       0
    5805     .07       0    5815     .08       0    5879     .05       0
    6678     .08       0    6730     .05       0    7110     .07       0
    7128     .04       0    7570     .08       0    9200     .08       0
    9430     .05       0    9620      .1       0
#XS Ineff= 5 ,-1
    4730    4840     479    4940    5355     479    5800    6800     451
    7385    7890     479    7990    8495     479
Permanent Ineff=
       T       T       T       T       T
#Block Obstruct= 2 , 0
       0    4730     480               0
Bank Sta=9430,9620
XS Rating Curve= 0 ,0
Exp/Cntr=0.5,0.3

Type RM Length L Ch R = 1 ,109561  ,50,79,72
BEGIN DESCRIPTION:
This cross section corresponds to cross section 109585 of the non-georeferenced CDC model which was the source of this model.
35 FT U/S OF F.M. 157 ROADWAY EMBANKMENT
Bldg between relief br and main br
END DESCRIPTION:
XS GIS Cut Line= 6
2399209.392226516980142.60961722 2399253.3003154 6976392.8666821
 2399287.2152403 6973496.5380002 2399796.5701928 6971993.9412678
 2399786.3832052 6971846.2283087 2399941.2867988 6971478.7115445
#Sta/Elev= 30
    1020     476    4935  467.25    5550  467.25    5880   470.7    5880     468
    5926  463.58    5968  453.44    6251  454.44    6301  454.09    6314  451.53
    6322  453.49    6643  453.43    6684  463.25    6760   469.8    6980   467.5
    7120   469.5    7925   469.5    8780   466.8    9240   472.5    9240     464
    9410     462    9420     445    9440     435    9470     429    9505     429
    9530     446    9600     460    9645     465    9646   476.3    9800   476.5
#Mann= 9 ,-1,0
    1020     .05       0    5926    .055       0    6684     .05       0
    7120     .04       0    7925     .07       0    9240    .065       0
    9410    .055       0    9600    .065       0    9646     .07       0
#XS Ineff= 6 ,-1
    4610    4840     479    4940    5450     479    5550    5610     479
    7315    7880     479    7980    8540     479    1020    4500     480
Permanent Ineff=
       T       T       T       T       T       F
#Block Obstruct= 2 ,-1
    4500    4610     480    7185    7510     479
Bank Sta=9410,9600
XS Rating Curve= 0 ,0
Exp/Cntr=0.5,0.3

Type RM Length L Ch R = 1 ,109482  ,155,124,124
BEGIN DESCRIPTION:
This cross section corresponds to cross section 109530 of the non-georeferenced CDC model which was the source of this model.
U/S FACE OF F.M. 157 BRIDGE Surveyed 2006  Main channel n values in channel reflect conc. and gabions.   Relief channel n values in channel reflect conc. slopes.
END DESCRIPTION:
XS GIS Cut Line= 6
2399288.48546073 6980140.8274858 2399327.9638465 6974041.5477369
 2399501.1442744 6973007.5573508 2399562.2668556 6972783.4413292
 2399628.4832586 6972523.6701952 2399956.6672794 6971624.8928634
#Sta/Elev= 30
    1070     476    4500     472    5261   467.4    5906  472.96  5906.1  463.58
    5948  453.44    6294  451.53    6623  453.43 6663.87  463.25    6664  472.93
    7174  467.96    8049  471.78    8782  468.87    9379  475.85    9379  468.86
    9395  461.73    9395  459.71    9406  459.38    9407  456.74    9457  434.97
    9457  433.08    9488  427.01    9516  428.87    9519  443.91    9527  444.82
    9532  449.07    9562   450.4    9624  469.21    9624  476.52    9675  476.62
#Mann= 10 ,-1,0
    1070    .045       0    5906     .02       0    5948     .05       0
    6623     .02       0    6664    .045       0    9379     .02       0
    9407     .03       0    9457    .055       0    9562     .02       0
    9624    .045       0
#XS Ineff= 5 ,-1
    4615    4840     479    4940    5450     479    5550    5675     479
    7280    7870     479    7970    8565     479
Permanent Ineff=
       T       T       T       T       T
#Block Obstruct= 2 , 0
       0    4615     480               0
Bank Sta=9379,9624
XS Rating Curve= 0 ,0
Exp/Cntr=0.5,0.3

Type RM Length L Ch R = 4 ,109439  ,,,
BEGIN DESCRIPTION:
F.M. 157
NEW X-SECTION BASED ON 1991 SURVEY DATA AND COE BRIDGE SECTIONS
D/S FACE OF WIDENED AND REALIGNED F.M. 157 BRIDGE
END DESCRIPTION:
Node Name=FM 157
Bridge Culvert--1,0,-1,-1, 0
Deck Dist Width WeirC Skew NumUp NumDn MinLoCord MaxHiCord MaxSubmerge Is_Ogee
0.5,123,2.6,0, 31, 31, , , 0.95, 0, 0,0,,
    5886    5906    5986    6059    6122    6122    6194    6263    6339    6407
    6478    6545    6614 6663.87    6683    6683    7072    7123    7174    7224
    7394    7900    8141    8279    8782    8878    9358    9358    9379    9624
    9645
  474.63  474.63   475.6  476.35  476.88  477.54  477.96  478.12  478.11  477.85
  477.29  476.61  475.75  474.61  474.73   471.9  468.52  468.11  467.96  467.89
  468.47  470.63  471.81  470.87  468.87  469.21  475.85  477.13  477.15  477.63
  477.65
     465  465.87  466.84  467.59  468.12  468.12  468.54   468.7  468.69  468.43
  467.87  467.19  466.33  466.19  466.19     465     465     465     465     465
     465     465     465     465     465     465     465     465  469.15  469.63
     465
    5886    5906    5986    6059    6122    6122    6194    6263    6339    6407
    6478    6545    6614 6663.87    6683    6683    7072    7123    7174    7224
    7394    7900    8141    8279    8782    8878    9358    9358    9379    9624
    9645
  474.63  474.63   475.6  476.35  476.88  477.54  477.96  478.12  478.11  477.85
  477.29  476.61  475.75  474.61  474.73   471.9  468.52  468.11  467.96  467.89
  468.47  470.63  471.81  470.87  468.87  469.21  475.85  477.13  477.15  477.63
  477.65
     465  465.87  466.84  467.59  468.12  468.12  468.54   468.7  468.69  468.43
  467.87  467.19  466.33  466.19  466.19     465     465     465     465     465
     465     465     465     465     465     465     465     465  469.15  469.63
     465
Pier Skew, UpSta & Num, DnSta & Num=  ,6015.91, 2 ,6015.91, 2 , 0 , 0 , 0 ,,
    3.28    3.28
  419.95     468
    3.28    3.28
  419.95     468
Pier Skew, UpSta & Num, DnSta & Num=  ,6124.18, 2 ,6124.18, 2 , 0 , 0 , 0 ,,
    3.28    3.28
  419.95   469.8
    3.28    3.28
  419.95   469.8
Pier Skew, UpSta & Num, DnSta & Num=  ,6232.44, 2 ,6232.44, 2 , 0 , 0 , 0 ,,
    3.28    3.28
  413.39   469.8
    3.28    3.28
  413.39   469.8
Pier Skew, UpSta & Num, DnSta & Num=  ,6340.71, 2 ,6340.71, 2 , 0 , 0 , 0 ,,
    3.28    3.28
  413.39   469.8
    3.28    3.28
  413.39   469.8
Pier Skew, UpSta & Num, DnSta & Num=  ,6448.98, 2 ,6448.98, 2 , 0 , 0 , 0 ,,
    3.28    3.28
  413.39   469.8
    3.28    3.28
  413.39   469.8
Pier Skew, UpSta & Num, DnSta & Num=  ,6557.25, 2 ,6557.25, 2 , 0 , 0 , 0 ,,
    3.28    3.28
  413.39   469.8
    3.28    3.28
  413.39   469.8
Pier Skew, UpSta & Num, DnSta & Num=  ,9449, 2 ,9449, 2 , 0 , 0 , 0 ,,
       3       3
     445   469.8
       3       3
     445   469.8
Pier Skew, UpSta & Num, DnSta & Num=  ,9555, 2 ,9555, 2 , 0 , 0 , 0 ,,
       3       3
     450   469.8
       3       3
     450   469.8
BR Coef= 0 , 0 , 1 ,1.05, 0 ,,,0.8,0,1.2,2,468.7
WSPro=,,,, 1 ,,,, 0 ,,,, 0 ,,,,-1 ,-1 ,-1 , 0 , 0 , 0 , 0 , 0
BR Coef= 0 , 0 , 1 ,1.05, 0 ,,,0.8006408,0,1.2,2,469.63
WSPro=,,,, 1 ,,,, 0 ,,,, 0 ,,,,-1 ,-1 ,-1 , 0 , 0 , 0 , 0 , 0
BC Mult= 3 ,1070,8141,1070,8141
BC Mult= 3 ,8141,9675,8141,9675
BC Design=,, 0 ,, 0 ,,,,,,
BC HTab HWMax=476.5
BC Use User HTab Curves=0
BC User HTab FreeFlow(D)= 0

Type RM Length L Ch R = 1 ,109377  ,24,24,24
BEGIN DESCRIPTION:
This cross section corresponds to cross section 109405 of the non-georeferenced CDC model which was the source of this model.
D/S FACE OF F.M. 157 BRIDGE Surveyed 2006  Main channel n values in channel reflect conc. and gabions.  Relief channel n values in channel reflect conc. slopes.
END DESCRIPTION:
XS GIS Cut Line= 6
2399338.723732596980154.00726031 2399455.3025026  6973975.331662
 2399485.8637932 6973654.4382749 2399582.6411587 6973134.8960069
 2399776.1958897 6972391.2380454 2400063.8544932 6971638.3539461
#Sta/Elev= 30
    1070     476    4500     472    5261   467.4    5906  472.96  5906.1  463.58
    5948  452.15    6230   453.1    6289  449.47    6621  451.74 6663.87  463.25
    6664  472.93    7174  467.96    8049  471.78    8782  468.87    9379  475.85
    9379   468.7    9396  459.95    9407  459.62    9408  456.91    9454  435.71
    9471  436.09    9508  429.52    9525  431.77    9539  435.87    9547  442.58
    9561  444.91    9561  449.11    9624  469.38    9624  476.52    9675  476.62
#Mann= 10 ,-1,0
    1070    .045       0    5906     .02       0    5948    .055       0
    6621     .02       0    6664    .045       0    9379     .02       0
    9408     .03       0    9454    .055       0    9561     .02       0
    9624    .045       0
#XS Ineff= 5 ,-1
    4510    4840     479    4940    5450     479    5550    5765     479
    7195    7885     479    7985    8675     479
Permanent Ineff=
       T       T       T       T       T
#Block Obstruct= 2 , 0
       0    4510     480               0
Bank Sta=9379,9624
XS Rating Curve= 0 ,0
Exp/Cntr=0.5,0.3