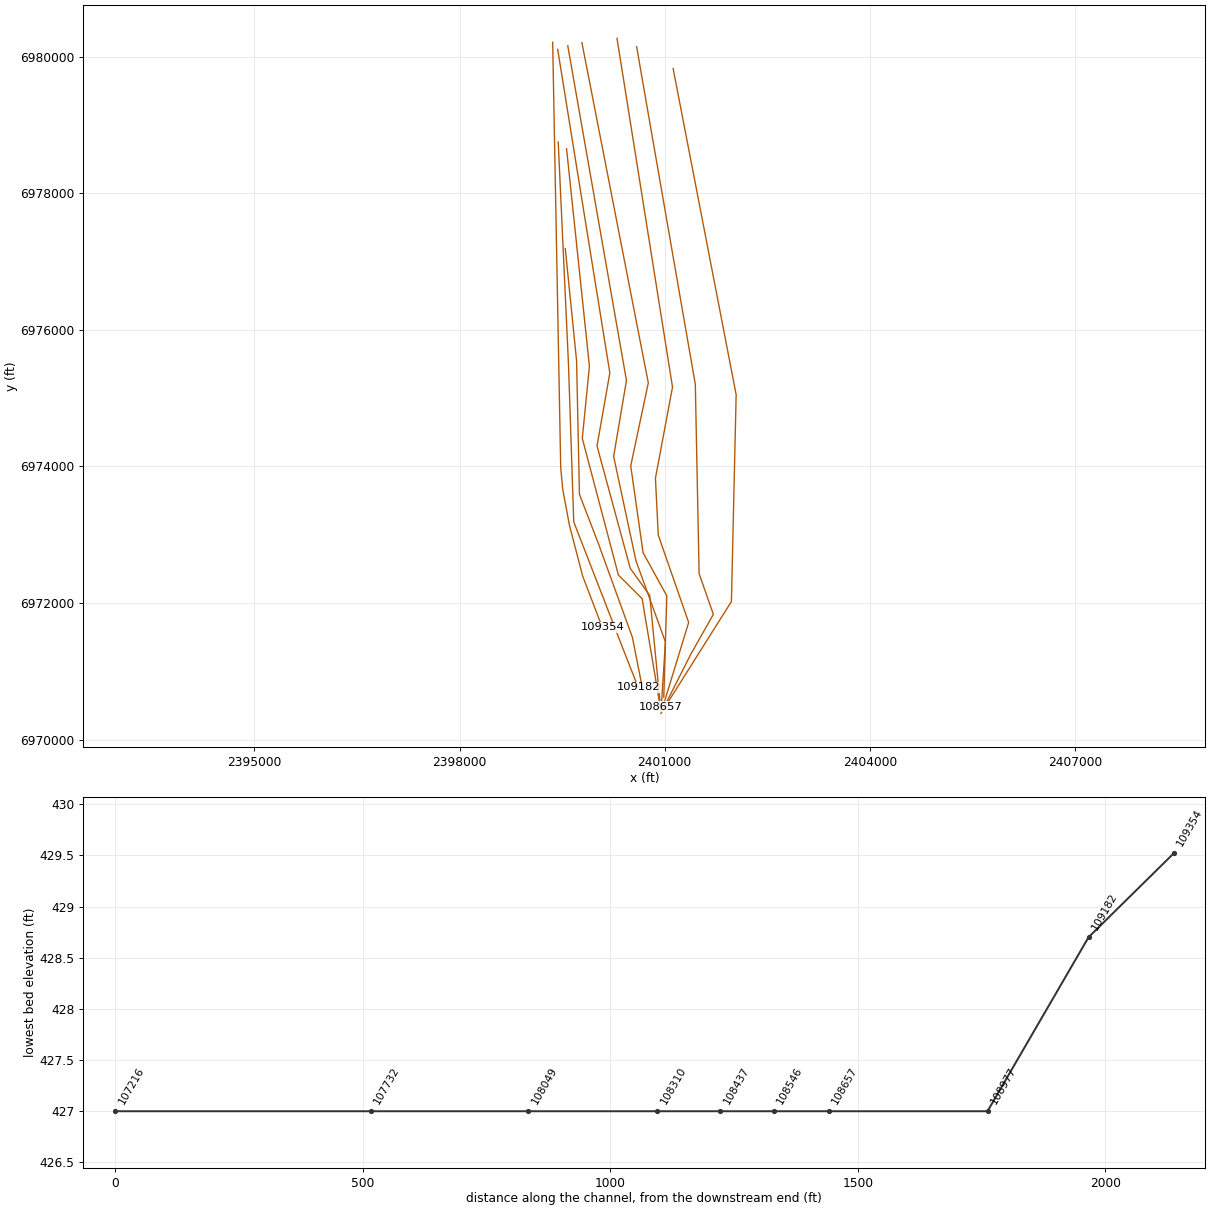
HEC-RAS study CDC_Consolidated_Model.prj: Upper Trinity CDC Consolidated Model

--- CDC_Consolidated_Model.g04 (geometry) --- (continued)

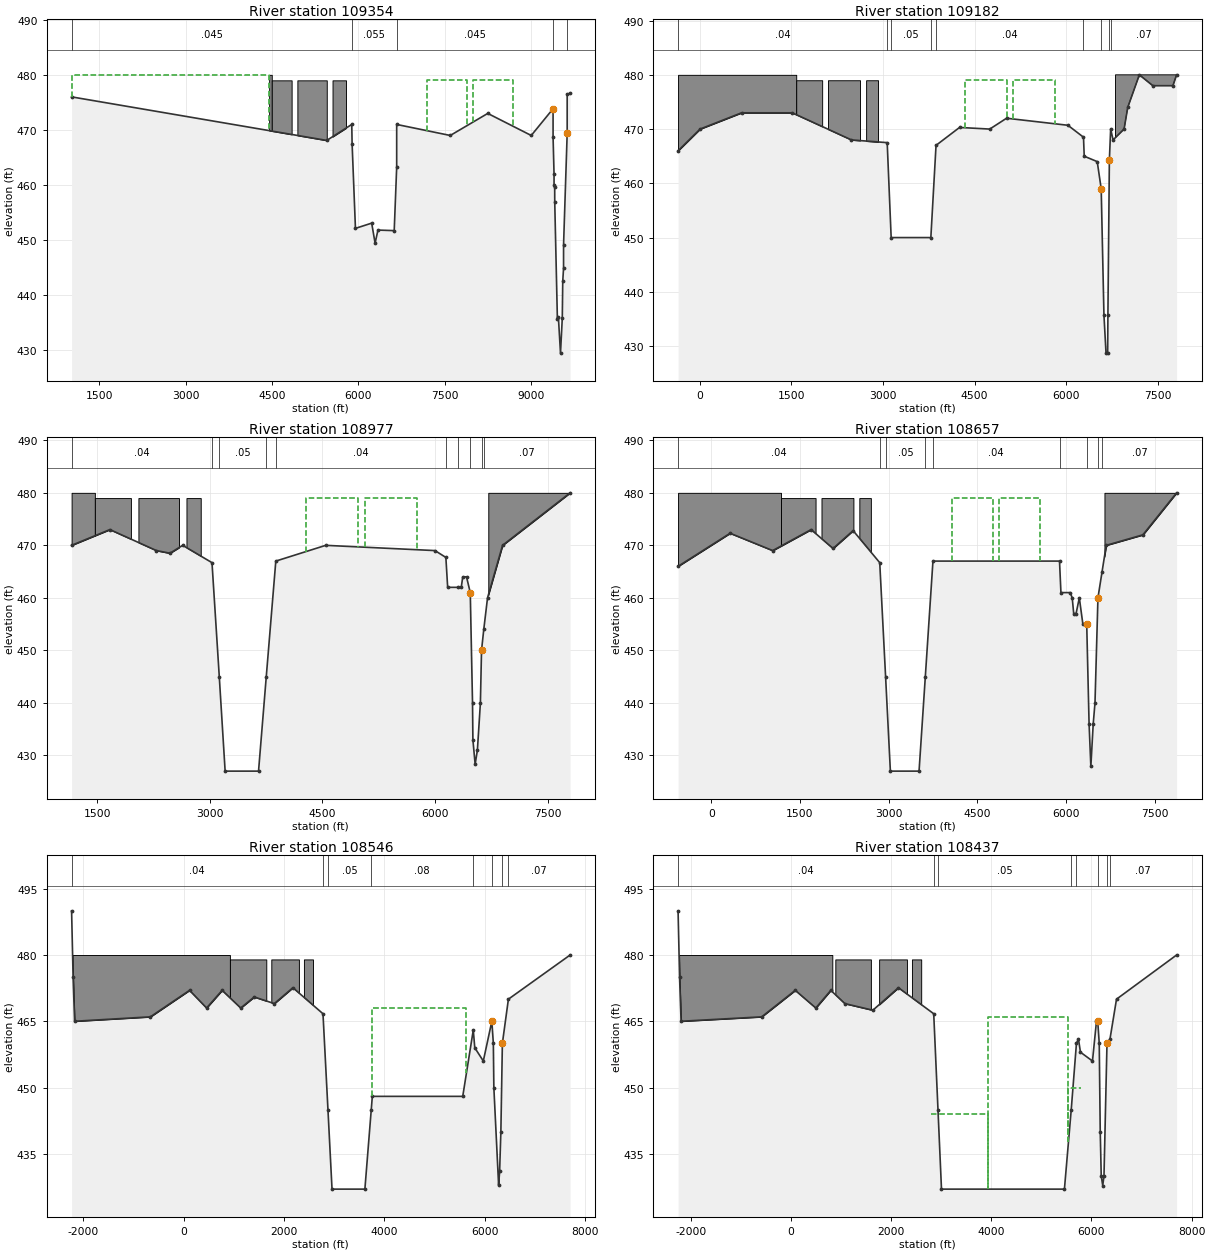
Type RM Length L Ch R = 1 ,109354  ,109,172,172
BEGIN DESCRIPTION:
This cross section corresponds to cross section 109385 of the non-georeferenced CDC model which was the source of this model.
20 FT D/S OF F.M. 157 ROADWAY EMBANKMENT  Flow limit 4495  X-SECTION BASED ON 1991 SURVEY DATA
END DESCRIPTION:
XS GIS Cut Line= 6
 2399361.27148956980208.07590398 2399478.7934841 6973979.4092031
 2399509.3547747 6973658.5158161 2399606.1321402  6973138.973548
 2399799.6868712 6972395.3155865 2400087.3454747 6971642.4314873
#Sta/Elev= 30
    1020     476    5450   468.1    5884     471    5890   467.5    5948  452.15
    6230   453.1    6289  449.47    6339  451.84    6621  451.74    6664  463.25
    6664     471    7594     469    8245     473    9000     469    9379  473.85
    9379   468.7    9396  461.96    9396  459.95    9407  459.62    9408  456.91
    9454  435.71    9471  436.09    9508  429.52    9539  435.87    9547  442.58
    9561  444.91    9561  449.11    9624  469.38    9624  476.52    9675  476.62
#Mann= 5 ,-1,0
    1020    .045       0    5890    .055       0    6664    .045       0
    9379    .055       0    9624     .12       0
#XS Ineff= 3 ,-1
    7195    7885     479    7985    8675     479    1020    4450     480
Permanent Ineff=
       T       T       F
#Block Obstruct= 4 ,-1
    4450    4495     480    4495    4840     479    4940    5450     479
    5550    5784     479
Bank Sta=9379,9624
XS Rating Curve= 0 ,0
Exp/Cntr=0.5,0.3

Type RM Length L Ch R = 1 ,109182  ,119,204,200
BEGIN DESCRIPTION:
This cross section corresponds to cross section 109220 of the non-georeferenced CDC model which was the source of this model.
Proposed fill on LOB.  Flow limit 1580  LOB from 2001 aerial topo.
ROB of X-SECTION BASED ON 1991 AND 2001 SURVEY DATA
END DESCRIPTION:
XS GIS Cut Line= 6
2399442.385553776978747.88510128      2399455.53      6978462.66
     2399592.973     6975480.245     2399669.362     6973188.578
     2400426.307     6971237.189      2400612.34      6970764.59
#Sta/Elev= 30
    -355     466       5     470     685     473    1515     473    2485     468
    3070   467.5    3135     450    3785     450    3870     467    4255   470.3
    4750     470    5025     472    6030   470.7    6285   468.5    6297     465
    6510     464    6575     459    6620   435.7    6654   428.7    6681   428.8
    6685   435.7    6709   464.3    6730     470    6770     468    6950     470
    7010     474    7200     480    7420     478    7750     478    7810     480
#Mann= 9 ,-1,0
    -355     .04       0    3070     .08       0    3135     .05       0
    3785     .08       0    3870     .04       0    6285    .065       0
    6575    .055       0    6709     .12       0    6730     .07       0
#XS Ineff= 2 ,-1
    4340    5030     479    5130    5820     479
Permanent Ineff=
       T       T
#Block Obstruct= 5 ,-1
    -355    1580     480    1580    2005     479    2100    2625     479
    2725    2920     479    6810    8000     480
Bank Sta=6575,6709
XS Rating Curve= 0 ,0
Exp/Cntr=0.5,0.3

Type RM Length L Ch R = 1 ,108977  ,125,321,306
BEGIN DESCRIPTION:
This cross section corresponds to cross section 109005 of the non-georeferenced CDC model which was the source of this model.
Proposed fill & lake on LOB.  Flow limit 1470  LOB from 2001 aerial topo.  ROB of X-SECTION BASED ON 1991 AND 2001 SURVEY DATA
END DESCRIPTION:
XS GIS Cut Line= 6
2399545.623881226977189.59776567     2399711.029     6975542.745
     2399752.696     6973591.356     2400027.484     6972877.343
     2400527.214     6971498.087       2400681.6      6970712.14
#Sta/Elev= 30
    1160     470    1670     473    2290     469    2470   468.5    2640     470
    3030   466.7    3127     445    3205     427    3650     427    3753     445
    3880     467    4545     470    6000     469    6145   467.7    6169     462
    6300     462    6350     462    6370     464    6420     464    6470     461
    6500     440    6505     433    6535   428.3    6565     431    6605     440
    6620     450    6650     454    6700     460    6900     470    7800     480
#Mann= 10 ,-1,0
    1160     .04       0    3030     .08       0    3127     .05       0
    3753     .08       0    3880     .04       0    6145     .07       0
    6300    .065       0    6470    .055       0    6620     .12       0
    6650     .07       0
#XS Ineff= 3 ,-1
    3000    3800     444    4280    4970     479    5070    5760     479
Permanent Ineff=
       T       T       T
#Block Obstruct= 5 ,-1
    1160    1470     480    1470    1950     479    2050    2590     479
    2690    2880     479    6710    8000     480
Bank Sta=6470,6620
XS Rating Curve= 0 ,0
Exp/Cntr=0.5,0.3

Type RM Length L Ch R = 1 ,108657  ,251,111,101
BEGIN DESCRIPTION:
This cross section corresponds to cross section 108685 of the non-georeferenced CDC model which was the source of this model.
Proposed fill & lake on LOB.  Flow limit 1180  LOB from 2001 aerial topo.  ROB of X-SECTION BASED ON 1991 AND 2001 SURVEY DATA
END DESCRIPTION:
XS GIS Cut Line= 6
      2399564.31      6978649.21     2399898.529     6975466.356
     2399794.362       6974410.8      2400322.14       6972410.8
     2400669.362     6972063.5782400934.385038086970481.20704212
#Sta/Elev= 30
    -560     466     320   472.3    1040     469    1690     473    2060   469.4
    2400   472.8    2850   466.7    2949     445    3030     427    3515     427
    3621     445    3750     467    5890     467    5914     461    6070     461
    6105     460    6130     457    6170     457    6225     460    6285     455
    6350     455    6390     436    6420   427.9    6460     436    6490     440
    6540     460    6610     465    6680     470    7300     472    7870     480
#Mann= 9 ,-1,0
    -560     .04       0    2850     .08       0    2949     .05       0
    3621     .08       0    3750     .04       0    5890     .09       0
    6350    .055       0    6540     .12       0    6610     .07       0
#XS Ineff= 3 ,-1
    2800    3800     444    4080    4770     479    4870    5560     479
Permanent Ineff=
       T       T       T
#Block Obstruct= 5 ,-1
    -560    1180     480    1180    1765     479    1865    2405     479
    2505    2700     479    6650    8000     480
Bank Sta=6350,6540
XS Rating Curve= 0 ,0
Exp/Cntr=0.5,0.3

Type RM Length L Ch R = 1 ,108546  ,284,108,103
BEGIN DESCRIPTION:
This cross section corresponds to cross section 108570 of the non-georeferenced CDC model which was the source of this model.
Proposed fill & lake on LOB.  Flow limit 920  LOB from 2001 aerial topo.  ROB of X-SECTION BASED ON 1991 AND 2001 SURVEY DATA
END DESCRIPTION:
XS GIS Cut Line= 6
      2399434.49      6980104.83      2400197.14     6975369.134
      2400009.64     6974299.689     2400495.751     6972508.023
     2400780.473     6972112.1892400943.305692966970421.89295229
#Sta/Elev= 30
   -2235     490   -2205     475   -2175     465    -665     466     115     472
     455     468     765     472    1135     468    1405   470.5    1805     469
    2175   472.6    2775   466.7    2874     445    2955     427    3610     427
    3737     445    3758     448    5560     448    5770     463    5800     459
    5970     456    6140     465    6170     460    6180     450    6275   427.9
    6295     431    6320     440    6350     460    6470     470    7700     480
#Mann= 8 ,-1,0
   -2235     .04       0    2775     .08       0    2874     .05       0
    3737     .08       0    5770     .12       0    6140    .055       0
    6350     .12       0    6470     .07       0
#XS Ineff= 2 ,-1
    3758    5634     468    2800    3758     444
Permanent Ineff=
       T       T
#Block Obstruct= 4 ,-1
   -2235     920     480     920    1645     479    1745    2295     479
    2395    2575     479
Bank Sta=6140,6350
XS Rating Curve= 0 ,0
Exp/Cntr=0.5,0.3

Type RM Length L Ch R = 1 ,108437  ,289,127,113
BEGIN DESCRIPTION:
This cross section corresponds to cross section 108465 of the non-georeferenced CDC model which was the source of this model.
Proposed fill & lake on LOB.  Flow limit 825  LOB from 2001 aerial topo.  ROB of X-SECTION BASED ON 1991 AND 2001 SURVEY DATA
END DESCRIPTION:
XS GIS Cut Line= 6
      2399582.02      6980157.94     2400440.196     6975258.023
     2400252.696     6974146.911     2400579.085     6972619.134
      2401009.64     6971431.6342400947.277455846970435.18187862
#Sta/Elev= 30
   -2255     490   -2225     475   -2195     465    -585     466      85     472
     495     468     795     472    1075     469    1635   467.5    2145   472.6
    2850   466.7    2935     445    3005     427    5460     427    5596     445
    5700     460    5740     461    5780     458    6020     456    6100     465
    6125     465    6155     460    6175     440    6195     430    6225   427.8
    6250     430    6310     460    6370     461    6500     470    7700     480
#Mann= 8 ,-1,0
   -2255     .04       0    2850     .08       0    2935     .05       0
    5596     .08       0    5700     .12       0    6125    .055       0
    6310     .12       0    6370     .07       0
#XS Ineff= 3 ,-1
    3938    5541     466    5541    5800     450    2800    3938     444
Permanent Ineff=
       T       T       T
#Block Obstruct= 4 ,-1
   -2255     825     480     885    1595     479    1760    2315     479
    2415    2600     479
Bank Sta=6125,6310
XS Rating Curve= 0 ,0
Exp/Cntr=0.5,0.3

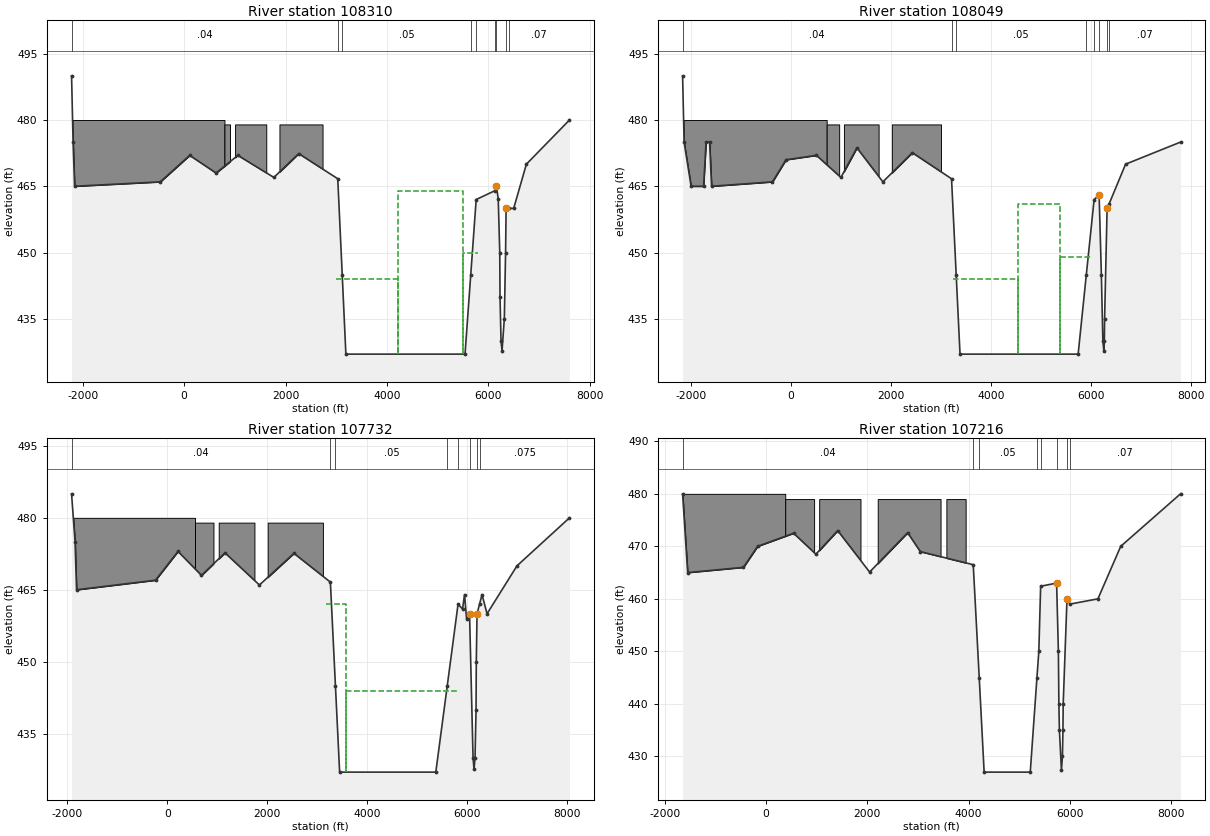
Type RM Length L Ch R = 1 ,108310  ,389,261,256
BEGIN DESCRIPTION:
This cross section corresponds to cross section 108335 of the non-georeferenced CDC model which was the source of this model.
Proposed fill & lake on LOB.  Flow limit 795  LOB from 2001 aerial topo.  ROB of X-SECTION BASED ON 1991 AND 2001 SURVEY DATA
END DESCRIPTION:
XS GIS Cut Line= 6
      2399788.56      6980203.18      2400759.64       6975223.3
     2400502.696     6974008.023     2400683.251     6972737.189
     2401030.473     6972105.2452400985.958658726970623.15565817
#Sta/Elev= 30
   -2220     490   -2190     475   -2160     465    -470     466     110     472
     630     468    1060     472    1770     467    2260   472.4    3030   466.7
    3118     445    3190     427    5540     427    5653     445    5760     462
    6130     464    6145     465    6160     465    6195   462.1    6225     450
    6230     440    6250     430    6270   427.8    6315     435    6340     450
    6350     460    6400     460    6500     460    6750     470    7600     480
#Mann= 9 ,-1,0
   -2220     .04       0    3030     .08       0    3118     .05       0
    5653     .08       0    5760    .085       0    6130     .12       0
    6160    .055       0    6350     .12       0    6400     .07       0
#XS Ineff= 3 ,-1
    4211    5497     464    5497    5800     450    3000    4211     444
Permanent Ineff=
       T       T       T
#Block Obstruct= 4 ,-1
   -2220     795     480     795     905     479    1005    1620     479
    1880    2730     479
Bank Sta=6145,6350
XS Rating Curve= 0 ,0
Exp/Cntr=0.5,0.3

Type RM Length L Ch R = 1 ,108049  ,573,318,365
BEGIN DESCRIPTION:
This cross section corresponds to cross section 108080 of the non-georeferenced CDC model which was the source of this model.
Proposed fill & lake on LOB.  Flow limit 715  LOB from 2001 aerial topo.  ROB of X-SECTION BASED ON 1991 AND 2001 SURVEY DATA
END DESCRIPTION:
XS GIS Cut Line= 6
      2400301.96      6980266.13     2401113.807       6975160.8
     2400863.807     6973827.467     2400905.473     6972994.134
     2401349.918     6971716.3562400988.144760936970530.56493095
#Sta/Elev= 30
   -2170     490   -2140     475   -2000     465   -1750     465   -1700     475
   -1630     475   -1590     465    -370     466    -100     471     510     472
    1000     467    1320   473.7    1840     466    2430   472.6    3215   466.7
    3308     445    3385     427    5750     427    5914     445    6070     462
    6170     463    6215     445    6245     430    6265   427.7    6275     430
    6280     435    6330     460    6370     461    6700     470    7800     475
#Mann= 8 ,-1,0
   -2170     .04       0    3215     .08       0    3308     .05       0
    5914     .08       0    6070     .12       0    6170    .055       0
    6330     .12       0    6370     .07       0
#XS Ineff= 3 ,-1
    4544    5384     461    5384    6000     449    3240    4544     444
Permanent Ineff=
       T       T       T
#Block Obstruct= 4 ,-1
   -2170     715     480     715     965     479    1060    1755     479
    2020    3005     479
Bank Sta=6170,6330
XS Rating Curve= 0 ,0
Exp/Cntr=0.3,0.1

Type RM Length L Ch R = 1 ,107732  ,521,516,123
BEGIN DESCRIPTION:
This cross section corresponds to cross section 107775 of the non-georeferenced CDC model which was the source of this model.
Proposed fill & lake on LOB.  Flow limit 555  LOB from 2001 aerial topo.  ROB of X-SECTION BASED ON 1991 AND 2001 SURVEY DATA
END DESCRIPTION:
XS GIS Cut Line= 6
2400588.902539156980143.42952312      2401447.14     6975202.467
     2401502.696     6972431.634     2401711.029     6971834.411
      2401384.64     6971258.023      2400986.35       6970469.1
#Sta/Elev= 30
   -1915     485   -1845     475   -1815     465    -235     467     215     473
     685     468    1155   472.7    1845     466    2535   472.6    3265   466.6
    3366     445    3450     427    5375     427    5604     445    5820     462
    5910     461    5950     464    5990     459    6050     460    6120     430
    6140   427.6    6160     430    6180     440    6185     450    6200     460
    6250     462    6300     464    6400     460    7000     470    8050     480
#Mann= 8 ,-1,0
   -1915     .04       0    3265     .08       0    3366     .05       0
    5604     .08       0    5820     .12       0    6050    .055       0
    6200     .12       0    6250    .075       0
#XS Ineff= 2 ,-1
    3170    3580     462    3580    5800     444
Permanent Ineff=
       T       T
#Block Obstruct= 4 ,-1
   -1915     555     480     555     925     479    1030    1745     479
    2010    3115     479
Bank Sta=6050,6200
XS Rating Curve= 0 ,0
Exp/Cntr=0.3,0.1

Type RM Length L Ch R = 1 ,107216  ,489,352,110
BEGIN DESCRIPTION:
This cross section corresponds to cross section 107250 of the non-georeferenced CDC model which was the source of this model.
Proposed fill & lake on LOB.  Flow limit 380  LOB from 2001 aerial topo.  ROB OF X-SECTION BASED ON 1991 AND 2001 SURVEY DATA
END DESCRIPTION:
XS GIS Cut Line= 6
 2401122.66788056979823.86187385     2401426.307     6978251.078
     2402044.362     6975049.689     2401974.918     6972021.911
     2401454.085     6971195.523      2400944.16      6970385.37
#Sta/Elev= 30
   -1645     480   -1545     465    -445     466    -165     470     545   472.5
     985   468.5    1415     473    2045   465.1    2795   472.6    3045     469
    4090   466.5    4208     445    4305     427    5215     427    5347     445
    5384     450    5420   462.4    5735     463    5770     450    5780     440
    5790     435    5830   427.4    5850     430    5860     435    5865     440
    5940     460    6000     459    6550     460    7000     470    8180     480
#Mann= 8 ,-1,0
   -1645     .04       0    4090     .08       0    4208     .05       0
    5347     .08       0    5420     .12       0    5735    .055       0
    5940     .15       0    6000     .07       0
#XS Ineff= 1 ,-1
    4000    5400     444
Permanent Ineff=
       T
#Block Obstruct= 5 ,-1
   -1645     380     480     380     950     479    1050    1865     479
    2205    3445     479    3560    3940     479
Bank Sta=5735,5940
XS Rating Curve= 0 ,0
Exp/Cntr=0.3,0.1