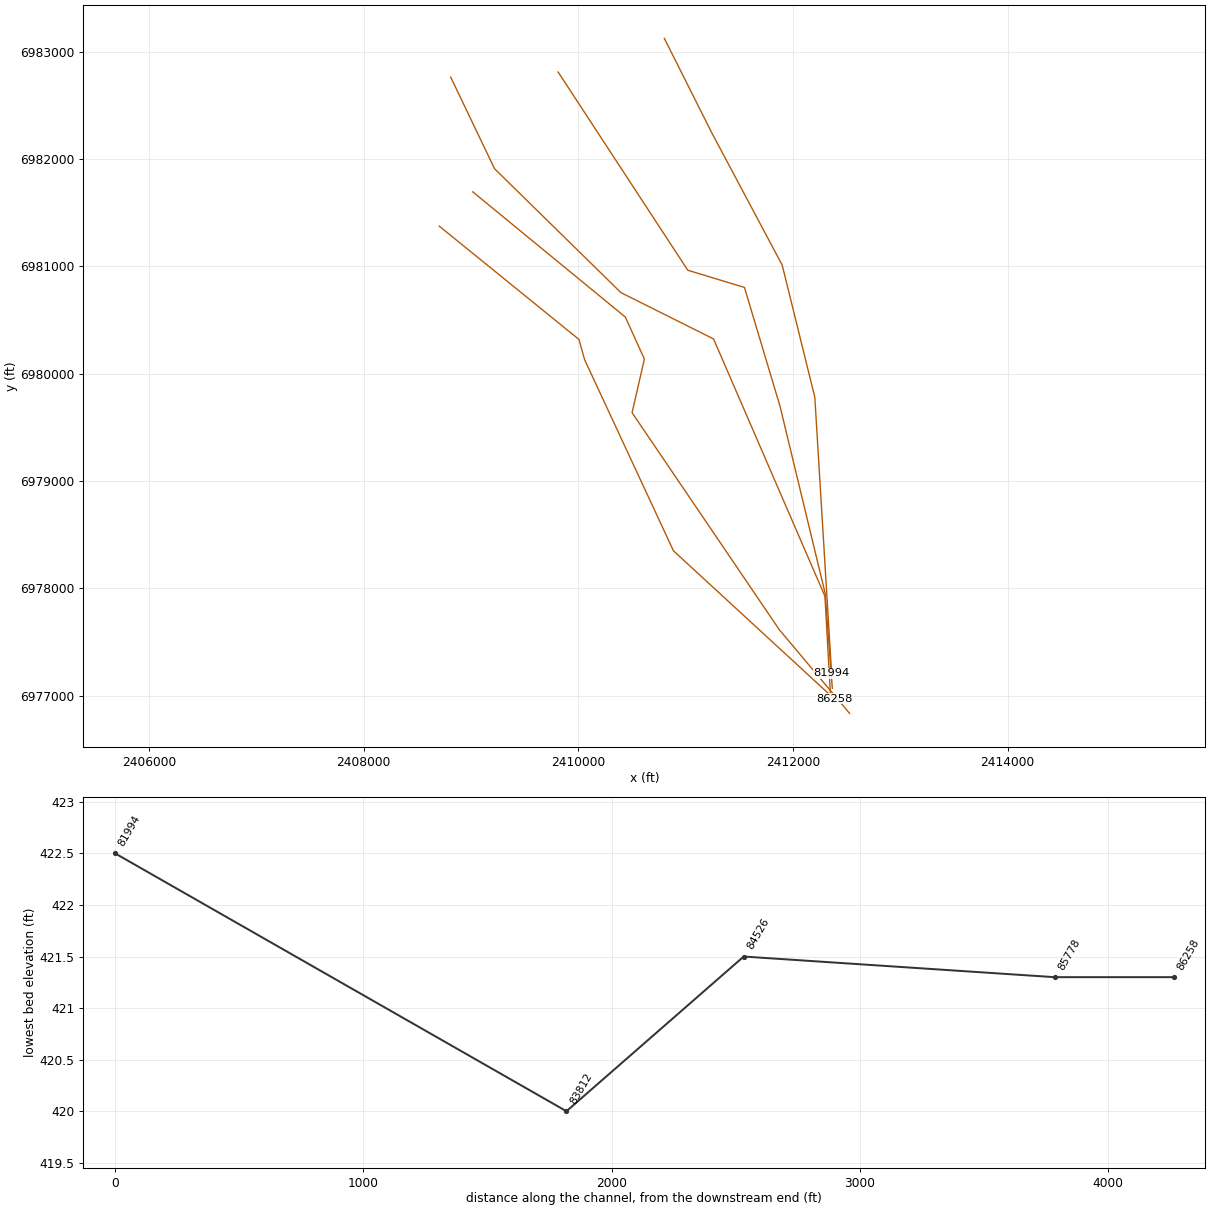
HEC-RAS study CDC_Consolidated_Model.prj: Upper Trinity CDC Consolidated Model

--- CDC_Consolidated_Model.g04 (geometry) --- (continued)

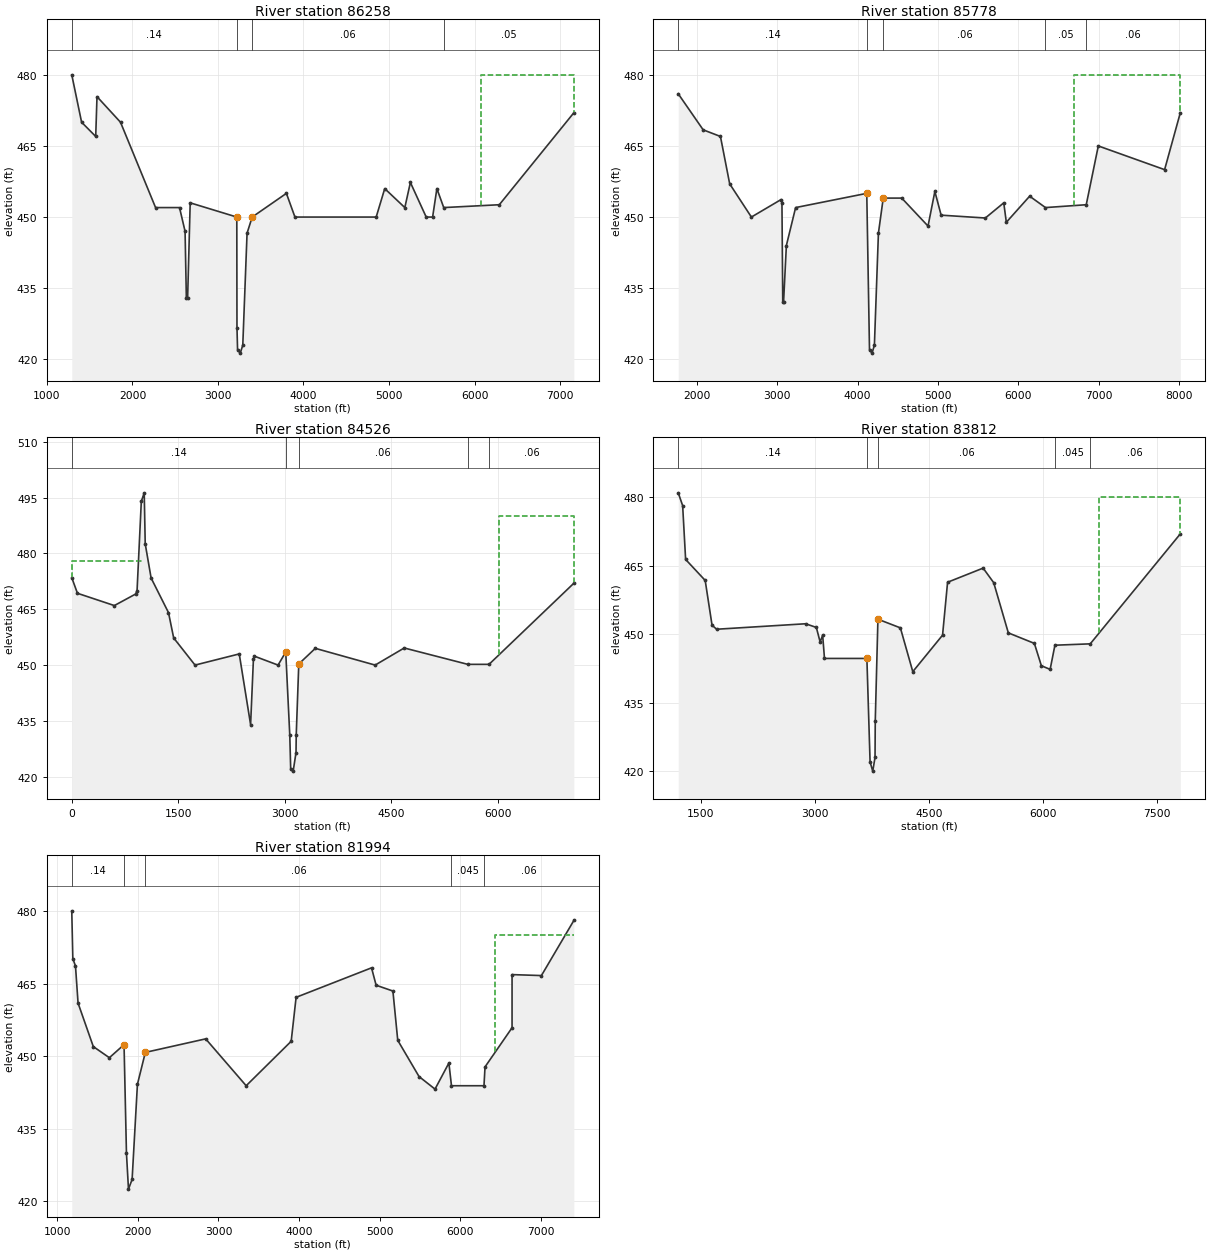
Type RM Length L Ch R = 1 ,86258   ,394,480,411
BEGIN DESCRIPTION:
This cross section corresponds to cross section 86300 of the non-georeferenced CDC model which was the source of this model.
LOB from 2001 aerial topo. - realigned for hydraulics -  ROB OF X-SECTION BASED ON 1991 AND 2001 SURVEY DATA  SET COE NON-EFFECTIVE FLOW LIMIT AT FILL LINE IN ROB  Added 2001 survey information for flood plain
END DESCRIPTION:
XS GIS Cut Line= 6
  2408703.405812 6981373.7449416 2408849.3191476 6981255.4368524
 2410005.5694597 6980317.9367589 2410057.6526889 6980130.4368058
 2410885.7776731 6978349.18675942412384.155768146976970.24438076
#Sta/Elev= 30
    1290     480    1405     470    1570     467    1585   475.4    1860     470
    2270     452    2550     452    2615     447    2630     433    2645     433
    2675     453    3220     450    3222   426.7    3229     422    3261   421.3
    3290     423    3340   446.6    3400     450    3800     455    3900     450
    4850     450    4950     456    5185     452    5250   457.3    5435     450
    5510     450    5560     456    5640     452    6290   452.6 7161.68     472
#Mann= 4 ,-1,0
    1290     .14       0    3220    .055       0    3400     .06       0
    5640     .05       0
#XS Ineff= 2 , 0
       0                    6080       0     480
Permanent Ineff=
       F       F
Bank Sta=3220,3400
XS Rating Curve= 0 ,0
Exp/Cntr=0.3,0.1

Type RM Length L Ch R = 1 ,85778   ,264,1252,793
BEGIN DESCRIPTION:
This cross section corresponds to cross section 85875 of the non-georeferenced CDC model which was the source of this model.
LOB from 2001 aerial topo.  - realigned for hydraulics - ROB from COE section 86951.  CHANNEL BASED ON 1991 AND 2001 SURVEY DATA  SET COE NON-EFFECTIVE FLOW LIMIT AT FILL LINE IN ROB  Added 2001 survey information for flood plain
CDC GP041795-1 Riverside Development
Cross-section 85875 - 94400
Located in ROB.
END DESCRIPTION:
XS GIS Cut Line= 6
     2409015.986     6981692.937     2410437.861      6980526.27
     2410614.944     6980135.645     2410500.361     6979635.645
     2411872.557     6977613.7562412527.285983586976834.47057364
#Sta/Elev= 30
    1770     476    2080   468.4    2295     467    2410     457    2680     450
    3050   453.7    3060     453    3070     432    3080     432    3115     444
    3230     452    4115     455    4149     422    4181   421.3    4210     423
    4260   446.6    4320     454    4550     454    4877   448.1    4962   455.4
    5040   450.4    5590   449.8    5819     453    5851   448.9    6141   454.4
    6338     452    6845   452.6    6995     465 7819.67     460    8015     472
#Mann= 5 ,-1,0
    1770     .14       0    4115    .055       0    4320     .06       0
    6338     .05       0    6845     .06       0
#XS Ineff= 2 , 0
       0                    6690       0     480
Permanent Ineff=
       F       F
Bank Sta=4115,4320
XS Rating Curve= 0 ,0
Exp/Cntr=0.3,0.1

Type RM Length L Ch R = 1 ,84526   ,902,714,211
BEGIN DESCRIPTION:
This cross section corresponds to cross section 84548 of the non-georeferenced CDC model which was the source of this model.
Flow limit moved for SPF conditions.  GRs added from storage model.  Boyd Br added.
END DESCRIPTION:
XS GIS Cut Line= 6
     2408810.039     6982762.393     2409218.499     6981908.865
     2410395.959      6980754.75     2411259.658     6980322.901
     2412297.668     6977925.6072412347.992532436977025.01205531
#Sta/Elev= 30
       0   473.5      80   469.3     600     466     900   469.1     920     470
     980     494    1021   496.3    1035   482.6    1118   473.4    1363   464.1
    1436   457.3    1737     450    2360     453    2520     434    2560   451.7
    2573   452.4    2907     450    3015   453.5    3072   431.2    3085     422
    3120   421.5    3160   426.5    3163   431.2    3199   450.3    3432   454.5
    4275     450    4685   454.6    5580   450.2    5880   450.2    7075     472
#Mann= 5 ,-1,0
       0     .14       0    3015    .055       0    3199     .06       0
    5580    .045       0    5880     .06       0
#XS Ineff= 2 , 0
       0    1000     478    6015       0     490
Permanent Ineff=
       F       F
Bank Sta=3015,3199
XS Rating Curve= 0 ,0
Exp/Cntr=0.3,0.1

Type RM Length L Ch R = 1 ,83812   ,950,1818,200
BEGIN DESCRIPTION:
This cross section corresponds to cross section 83836 of the non-georeferenced CDC model which was the source of this model.
Flow limit moved for SPF conditions.  GRs added from storage model and 1991 topo.  Section modified for continuity.  See 100 yr model for modifications.
END DESCRIPTION:
XS GIS Cut Line= 6
     2409811.199     6982809.534     2411019.741     6980962.678
     2411547.557     6980802.734     2411878.949     6979696.036
     2412299.304     6977953.9412412366.388365966977067.47714849
#Sta/Elev= 30
    1207     481    1265   478.2    1304   466.4    1561   461.8    1651     452
    1711   451.1    2880   452.3    3021   451.5    3071   448.3    3104   449.8
    3128   444.7    3685   444.7    3727     422    3762     420    3792     423
    3795     431    3830   453.3    4125   451.4    4288   441.8    4679   449.8
    4745   461.4    5212   464.5    5351   461.3    5543   450.3    5885     448
    5977   443.1    6092   442.3    6155   447.6    6619   447.9    7802     472
#Mann= 5 ,-1,0
    1207     .14       0    3685    .055       0    3830     .06       0
    6155    .045       0    6619     .06       0
#XS Ineff= 2 , 0
       0                    6735       0     480
Permanent Ineff=
       F       F
Bank Sta=3685,3830
XS Rating Curve= 0 ,0
Exp/Cntr=0.5,0.3

Type RM Length L Ch R = 1 ,81994   ,309,886,399
BEGIN DESCRIPTION:
This cross section corresponds to cross section 82018 of the non-georeferenced CDC model which was the source of this model.
Flow limit moved for SPF conditions.  Data added to relief from CORPS data.  See 100 yr model for modifications.
END DESCRIPTION:
XS GIS Cut Line= 6
     2410800.738     6983123.357     2411243.663     6982242.231
     2411899.434     6981010.661     2412203.328     6979779.091
     2412351.956     6977334.862     2412358.376     6977209.727
#Sta/Elev= 30
    1182   480.1    1195   470.2    1228   468.7    1260     461    1449     452
    1648   449.7    1830   452.4    1860   429.9    1885   422.5    1930   424.5
    1996   444.2    2094   450.8    2842   453.6    3344   443.9    3902   453.1
    3963   462.2    4898   468.3    4955   464.7    5163   463.5    5223   453.3
    5487   445.8    5685   443.2    5857   448.6    5889   443.9    6292   443.9
    6305   447.8    6640   455.9    6640   466.9    7004   466.7    7406   478.1
#Mann= 5 ,-1,0
    1182     .14       0    1830    .055       0    2094     .06       0
    5889    .045       0    6292     .06       0
#XS Ineff= 2 , 0
       0                    6430       0     475
Permanent Ineff=
       F       F
Bank Sta=1830,2094
XS Rating Curve= 0 ,0
Exp/Cntr=0.5,0.3