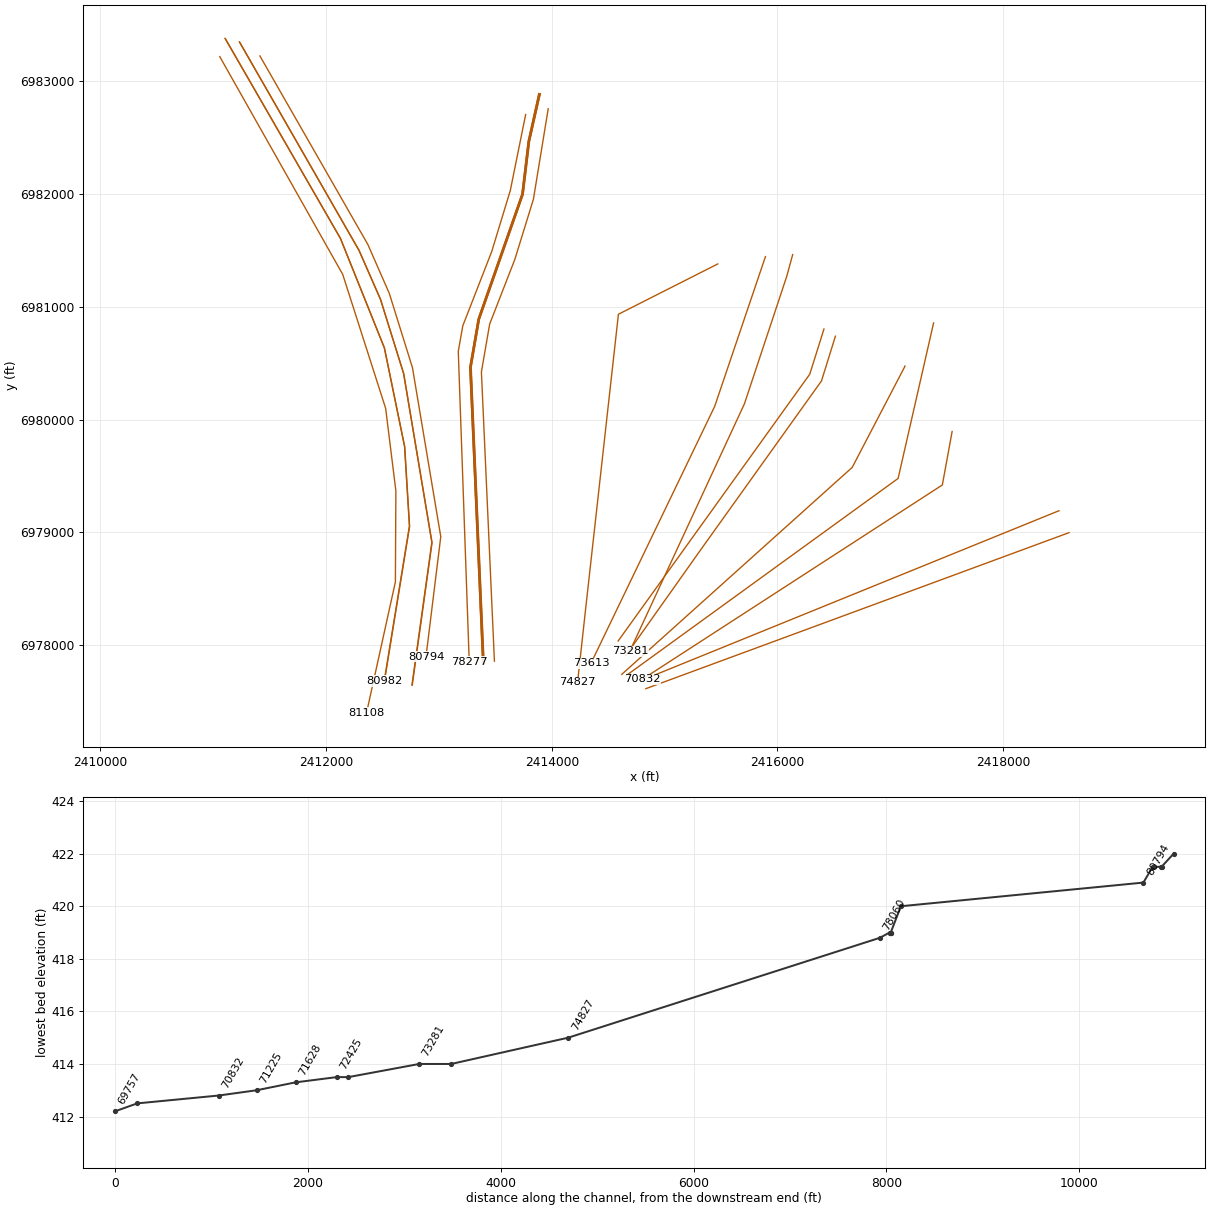
HEC-RAS study CDC_Consolidated_Model.prj: Upper Trinity CDC Consolidated Model

--- CDC_Consolidated_Model.g04 (geometry) --- (continued)

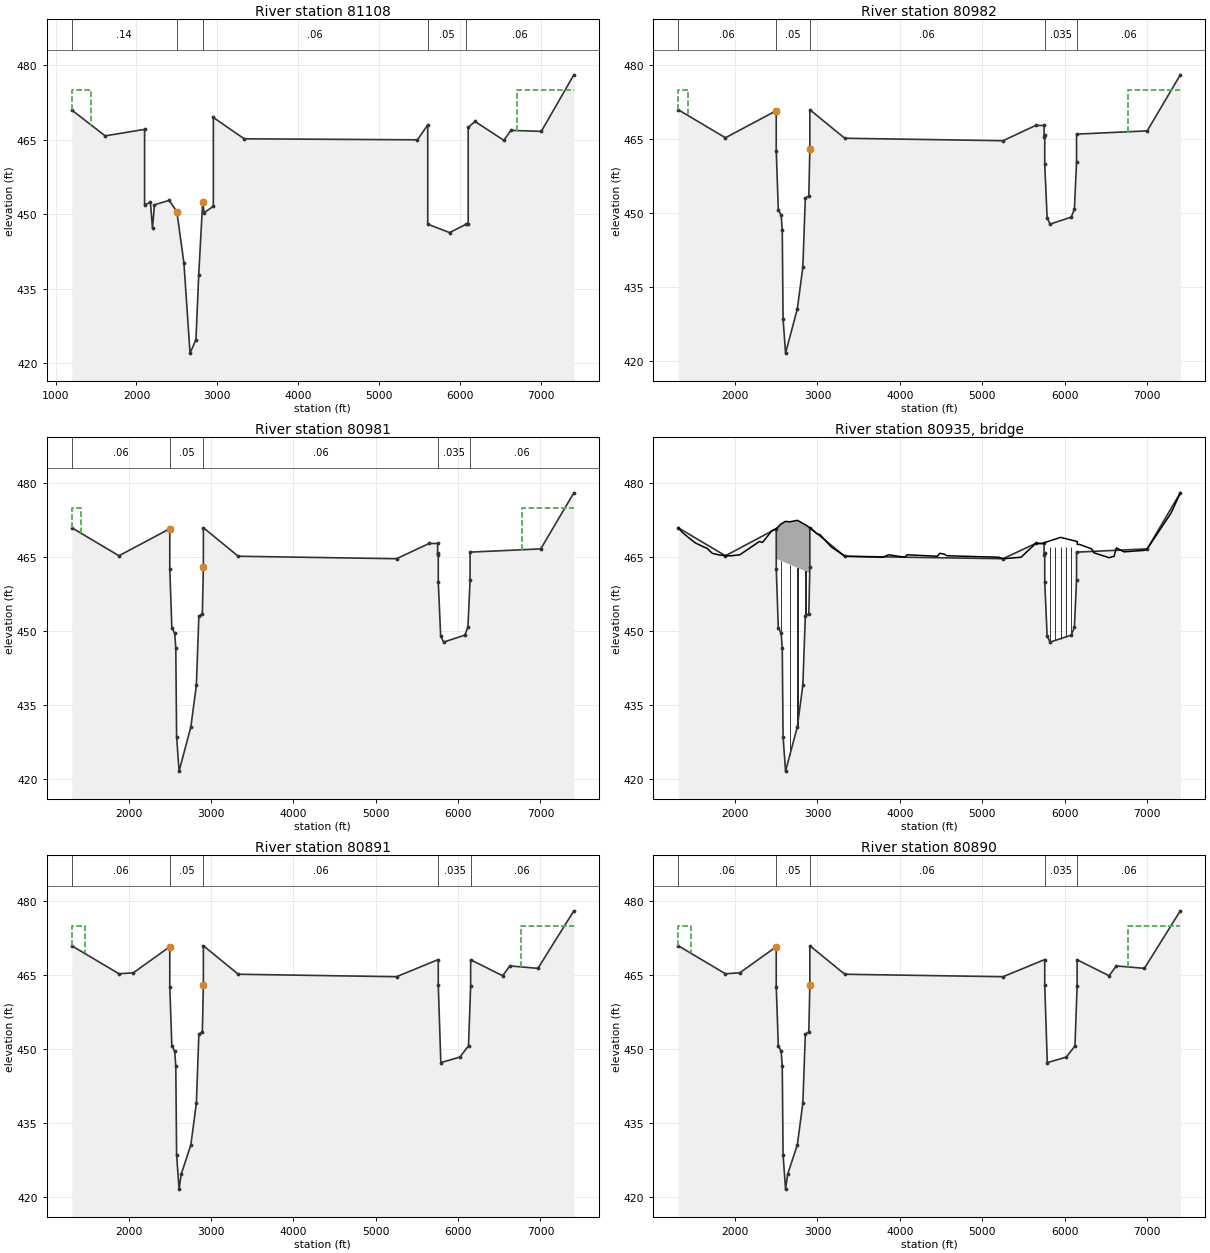
Type RM Length L Ch R = 1 ,81108   ,126,126,126
BEGIN DESCRIPTION:
This cross section corresponds to cross section 81130 of the non-georeferenced CDC model which was the source of this model.
Left flow limit due to u/s high ground.  Right flow limit due to d/s high ground.  Data added to relief from CORPS data.  Cont/Exp raised due to influences from SH 360.  'n' value lowered to reflect irregular pavement section and short vegetation.
CDC ARL062007-1 Viridian Project
Cross-section 81131 - 109405
Located in LOB.
--------------------------------
END DESCRIPTION:
XS GIS Cut Line= 6
   2411057.64181 6983220.6152984 2412147.2449664 6981288.3380333
 2412527.5119224 6980100.0031396  2412618.258132  6979367.557098
 2412613.9359622 6978559.4901446 2412358.3597017 6977398.0984385
#Sta/Elev= 30
    1200     471    1613   465.8    2100   467.1    2100   451.9    2172   452.4
    2198   447.2    2222   451.9    2405   452.8    2499   450.5    2586   440.2
    2662     422    2735   424.7    2769   437.7    2818   452.4    2837   450.3
    2950   451.6    2950   469.5    3332   465.2    5473     465    5600     468
    5600     448    5870   446.3    6077     448    6100     448    6100   467.5
    6184   468.7    6541   464.9    6629   466.9    7004   466.7    7406   478.1
#Mann= 5 ,-1,0
    1200     .14       0    2499    .055       0    2818     .06       0
    5600     .05       0    6077     .06       0
#XS Ineff= 2 , 0
       0    1435     475    6700       0     475
Permanent Ineff=
       F       F
Bank Sta=2499,2818
XS Rating Curve= 0 ,0
Exp/Cntr=0.5,0.3

Type RM Length L Ch R = 1 ,80982   ,1,1,1
BEGIN DESCRIPTION:
This cross section corresponds to cross section 81004 of the non-georeferenced CDC model which was the source of this model.
Left flow limit due to u/s high ground.  Right flow limit due to d/s high ground.  'n' value lowered through relief bridge to reflect normal high grass and regular pavement section.  Relief bridge surveyed 10-06.
END DESCRIPTION:
XS GIS Cut Line= 6
  2411103.941935 6983383.1987873 2412126.6193515 6981607.3331302
 2412515.5283506 6980637.2202411 2412694.8593567 6979762.1740909
 2412738.0715407 6979055.6551627 2412514.6582736 6977680.4269421
#Sta/Elev= 30
    1310     471    1883   465.3    2500   470.8    2500   462.7    2525   450.7
    2560   449.5    2573   446.5    2583   428.5    2613   421.5    2756   430.5
    2823     439    2853     453  2895.5   453.5    2908     463    2908     471
    3332   465.2    5253   464.7    5649   467.8    5752   467.8    5752  465.51
    5760  465.88    5760  459.92    5789  449.02    5825  447.74    6082  449.16
    6120  450.76    6146  460.29    6146  466.04    7004   466.7    7406   478.1
#Mann= 5 ,-1,0
    1310     .06       0    2500     .05       0    2908     .06       0
    5760    .035       0    6146     .06       0
#XS Ineff= 2 , 0
       0    1425     475    6775       0     475
Permanent Ineff=
       F       F
Bank Sta=2500,2908
XS Rating Curve= 0 ,0
Exp/Cntr=0.5,0.3

Type RM Length L Ch R = 1 ,80981   ,90,90,90
BEGIN DESCRIPTION:
This cross section corresponds to cross section 81003 of the non-georeferenced CDC model which was the source of this model.
Left flow limit due to u/s high ground.  Right flow limit due to d/s high ground.  'n' value lowered through relief bridge to reflect normal high grass and regular pavement section.  Relief bridge surveyed 10-06.
END DESCRIPTION:
XS GIS Cut Line= 6
  2411108.350972 6983377.5437578 2412127.4631818 6981607.7986805
 2412517.0785443 6980635.8980652 2412696.7199173 6979759.3079549
 2412740.0065762 6979051.5711814 2412516.3026272 6977674.0076636
#Sta/Elev= 30
    1310     471    1883   465.3    2500   470.8    2500   462.7    2525   450.7
    2560   449.5    2573   446.5    2583   428.5    2613   421.5    2756   430.5
    2823     439    2853     453  2895.5   453.5    2908     463    2908     471
    3332   465.2    5253   464.7    5649   467.8    5752   467.8    5752  465.51
    5760  465.88    5760  459.92    5789  449.02    5825  447.74    6082  449.16
    6120  450.76    6146  460.29    6146  466.04    7004   466.7    7406   478.1
#Mann= 5 ,-1,0
    1310     .06       0    2500     .05       0    2908     .06       0
    5760    .035       0    6146     .06       0
#XS Ineff= 2 , 0
       0    1425     475    6775       0     475
Permanent Ineff=
       F       F
Bank Sta=2500,2908
XS Rating Curve= 0 ,0
Exp/Cntr=0.5,0.3

Type RM Length L Ch R = 3 ,80935   ,,,
BEGIN DESCRIPTION:
S.H. 360
Relief bridge superelevated.  D/S sided higher.  Relief bridge surveyed 10-06.
END DESCRIPTION:
Node Name=S.H. 360
Bridge Culvert--1,0,-1,-1, 0
Deck Dist Width WeirC Skew NumUp NumDn MinLoCord MaxHiCord MaxSubmerge Is_Ogee
1,88,2.6,0, 62, 62, , , 0.95, 0, ,,,
    1310    1362    1442    1519    1606    1661    1723    1795    1883    1956
    2058    2295    2329    2358    2446    2500    2500    2560  2562.5    2613
    2663    2756  2758.5    2853  2855.5    2908    2908    2952    2992    3032
    3168    3332    3796    3863    4061    4089    4457    4486    4544    4570
    5203    5253    5473    5649    5752    5752    5760    5953    6146    6155
    6155    6184    6329    6358    6541    6602    6629    6722    6970    7004
    7294    7406
     471     470   468.9   467.9   467.2   466.8   465.8   465.5   465.3   465.3
   465.5   468.2     468   468.5   470.4   470.8   470.8   471.8   471.8   472.3
   472.2   472.5   472.5   471.6   471.6     471     471   470.4   469.8   469.6
   467.1   465.2     465   465.5     465   465.5   465.2   465.8   465.6   465.3
     465   464.7     465   467.8   467.8  467.89  467.99  469.04  468.23  468.17
   467.6   467.6   466.7   465.9   464.9   465.2   466.9   466.1   466.4   466.7
     474   478.1
                                                   464.6     465   464.1   464.1
   464.1   464.1   464.1   464.1   465.1   464.7
                                                  461.75  462.86  461.93
    1310    1362    1442    1519    1606    1661    1723    1795    1883    1956
    2058    2295    2329    2358    2446    2500    2500    2560  2562.5    2613
    2663    2756  2758.5    2853  2855.5    2908    2908    2952    2992    3032
    3168    3332    3796    3863    4061    4089    4457    4486    4544    4570
    5203    5253    5473    5649    5751    5751    5760    5956    6153    6161
    6161    6184    6329    6358    6541    6602    6629    6722    6970    7004
    7294    7406
     471     470   468.9   467.9   467.2   466.8   465.8   465.5   465.3   465.3
   465.5   468.2     468   468.5   470.4   470.8   470.8   471.8   471.8   472.3
   472.2   472.5   472.5   471.6   471.6     471     471   470.4   469.8   469.6
   467.1   465.2     465   465.5     465   465.5   465.2   465.8   465.6   465.3
     465   464.7     465     468   468.9  470.78  470.89  472.11  470.89  470.79
     469   468.7   466.7   465.9   464.9   465.2   466.9   466.1   466.4   466.7
     474   478.1
                                                   464.6     465   464.1   464.1
   464.1   464.1   464.1   464.1   465.1   464.7
                                                  464.04  465.24  464.06
Pier Skew, UpSta & Num, DnSta & Num=  ,2561.25, 2 ,2561.25, 2 , 0 , 0 , 0 ,,
     2.5     2.5
     420     467
     2.5     2.5
     420     467
Pier Skew, UpSta & Num, DnSta & Num=  ,2664.25, 2 ,2664.25, 2 , 0 , 0 , 0 ,,
     2.5     2.5
     420     467
     2.5     2.5
     420     467
Pier Skew, UpSta & Num, DnSta & Num=  ,2758.25, 2 ,2758.25, 2 , 0 , 0 , 0 ,,
     2.5     2.5
     420     467
     2.5     2.5
     420     467
Pier Skew, UpSta & Num, DnSta & Num=  ,2854.25, 2 ,2854.25, 2 , 0 , 0 , 0 ,,
     2.5     2.5
     420     467
     2.5     2.5
     420     467
Pier Skew, UpSta & Num, DnSta & Num=  ,5825, 2 ,5825, 2 , 0 , 0 , 0 ,,
       3       3
     420     467
       3       3
     420     467
Pier Skew, UpSta & Num, DnSta & Num=  ,5889, 2 ,5891, 2 , 0 , 0 , 0 ,,
       3       3
     420     467
       3       3
     420     467
Pier Skew, UpSta & Num, DnSta & Num=  ,5953, 2 ,5956, 2 , 0 , 0 , 0 ,,
       3       3
     420     467
       3       3
     420     467
Pier Skew, UpSta & Num, DnSta & Num=  ,6017, 2 ,6022, 2 , 0 , 0 , 0 ,,
       3       3
     420     467
       3       3
     420     467
Pier Skew, UpSta & Num, DnSta & Num=  ,6082, 2 ,6087, 2 , 0 , 0 , 0 ,,
       3       3
     420     467
       3       3
     420     467
BR Coef= 1 , 0 , 0 ,1.05, 0 ,,,0.8,-1,0.5,1,
WSPro=,,,, 1 ,,,, 0 ,,,, 0 ,,,,-1 ,-1 ,-1 , 0 , 0 , 0 , 0 , 0
BC Design=,, 0 ,, 0 ,,,,,,
BC HTab HWMax=478.1
BC Use User HTab Curves=0
BC User HTab FreeFlow(D)= 0

Type RM Length L Ch R = 1 ,80891   ,1,1,1
BEGIN DESCRIPTION:
This cross section corresponds to cross section 80913 of the non-georeferenced CDC model which was the source of this model.
Flow limits due to d/s high ground.  'n' value lowered through relief bridge to reflect normal high grass and regular pavement section.  Relief bridge surveyed 10-06.
END DESCRIPTION:
XS GIS Cut Line= 6
  2411231.377001 6983351.3869289 2412291.5563576 6981500.4291446
 2412481.2931828 6981067.0664942 2412686.2429042 6980409.0701068
 2412936.8290172 6978910.7876703 2412760.6915345 6977645.8100276
#Sta/Elev= 30
    1310     471    1883   465.3    2058   465.5    2500   470.8    2500   462.7
    2525   450.7    2560   449.5    2573   446.5    2583   428.5    2613   421.5
    2638   424.5    2756   430.5    2823     439    2853     453  2895.5   453.5
    2908     463    2908     471    3332   465.2    5253   464.7    5760  468.19
    5760  462.97    5791  447.23    6022  448.35    6127  450.63    6153  462.81
    6153  468.15    6541   464.9    6629   466.9    6970   466.4    7406   478.1
#Mann= 5 ,-1,0
    1310     .06       0    2500     .05       0    2908     .06       0
    5760    .035       0    6153     .06       0
#XS Ineff= 2 , 0
       0    1465     475    6770       0     475
Permanent Ineff=
       F       F
Bank Sta=2500,2908
XS Rating Curve= 0 ,0
Exp/Cntr=0.5,0.3

Type RM Length L Ch R = 1 ,80890   ,96,96,96
BEGIN DESCRIPTION:
This cross section corresponds to cross section 80912 of the non-georeferenced CDC model which was the source of this model.
Flow limits due to d/s high ground.  'n' value lowered through relief bridge to reflect normal high grass and regular pavement section.  Relief bridge surveyed 10-06.
END DESCRIPTION:
XS GIS Cut Line= 6
  2411234.004349 6983348.8685622 2412292.6410011 6981500.5239607
 2412482.7738229 6981066.2410366 2412688.0319426  6980407.255806
 2412938.9389211 6978907.3877427 2412763.3695778 6977642.9633245
#Sta/Elev= 30
    1310     471    1883   465.3    2058   465.5    2500   470.8    2500   462.7
    2525   450.7    2560   449.5    2573   446.5    2583   428.5    2613   421.5
    2638   424.5    2756   430.5    2823     439    2853     453  2895.5   453.5
    2908     463    2908     471    3332   465.2    5253   464.7    5760  468.19
    5760  462.97    5791  447.23    6022  448.35    6127  450.63    6153  462.81
    6153  468.15    6541   464.9    6629   466.9    6970   466.4    7406   478.1
#Mann= 5 ,-1,0
    1310     .06       0    2500     .05       0    2908     .06       0
    5760    .035       0    6153     .06       0
#XS Ineff= 2 , 0
       0    1465     475    6770       0     475
Permanent Ineff=
       F       F
Bank Sta=2500,2908
XS Rating Curve= 0 ,0
Exp/Cntr=0.5,0.3

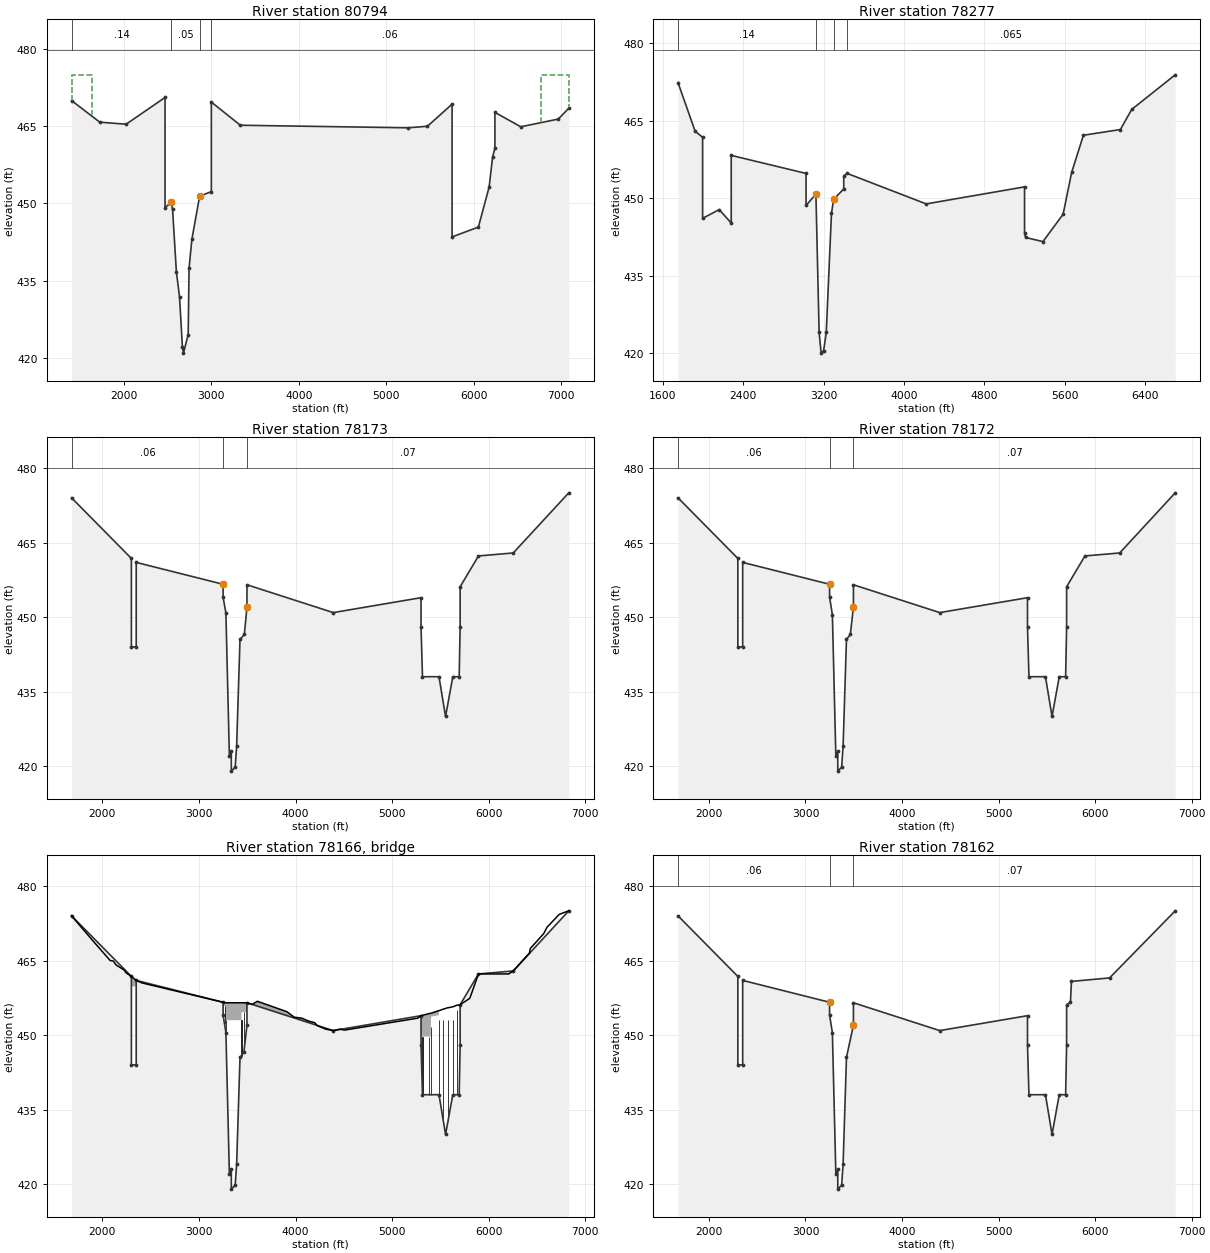
Type RM Length L Ch R = 1 ,80794   ,2199,2516,280
BEGIN DESCRIPTION:
This cross section corresponds to cross section 80816 of the non-georeferenced CDC model which was the source of this model.
Flow limits due to d/s high ground.  Left 'n' value corrected from 0.014 to 0.14.  Data added to relief from CORPS data.
END DESCRIPTION:
XS GIS Cut Line= 6
  2411413.125112 6983226.9088134 2412369.7881565 6981554.0930792
 2412559.9209783 6981119.8101552  2412765.179098 6980460.8249246
 2413016.0860765 6978960.9568613 2412884.9808202 6977894.6029986
#Sta/Elev= 30
    1400     470    1723   465.8    2025   465.4    2470   470.6    2470   449.2
    2542   450.2    2556   448.9    2600   436.7    2636   431.8    2669   422.1
    2681   420.9    2735   424.5    2745   437.4    2777     443    2866   451.4
    3000   452.3    3000   469.7    3332   465.2    5253   464.7    5473     465
    5755   469.3    5755   443.5    6056   445.4    6179   453.2    6219   459.1
    6245   460.7    6245   467.7    6541   464.9    6970   466.4    7090   468.5
#Mann= 4 ,-1,0
    1400     .14       0    2542     .05       0    2866     .09       0
    3000     .06       0
#XS Ineff= 2 , 0
       0    1635     475    6770       0     475
Permanent Ineff=
       F       F
Bank Sta=2542,2866
XS Rating Curve= 0 ,0
Exp/Cntr=0.5,0.3

Type RM Length L Ch R = 1 ,78277   ,105,105,105
BEGIN DESCRIPTION:
This cross section corresponds to cross section 78299 of the non-georeferenced CDC model which was the source of this model.
Railroad lowered 2' below rails.  Left 'n' value corrected from 0.014 to 0.14.  Data added to LOB from CORPS data.  'n' value changed in ROB  to transition from RR to 360 'n' value.
END DESCRIPTION:
XS GIS Cut Line= 6
  2413768.241068 6982706.7886085 2413632.3000672 6982032.7138412
 2413467.6439004 6981491.1801473 2413211.5141633 6980832.5590892
    2413171.2649 6980605.6999629  2413268.339753 6977849.5186728
#Sta/Elev= 30
    1750   472.4    1920     463    1995   461.8    1995   446.1    2160   447.8
    2280   445.2    2280   458.3    3025   454.8    3025   448.6    3123   450.8
    3155     424    3175     420    3200   420.5    3226     424    3278   447.1
    3300   449.8    3400   451.8    3400   454.3    3435   454.8    4221   448.9
    5200   452.2    5200   443.3    5210   442.4    5383   441.6    5584   446.9
    5669     455    5786   462.2    6154   463.3    6267   467.2    6700   473.9
#Mann= 4 ,-1,0
    1750     .14       0    3123     .05       0    3300     .09       0
    3435    .065       0
Bank Sta=3123,3300
XS Rating Curve= 0 ,0
Exp/Cntr=0.5,0.3

Type RM Length L Ch R = 1 ,78173   ,1,1,1
BEGIN DESCRIPTION:
This cross section corresponds to cross section 78195 of the non-georeferenced CDC model which was the source of this model.
Far LOB extended with 1991 topo.  High ground from u/s added to ROB.  'n' value raised in ROB  to be consistent.
END DESCRIPTION:
XS GIS Cut Line= 6
  2413884.730336  6982892.148474 2413790.3046724 6982468.5171034
 2413734.5738128 6982000.4803098 2413346.8859398 6980892.4546387
 2413272.9149592 6980463.4548406 2413387.0961613 6977837.8193438
#Sta/Elev= 30
    1680     474    2300   461.8    2300     444    2350     444    2350     461
    3250   456.6    3250     454    3279   450.8    3315     422    3335     423
    3335     419    3375   419.8    3390     424    3425   445.5    3470   446.5
    3497     452    3497   456.5    4391   450.9    5300   453.9    5300     448
    5315     438    5486     438    5554     430    5629     438    5695     438
    5705     448    5705   456.1    5895   462.3    6255   462.9    6830     475
#Mann= 3 ,0,0
    1680     .06       0    3250     .05       0    3497     .07       0
Bank Sta=3250,3497
XS Rating Curve= 0 ,0
Exp/Cntr=0.5,0.3

Type RM Length L Ch R = 1 ,78172   ,10,10,10
BEGIN DESCRIPTION:
This cross section corresponds to cross section 78194 of the non-georeferenced CDC model which was the source of this model.
Far LOB extended with 1991 topo.  High ground from u/s added to ROB.  'n' value raised in ROB  to be consistent.
END DESCRIPTION:
XS GIS Cut Line= 6
  2413885.692276 6982891.6369921 2413791.4414812  6982468.980029
 2413735.6144931 6982000.5170552 2413347.9069352 6980892.4146126
 2413274.0288021 6980463.9505745 2413388.2470776 6977837.5526121
#Sta/Elev= 30
    1680     474    2300   461.8    2300     444    2350     444    2350     461
    3250   456.6    3250     454    3279   450.5    3315     422    3335     423
    3335     419    3375   419.8    3390     424    3425   445.5    3465   446.5
    3497     452    3497   456.5    4391   450.9    5300   453.9    5300     448
    5315     438    5486     438    5554     430    5629     438    5695     438
    5705     448    5705   456.1    5895   462.3    6255   462.9    6830     475
#Mann= 3 ,0,0
    1680     .06       0    3250     .05       0    3497     .07       0
Bank Sta=3250,3497
XS Rating Curve= 0 ,0
Exp/Cntr=0.5,0.3

Type RM Length L Ch R = 3 ,78166   ,,,
BEGIN DESCRIPTION:
Union Pacific Railroad
END DESCRIPTION:
Node Name=Union Pacific Ra
Bridge Culvert--1,0,-1,-1, 0
Deck Dist Width WeirC Skew NumUp NumDn MinLoCord MaxHiCord MaxSubmerge Is_Ogee
1,8,2.6,0, 68, 73, , , 0.95, 0, 0,0,,
    1680    1900    2080    2112    2142    2224    2246    2300    2300    2350
    2350    2408    3250    3250    3265    3266    3275    3275    3279    3437
    3441    3441    3465    3470    3497    3497    3529    3552    3605    3911
    3986    4066    4138    4198    4226    4311    4391    4462    4507    5266
    5300    5300    5400    5404    5482    5482    5486    5526    5530    5577
    5583    5629    5633    5633    5668    5673    5705    5705    5805    5895
    6208    6255    6423    6431    6570    6605    6732    6830
     474     469     465   464.9   464.1   463.1   462.5   461.8   461.8     461
     461   460.5   456.6   456.6   456.5   456.5   456.5   456.5   456.5   456.5
   456.5   456.5   456.5   456.5   456.5   456.5   456.3   456.2   456.8   454.7
   453.6   453.4   452.8   452.5   451.9   451.2   450.9   451.2     451   453.4
   453.9   453.9   454.4   454.4   454.9   454.9   454.9   455.2   455.2   455.5
   455.5   455.7   455.7   455.7     456     456   456.1   456.1   457.4   462.3
   462.3   462.9   466.5   467.4   470.4   471.7   474.3     475
                                                                   459.8   459.8
                           455.8   455.8   455.8   455.8     453     453     453
     453   454.6   454.6   454.6   454.6
           452.5   452.5   452.5   452.5   448.9   448.9   449.2   449.2   449.5
   449.5   449.7   449.7   453.7     454     454   454.1
    1680    1900    2080    2112    2142    2224    2246    2300    2300    2350
    2350    2408    3250    3250    3265    3266    3275    3275    3279    3437
    3441    3441    3465    3470    3497    3497    3529    3552    3605    3911
    3986    4066    4138    4198    4226    4311    4391    4462    4507    5266
    5300    5300    5400    5404    5482    5482    5486    5526    5530    5577
    5583    5629    5633    5633    5668    5673    5705    5705    5745    5755
    5770    5900    5960    6010    6100    6150    6255    6423    6431    6570
    6605    6732    6830
     474     469     465   464.9   464.1   463.1   462.5   461.8   461.8     461
     461   460.5   456.6   456.6   456.5   456.5   456.5   456.5   456.5   456.5
   456.5   456.5   456.5   456.5   456.5   456.5   456.3   456.2   456.8   454.7
   453.6   453.4   452.8   452.5   451.9   451.2   450.9   451.2     451   453.4
   453.9   453.9   454.4   454.4   454.9   454.9   454.9   455.2   455.2   455.5
   455.5   455.7   455.7   455.7     456     456   456.1   456.1   456.6   460.8
     461     461     462     462   461.5   461.5   462.9   466.5   467.4   470.4
   471.7   474.3     475
                                                                   459.8   459.8
                           455.8   455.8   455.8   455.8     453     453     453
     453   454.6   454.6   454.6   454.6
           452.5   452.5   452.5   452.5   448.9   448.9   449.2   449.2   449.5
   449.5   449.7   449.7   453.7     454     454   454.1
Pier Skew, UpSta & Num, DnSta & Num=  ,3265.5, 2 ,3265.5, 2 , 0 , 0 , 0 ,,
       1       1
     450     456
       1       1
     450     456
Pier Skew, UpSta & Num, DnSta & Num=  ,3277, 2 ,3277, 2 , 0 , 0 , 0 ,,
       4       4
     450     456
       4       4
     450     456
Pier Skew, UpSta & Num, DnSta & Num=  ,3439, 2 ,3439, 2 , 0 , 0 , 0 ,,
       4       4
     450     456
       4       4
     450     456
Pier Skew, UpSta & Num, DnSta & Num=  ,3467.5, 2 ,3467.5, 2 , 0 , 0 , 0 ,,
       5       5
     450     456
       5       5
     450     456
Pier Skew, UpSta & Num, DnSta & Num=  ,5317, 2 ,5317, 2 , 0 , 0 , 0 ,,
       4       4
     430     453
       4       4
     430     453
Pier Skew, UpSta & Num, DnSta & Num=  ,5382, 2 ,5382, 2 , 0 , 0 , 0 ,,
       4       4
     430     453
       4       4
     430     453
Pier Skew, UpSta & Num, DnSta & Num=  ,5402, 2 ,5402, 2 , 0 , 0 , 0 ,,
       4       4
     430     453
       4       4
     430     453
Pier Skew, UpSta & Num, DnSta & Num=  ,5484, 2 ,5484, 2 , 0 , 0 , 0 ,,
       4       4
     430     453
       4       4
     430     453
Pier Skew, UpSta & Num, DnSta & Num=  ,5528, 2 ,5528, 2 , 0 , 0 , 0 ,,
       4       4
     430     453
       4       4
     430     453
Pier Skew, UpSta & Num, DnSta & Num=  ,5579, 2 ,5579, 2 , 0 , 0 , 0 ,,
       4       4
     430     453
       4       4
     430     453
Pier Skew, UpSta & Num, DnSta & Num=  ,5631, 2 ,5631, 2 , 0 , 0 , 0 ,,
       4       4
     430     453
       4       4
     430     453
Pier Skew, UpSta & Num, DnSta & Num=  ,5670.5, 2 ,5670.5, 2 , 0 , 0 , 0 ,,
       4       4
     430     455
       4       4
     430     455
BR Coef=-1 , 0 , 0 ,, 0 ,,,0.8,-1,,1,
WSPro=,,,, 1 ,,,, 0 ,,,, 0 ,,,,-1 ,-1 ,-1 , 0 , 0 , 0 , 0 , 0
BC Design=,, 0 ,, 0 ,,,,,,
BC HTab HWMax=475
BC Use User HTab Curves=0
BC User HTab FreeFlow(D)= 0

Type RM Length L Ch R = 1 ,78162   ,1,1,1
BEGIN DESCRIPTION:
This cross section corresponds to cross section 78184 of the non-georeferenced CDC model which was the source of this model.
Far LOB extended with 1991 topo.  Cont/Exp raised due to railroad.   High ground from d/s added to ROB.  'n' value raised in ROB  to be consistent.
END DESCRIPTION:
XS GIS Cut Line= 6
  2413895.712598 6982889.0162624 2413801.1278135 6982466.7277369
 2413745.0603403 6981997.1998046  2413357.303898 6980888.9047771
  2413283.658376 6980461.7806313 2413398.0075567 6977832.6179107
#Sta/Elev= 30
    1680     474    2300   461.8    2300     444    2350     444    2350     461
    3250   456.6    3250     454    3279   450.5    3315     422    3335     423
    3335     419    3375   419.8    3390     424    3425   445.5    3497     452
    3497   456.5    4391   450.9    5300   453.9    5300     448    5315     438
    5486     438    5554     430    5629     438    5695     438    5705     448
    5705   456.1    5745   456.6    5755   460.8    6150   461.5    6830     475
#Mann= 3 ,0,0
    1680     .06       0    3250     .05       0    3497     .07       0
Bank Sta=3250,3497
XS Rating Curve= 0 ,0
Exp/Cntr=0.5,0.3

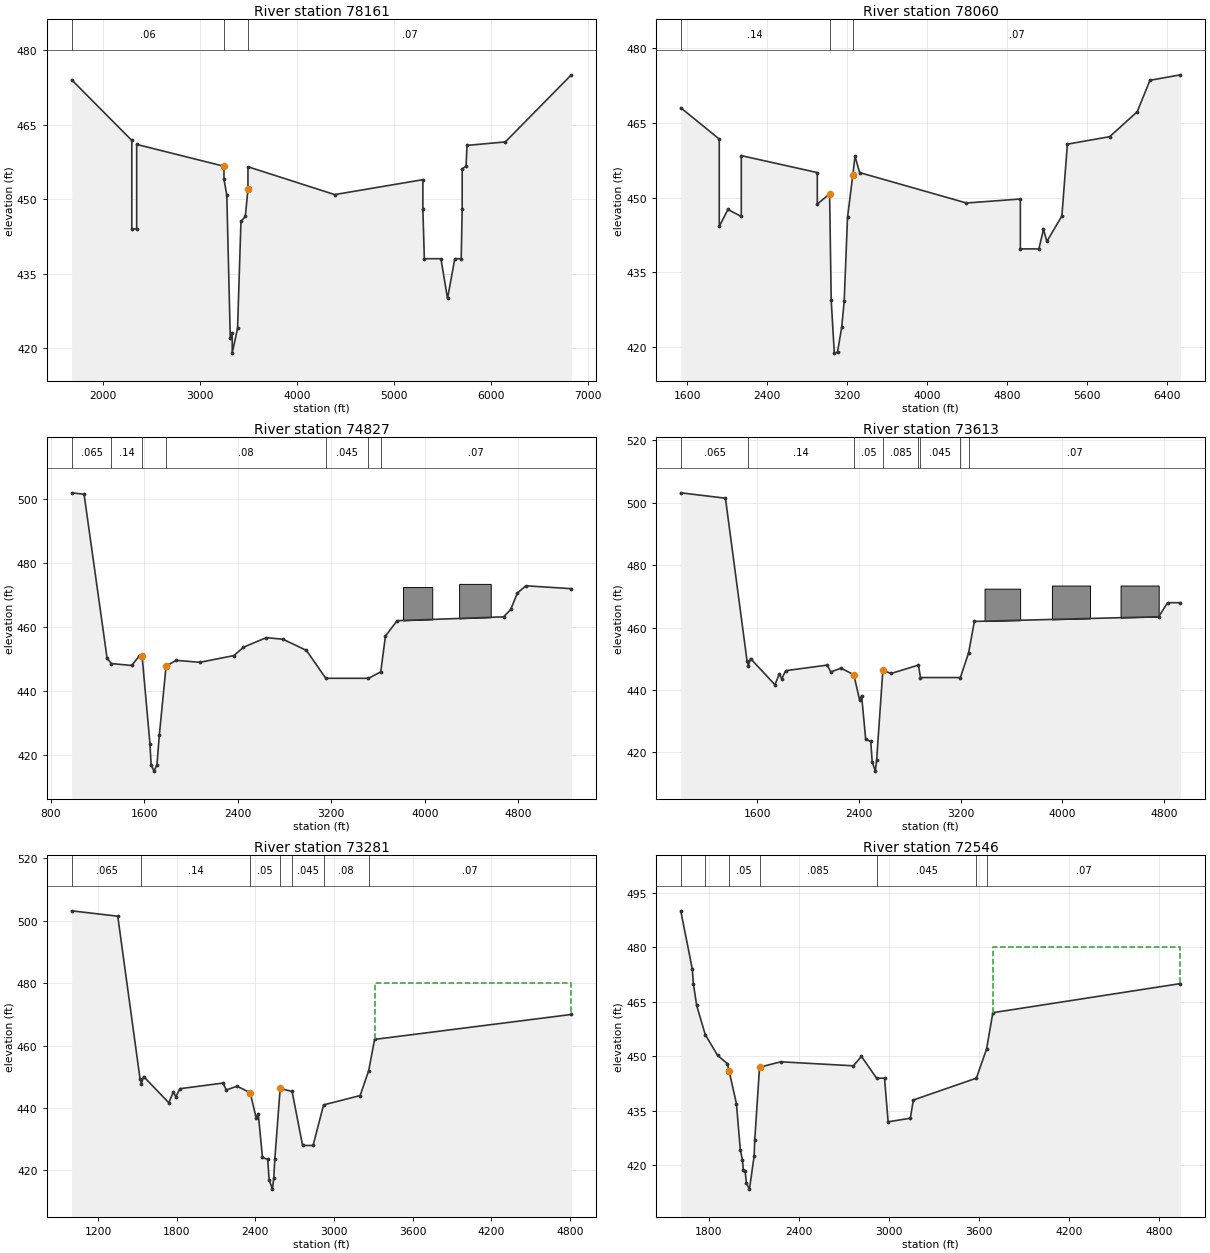
Type RM Length L Ch R = 1 ,78161   ,100,100,100
BEGIN DESCRIPTION:
This cross section corresponds to cross section 78183 of the non-georeferenced CDC model which was the source of this model.
LOB 'n' value lowered to 0.06.  Far LOB extended with 1991 topo.  Cont/Exp raised due to railroad.   High ground from d/s added to ROB.
END DESCRIPTION:
XS GIS Cut Line= 6
    2413898.2267 6982891.6724251 2413803.3873234  6982470.609947
 2413746.8392082 6981998.9511134 2413358.9843408 6980890.2719003
 2413285.8043691 6980465.8268831 2413400.2562399 6977834.6457937
#Sta/Elev= 30
    1680     474    2300   461.8    2300     444    2350     444    2350     461
    3250   456.6    3250     454    3279   450.8    3315     422    3335     423
    3335     419    3390     424    3425   445.5    3470   446.5    3497     452
    3497   456.5    4391   450.9    5300   453.9    5300     448    5315     438
    5486     438    5554     430    5629     438    5695     438    5705     448
    5705   456.1    5745   456.6    5755   460.8    6150   461.5    6830     475
#Mann= 3 ,0,0
    1680     .06       0    3250     .05       0    3497     .07       0
Bank Sta=3250,3497
XS Rating Curve= 0 ,0
Exp/Cntr=0.5,0.3

Type RM Length L Ch R = 1 ,78060   ,1773,3234,942
BEGIN DESCRIPTION:
This cross section corresponds to cross section 78083 of the non-georeferenced CDC model which was the source of this model.
Flow limit due to railroad.  Railroad lowered 2' below rails.  Cont/Exp raised due to railroad.  'n' value lowered in ROB  to be consistent.
----------------------------------------
CDC ARL071405-1 SVC Park Highlands, LTD.
In ROB beyond eff. flow line - storage mitigation area d/s SH 360 d/s cross-sect 78083.
----------------------------------------
END DESCRIPTION:
XS GIS Cut Line= 6
  2413968.174395 6982757.5342419 2413837.2038568 6981955.8740998
 2413672.5490024 6981421.6589609 2413449.3489895 6980847.1948867
 2413376.1690177 6980422.74986952413491.596804136977856.21586878
#Sta/Elev= 30
    1535     468    1920  461.72    1920   444.2    2006   447.6    2140   446.2
    2140   458.4    2900     455    2900   448.7    3023   450.7    3039   429.4
    3070   418.8    3102     419    3144     424    3169   429.3    3202     446
    3255   454.5    3277   458.3    3323     455    4391   448.9    4930   449.7
    4930   439.7    5115   439.7    5161   443.6    5195   441.2    5345   446.3
    5400   460.7    5823   462.2    6098   467.2    6225   473.5    6530   474.6
#Mann= 3 ,0,0
    1535     .14       0    3023     .05       0    3255     .07       0
Bank Sta=3023,3255
XS Rating Curve= 0 ,0
Exp/Cntr=0.5,0.3

Type RM Length L Ch R = 1 ,74827   ,869,1214,1352
BEGIN DESCRIPTION:
This cross section corresponds to cross section 74891 of the non-georeferenced CDC model which was the source of this model.
END DESCRIPTION:
XS GIS Cut Line= 6
  2415471.004723 6981381.1974277 2414978.3492123 6981131.3980585
 2414590.3768912 6980934.6858535 2414446.0609068 6979635.9505901
 2414301.7314711 6978337.2163109 2414228.4960533 6977670.7035363
#Sta/Elev= 30
 980.741501.94171086.999   501.51283.878450.2066    1321   448.6    1494     448
    1557   450.9    1583   450.9    1650   423.6    1660     417    1685     415
    1710     417    1730   426.2    1788   447.8    1874   449.6    2078     449
    2368   451.1    2449   453.7    2644   456.7    2788   456.2    2988   452.7
    3153     444    3518     444    3623     446    3663   457.2    3763     462
    4673   463.2    4734   465.5    4790   470.6    4863   472.9    5252     472
#Mann= 7 ,-1,0
 980.741    .065       0    1321     .14       0    1583    .055       0
    1788     .08       0    3153    .045       0    3518     .08       0
    3623     .07       0
#Block Obstruct= 2 ,-1
    3813    4063   472.5    4293    4563   473.5
Bank Sta=1583,1788
XS Rating Curve= 0 ,0
Exp/Cntr=0.3,0.1

Type RM Length L Ch R = 1 ,73613   ,332,332,332
BEGIN DESCRIPTION:
This cross section corresponds to cross section 73634 of the non-georeferenced CDC model which was the source of this model.
END DESCRIPTION:
XS GIS Cut Line= 6
  2415893.225007 6981445.9968387 2415683.3592852 6980825.8635646
 2415443.5021534 6980117.1418849 2414906.6088702 6979000.7527135
 2414617.4969157 6978399.6239945 2414347.8555254 6977839.0005659
#Sta/Elev= 30
  999.19503.22311350.739   501.51520.912 449.257    1531   447.8    1548   450.1
    1740   441.7    1775   445.2    1793   443.6    1825   446.2    2152     448
    2179   445.8    2261     447    2361   444.9    2406   436.8    2422   438.2
    2454   424.2    2494   423.5    2505     417    2530     414    2540   417.5
    2589   446.3    2653   445.3    2869     448    2885     444    3199     444
    3264     452    3309     462    4759   463.5    4829     468    4930     468
#Mann= 8 ,-1,0
  999.19    .065       0    1531     .14       0    2361     .05       0
    2589    .085       0    2869     .08       0    2885    .045       0
    3199     .08       0    3264     .07       0
#Block Obstruct= 3 ,-1
    3389    3669   472.5    3919    4219   473.5    4459    4759   473.5
Bank Sta=2361,2589
XS Rating Curve= 0 ,0
Exp/Cntr=0.3,0.1

Type RM Length L Ch R = 1 ,73281   ,735,735,735
BEGIN DESCRIPTION:
This cross section corresponds to cross section 73460 of the non-georeferenced CDC model which was the source of this model.
Copy of 73634
END DESCRIPTION:
XS GIS Cut Line= 6
  2416134.643815 6981463.9469341 2416109.5634853  6981371.966475
 2416083.0920816 6981274.3898985 2415706.7854195 6980139.3275361
 2415321.4941953 6979306.59068452414691.625355876977945.24383483
#Sta/Elev= 30
  999.19503.22311350.739   501.51520.912 449.257    1531   447.8    1548   450.1
    1740   441.7    1775   445.2    1793   443.6    1825   446.2    2152     448
    2179   445.8    2261     447    2361   444.9    2406   436.8    2422   438.2
    2454   424.2    2494   423.5    2505     417    2530     414    2540   417.5
    2548   423.5    2589   446.3    2680   445.3    2760     428    2840     428
    2920     441    3199     444    3264     452    3309     462    4809     470
#Mann= 7 ,-1,0
  999.19    .065       0    1531     .14       0    2361     .05       0
    2589    .085       0    2680    .045       0    2920     .08       0
    3264     .07       0
#XS Ineff= 1 ,-1
    3309    4809     480
Permanent Ineff=
       F
Bank Sta=2361,2589
XS Rating Curve= 0 ,0
Exp/Cntr=0.3,0.1

Type RM Length L Ch R = 1 ,72546   ,121,121,121
BEGIN DESCRIPTION:
This cross section corresponds to cross section 72628 of the non-georeferenced CDC model which was the source of this model.
Copy of 72500
END DESCRIPTION:
XS GIS Cut Line= 4
  2416411.804022 6980803.2500927 2416286.0418069 6980402.6304871
 2415316.5450583 6979051.08036872414587.956632566978035.37425674
#Sta/Elev= 30
    1614     490    1691     474    1698     470    1720     464    1777     456
    1859   450.3    1924     448    1936     446    1985     437    2011   424.3
    2025   421.6    2031   418.8    2043   418.4    2052   415.1    2072   413.5
    2103   422.6    2107   426.9    2139     447    2280   448.5    2765   447.4
    2818     450    2919     444    2972     444    2996     432    3144     433
    3164     438    3584     444    3652     452    3694     462    4944     470
#Mann= 7 ,-1,0
    1614    .065       0    1777     .12       0    1936     .05       0
    2139    .085       0    2919    .045       0    3584     .08       0
    3652     .07       0
#XS Ineff= 1 ,-1
    3694    4944     480
Permanent Ineff=
       F
Bank Sta=1936,2139
XS Rating Curve= 0 ,0
Exp/Cntr=0.3,0.1

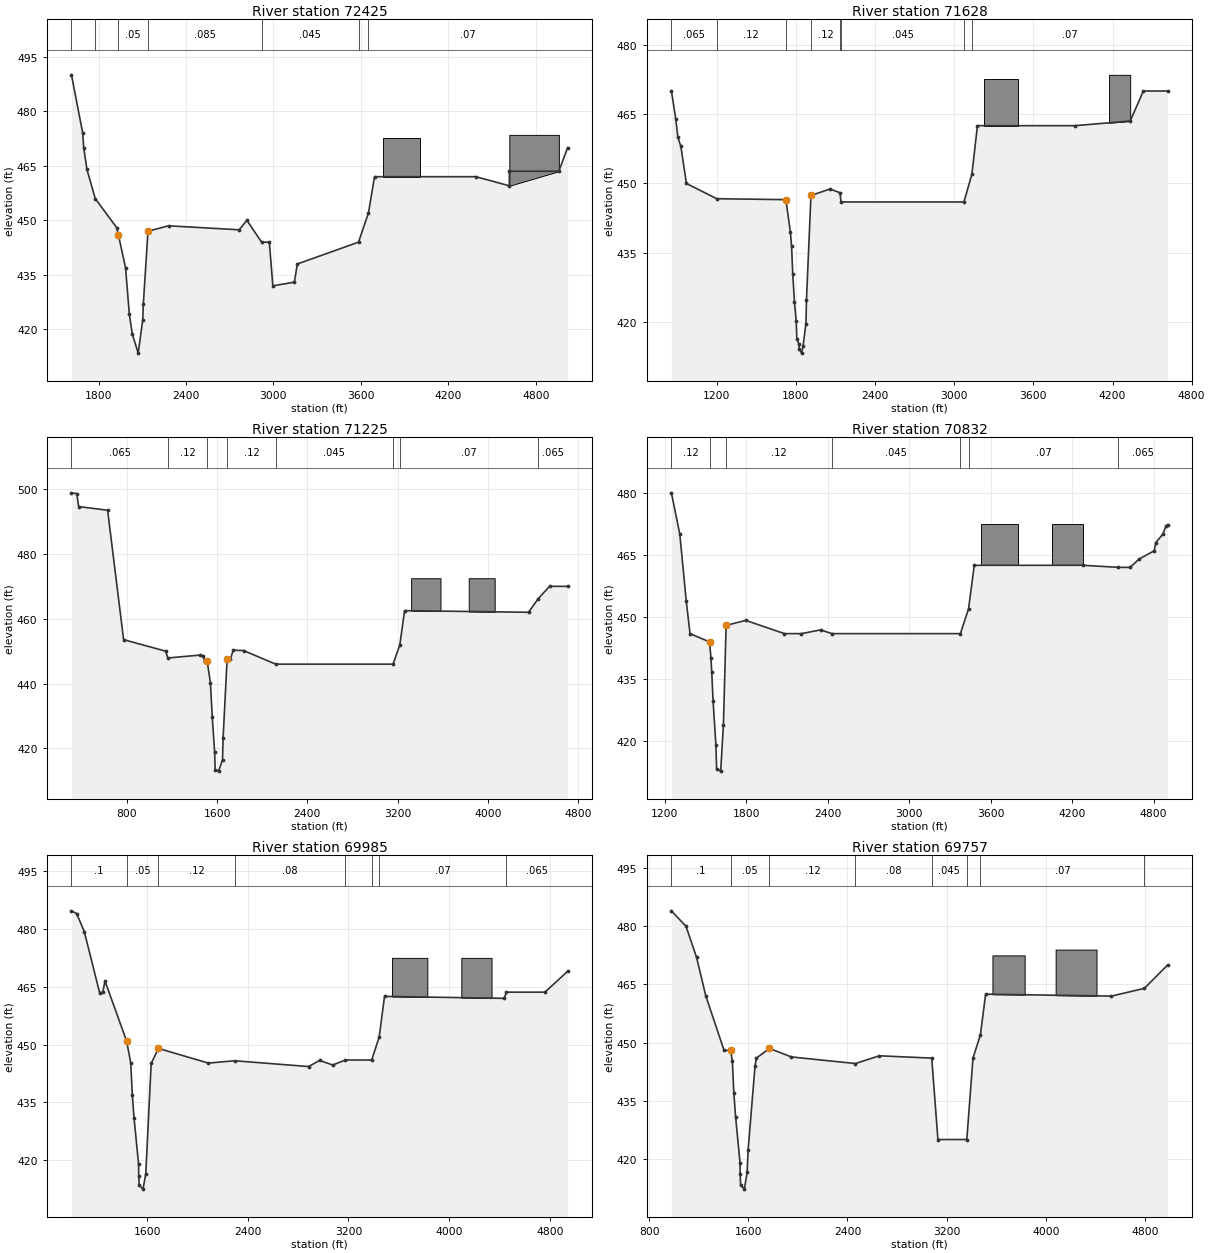
Type RM Length L Ch R = 1 ,72425   ,363,427,277
BEGIN DESCRIPTION:
This cross section corresponds to cross section 72500 of the non-georeferenced CDC model which was the source of this model.
END DESCRIPTION:
XS GIS Cut Line= 4
  2416513.265761 6980739.9887363 2416390.0452078 6980343.0594121
 2415317.8967616 6978842.4525052 2414656.4571396 6977906.9881687
#Sta/Elev= 30
    1614     490    1691     474    1698     470    1720     464    1777     456
    1924     448    1936     446    1985     437    2011   424.3    2031   418.8
    2072   413.5    2103   422.6    2107   426.9    2139     447    2280   448.5
    2765   447.4    2818     450    2919     444    2972     444    2996     432
    3144     433    3164     438    3584     444    3652     452    3694     462
    4389     462    4619   459.5    4619   463.5    4959   463.5    5019     470
#Mann= 7 ,-1,0
    1614    .065       0    1777     .12       0    1936     .05       0
    2139    .085       0    2919    .045       0    3584     .08       0
    3652     .07       0
#Block Obstruct= 2 ,-1
    3749    4009   472.5    4619    4959   473.5
Bank Sta=1936,2139
XS Rating Curve= 0 ,0
Exp/Cntr=0.3,0.1

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
Type RM Length L Ch R = 1 ,71628   ,301,403,284
BEGIN DESCRIPTION:
This cross section corresponds to cross section 71700 of the non-georeferenced CDC model which was the source of this model.
END DESCRIPTION:
XS GIS Cut Line= 4
  2417130.693476  6980475.338131 2417130.6934765  6980475.338131
 2416662.2543091 6979575.7860122 2414619.8986056 6977739.0447145
#Sta/Elev= 30
     856     470     889     464     905     460     928     458     970     450
    1200   446.7    1724   446.5    1758   439.5    1767   436.4    1776   430.4
    1789   424.3    1802   420.3    1807   416.4    1822   415.3    1825   414.2
    1843   413.3    1854   414.8    1876   419.7    1880   424.8    1914   447.4
    2058   448.8    2134     448    2142     446    3074     446    3134     452
    3176   462.5    3914   462.5    4334   463.5    4434     470    4617     470
#Mann= 8 ,-1,0
     856    .065       0    1200     .12       0    1724     .05       0
    1914     .12       0    2134     .08       0    2142    .045       0
    3074     .08       0    3134     .07       0
#Block Obstruct= 2 ,-1
    3224    3484   472.5    4174    4334   473.5
Bank Sta=1724,1914
XS Rating Curve= 0 ,0
Exp/Cntr=0.3,0.1

Type RM Length L Ch R = 1 ,71225   ,380,393,241
BEGIN DESCRIPTION:
This cross section corresponds to cross section 71246 of the non-georeferenced CDC model which was the source of this model.
----------------------------------
CDC FW020105-01 Riverpark Addition
Cross-section 71246 - 74891
Located in LOB.
----------------------------------
END DESCRIPTION:
XS GIS Cut Line= 3
     2417383.365     6980857.409     2417068.926     6979477.766
     2414657.399     6977727.086
#Sta/Elev= 30
 309.988498.8458357.3073   498.6 373.718   494.6630.1356493.4716771.8537453.5542
1144.922     450    1163   447.9    1449   448.8    1479   448.6    1489   446.7
    1512     447    1541   440.2    1557   429.7    1578     419    1583   413.5
    1613     413    1648   416.5    1653   423.1    1689   447.7    1717   447.5
    1743   450.3    1834   450.2    2119     446    3159     446    3219     452
    3261   462.5    4359     462    4445   466.2    4545     470    4705     470
#Mann= 8 ,-1,0
 309.988    .065       0    1163     .12       0    1512     .05       0
    1689     .12       0    2119    .045       0    3159     .08       0
    3219     .07       0    4445    .065       0
#Block Obstruct= 2 ,-1
    3319    3579   472.5    3829    4059   472.5
Bank Sta=1512,1689
XS Rating Curve= 0 ,0
Exp/Cntr=0.3,0.1

Type RM Length L Ch R = 1 ,70832   ,1077,847,406
BEGIN DESCRIPTION:
This cross section corresponds to cross section 70832 of the non-georeferenced CDC model which was the source of this model.
END DESCRIPTION:
XS GIS Cut Line= 3
  2417547.578325 6979894.0199558 2417460.8819769 6979419.8174921
 2414801.2832935 6977694.6723204
#Sta/Elev= 30
    1250     480    1312     470    1359     454    1387     446    1531     444
    1541   440.2    1547   436.8    1557   429.7    1578     419    1583   413.3
    1613   412.8    1633     424    1653     448    1798   449.2    2082     446
    2207     446    2348   446.9    2433     446    3378     446    3438     452
    3480   462.5    4283   462.5    4541     462    4628     462    4693     464
    4805     466    4817     468    4868     470    4892     472    4903   472.3
#Mann= 7 ,-1,0
    1250     .12       0    1531     .05       0    1653     .12       0
    2433    .045       0    3378     .08       0    3438     .07       0
    4541    .065       0
#Block Obstruct= 2 ,-1
    3533    3803   472.5    4053    4283   472.5
Bank Sta=1531,1653
XS Rating Curve= 0 ,0
Exp/Cntr=0.3,0.1

Type RM Length L Ch R = 1 ,69985   ,228,228,228
BEGIN DESCRIPTION:
This cross section corresponds to cross section 70006 of the non-georeferenced CDC model which was the source of this model.
END DESCRIPTION:
XS GIS Cut Line= 6
  2418494.785092 6979191.3750356  2417625.039457 6978837.3659011
 2417150.6247234 6978644.2800012 2416676.2044124 6978451.2009911
 2415806.4194066 6978097.24106912414857.488231366977711.10457569
#Sta/Elev= 30
    1000   484.7    1041     484    1102   479.3    1223   463.5    1249   463.6
    1266   466.5    1438   450.9    1471   445.2    1483     437    1497   430.9
    1533     419    1534     416    1538   413.5    1568   412.5    1590   416.5
    1633   445.1    1691     449    2087   445.2    2297   445.8    2884   444.3
    2970   445.9    3074   444.7    3176     446    3384     446    3444     452
    3486   462.5    4436     462    4454   463.6    4760   463.6    4940     469
#Mann= 8 ,-1,0
    1000      .1       0    1438     .05       0    1691     .12       0
    2297     .08       0    3176    .045       0    3384     .08       0
    3444     .07       0    4454    .065       0
#Block Obstruct= 2 ,-1
    3546    3826   472.5    4096    4336   472.5
Bank Sta=1438,1691
XS Rating Curve= 0 ,0
Exp/Cntr=0.3,0.1

Type RM Length L Ch R = 1 ,69757   ,166,127,109
BEGIN DESCRIPTION:
69798
END DESCRIPTION:
XS GIS Cut Line= 2
  2418583.8709296978996.755135862414833.43700001     6977612.207
#Sta/Elev= 30
     979     484    1097     480    1182     472    1257     462    1404     448
    1457     448    1471   445.2    1483     437    1497   430.9    1533     419
    1534     416    1538   413.2    1568   412.2    1590   416.5    1598   422.2
    1654     444    1665     446    1770   448.5    1948   446.3    2464   444.6
    2657   446.6    3080     446    3130     425    3363     425    3413     446
    3473     452    3515   462.5    4530     462    4796     464    4983     470
#Mann= 8 ,-1,0
     979      .1       0    1457     .05       0    1770     .12       0
    2464     .08       0    3080    .045       0    3363     .08       0
    3473     .07       0    4796    .065       0
#XS Ineff= 1 ,-1
    3080    3413     446
Permanent Ineff=
       T
#Block Obstruct= 2 ,-1
    3570    3830   472.5    4080    4410     474
Bank Sta=1457,1770
XS Rating Curve= 0 ,0
Exp/Cntr=0.3,0.1