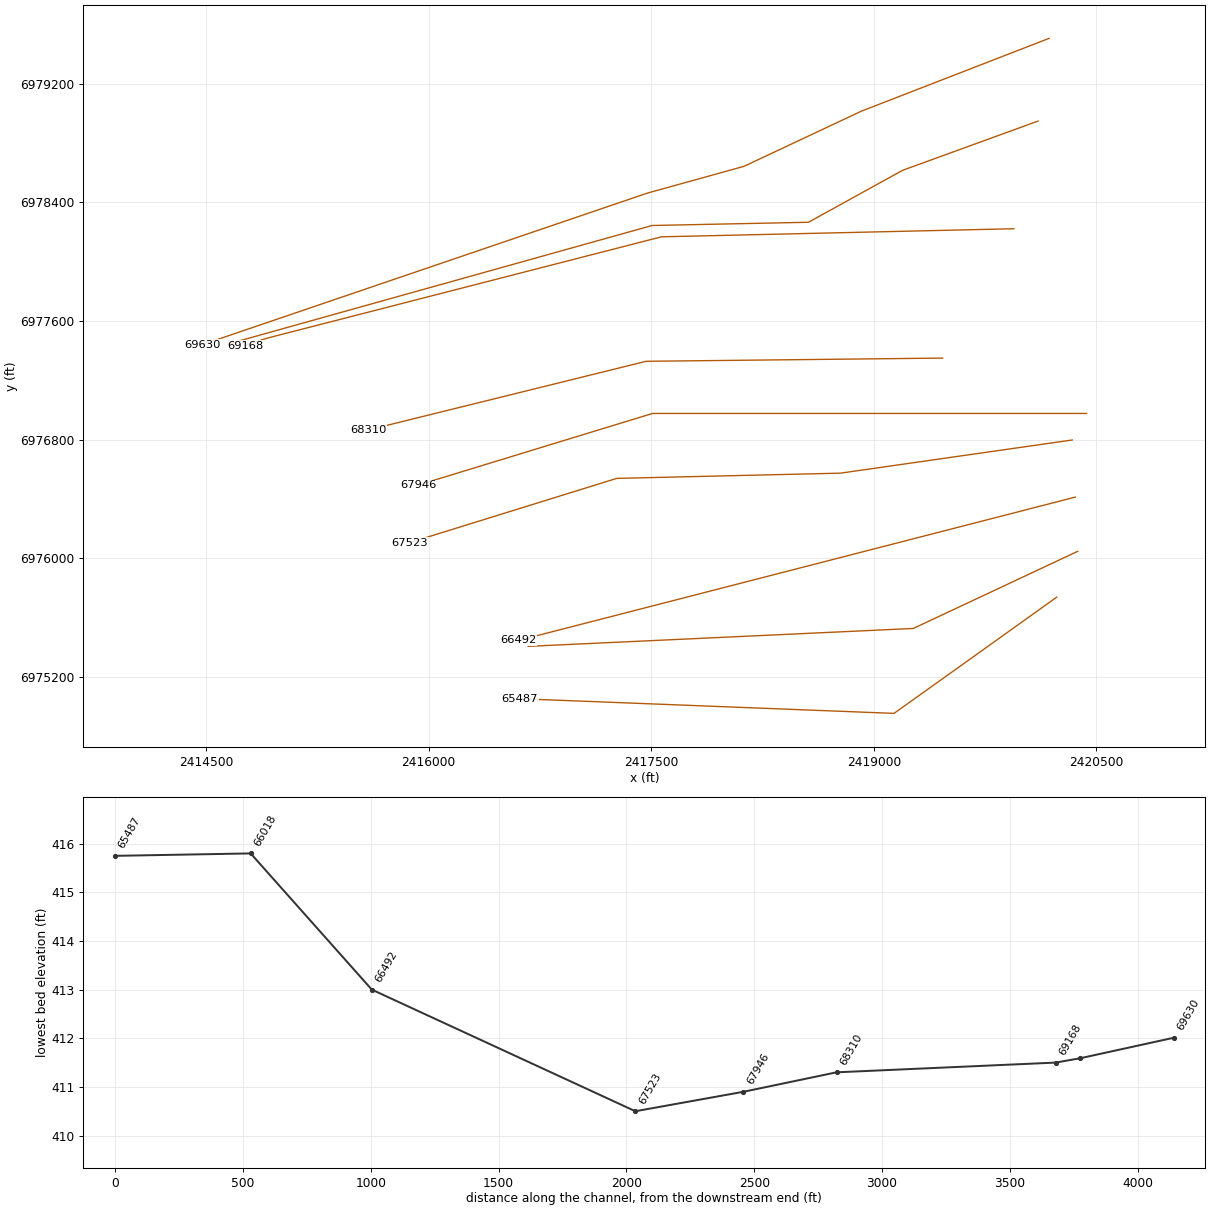
HEC-RAS study CDC_Consolidated_Model.prj: Upper Trinity CDC Consolidated Model

--- CDC_Consolidated_Model.g04 (geometry) --- (continued)

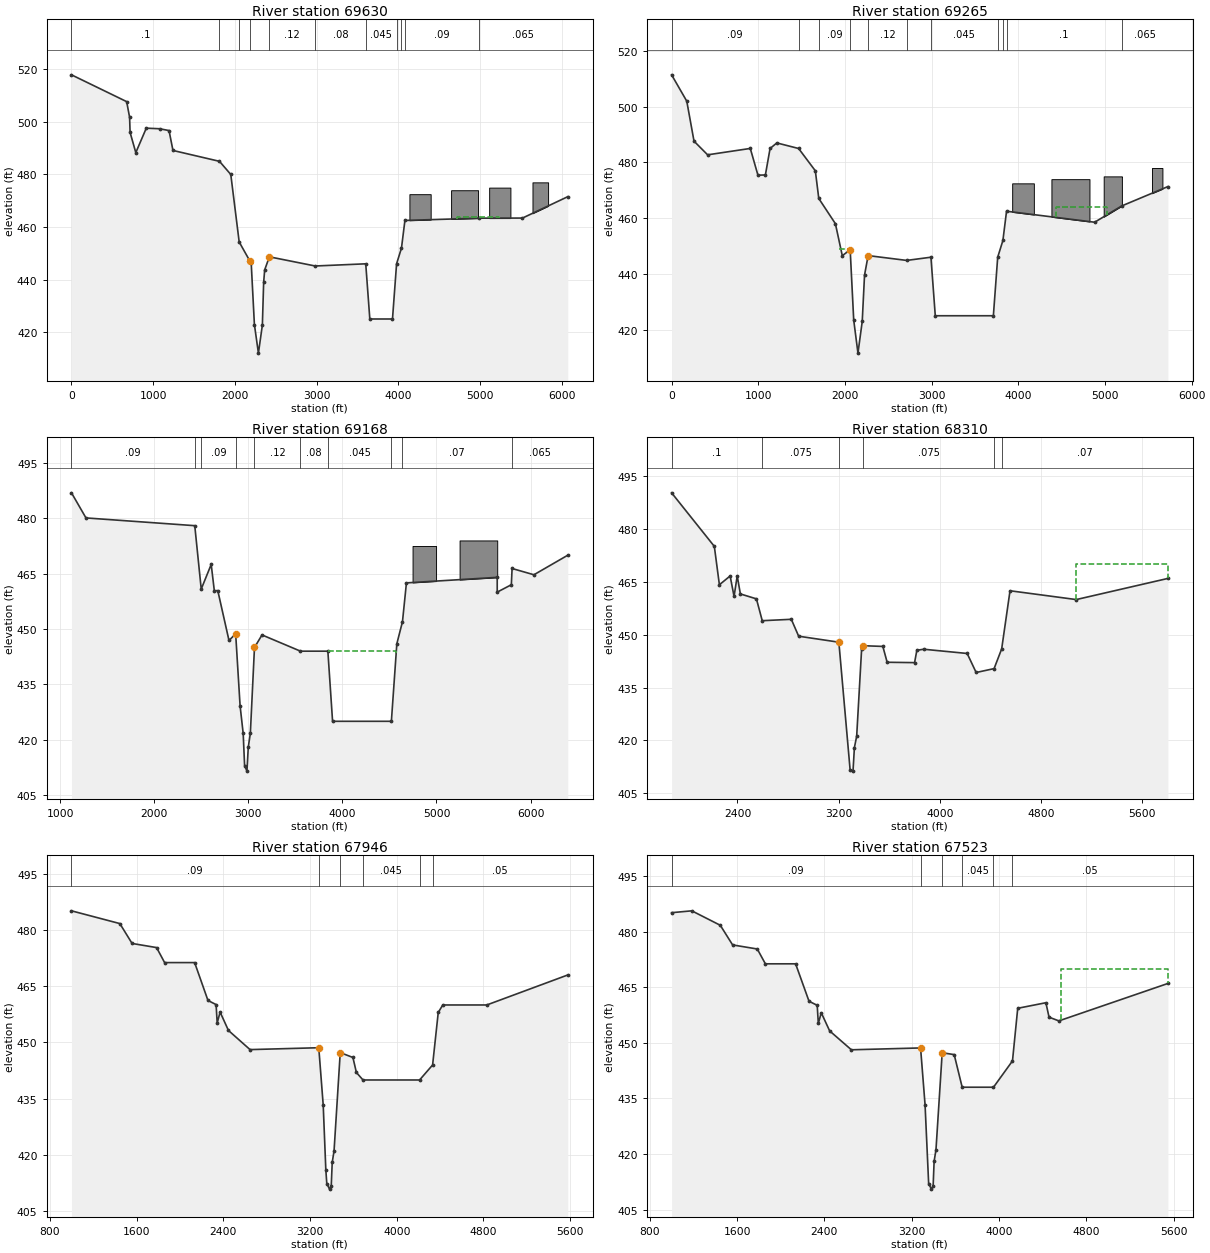
Type RM Length L Ch R = 1 ,69630   ,425,365,210
BEGIN DESCRIPTION:
69630
2009 LiDAR - LOB Includes Pettigrew Fill
END DESCRIPTION:
XS GIS Cut Line= 5
  2420181.3521216979505.819805952418915.727122046979014.50036153
2418125.796566436978642.972583742417472.071161366978461.55258952
2414474.024286366977440.01034415
#Sta/Elev= 30
       0  517.92  675.07  507.72  711.01  501.76  716.97  496.01  786.99  488.32
  915.19  497.62 1077.64   497.4 1193.47  496.71 1241.54  489.14 1810.87     485
 1948.99     480 2051.75  454.31 2179.17  447.24 2198.94  446.23 2237.89   422.9
    2287  412.01 2335.36  422.68  2351.1  438.91 2363.59  443.69 2421.06  448.66
  2981.7  445.17    3600     446    3650     425 3927.34     425 3977.34     446
 4037.34     452 4079.34   462.5 4986.41  463.37 5517.64  463.41    6072  471.55
#Mann= 11 ,-1,0
       0      .1       0 1810.87     .07       0 2051.75      .1       0
 2179.17     .05       0 2421.06     .12       0  2981.7     .08       0
    3600    .045       0 3977.34     .08       0 4037.34     .07       0
 4079.34     .09       0 4986.41    .065       0
#XS Ineff= 2 ,-1
    3600 3977.34     446 4715.94 5235.39  463.64
Permanent Ineff=
       T       F
#Block Obstruct= 4 ,-1
    5110    5370     475    5640    5831     477 4134.34 4394.34   472.5
 4644.34 4974.34     474
Bank Sta=2179.17,2421.06
XS Rating Curve= 0 ,0
Exp/Cntr=0.3,0.1

Type RM Length L Ch R = 1 ,69265   ,78,97,80
BEGIN DESCRIPTION:
69265
2009 LiDAR - LOB Includes Pettigrew Fill
END DESCRIPTION:
XS GIS Cut Line= 5
  2420106.5098186978947.835141612419193.749402116978615.80389161
2418559.634818736978265.543474962417505.815374346978243.69741014
2414644.270000046977443.35000001
#Sta/Elev= 30
       0  511.43  175.08  501.97  258.55  487.63   415.5  482.73  907.77  485.02
  996.08  475.43 1082.03  475.51    1136     485    1214     487 1465.46     485
 1658.23     477 1697.95  467.07 1889.67  458.03 1969.17  446.55 2060.18  448.66
    2101  423.46    2150  411.59 2199.25  422.95 2225.88  439.59 2267.44  446.58
 2712.06  444.85 2992.02     446 3042.02     425 3712.25     425 3762.25     446
 3822.25     452 3864.25   462.5 4880.77  458.55 5192.84  464.39    5726  471.34
#Mann= 11 ,-1,0
       0     .09       0 1465.46     .07       0 1697.95     .09       0
 2060.18     .05       0 2267.44     .12       0 2712.06     .08       0
 2992.02    .045       0 3762.25     .08       0 3822.25     .07       0
 3864.25      .1       0 5192.84    .065       0
#XS Ineff= 4 ,-1
  164.38    1214     487  1934.3 2055.48     449 2992.02 3762.25     446
 4437.25 5027.87  463.98
Permanent Ineff=
       F       F       T       F
#Block Obstruct= 4 ,-1
 3929.25 4179.25   472.5    4382    4821     474    4985    5195     475
  5541.8  5662.6     478
Bank Sta=2060.18,2267.44
XS Rating Curve= 0 ,0
Exp/Cntr=0.3,0.1

Type RM Length L Ch R = 1 ,69168   ,850,857,800
BEGIN DESCRIPTION:
69186
----------------------------------------------------------------
LOMR#17-06-0659P & CDC FW050115-01 Pettigrew Development
Cross-sections 69186 - 69630
----------------------------------------------------------------
LOB includes Pettigrew Fill.
END DESCRIPTION:
XS GIS Cut Line= 6
  2419943.983309 6978221.9225782  2418749.186815 6978194.4262421
 2417568.4959349 6978167.2980156 2416327.9416575 6977848.2471445
  2414910.690555 6977483.8148025 2414762.2476104 6977434.2709383
#Sta/Elev= 30
    1121   486.9    1275   480.1 2431.28     478    2500  460.82    2606   467.5
    2639   460.4    2676   460.4    2795   446.9    2866   448.7    2913   429.2
    2946   421.7    2961     413    2986   411.5    3000     418    3022   421.7
    3066     445    3146   448.4    3555     444    3846     444    3896     425
    4521     425    4579     446    4639     452    4681   462.5    5646     464
    5646     460    5796     462    5804   466.4    6036   464.7    6396     470
#Mann= 10 ,-1,0
    1121     .09       0 2431.28     .07       0    2500     .09       0
    2866     .05       0    3066     .12       0    3555     .08       0
    3846    .045       0    4521     .08       0    4639     .07       0
    5804    .065       0
#XS Ineff= 1 ,-1
    3846    4571     444
Permanent Ineff=
       T
#Block Obstruct= 2 ,-1
    4746    4996   472.5    5246    5646     474
Bank Sta=2866,3066
XS Rating Curve= 0 ,0
Exp/Cntr=0.3,0.1

Type RM Length L Ch R = 1 ,68310   ,339,364,334
BEGIN DESCRIPTION:
This cross section corresponds to cross section 68329 of the non-georeferenced CDC model which was the source of this model.
END DESCRIPTION:
XS GIS Cut Line= 6
  2419464.020533 6977349.6039763 2418555.6301155 6977339.7366786
 2417968.6099641 6977333.3741585 2417465.4498812 6977327.9289594
 2416631.7796325 6977121.72530362415594.513645666976865.18881984
#Sta/Elev= 30
    1879   490.3    2217   475.1    2257   464.2    2342   466.7    2373   460.9
    2398   466.7    2423   461.6    2550   460.2    2596     454    2826   454.4
    2884   449.6    3202   447.9    3291   411.7    3314   411.3    3325     418
    3343   421.2    3382   445.9    3395   446.9    3550   446.7    3584   442.2
    3801   442.1    3819   445.6    3873   445.9    4217   444.7    4288   439.3
    4430   440.4    4490     446    4556   462.5    5080     460    5805     466
#Mann= 6 ,-1,0
    1879      .1       0    2596    .075       0    3202     .05       0
    3395    .075       0    4430     .08       0    4490     .07       0
#XS Ineff= 1 ,-1
    5080    5805     470
Permanent Ineff=
       F
Bank Sta=3202,3395
XS Rating Curve= 0 ,0
Exp/Cntr=0.3,0.1

Type RM Length L Ch R = 1 ,67946   ,454,423,449
BEGIN DESCRIPTION:
This cross section corresponds to cross section 67950 of the non-georeferenced CDC model which was the source of this model.
END DESCRIPTION:
XS GIS Cut Line= 3
  2420433.972159 6976976.2410145 2417508.6249917 6976976.2410145
 2415928.2474444 6976492.8486351
#Sta/Elev= 30
    1000   485.1    1446   481.7    1559   476.4    1785   475.3    1859   471.3
    2136   471.3    2259   461.2    2334   460.1    2344   455.2    2371   458.1
    2448   453.2    2647   448.1    3281   448.6    3322   433.3    3346   416.1
    3355   412.4    3380   410.9    3396   411.7    3405     418    3422   421.1
    3479   447.3    3596     446    3628     442    3689     440    4211     440
    4331     444    4383     458    4425     460    4831     460    5578     468
#Mann= 6 ,-1,0
    1000     .09       0    3281    .055       0    3479     .07       0
    3689    .045       0    4211     .07       0    4331     .05       0
Bank Sta=3281,3479
XS Rating Curve= 0 ,0
Exp/Cntr=0.3,0.1

Type RM Length L Ch R = 1 ,67523   ,522,1031,853
BEGIN DESCRIPTION:
This cross section corresponds to cross section 67543 of the non-georeferenced CDC model which was the source of this model.
END DESCRIPTION:
XS GIS Cut Line= 6
    2420337.2381 6976797.2948501 2419597.4981105 6976691.3432903
 2418775.5591376 6976573.6391294 2417937.7222306 6976554.0158091
 2417267.4519176 6976538.33309772415872.391759036976105.24664666
#Sta/Elev= 30
    1000   485.1    1185   485.6    1446   481.7    1559   476.4    1785   475.3
    1859   471.3    2136   471.3    2259   461.2    2334   460.1    2344   455.2
    2371   458.1    2448   453.2    2647   448.1    3281   448.6    3322   433.3
    3355     412    3380   410.5    3396   411.3    3405     418    3422   421.1
    3479   447.3    3589   446.8    3662     438    3949     438    4123   445.1
    4171   459.3    4429   460.8    4458   456.9    4548   455.9    5547     466
#Mann= 6 ,-1,0
    1000     .09       0    3281    .055       0    3479     .07       0
    3662    .045       0    3949     .07       0    4123     .05       0
#XS Ineff= 1 ,-1
    4567    5547     470
Permanent Ineff=
       F
Bank Sta=3281,3479
XS Rating Curve= 0 ,0
Exp/Cntr=0.3,0.1

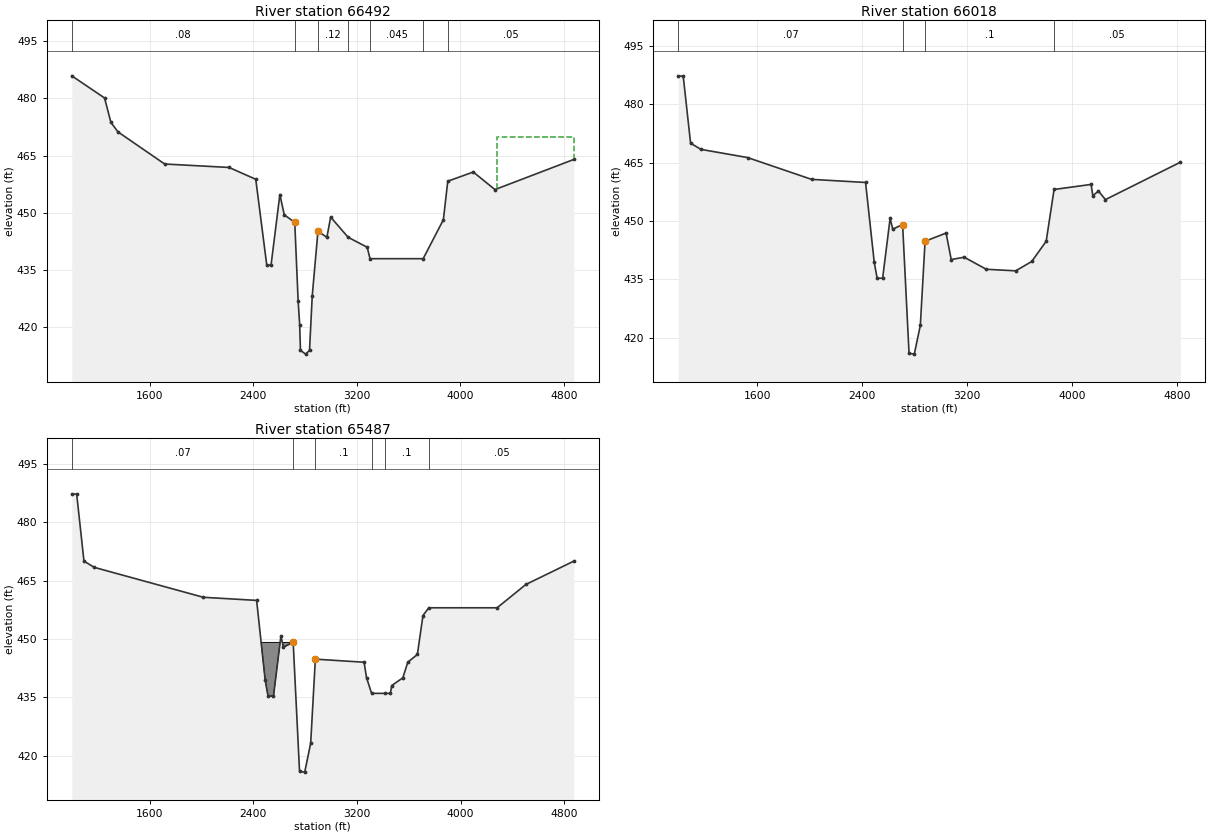
Type RM Length L Ch R = 1 ,66492   ,526,474,298
BEGIN DESCRIPTION:
This cross section corresponds to cross section 66515 of the non-georeferenced CDC model which was the source of this model.
END DESCRIPTION:
XS GIS Cut Line= 6
  2420357.846983 6976412.1230482 2419529.0172763 6976198.6093677
 2418948.8301165 6976049.1624881 2418534.4073889 6975942.4212317
 2417705.5540597 6975728.95446712416605.313413346975445.62587406
#Sta/Elev= 30
    1000   485.9    1253   480.1    1302   473.7    1357   471.2    1717   462.8
    2214   461.9    2420   458.8    2505   436.3    2538   436.3    2606   454.8
    2640   449.5    2721   447.5    2747     427    2759   420.7    2765     414
    2805     413    2835     414    2856   428.3    2900   445.2    2969   443.6
    2998   448.9    3133   443.6    3280     441    3302     438    3712     438
    3868   448.2    3902   458.3    4099   460.7    4266   456.1    4875     464
#Mann= 7 ,-1,0
    1000     .08       0    2721     .05       0    2900     .12       0
    3133     .07       0    3302    .045       0    3712     .07       0
    3902     .05       0
#XS Ineff= 1 ,-1
    4285    4875     470
Permanent Ineff=
       F
#Block Obstruct= 2 , 0
            2606   454.8
Bank Sta=2721,2900
XS Rating Curve= 0 ,0
Exp/Cntr=0.3,0.1

Type RM Length L Ch R = 1 ,66018   ,209,530,426
BEGIN DESCRIPTION:
This cross section corresponds to cross section 66037 of the non-georeferenced CDC model which was the source of this model.
END DESCRIPTION:
XS GIS Cut Line= 6
  2420373.650101 6976046.3809976 2419819.9149885 6975786.3592079
 2419266.1710172 6975526.3469327 2418596.2547062 6975495.1635961
 2417926.3370827  6975463.9940392416670.475325896975405.59604374
#Sta/Elev= 30
    1000   487.3    1038   487.2    1094     470    1173   468.4    1528   466.3
    2015   460.7    2426   459.9    2492   439.4    2514   435.3    2556   435.3
    2613   450.7    2633   447.9    2708   449.1    2757     416    2797   415.8
    2843   423.2    2879   444.8    3039   446.9    3078   440.1    3177   440.7
    3345   437.6    3569   437.2    3691   439.6    3801   444.8    3861   458.1
    4143   459.4    4156   456.5    4199   457.7    4252   455.5    4822   465.1
#Mann= 4 ,-1,0
    1000     .07       0    2708    .055       0    2879      .1       0
    3861     .05       0
#Block Obstruct= 2 , 0
            2681   449.1
Bank Sta=2708,2879
XS Rating Curve= 0 ,0
Exp/Cntr=0.3,0.1

Type RM Length L Ch R = 1 ,65487   ,790,1998,1603
BEGIN DESCRIPTION:
This cross section corresponds to cross section 65500 of the non-georeferenced CDC model which was the source of this model.
END DESCRIPTION:
XS GIS Cut Line= 4
  2420232.389229 6975737.3304346 2419637.9261792 6975312.0264951
  2419136.229348 6974953.6715688 2416615.2927888 6975052.3741273
#Sta/Elev= 30
    1000   487.3    1038   487.2    1094     470    1173   468.4    2015   460.7
    2426   459.9    2492   439.4    2514   435.3    2556   435.3    2613   450.7
    2633   447.9    2708   449.1    2757  415.95    2797  415.75    2843   423.2
    2879   444.8    3255     444    3274     440    3313     436    3420     436
    3458     436    3468     438    3554     440    3592     444    3666     446
    3709     456    3754     458    4281     458    4503     464    4873     470
#Mann= 6 ,-1,0
    1000     .07       0    2708    .055       0    2879      .1       0
    3313    .045       0    3420      .1       0    3754     .05       0
#Block Obstruct= 2 , 0
       0    2681   449.1               0
Bank Sta=2708,2879
XS Rating Curve= 0 ,0
Exp/Cntr=0.3,0.1