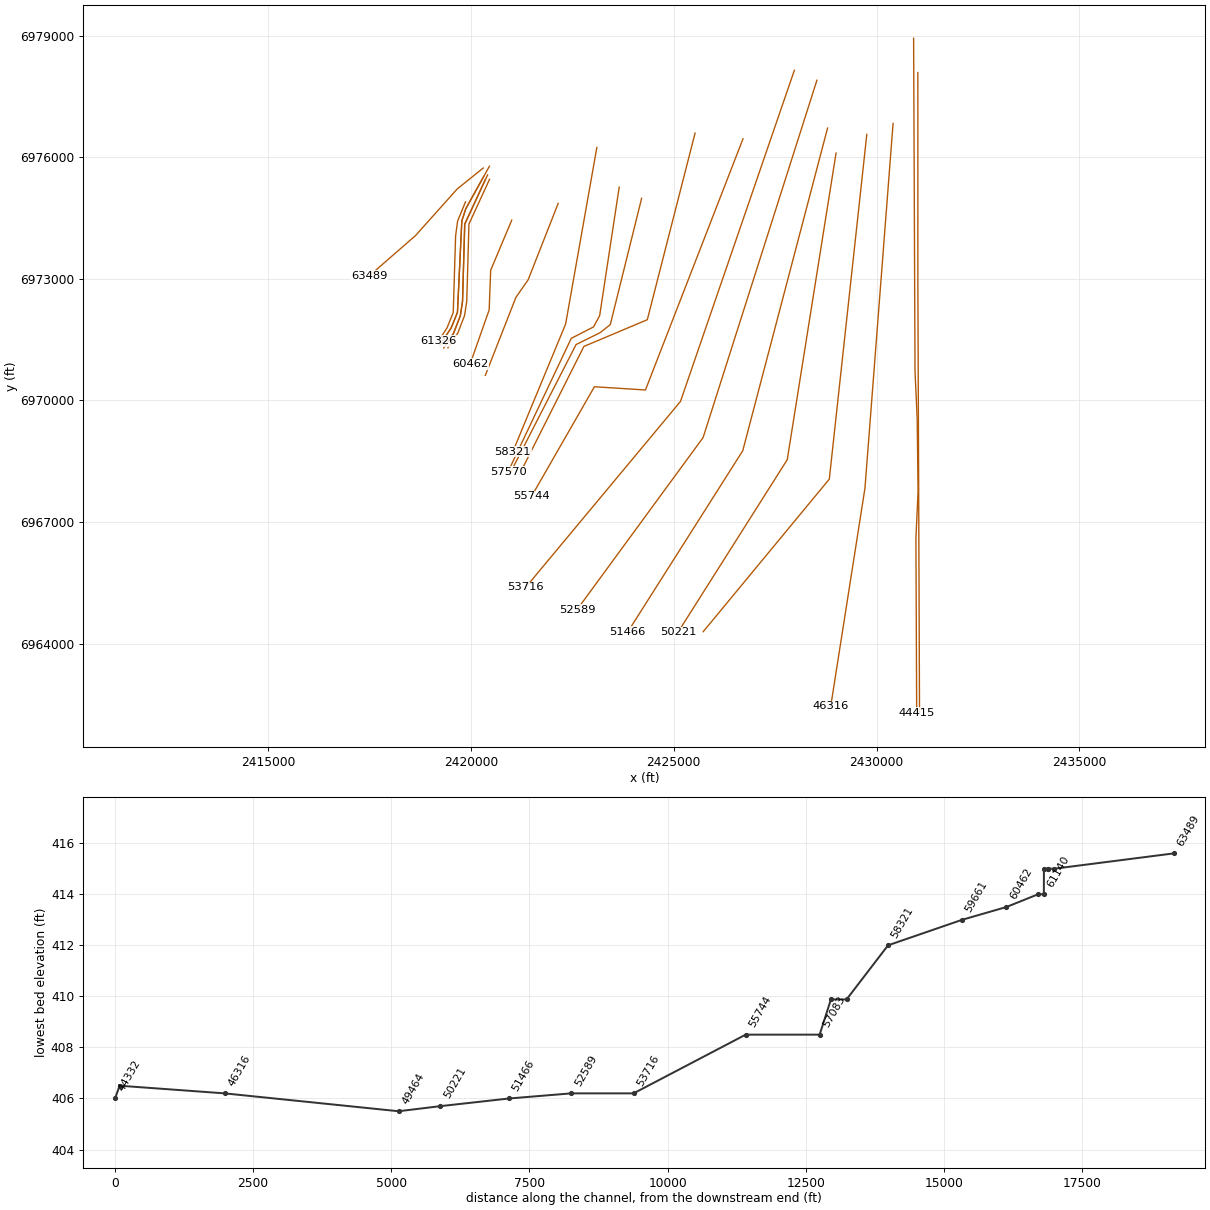
HEC-RAS study CDC_Consolidated_Model.prj: Upper Trinity CDC Consolidated Model

--- CDC_Consolidated_Model.g04 (geometry) --- (continued)

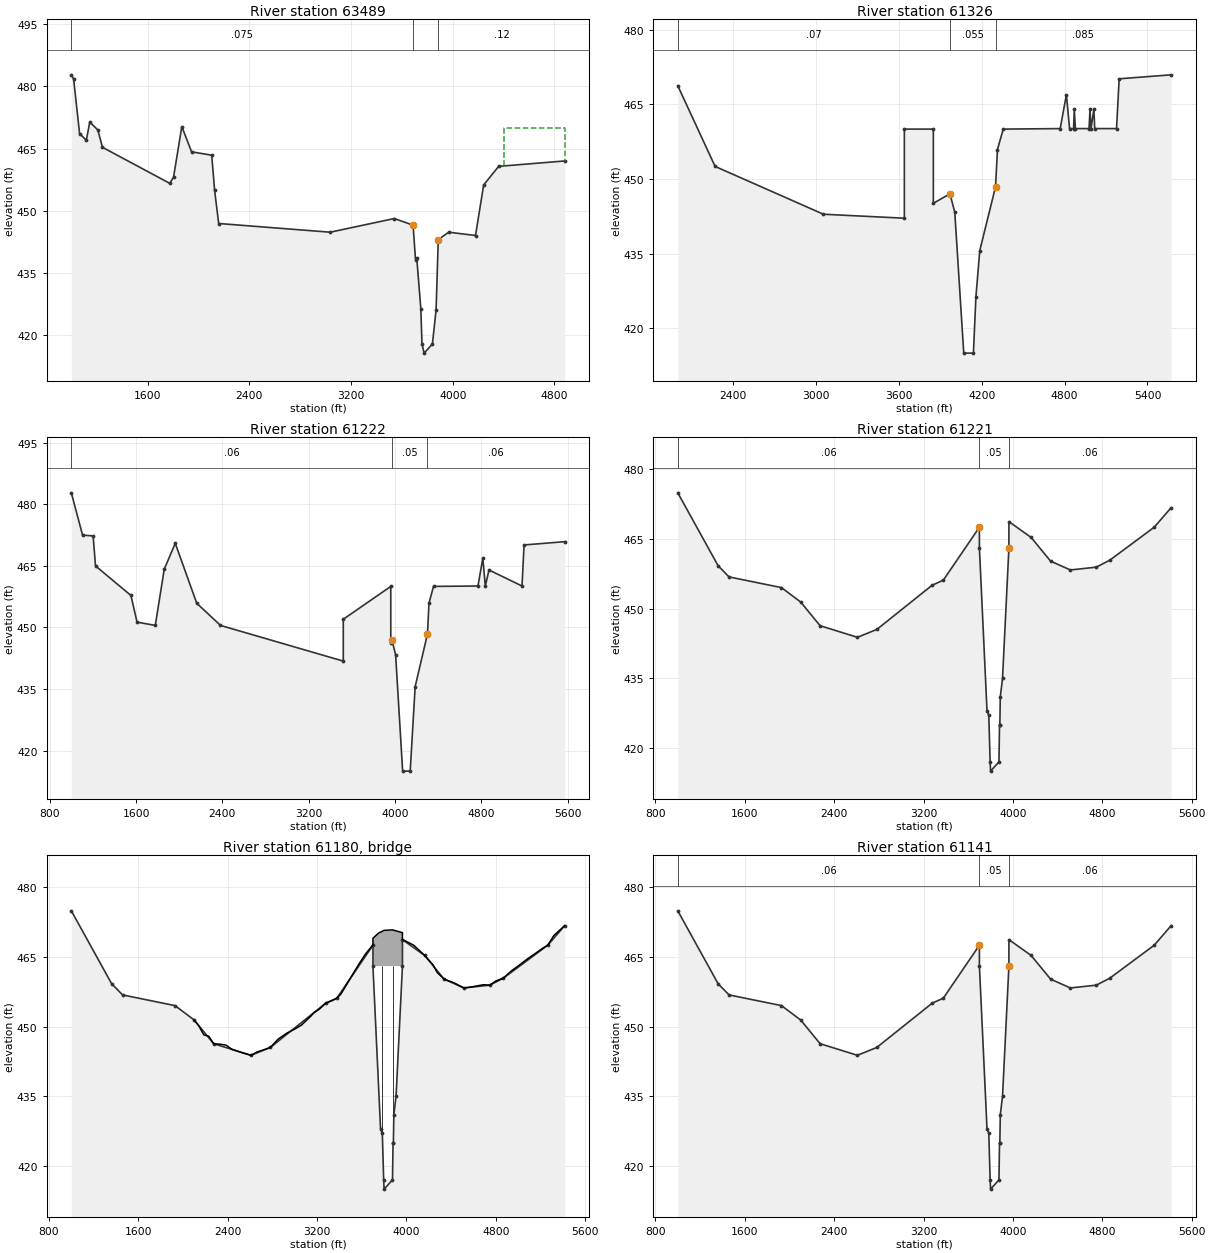
Type RM Length L Ch R = 1 ,63489   ,1000,2164,2351
BEGIN DESCRIPTION:
This cross section corresponds to cross section 63507 of the non-georeferenced CDC model which was the source of this model.
----------------------------------------------
Great Southwestern Development CDC GP120899-01
Located in ROB.
Cross-sections 65500 - 74891
----------------------------------------------
END DESCRIPTION:
XS GIS Cut Line= 6
  2420304.030616 6975732.7746982 2419661.9809212 6975215.3531321
 2419118.1667201 6974606.6660292 2418634.7588942  6974065.618883
 2418061.6914708 6973566.71961832417493.125881256973071.76098912
#Sta/Elev= 30
    1000   482.8    1018   481.8    1065   468.6    1118     467    1145   471.4
    1208   469.5    1245   465.3    1774   456.6    1804   458.1    1869   470.3
    1946   464.2    2104   463.4    2127   454.9    2159   446.9    3036   444.8
    3540   448.1    3688   446.5    3707   438.2    3717   438.5    3749   426.3
    3758   417.8    3775   415.6    3840   417.8    3869   426.1    3886     443
    3968   444.8    4179     444    4243   456.2    4361   460.7    4880     462
#Mann= 3 ,0,0
    1000    .075       0    3688    .055       0    3886     .12       0
#XS Ineff= 2 , 0
       0                    4400       0     470
Permanent Ineff=
       F       T
Bank Sta=3688,3886
XS Rating Curve= 0 ,0
Exp/Cntr=0.3,0.1

Type RM Length L Ch R = 1 ,61326   ,103,103,103
BEGIN DESCRIPTION:
This cross section corresponds to cross section 61344 of the non-georeferenced CDC model which was the source of this model.
END DESCRIPTION:
XS GIS Cut Line= 6
 2419867.90292956974899.05687319     2419673.129     6974425.111
     2419623.547     6974060.004      2419564.95     6972166.855
     2419411.695     6971788.225     2419202.543     6971467.202
#Sta/Elev= 30
    2000   468.7    2270   452.5    3054   442.9    3640   442.1    3640     460
    3850     460    3850   445.1    3970     447    4005   443.3    4070     415
    4140     415    4158   426.3    4186   435.6    4300   448.4    4314   455.9
    4356     460    4768   460.1    4813   466.9    4836   460.1    4865   460.1
    4870     464    4878   460.1    4977   460.1    4984     464    4991   460.1
    5012     464    5018   460.1    5176   460.1    5195   470.1    5571   470.9
#Mann= 3 ,0,0
    2000     .07       0    3970    .055       0    4300    .085       0
Bank Sta=3970,4300
XS Rating Curve= 0 ,0
Exp/Cntr=0.3,0.1

Type RM Length L Ch R = 1 ,61222   ,1,1,1
BEGIN DESCRIPTION:
This cross section corresponds to cross section 61239 of the non-georeferenced CDC model which was the source of this model.
END DESCRIPTION:
XS GIS Cut Line= 6
     2420457.214     6975777.636     2419875.645     6974731.711
     2419776.479     6974429.709       2419668.3     6972171.453
     2419515.046     6971792.824     2419305.893     6971471.801
#Sta/Elev= 30
    1000   482.8    1104   472.5    1202   472.3    1224     465    1552   457.8
    1609   451.3    1778   450.5    1861   464.2    1963   470.5    2162   455.9
    2382   450.5    3520   441.8    3520     452    3960     460    3960   446.3
    3970     447    4005   443.3    4070     415    4140     415    4186   435.6
    4300   448.4    4314   455.9    4356     460    4768   460.1    4813   466.9
    4836   460.1    4870     464    5176   460.1    5195   470.1    5571   470.9
#Mann= 3 ,0,0
    1000     .06       0    3970     .05       0    4300     .06       0
Bank Sta=3970,4300
XS Rating Curve= 0 ,0
Exp/Cntr=0.5,0.3

Type RM Length L Ch R = 1 ,61221   ,80,80,80
BEGIN DESCRIPTION:
This cross section corresponds to cross section 61238 of the non-georeferenced CDC model which was the source of this model.
END DESCRIPTION:
XS GIS Cut Line= 6
     2420314.954     6975521.336     2419876.525     6974731.399
     2419777.477     6974429.754     2419669.298     6972171.498
     2419516.044     6971792.868     2419231.253     6971355.756
#Sta/Elev= 30
    1000   474.9    1361   459.2    1459   456.8    1928   454.5    2100   451.4
    2274   446.3    2608   443.8    2782   445.5    3276     455    3377   456.1
    3700   467.5    3700     463    3768     428    3784     427    3796     417
    3800     415    3875     417    3880     425    3883     425    3887     431
    3907     435    3964     463    3964   468.7    4163   465.3    4337   460.2
    4514   458.3    4746   458.9    4867   460.4    5265   467.5    5416   471.7
#Mann= 3 ,0,0
    1000     .06       0    3700     .05       0    3964     .06       0
Bank Sta=3700,3964
XS Rating Curve= 0 ,0
Exp/Cntr=0.3,0.1

Type RM Length L Ch R = 3 ,61180   ,,,
BEGIN DESCRIPTION:
Roy Orr Boulevard/N.W. 19th Street
END DESCRIPTION:
Node Name=NW 19th Street
Bridge Culvert--1,0,-1,-1, 0
Deck Dist Width WeirC Skew NumUp NumDn MinLoCord MaxHiCord MaxSubmerge Is_Ogee
1,78,2.6,0, 57, 57, , , 0.95, 0, ,,,
    2100    2142    2186    2231    2274    2328    2384    2437    2524    2608
    2661    2749    2782    2852    2931    3004    3060    3143    3173    3219
    3276    3354    3377    3414    3503    3576    3633    3698    3700    3700
    3750    3800    3875    3964    3964    3967    4065    4163    4237    4276
    4337    4426    4514    4578    4645    4690    4746    4800    4867    4935
    5004    5080    5158    5229    5265    5320    5416
   451.4   450.1   448.2   447.9   446.3   446.2     446   445.1   444.4   443.8
   444.5   445.2   445.5   447.3   448.6   449.5   450.3   452.2     453   453.7
     455   455.8   456.1     457   460.6   463.5   465.6   467.5   467.5     469
   470.1   470.7   470.8   470.2   468.7   468.7   467.5   465.3   463.3   461.6
   460.2   459.4   458.3   458.5   458.8     459   458.9   459.8   460.4   461.9
   463.1   464.5   465.8     467   467.5   469.6   471.7
   451.4   450.1   448.2   447.9   446.3   446.2     446   445.1   444.4   443.8
   444.5   445.2   445.5   447.3   448.6   449.5   450.3   452.2     453   453.7
     455   455.8   456.1     457   460.6   463.5   465.6   467.5   467.5     463
     463     463     463     463   468.7   468.7   467.5   465.3   463.3   461.6
   460.2   459.4   458.3   458.5   458.8     459   458.9   459.8   460.4   461.9
   463.1   464.5   465.8     467   467.5   469.6   471.7
    2100    2142    2186    2231    2274    2328    2384    2437    2524    2608
    2661    2749    2782    2852    2931    3004    3060    3143    3173    3219
    3276    3354    3377    3414    3503    3576    3633    3698    3700    3700
    3750    3800    3875    3964    3964    3967    4065    4163    4237    4276
    4337    4426    4514    4578    4645    4690    4746    4800    4867    4935
    5004    5080    5158    5229    5265    5320    5416
   451.4   450.1   448.2   447.9   446.3   446.2     446   445.1   444.4   443.8
   444.5   445.2   445.5   447.3   448.6   449.5   450.3   452.2     453   453.7
     455   455.8   456.1     457   460.6   463.5   465.6   467.5   467.5     469
   470.1   470.7   470.8   470.2   468.7   468.7   467.5   465.3   463.3   461.6
   460.2   459.4   458.3   458.5   458.8     459   458.9   459.8   460.4   461.9
   463.1   464.5   465.8     467   467.5   469.6   471.7
   451.4   450.1   448.2   447.9   446.3   446.2     446   445.1   444.4   443.8
   444.5   445.2   445.5   447.3   448.6   449.5   450.3   452.2     453   453.7
     455   455.8   456.1     457   460.6   463.5   465.6   467.5   467.5     463
     463     463     463     463   468.7   468.7   467.5   465.3   463.3   461.6
   460.2   459.4   458.3   458.5   458.8     459   458.9   459.8   460.4   461.9
   463.1   464.5   465.8     467   467.5   469.6   471.7
Pier Skew, UpSta & Num, DnSta & Num=  ,3782.5, 2 ,3782.5, 2 , 0 , 0 , 0 ,,
       3       3
     400     464
       3       3
     400     464
Pier Skew, UpSta & Num, DnSta & Num=  ,3881.5, 2 ,3881.5, 2 , 0 , 0 , 0 ,,
       3       3
     400     464
       3       3
     400     464
BR Coef= 1 , 0 , 0 ,1.05, 0 ,,,0.8,-1,0.5,1,
WSPro=,,,, 1 ,,,, 0 ,,,, 0 ,,,,-1 ,-1 ,-1 , 0 , 0 , 0 , 0 , 0
BC Design=,, 0 ,, 0 ,,,,,,
BC HTab HWMax=471.7
BC Use User HTab Curves=0
BC User HTab FreeFlow(D)= 0

Type RM Length L Ch R = 1 ,61141   ,1,1,1
BEGIN DESCRIPTION:
This cross section corresponds to cross section 61158 of the non-georeferenced CDC model which was the source of this model.
END DESCRIPTION:
XS GIS Cut Line= 6
     2420411.952     6975562.168     2419847.886     6974348.333
     2419793.796     6972446.168     2419739.706     6972090.077
     2419573.081     6971657.752     2419379.336     6971369.819
#Sta/Elev= 30
    1000   474.9    1361   459.2    1459   456.8    1928   454.5    2100   451.4
    2274   446.3    2608   443.8    2782   445.5    3276     455    3377   456.1
    3700   467.5    3700     463    3768     428    3784     427    3796     417
    3800     415    3875     417    3880     425    3883     425    3887     431
    3907     435    3964     463    3964   468.7    4163   465.3    4337   460.2
    4514   458.3    4746   458.9    4867   460.4    5265   467.5    5416   471.7
#Mann= 3 ,0,0
    1000     .06       0    3700     .05       0    3964     .06       0
Bank Sta=3700,3964
XS Rating Curve= 0 ,0
Exp/Cntr=0.3,0.1

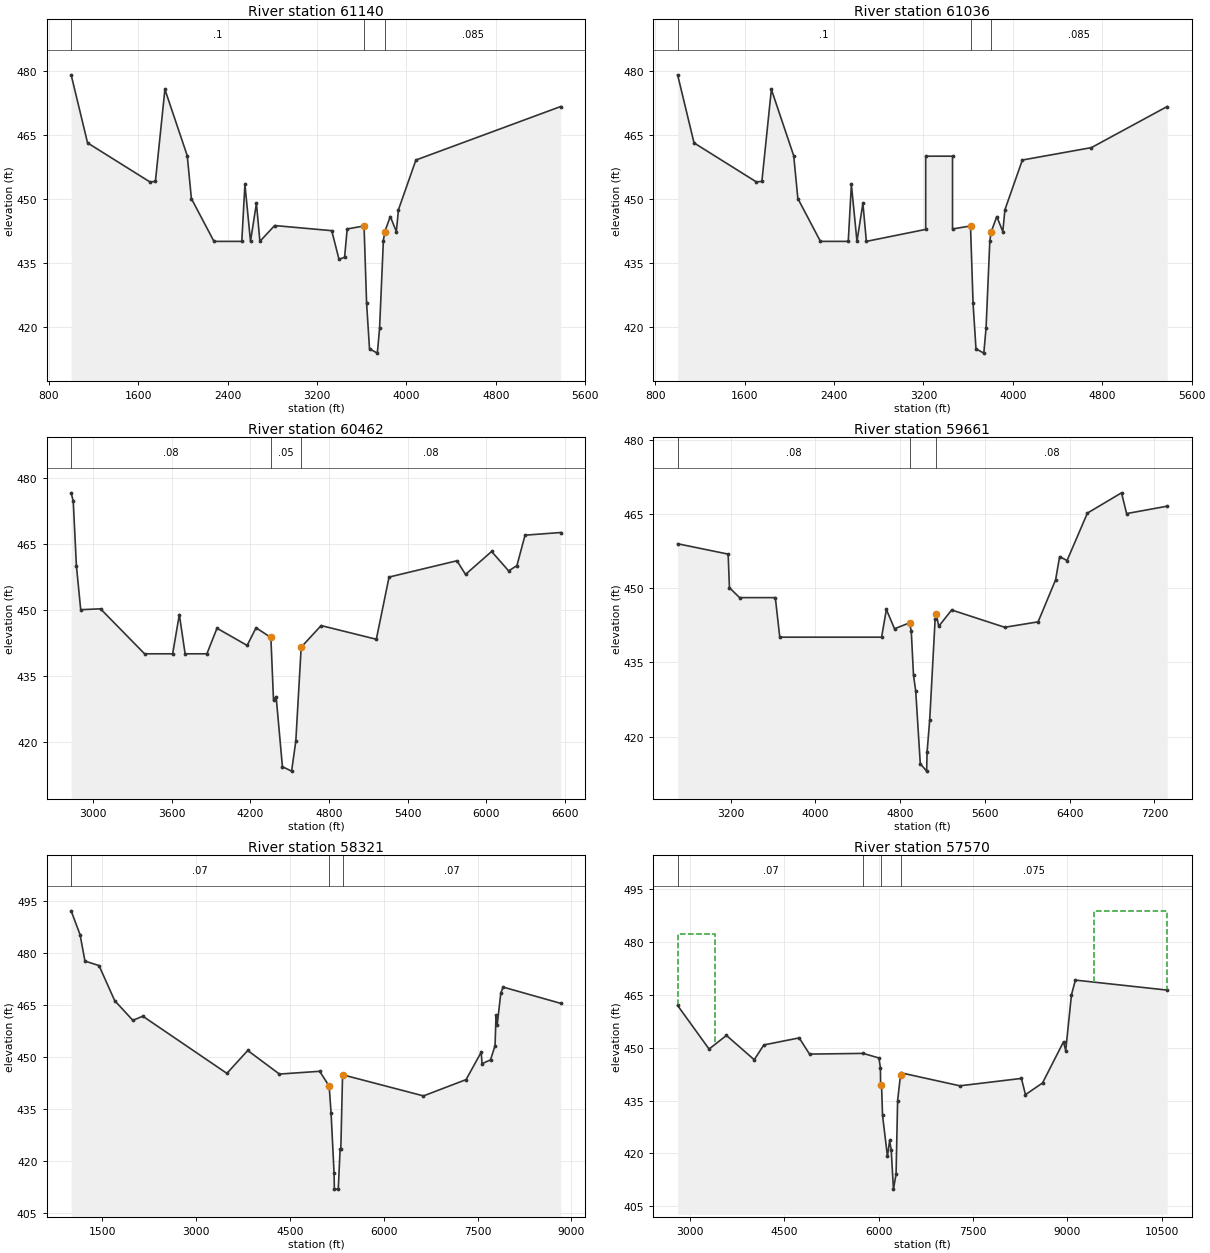
Type RM Length L Ch R = 1 ,61140   ,104,104,104
BEGIN DESCRIPTION:
This cross section corresponds to cross section 61157 of the non-georeferenced CDC model which was the source of this model.
END DESCRIPTION:
XS GIS Cut Line= 6
     2420356.356     6975448.961     2419848.884     6974348.377
     2419794.794     6972446.213     2419740.704     6972090.121
     2419573.927     6971657.4022419329.73591478  6971293.508873
#Sta/Elev= 30
    1000     479    1147   463.1    1704     454    1754   454.1    1839   475.6
    2039   460.1    2076   450.1    2278   440.1    2527   440.1    2555   453.4
    2605   440.1    2658     449    2689   440.1    2821   443.8    3332   442.6
    3397   435.9    3447   436.4    3470     443    3621   443.7    3644   425.6
    3670     415    3740     414    3760   419.8    3794   440.3    3807   442.4
    3856   445.9    3910   442.4    3929   447.5    4085   459.1    5381   471.6
#Mann= 3 ,0,0
    1000      .1       0    3621     .05       0    3807    .085       0
#XS Ineff= 2 , 0
       0    3621   443.7    3807       0   442.4
Permanent Ineff=
       F       F
Bank Sta=3621,3807
XS Rating Curve= 0 ,0
Exp/Cntr=0.3,0.1

Type RM Length L Ch R = 1 ,61036   ,851,574,550
BEGIN DESCRIPTION:
This cross section corresponds to cross section 61054 of the non-georeferenced CDC model which was the source of this model.
END DESCRIPTION:
XS GIS Cut Line= 6
     2420460.066     6975453.575     2419952.594     6974352.991
     2419898.504     6972450.827     2419844.414     6972094.735
     2419677.637     6971662.016     2419433.446     6971298.123
#Sta/Elev= 30
    1000     479    1147   463.1    1704     454    1754   454.1    1839   475.6
    2039   460.1    2076   450.1    2278   440.1    2527   440.1    2555   453.4
    2605   440.1    2658     449    2689   440.1    3220   442.9    3220     460
    3460     460    3460     443    3621   443.7    3644   425.6    3670     415
    3740     414    3760   419.8    3794   440.3    3807   442.4    3856   445.9
    3910   442.4    3929   447.5    4085   459.1    4703     462    5381   471.6
#Mann= 3 ,0,0
    1000      .1       0    3621     .05       0    3807    .085       0
Bank Sta=3621,3807
XS Rating Curve= 0 ,0
Exp/Cntr=0.3,0.1

Type RM Length L Ch R = 1 ,60462   ,951,801,550
BEGIN DESCRIPTION:
This cross section corresponds to cross section 60480 of the non-georeferenced CDC model which was the source of this model.
END DESCRIPTION:
XS GIS Cut Line= 6
  2421007.528312 6974447.4330934  2420749.167067  6973832.761081
 2420488.2978381 6973212.1491332 2420450.6020473 6972232.0470908
  2420200.416196 6971521.6413594 2419981.4940617 6970900.0379438
#Sta/Elev= 30
    2834   476.6    2850   474.7    2874   460.1    2907   450.1    3058   450.3
    3394   440.1    3608   440.1    3659     449    3703   440.1    3869   440.1
    3946   445.9    4176     442    4244     446    4357   443.8    4377   429.6
    4397   430.4    4445   414.5    4515   413.5    4547   420.3    4588   441.6
    4740   446.5    5161   443.4    5258   457.5    5776   461.2    5841   458.1
    6040   463.3    6170   458.9    6233   460.1    6295     467    6567   467.6
#Mann= 3 ,0,0
    2834     .08       0    4357     .05       0    4588     .08       0
Bank Sta=4357,4588
XS Rating Curve= 0 ,0
Exp/Cntr=0.3,0.1

Type RM Length L Ch R = 1 ,59661   ,948,1341,1597
BEGIN DESCRIPTION:
This cross section corresponds to cross section 56980 of the non-georeferenced CDC model which was the source of this model.
END DESCRIPTION:
XS GIS Cut Line= 6
  2422152.102599 6974861.3943193  2421770.165025  6973888.859394
 2421411.8550461 6972976.5478984 2421110.2860954 6972543.0408914
 2420767.5013479 6971668.2998587 2420356.1340604 6970618.6159345
#Sta/Elev= 30
    2700     459    3177   456.9    3189   450.1    3285   448.1    3622   448.1
    3664   440.1    4625   440.1    4670   445.7    4747   441.8    4889     443
    4905   441.3    4926   432.4    4947   429.2    4990   414.5    5050     413
    5054   416.8    5079   423.4    5130   443.7    5142   444.7    5164   442.3
    5286   445.6    5787   442.1    6102   443.2    6267   451.7    6305   456.4
    6375   455.6    6567   465.2    6889   469.3    6937   465.1    7320   466.6
#Mann= 3 ,0,0
    2700     .08       0    4889     .05       0    5142     .08       0
Bank Sta=4889,5142
XS Rating Curve= 0 ,0
Exp/Cntr=0.3,0.1

Type RM Length L Ch R = 1 ,58321   ,714,751,739
BEGIN DESCRIPTION:
This cross section corresponds to cross section 58337 of the non-georeferenced CDC model which was the source of this model.
END DESCRIPTION:
XS GIS Cut Line= 6
  2423105.205005 6976239.6250337 2422745.9967347 6974206.6970129
 2422335.4129103 6971883.3568433 2421702.9167999 6970353.5770945
 2421368.0408292 6969543.6991211 2421033.8755708 6968735.5843649
#Sta/Elev= 30
    1000   492.3    1143   485.4    1221   477.8    1446   476.5    1696   466.4
    1987   460.7    2146   461.9    3491   445.4    3824     452    4331   445.2
    4975     446    5127   441.7    5157     434    5205   416.6    5210     412
    5272     412    5302   423.6    5313   423.6    5341     445    6635   438.9
    7316   443.6    7558   451.5    7572   448.2    7707   449.3    7780   453.4
    7795   462.2    7814   459.4    7872   468.6    7908   470.3    8830   465.6
#Mann= 3 ,0,0
    1000     .07       0    5127     .05       0    5341     .07       0
Bank Sta=5127,5341
XS Rating Curve= 0 ,0
Exp/Cntr=0.3,0.1

Type RM Length L Ch R = 1 ,57570   ,354,283,357
BEGIN DESCRIPTION:
This cross section corresponds to cross section 57586 of the non-georeferenced CDC model which was the source of this model.
Upstream bounding cross-section.
Section data is generated through the TXdot's topo file.
END DESCRIPTION:
XS GIS Cut Line= 6
  2423656.005741 6975259.9862449 2423174.4397755  6972091.859051
 2423098.6620399 6971952.4134637 2423022.8846324 6971812.9675484
 2422474.5373039 6971531.5150273 2420915.9629932 6968239.1420189
#Sta/Elev= 30
    2807     462    3307  449.63    3583   453.5 4024.62   446.6 4177.12   450.8
 4739.32   452.8 4903.42   448.2 5756.12   448.4 6006.02   447.1 6029.82   444.3
 6032.72  439.46 6047.22   439.8 6063.82   430.8 6141.52   419.2 6176.42   423.7
 6201.42     421 6237.12  409.88 6278.62   414.1 6303.32     435 6350.22   442.4
6353.921   442.9 7292.62   439.2 8270.82   441.3 8334.92   436.7 8605.92     440
 8939.92   451.7 8974.52   449.2 9065.82     465 9128.12   469.210587.26  466.36
#Mann= 4 ,-1,0
    2807     .07       0 5756.12    .075       0 6032.72     .05       0
6353.921    .075       0
#XS Ineff= 2 , 0
       0 3395.12  482.16 9422.26       0  488.86
Permanent Ineff=
       F       F
Bank Sta=6032.72,6350.22
XS Rating Curve= 0 ,0
Exp/Cntr=0.5,0.3

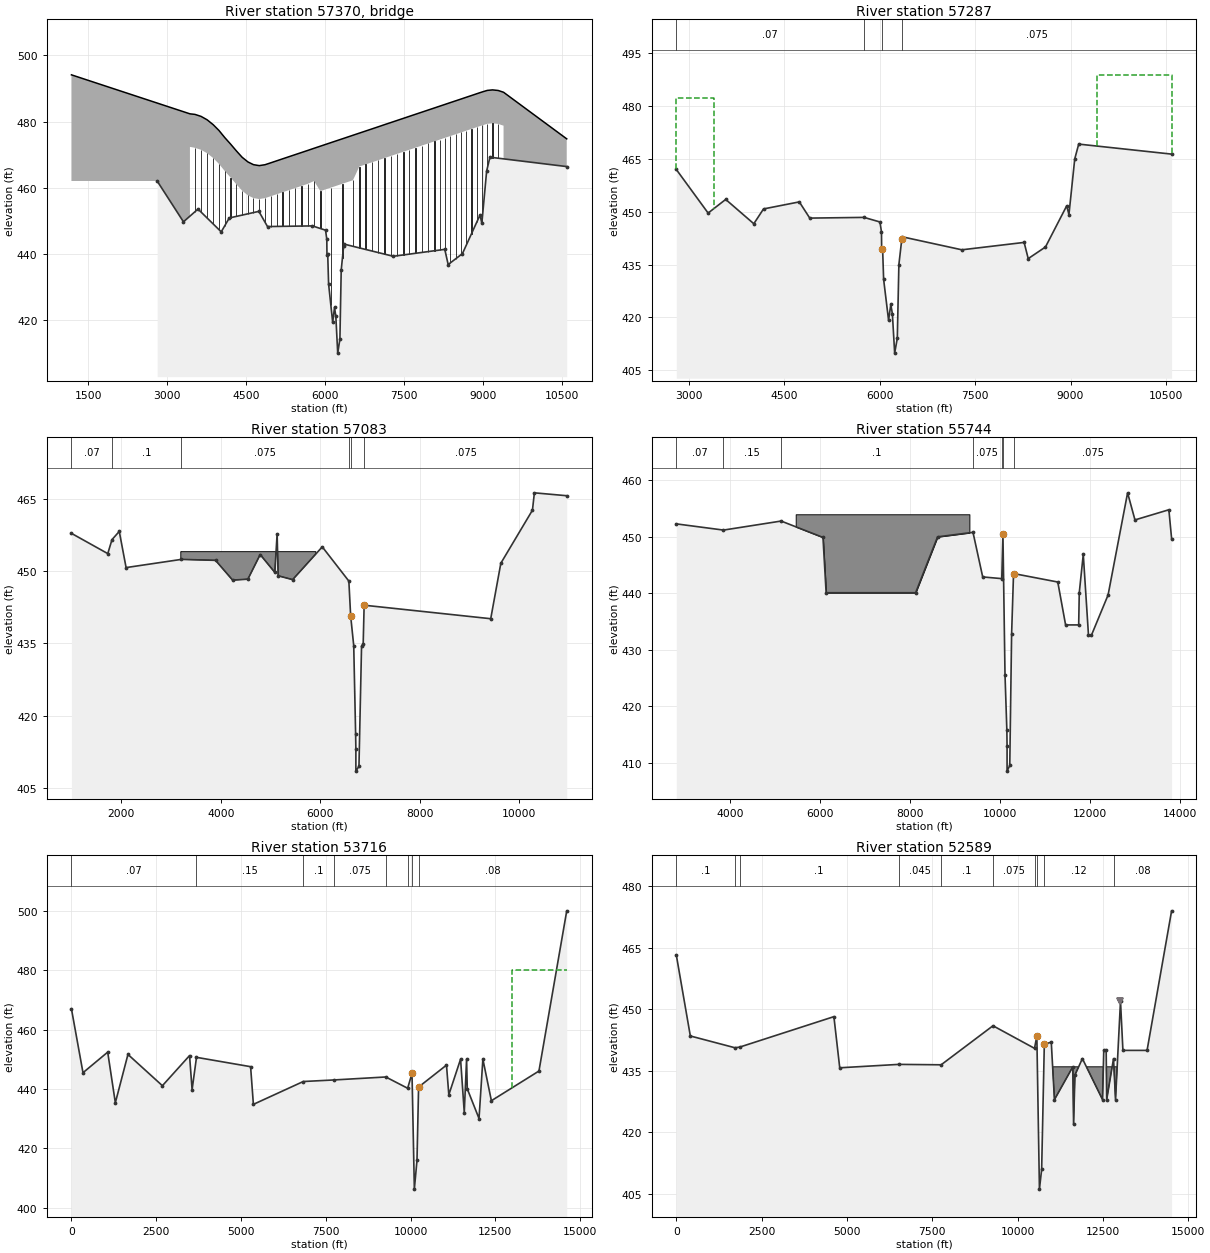
Type RM Length L Ch R = 3 ,57370   ,,,
BEGIN DESCRIPTION:
SH 161
---------------------
CDC GP011404-1 SH 161
---------------------
END DESCRIPTION:
Node Name=SH 161
Bridge Culvert--1,0,-1,-1, 0
Deck Dist Width WeirC Skew NumUp NumDn MinLoCord MaxHiCord MaxSubmerge Is_Ogee
47,166,2.6,0, 56, 56, , , 0.95, 0, 3,3,,
 1179.12 3430.12 3430.12 3525.12 3641.12 3757.12 3872.12 3982.12 4092.12 4202.12
 4312.12 4422.12 4532.12 4637.12 4747.12 4857.12 4967.12 5077.12 5187.12 5307.12
 5427.12 5547.12 5667.12 5787.12 5907.12 6107.12 6327.12 6527.12 6647.12 6767.12
 6887.12 7007.12 7127.12 7247.12 7367.12 7487.12 7595.26 7715.26 7835.26 7955.26
 8075.26 8176.26 8277.26 8377.26 8477.26 8577.26 8677.26 8777.26 8877.26 8977.26
 9077.26 9177.26 9285.26 9387.26 9387.2610587.26
  494.14  482.33  482.33  482.16  481.56  480.52  479.04  477.28  475.13  473.17
  471.11  469.17  467.76  466.94  466.65  466.93  467.51   468.1  468.69  469.33
  469.97  470.61  471.25   471.9  472.54  473.61  474.78  475.85  476.49  477.13
  477.77  478.41  479.06   479.7  480.34  480.98  481.56   482.2  482.84  483.48
  484.12  484.66   485.2  485.74  486.27   486.8  487.34  487.87  488.41  488.94
  489.42  489.58   489.4  488.86  488.86  474.75
       0       0  472.33  472.04  471.44   470.4  468.95  467.16  465.01  463.05
  460.99  459.05  457.64  456.82  456.53  456.81  457.39  457.98  458.57  459.21
  459.85  460.49  461.13  461.98  458.92  459.99  461.16  462.23  466.37  467.01
  467.65  468.29  468.94  469.58  470.22  470.86  471.44  472.08  472.72  473.36
     474  474.54  475.08  475.62  476.15  476.68  477.22  477.75  478.29  478.82
   479.3  479.46  479.28  478.74       0       0
 1179.12 3430.12 3430.12 3525.12 3641.12 3757.12 3872.12 3982.12 4092.12 4202.12
 4312.12 4422.12 4532.12 4637.12 4747.12 4857.12 4967.12 5077.12 5187.12 5307.12
 5427.12 5547.12 5667.12 5787.12 5907.12 6107.12 6327.12 6527.12 6647.12 6767.12
 6887.12 7007.12 7127.12 7247.12 7367.12 7487.12 7595.26 7715.26 7835.26 7955.26
 8075.26 8176.26 8277.26 8377.26 8477.26 8577.26 8677.26 8777.26 8877.26 8977.26
 9077.26 9177.26 9285.26 9387.26 9387.2610587.26
  494.14  482.33  482.33  482.16  481.56  480.52  479.04  477.28  475.13  473.17
  471.11  469.17  467.76  466.94  466.65  466.93  467.51   468.1  468.69  469.33
  469.97  470.61  471.25   471.9  472.54  473.61  474.78  475.85  476.49  477.13
  477.77  478.41  479.06   479.7  480.34  480.98  481.56   482.2  482.84  483.48
  484.12  484.66   485.2  485.74  486.27   486.8  487.34  487.87  488.41  488.94
  489.42  489.58   489.4  488.86  488.86  474.75
       0       0  472.33  472.04  471.44   470.4  468.95  467.16  465.01  463.05
  460.99  459.05  457.64  456.82  456.53  456.81  457.39  457.98  458.57  459.21
  459.85  460.49  461.13  461.98  458.92  459.99  461.16  462.23  466.37  467.01
  467.65  468.29  468.94  469.58  470.22  470.86  471.44  472.08  472.72  473.36
     474  474.54  475.08  475.62  476.15  476.68  477.22  477.75  478.29  478.82
   479.3  479.46  479.28  478.74       0       0
Pier Skew, UpSta & Num, DnSta & Num=  ,3525.12, 2 ,3525.12, 2 , 0 , 0 , 0 ,,
       4       4
     440  482.33
       4       4
     440  482.33
Pier Skew, UpSta & Num, DnSta & Num=  ,3641.12, 2 ,3641.12, 2 , 0 , 0 , 0 ,,
       4       4
     440  482.33
       4       4
     440  482.33
Pier Skew, UpSta & Num, DnSta & Num=  ,3757.12, 2 ,3757.12, 2 , 0 , 0 , 0 ,,
       4       4
     440  482.33
       4       4
     440  482.33
Pier Skew, UpSta & Num, DnSta & Num=  ,3872.12, 2 ,3872.12, 2 , 0 , 0 , 0 ,,
       4       4
     440  482.33
       4       4
     440  482.33
Pier Skew, UpSta & Num, DnSta & Num=  ,3982.12, 2 ,3982.12, 2 , 0 , 0 , 0 ,,
       4       4
     440  482.33
       4       4
     440  482.33
Pier Skew, UpSta & Num, DnSta & Num=  ,4092.12, 2 ,4092.12, 2 , 0 , 0 , 0 ,,
       4       4
     440  482.33
       4       4
     440  482.33
Pier Skew, UpSta & Num, DnSta & Num=  ,4202.12, 2 ,4202.12, 2 , 0 , 0 , 0 ,,
       4       4
     440  482.33
       4       4
     440  482.33
Pier Skew, UpSta & Num, DnSta & Num=  ,4312.12, 2 ,4312.12, 2 , 0 , 0 , 0 ,,
       4       4
     440  482.33
       4       4
     440  482.33
Pier Skew, UpSta & Num, DnSta & Num=  ,4422.12, 2 ,4422.12, 2 , 0 , 0 , 0 ,,
       4       4
     440  482.33
       4       4
     440  482.33
Pier Skew, UpSta & Num, DnSta & Num=  ,4532.12, 2 ,4532.12, 2 , 0 , 0 , 0 ,,
       4       4
     440  482.33
       4       4
     440  482.33
Pier Skew, UpSta & Num, DnSta & Num=  ,4632.12, 2 ,4632.12, 2 , 0 , 0 , 0 ,,
       4       4
     440  482.33
       4       4
     440  482.33
Pier Skew, UpSta & Num, DnSta & Num=  ,4747.12, 2 ,4747.12, 2 , 0 , 0 , 0 ,,
       4       4
     440  479.46
       4       4
     440  479.46
Pier Skew, UpSta & Num, DnSta & Num=  ,4857.12, 2 ,4857.12, 2 , 0 , 0 , 0 ,,
       4       4
     440  482.33
       4       4
     440  482.33
Pier Skew, UpSta & Num, DnSta & Num=  ,4967.12, 2 ,4967.12, 2 , 0 , 0 , 0 ,,
       4       4
     440  482.33
       4       4
     440  482.33
Pier Skew, UpSta & Num, DnSta & Num=  ,5077.12, 2 ,5077.12, 2 , 0 , 0 , 0 ,,
       4       4
     440  482.33
       4       4
     440  482.33
Pier Skew, UpSta & Num, DnSta & Num=  ,5187.12, 2 ,5187.12, 2 , 0 , 0 , 0 ,,
       4       4
     440  482.33
       4       4
     440  482.33
Pier Skew, UpSta & Num, DnSta & Num=  ,5307.12, 2 ,5307.12, 2 , 0 , 0 , 0 ,,
       4       4
     440  479.46
       4       4
     440  479.46
Pier Skew, UpSta & Num, DnSta & Num=  ,5427.12, 2 ,5427.12, 2 , 0 , 0 , 0 ,,
       8       8
     440  482.33
       8       8
     440  482.33
Pier Skew, UpSta & Num, DnSta & Num=  ,5547.12, 2 ,5547.12, 2 , 0 , 0 , 0 ,,
       8       8
     440  482.33
       8       8
     440  482.33
Pier Skew, UpSta & Num, DnSta & Num=  ,5667.12, 2 ,5667.12, 2 , 0 , 0 , 0 ,,
       8       8
     440  482.33
       8       8
     440  482.33
Pier Skew, UpSta & Num, DnSta & Num=  ,5787.12, 2 ,5787.12, 2 , 0 , 0 , 0 ,,
       8       8
     440  482.33
       8       8
     440  482.33
Pier Skew, UpSta & Num, DnSta & Num=  ,5907.12, 2 ,5907.12, 2 , 0 , 0 , 0 ,,
       8       8
     440  482.33
       8       8
     440  482.33
Pier Skew, UpSta & Num, DnSta & Num=  ,6107.12, 2 ,6107.12, 2 , 0 , 0 , 0 ,,
       8       8
     440  482.33
       8       8
     440  482.33
Pier Skew, UpSta & Num, DnSta & Num=  ,6327.12, 2 ,6327.12, 2 , 0 , 0 , 0 ,,
       8       8
     440  482.33
       8       8
     440  482.33
Pier Skew, UpSta & Num, DnSta & Num=  ,6527.12, 2 ,6527.12, 2 , 0 , 0 , 0 ,,
       8       8
     440  482.33
       8       8
     440  482.33
Pier Skew, UpSta & Num, DnSta & Num=  ,6647.12, 2 ,6647.12, 2 , 0 , 0 , 0 ,,
       8       8
     440  482.33
       8       8
     440  482.33
Pier Skew, UpSta & Num, DnSta & Num=  ,6767.12, 2 ,6767.12, 2 , 0 , 0 , 0 ,,
       8       8
     440  482.33
       8       8
     440  482.33
Pier Skew, UpSta & Num, DnSta & Num=  ,6887.12, 2 ,6887.12, 2 , 0 , 0 , 0 ,,
       8       8
     440  482.33
       8       8
     440  482.33
Pier Skew, UpSta & Num, DnSta & Num=  ,7007.12, 2 ,7007.12, 2 , 0 , 0 , 0 ,,
       4       4
     440  482.33
       4       4
     440  482.33
Pier Skew, UpSta & Num, DnSta & Num=  ,7127.12, 2 ,7127.12, 2 , 0 , 0 , 0 ,,
       4       4
     440  482.33
       4       4
     440  482.33
Pier Skew, UpSta & Num, DnSta & Num=  ,7247.12, 2 ,7247.12, 2 , 0 , 0 , 0 ,,
       4       4
     440  482.33
       4       4
     440  482.33
Pier Skew, UpSta & Num, DnSta & Num=  ,7367.12, 2 ,7367.12, 2 , 0 , 0 , 0 ,,
       4       4
     440  482.33
       4       4
     440  482.33
Pier Skew, UpSta & Num, DnSta & Num=  ,7487.12, 2 ,7487.12, 2 , 0 , 0 , 0 ,,
       4       4
     440  482.33
       4       4
     440  482.33
Pier Skew, UpSta & Num, DnSta & Num=  ,7595.26, 2 ,7595.26, 2 , 0 , 0 , 0 ,,
       4       4
     440  482.33
       4       4
     440  482.33
Pier Skew, UpSta & Num, DnSta & Num=  ,7715.26, 2 ,7715.26, 2 , 0 , 0 , 0 ,,
       4       4
     440  482.33
       4       4
     440  482.33
Pier Skew, UpSta & Num, DnSta & Num=  ,7835.26, 2 ,7835.26, 2 , 0 , 0 , 0 ,,
       4       4
     440  482.33
       4       4
     440  482.33
Pier Skew, UpSta & Num, DnSta & Num=  ,7955.26, 2 ,7955.26, 2 , 0 , 0 , 0 ,,
       4       4
     440  482.33
       4       4
     440  482.33
Pier Skew, UpSta & Num, DnSta & Num=  ,8075.26, 2 ,8075.26, 2 , 0 , 0 , 0 ,,
       4       4
     440  482.33
       4       4
     440  482.33
Pier Skew, UpSta & Num, DnSta & Num=  ,8176.26, 2 ,8176.26, 2 , 0 , 0 , 0 ,,
       4       4
     440  482.33
       4       4
     440  482.33
Pier Skew, UpSta & Num, DnSta & Num=  ,8277.26, 2 ,8277.26, 2 , 0 , 0 , 0 ,,
       4       4
     440  482.33
       4       4
     440  482.33
Pier Skew, UpSta & Num, DnSta & Num=  ,8377.26, 2 ,8377.26, 2 , 0 , 0 , 0 ,,
       4       4
     440  482.33
       4       4
     440  482.33
Pier Skew, UpSta & Num, DnSta & Num=  ,8477.26, 2 ,8477.26, 2 , 0 , 0 , 0 ,,
       4       4
     440  482.33
       4       4
     440  482.33
Pier Skew, UpSta & Num, DnSta & Num=  ,8577.26, 2 ,8577.26, 2 , 0 , 0 , 0 ,,
       4       4
     440  482.33
       4       4
     440  482.33
Pier Skew, UpSta & Num, DnSta & Num=  ,8677.26, 2 ,8677.26, 2 , 0 , 0 , 0 ,,
       4       4
     440  482.33
       4       4
     440  482.33
Pier Skew, UpSta & Num, DnSta & Num=  ,8777.26, 2 ,8777.26, 2 , 0 , 0 , 0 ,,
       4       4
     440  482.33
       4       4
     440  482.33
Pier Skew, UpSta & Num, DnSta & Num=  ,8877.26, 2 ,8877.26, 2 , 0 , 0 , 0 ,,
       4       4
     440  482.33
       4       4
     440  482.33
Pier Skew, UpSta & Num, DnSta & Num=  ,8977.26, 2 ,8977.26, 2 , 0 , 0 , 0 ,,
       4       4
     440  482.33
       4       4
     440  482.33
Pier Skew, UpSta & Num, DnSta & Num=  ,9077.26, 2 ,9077.26, 2 , 0 , 0 , 0 ,,
       4       4
     440  482.33
       4       4
     440  482.33
Pier Skew, UpSta & Num, DnSta & Num=  ,9177.26, 2 ,9177.26, 2 , 0 , 0 , 0 ,,
       4       4
     440  482.33
       4       4
     440  482.33
Pier Skew, UpSta & Num, DnSta & Num=  ,9282.26, 2 ,9282.26, 2 , 0 , 0 , 0 ,,
       4       4
     440  482.33
       4       4
     440  482.33
Abutment Skew #Up #Dn= , 2 , 2
 3430.12    3465
  482.33     440
 3430.12    3465
  482.33     440
Abutment Skew #Up #Dn= , 2 , 2
    9335 9387.26
     440  488.86
    9335 9387.26
     440  488.86
BR Coef=-1 , 1 , 1 ,0.9, 0 ,,,0.8,-1,1.33,0,
WSPro=,,,, 1 ,,,, 0 ,,,, 0 ,,,,-1 ,-1 ,-1 , 0 , 0 , 0 , 0 , 0
BC Design=,, 0 ,, 0 ,,,,,,
BC Use User HTab Curves=0
BC User HTab FreeFlow(D)= 0

Type RM Length L Ch R = 1 ,57287   ,926,204,183
BEGIN DESCRIPTION:
This cross section corresponds to cross section 57303 of the non-georeferenced CDC model which was the source of this model.
Downstream bounding cross-section.
Copied from cross-section 57586
END DESCRIPTION:
XS GIS Cut Line= 6
  2424208.296303 6974983.5566797 2423436.3326244 6971871.1475502
 2423312.4001295 6971772.0109374 2423188.4676346 6971672.8743247
 2422592.5928421 6971377.8693372 2420957.5370571  6968184.162142
#Sta/Elev= 30
    2807     462    3307  449.63    3583   453.5 4024.62   446.6 4177.12   450.8
 4739.32   452.8 4903.42   448.2 5756.12   448.4 6006.02   447.1 6029.82   444.3
 6032.72  439.46 6047.22   439.8 6063.82   430.8 6141.52   419.2 6176.42   423.7
 6201.42     421 6237.12  409.88 6278.62   414.1 6303.32     435 6350.22   442.4
6353.921   442.9 7292.62   439.2 8270.82   441.3 8334.92   436.7 8605.92     440
 8939.92   451.7 8974.52   449.2 9065.82     465 9128.12   469.210587.26  466.36
#Mann= 4 ,-1,0
    2807     .07       0 5756.12    .075       0 6032.72     .05       0
6353.921    .075       0
#XS Ineff= 2 , 0
       0 3395.12  482.16 9422.26       0  488.86
Permanent Ineff=
       F       F
Bank Sta=6032.72,6350.22
XS Rating Curve= 0 ,0
Exp/Cntr=0.5,0.3

Type RM Length L Ch R = 1 ,57083   ,650,1339,650
BEGIN DESCRIPTION:
This cross section corresponds to cross section 57099 of the non-georeferenced CDC model which was the source of this model.
END DESCRIPTION:
XS GIS Cut Line= 6
  2425526.340911 6976594.0629731 2424937.7092148 6974292.6948724
 2424348.9889356 6971991.3389108 2422785.3798581 6971331.7588652
 2421970.7965135   6969712.04885 2421211.8458218 6968203.1268699
#Sta/Elev= 30
    1000   457.8    1730   453.6    1815   456.5    1961   458.2    2098   450.7
    3209   452.4    3895   452.2    4238   448.1    4545   448.3    4792   453.4
    5086   449.7    5132   457.7    5153     449    5444   448.2    6039     455
    6573   447.9    6609   440.7    6671   434.5    6709   416.2    6714     413
    6714   408.5    6776   409.5    6828   434.4    6861   434.9    6880   442.9
    9423   440.1    9626   451.6   10261   462.6   10300   466.2   10950   465.6
#Mann= 6 ,-1,0
    1000     .07       0    1815      .1       0    3209    .075       0
    6573     .12       0    6609     .05       0    6880    .075       0
#Block Obstruct= 1 ,-1
    3197    5910     454
Bank Sta=6609,6880
XS Rating Curve= 0 ,0
Exp/Cntr=0.3,0.1

Type RM Length L Ch R = 1 ,55744   ,2029,2029,2029
BEGIN DESCRIPTION:
This cross section corresponds to cross section 55761 of the non-georeferenced CDC model which was the source of this model.
END DESCRIPTION:
XS GIS Cut Line= 6
  2426708.155149 6976454.2332002 2425510.9052469 6973368.7994105
 2424303.4358771 6970257.6930999 2423045.2090628 6970337.7700395
 2422241.3379672 6968935.5973189 2421497.8404384 6967638.8620515
#Sta/Elev= 30
    2798   452.3    3848   451.2    5130   452.8    6061   449.9    6131   440.1
    8122   440.1    8610     450    9398   450.8    9614   442.9   10038   442.6
   10064   450.5   10110   425.6   10151   415.8   10156     413   10156   408.5
   10216   409.5   10257   432.8   10300   443.5   11284     442   11458   434.4
   11749   434.4   11762   440.1   11851   446.9   11967   432.6   12034   432.6
   12403   439.7   12837   457.8   13001     453   13755   454.8   13816   449.7
#Mann= 7 ,-1,0
    2798     .07       0    3848     .15       0    5130      .1       0
    9398    .075       0   10038     .12       0   10064     .05       0
   10300    .075       0
#Block Obstruct= 1 ,-1
    5454    9318     454
Bank Sta=10064,10300
XS Rating Curve= 0 ,0
Exp/Cntr=0.3,0.1

Type RM Length L Ch R = 1 ,53716   ,1363,1127,1159
BEGIN DESCRIPTION:
This cross section corresponds to cross section 53730 of the non-georeferenced CDC model which was the source of this model.
END DESCRIPTION:
XS GIS Cut Line= 6
   2427973.59198 6978142.1615694 2426568.5632366 6974053.6789462
 2425867.6797958 6972014.6088774 2425166.7041637 6969975.5548846
 2423257.7466955 6967680.7162985 2421348.5149497 6965385.9918853
#Sta/Elev= 30
       0  466.98  340.87  445.44 1069.55  452.37 1294.81  435.31 1666.57   451.6
 2682.26  441.06 3483.04  451.21 3558.14  439.73 3687.83  450.62 5283.42  447.47
 5365.51  434.77 6836.28  442.47 7746.08     443    9270     444    9914   440.2
   10043   445.2   10112   406.2   10190   415.9   10237   440.611059.73     448
11128.44     43811475.07     45011583.97     43211652.12     45011672.87     440
12019.06     43012132.55     45012383.62     43613786.05     44614605.66     500
#Mann= 8 ,-1,0
       0     .07       0 3687.83     .15       0 6836.28      .1       0
 7746.08    .075       0    9270    .075       0    9914     .12       0
   10043     .05       0   10237     .08       0
#XS Ineff= 2 , 0
       0                   13000       0     480
Permanent Ineff=
       F       F
Bank Sta=10043,10237
XS Rating Curve= 0 ,0
Exp/Cntr=0.3,0.1

Type RM Length L Ch R = 1 ,52589   ,1357,1123,1233
BEGIN DESCRIPTION:
This cross section corresponds to cross section 52592 of the non-georeferenced CDC model which was the source of this model.
END DESCRIPTION:
XS GIS Cut Line= 6
  2428529.736807  6977898.615154 2427839.5436342 6975729.3947549
 2427124.8232789 6973483.4241812 2425724.8621681 6969085.1140802
 2424173.9420416 6966966.3991576 2422614.9451596 6964837.0100437
#Sta/Elev= 30
       0  463.26  411.38  443.51 1719.49  440.64 1857.49   440.8 4618.21  448.22
 4789.26  435.76 6517.48  436.59 7760.53  436.49    9280     44610496.67   440.5
   10565   443.5   10641   406.2   10706     411   10784   441.510987.93     442
11080.78     428 11619.3     43611641.57     42211681.36     43411899.36     438
12490.09     42812525.85     44012596.46     44012612.16     42812811.75     438
12870.43     428 13016.3     45213087.25     440 13794.8     440 14513.8     474
#Mann= 10 ,-1,0
       0      .1       0 1719.49    .065       0 1857.49      .1       0
 6517.48    .045       0 7760.53      .1       0    9280    .075       0
10496.67     .11       0   10565     .05       0   10784     .12       0
12811.75     .08       0
Levee=0,,,-1,13016.2,452,,
#Block Obstruct= 1 ,-1
   11000   13200     436
Bank Sta=10565,10784
XS Rating Curve= 0 ,0
Exp/Cntr=0.3,0.1

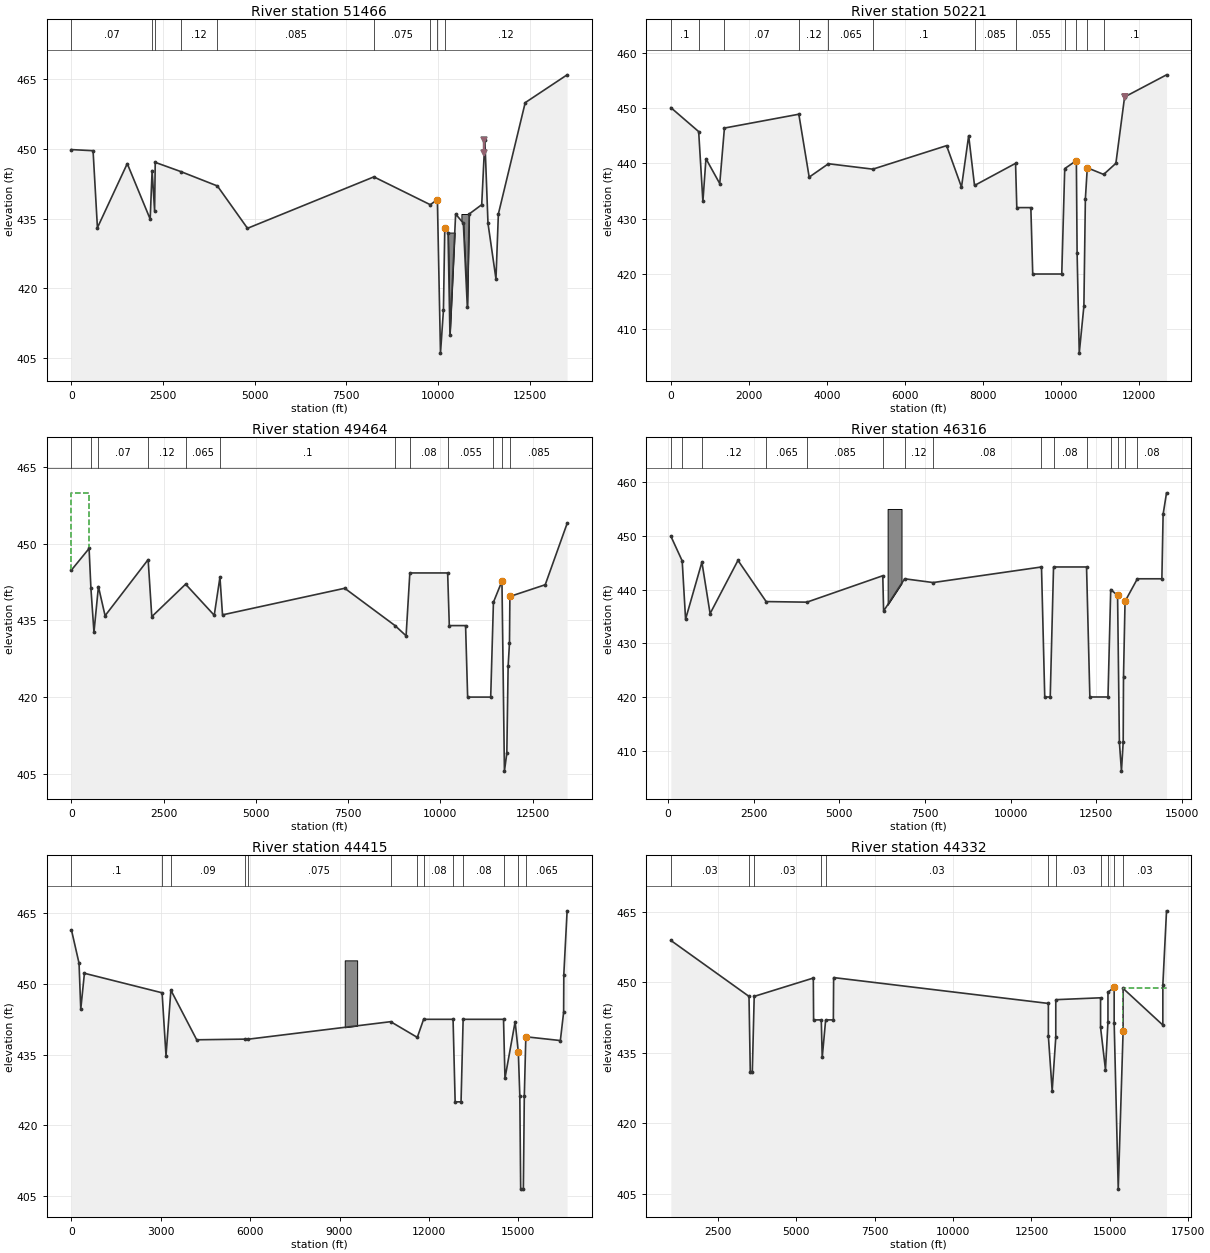
Type RM Length L Ch R = 1 ,51466   ,1048,1245,1120
BEGIN DESCRIPTION:
This cross section corresponds to cross section 51481 of the non-georeferenced CDC model which was the source of this model.
END DESCRIPTION:
XS GIS Cut Line= 6
  2428792.155574 6976717.4905477 2428255.6648493 6974674.6278356
 2427729.3785003 6972670.8956226 2426701.6689415 6968758.8739191
 2425283.6255178 6966522.8610027 2423867.0381278 6964289.5219654
#Sta/Elev= 30
       0  449.88  589.71  449.64  708.61  433.04  1522.3  446.86 2147.65  434.89
 2200.56  445.37 2268.28  436.69 2285.34  447.13 2983.59  445.14 3980.97  442.04
 4802.25  432.91    8250     444 9787.86     438    9982   439.1   10067     406
   10147   415.2   10184     43310272.72     43210324.68     41010480.26     436
10690.35     43410798.95     416 10850.2     43611191.49     43811277.45     452
11362.48     43411580.19     42211645.85     436 12377.7     46013520.99     466
#Mann= 9 ,-1,0
       0     .07       0 2200.56     .05       0 2285.34     .07       0
 2983.59     .12       0 3980.97    .085       0    8250    .075       0
 9787.86     .09       0    9982    .055       0   10184     .12       0
Levee=0,,,-1,11259.76,452,,
#Block Obstruct= 2 ,-1
10272.72   10550     43210637.55   10900     436
Bank Sta=9982,10184
XS Rating Curve= 0 ,0
Exp/Cntr=0.3,0.1

Type RM Length L Ch R = 1 ,50221   ,1095,757,668
BEGIN DESCRIPTION:
This cross section corresponds to cross section 50225 of the non-georeferenced CDC model which was the source of this model.
END DESCRIPTION:
XS GIS Cut Line= 6
  2429001.342726 6976101.2903723 2428396.3348435 6972296.1739311
 2427798.8422721 6968539.2975866 2427143.2340033 6967502.8852893
 2426437.1461766 6966386.7638339  2425102.682599 6964277.6183724
#Sta/Elev= 30
       0  450.07  712.53  445.74  820.76  433.12   899.3  440.84 1252.62  436.34
 1372.33  446.38 3278.76  448.88 3544.05  437.51  4037.1  439.93 5175.31  438.95
 7064.74   443.2 7446.47  435.71 7630.48     445    7780     436  8831.7     440
  8863.7     432  9223.7     432  9271.7     420 10015.7     420 10091.7  439.05
 10389.7   440.5 10408.7   423.8 10463.7   405.7 10582.7   414.2 10620.7   433.6
 10669.7   439.211089.03     43811402.21     44011625.44     45212699.94     456
#Mann= 12 ,-1,0
       0      .1       0  712.53    .065       0 1372.33     .07       0
 3278.76     .12       0  4037.1    .065       0 5175.31      .1       0
    7780    .085       0  8831.7    .055       0 10091.7     .09       0
 10389.7     .05       0 10669.7     .04       011089.03      .1       0
Levee=0,,,-1,11625.44,452,,
Bank Sta=10389.7,10669.7
XS Rating Curve= 0 ,0
Exp/Cntr=0.3,0.1

Type RM Length L Ch R = 1 ,49464   ,803,3148,3446
BEGIN DESCRIPTION:
This cross section corresponds to cross section 49477 of the non-georeferenced CDC model which was the source of this model.
END DESCRIPTION:
XS GIS Cut Line= 3
  2429759.517812 6976561.5827231  2428835.198139 6968058.7621303
 2425726.7138704 6964295.5813365
#Sta/Elev= 30
       0  444.88   477.9   449.1  527.69  441.29  610.17   432.7   731.1  441.64
  911.56  435.93 2078.27  446.92 2177.35  435.75 3093.81  442.11 3869.88  436.02
 4024.67  443.47 4094.16   436.1 7406.48  441.31    8770     434 9069.62     432
  9171.5  444.31 10196.2  444.31   10241     434   10682     434   10738     420
   11363     420   11437  438.58   11668   442.7   11735   405.5   11800     409
   11835     426   11872   430.6   11883   439.712840.75     44213433.91     454
#Mann= 12 ,-1,0
       0      .1       0  527.69    .065       0   731.1     .07       0
 2078.27     .12       0 3093.81    .065       0 4024.67      .1       0
    8770     .11       0  9171.5     .08       0 10196.2    .055       0
   11437     .09       0   11668     .05       0   11883    .085       0
#XS Ineff= 2 , 0
       0   477.9     460               0
Permanent Ineff=
       F       F
Bank Sta=11668,11883
XS Rating Curve= 0 ,0
Exp/Cntr=0.3,0.1

Type RM Length L Ch R = 1 ,46316   ,836,1901,1978
BEGIN DESCRIPTION:
This cross section corresponds to cross section 46329 of the non-georeferenced CDC model which was the source of this model.
END DESCRIPTION:
XS GIS Cut Line= 6
  2430406.963215   6976831.81924 2430067.3711996 6972422.0506478
 2429890.7065267 6970128.5421115 2429714.0119982 6967835.0358717
 2429284.4127917 6965095.9268487 2428870.0809433  6962454.649979
#Sta/Elev= 30
   81.47  449.93  412.21  445.33     511  434.48  987.91   445.1 1226.81  435.52
 2040.52  445.43 2862.94  437.76 4053.32  437.65    6268  442.57    6292     436
    6906     442    7738   441.3   10901   444.2   10996     420   11156     420
 11252.8   444.2 12216.2   444.2   12313     420   12842     420   12922     440
   13122   438.9   13175   411.6   13235   406.2   13286   411.6   13295   423.7
   13340   437.813699.83     44214415.12     44214451.41     45414551.07     458
#Mann= 15 ,-1,0
   81.47      .1       0  412.21    .065       0  987.91     .12       0
 2862.94    .065       0 4053.32    .085       0    6268    .065       0
    6906     .12       0    7738     .08       0   10901    .055       0
 11252.8     .08       0 12216.2    .055       0   12922     .09       0
   13122    .055       0   13340     .04       013699.83     .08       0
#Block Obstruct= 1 ,-1
    6409    6815     455
Bank Sta=13122,13340
XS Rating Curve= 0 ,0
Exp/Cntr=0.3,0.1

Type RM Length L Ch R = 1 ,44415   ,83,83,83
BEGIN DESCRIPTION:
This cross section corresponds to cross section 44427 of the non-georeferenced CDC model which was the source of this model.
END DESCRIPTION:
XS GIS Cut Line= 6
  2430913.642398 6978931.8831911  2430948.008874 6970715.5409375
 2431001.3181506 6969547.1820537 2431023.5300484 6967770.2089016
 2430970.2210999 6966597.4061292 2430989.0199468 6962293.8081091
#Sta/Elev= 30
       0  461.45     255  454.39  312.79  444.64  435.51  452.26 3043.06  448.12
 3174.56  434.79 3338.56  448.67 4205.09  438.16 5831.08   438.3 5927.27  438.28
   10717     442   11611  438.67   11823   442.5   12812   442.5   12882     425
   13080     425   13150   442.5   14506   442.5   14555     430   14896     442
   15003   435.5   15053   426.3   15082   406.5   15172   406.5   15204   426.2
   15255   438.8   16414     438   16524     444   16530     452   16641   465.5
#Mann= 13 ,-1,0
       0      .1       0 3043.06    .075       0 3338.56     .09       0
 5831.08    .065       0 5927.27    .075       0   10717     .07       0
   11611     .09       0   11823     .08       0   12812    .055       0
   13150     .08       0   14506    .055       0   15003     .05       0
   15255    .065       0
#Block Obstruct= 1 ,-1
    9175    9592     455
Bank Sta=15003,15255
XS Rating Curve= 0 ,0
Exp/Cntr=0.3,0.1

Type RM Length L Ch R = 1 ,44332   ,118,118,118
BEGIN DESCRIPTION:
This cross section corresponds to cross section 44351 of the non-georeferenced CDC model which was the source of this model.
Belt Line Road upstream bounding cross-section.
END DESCRIPTION:
XS GIS Cut Line= 6
  2431017.183604 6978088.3306538 2431018.2610301 6977391.1883473
 2431018.2610301 6972897.9719401 2431032.2075245 6969275.3079256
 2431044.5969354 6966055.1641034 2431059.1234812 6962280.6076762
#Sta/Elev= 30
    1000   458.9    3492     447    3533     431    3598     431    3658     447
    5543   450.9  5552.3     442    5797     442    5827     434    5937     442
  6182.3     442    6191     451   13040   445.5   13040   438.5   13161   426.9
   13276   438.3   13276   446.3   14704   446.7   14704   440.4   14861   431.4
   14940   441.6   14940   447.9   15138   448.9   15138   441.4   15268     406
   15423   439.6   15423   448.7   16690   440.9   16691   449.5   16808   465.2
#Mann= 11 ,-1,0
    1000     .03       0    3492     .05       0    3658     .03       0
    5797     .05       0    5937     .03       0   13040     .05       0
   13276     .03       0   14704     .05       0   14940     .03       0
   15138     .05       0   15423     .03       0
#XS Ineff= 2 , 0
       0                   15423       0   448.7
Permanent Ineff=
       F       T
Bank Sta=15138,15423
XS Rating Curve= 0 ,0
Exp/Cntr=0.3,0.1