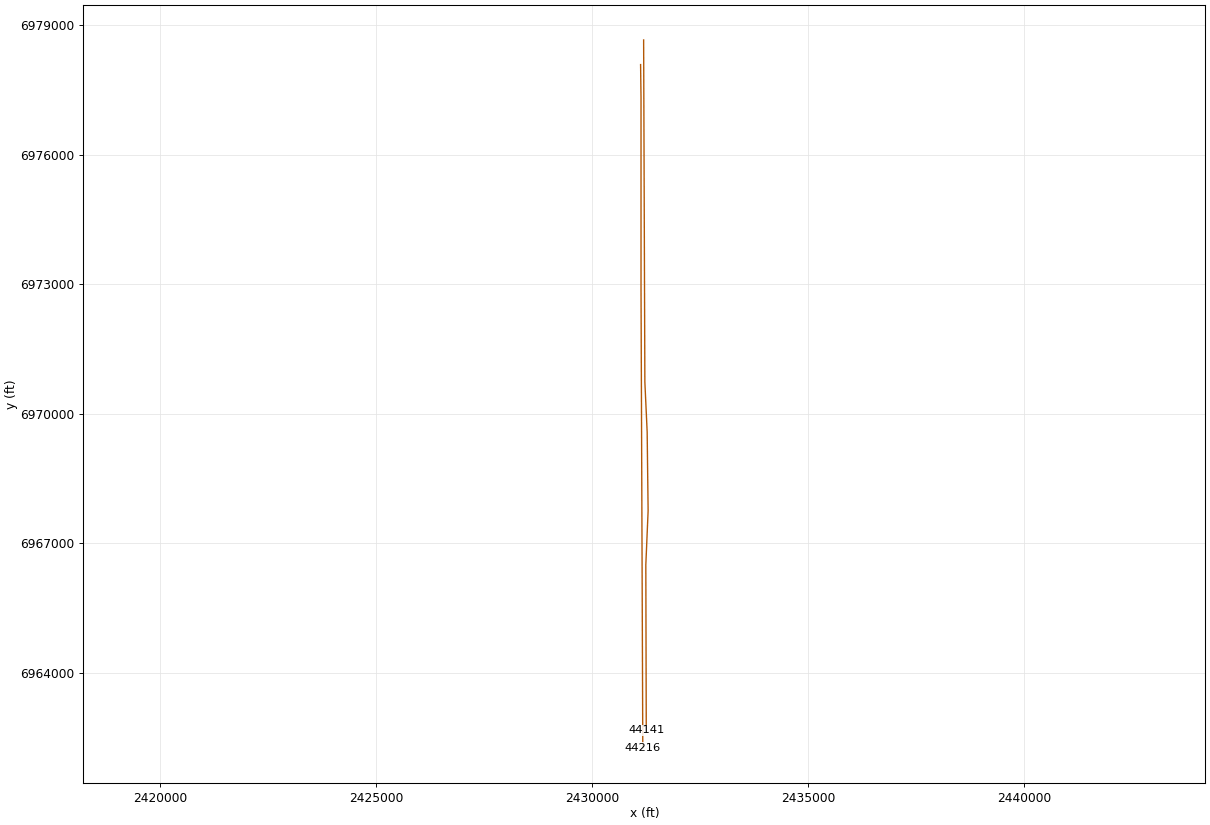
HEC-RAS study CDC_Consolidated_Model.prj: Upper Trinity CDC Consolidated Model

--- CDC_Consolidated_Model.g04 (geometry) --- (continued)

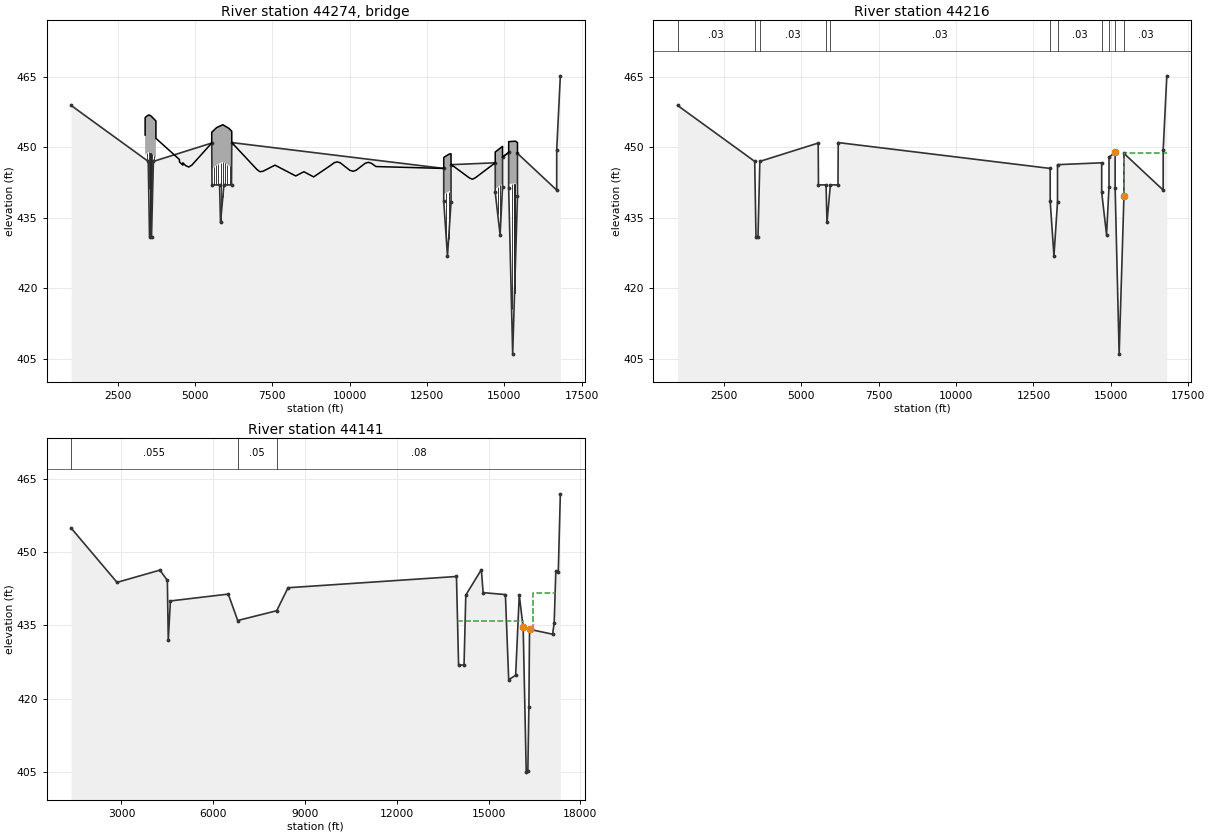
Type RM Length L Ch R = 3 ,44274   ,,,
BEGIN DESCRIPTION:
Belt Line Road
END DESCRIPTION:
Node Name=Belt Line Road
Bridge Culvert--1,0,-1,-1, 0
Deck Dist Width WeirC Skew NumUp NumDn MinLoCord MaxHiCord MaxSubmerge Is_Ogee
0.5,117,2.6,0, 59, 59, , , 0.95, 0, 0,0,,
    3391    3391    3438    3515    3592    3740    3740    4500    4500    4610
    4610    4700    4800    4900    5543    5543    5704    5904    6104    6191
    6191    7000    7100    7200    7587    8257    8521    8837    9397    9495
    9595    9695   10007   10107   10207   10502   10602   10702   10850   13040
   13040   13040   13100   13231   13276   13276   13350   13864   13962   14060
   14704   14704   14940   14940   15138   15138   15357   15423   15423
   452.6   456.3   456.6   456.9   456.6   455.6   451.9   447.4   446.9   446.2
   446.7   446.1   445.8   446.2   450.9   453.2   454.2   454.8     454   453.4
     451   445.3   444.8   444.9   446.2   443.9   444.8   443.7   446.2   446.7
   446.9   446.7   445.1   444.9   445.1   446.6   446.8   446.6   445.9   445.5
   445.5   447.8   448.1   448.6   448.6   446.3     446   443.5   443.2   443.5
   446.7     449   450.2   447.9   448.9   451.2   451.3     451   448.7
   452.6   448.4   448.7     449   448.7   447.7   451.9   447.4   446.9   446.2
   446.7   446.1   445.8   446.2   450.9   445.3   446.3   446.9   446.1   445.5
     451   445.3   444.8   444.9   446.2   443.9   444.8   443.7   446.2   446.7
   446.9   446.7   445.1   444.9   445.1   446.6   446.8   446.6   445.9   445.5
   445.5   439.9   440.2   440.7   440.7   446.3     446   443.5   443.2   443.5
   446.7   441.1   442.3   447.9   448.9   442.2   442.3     442   448.7
    3391    3391    3438    3515    3592    3740    3740    4500    4500    4610
    4610    4700    4800    4900    5543    5543    5704    5904    6104    6191
    6191    7000    7100    7200    7587    8257    8521    8837    9397    9495
    9595    9695   10007   10107   10207   10502   10602   10702   10850   13040
   13040   13040   13100   13231   13276   13276   13350   13864   13962   14060
   14704   14704   14940   14940   15138   15138   15357   15423   15423
   452.6   456.3   456.6   456.9   456.6   455.6   451.9   447.4   446.9   446.2
   446.7   446.1   445.8   446.2   450.9   453.2   454.2   454.8     454   453.4
     451   445.3   444.8   444.9   446.2   443.9   444.8   443.7   446.2   446.7
   446.9   446.7   445.1   444.9   445.1   446.6   446.8   446.6   445.9   445.5
   445.5   447.8   448.1   448.6   448.6   446.3     446   443.5   443.2   443.5
   446.7     449   450.2   447.9   448.9   451.2   451.3     451   448.7
   452.6   448.4   448.7     449   448.7   447.7   451.9   447.4   446.9   446.2
   446.7   446.1   445.8   446.2   450.9   445.3   446.3   446.9   446.1   445.5
     451   445.3   444.8   444.9   446.2   443.9   444.8   443.7   446.2   446.7
   446.9   446.7   445.1   444.9   445.1   446.6   446.8   446.6   445.9   445.5
   445.5   439.9   440.2   440.7   440.7   446.3     446   443.5   443.2   443.5
   446.7   441.1   442.3   447.9   448.9   442.2   442.3     442   448.7
Pier Skew, UpSta & Num, DnSta & Num=  ,3449, 2 ,3449, 2 , 0 , 0 , 0 ,,
     2.5     2.5
     430     450
     2.5     2.5
     430     450
Pier Skew, UpSta & Num, DnSta & Num=  ,3507, 2 ,3507, 2 , 0 , 0 , 0 ,,
     2.5     2.5
     430     450
     2.5     2.5
     430     450
Pier Skew, UpSta & Num, DnSta & Num=  ,3565, 2 ,3565, 2 , 0 , 0 , 0 ,,
     2.5     2.5
     430     450
     2.5     2.5
     430     450
Pier Skew, UpSta & Num, DnSta & Num=  ,3623, 2 ,3623, 2 , 0 , 0 , 0 ,,
     2.5     2.5
     430     450
     2.5     2.5
     430     450
Pier Skew, UpSta & Num, DnSta & Num=  ,3681, 2 ,36812.54, 2 , 0 , 0 , 0 ,,
     2.5     2.5
     430     450
     2.5     2.5
     430     450
Pier Skew, UpSta & Num, DnSta & Num=  ,5615, 2 ,56152.54, 2 , 0 , 0 , 0 ,,
     2.5     2.5
     430     450
     2.5     2.5
     430     450
Pier Skew, UpSta & Num, DnSta & Num=  ,5687, 2 ,56872.54, 2 , 0 , 0 , 0 ,,
     2.5     2.5
     430     450
     2.5     2.5
     430     450
Pier Skew, UpSta & Num, DnSta & Num=  ,5759, 2 ,57592.54, 2 , 0 , 0 , 0 ,,
     2.5     2.5
     430     450
     2.5     2.5
     430     450
Pier Skew, UpSta & Num, DnSta & Num=  ,5831, 2 ,58312.54, 2 , 0 , 0 , 0 ,,
     2.5     2.5
     430     450
     2.5     2.5
     430     450
Pier Skew, UpSta & Num, DnSta & Num=  ,5903, 2 ,59032.54, 2 , 0 , 0 , 0 ,,
     2.5     2.5
     430     450
     2.5     2.5
     430     450
Pier Skew, UpSta & Num, DnSta & Num=  ,5975, 2 ,59752.54, 2 , 0 , 0 , 0 ,,
     2.5     2.5
     430     450
     2.5     2.5
     430     450
Pier Skew, UpSta & Num, DnSta & Num=  ,6047, 2 ,60472.54, 2 , 0 , 0 , 0 ,,
     2.5     2.5
     430     450
     2.5     2.5
     430     450
Pier Skew, UpSta & Num, DnSta & Num=  ,6119, 2 ,61192.54, 2 , 0 , 0 , 0 ,,
     2.5     2.5
     430     450
     2.5     2.5
     430     450
Pier Skew, UpSta & Num, DnSta & Num=  ,13119, 2 ,13119, 2 , 0 , 0 , 0 ,,
     2.5     2.5
     400     444
     2.5     2.5
     400     444
Pier Skew, UpSta & Num, DnSta & Num=  ,13198, 2 ,13198, 2 , 0 , 0 , 0 ,,
     2.5     2.5
     400     444
     2.5     2.5
     400     444
Pier Skew, UpSta & Num, DnSta & Num=  ,14783, 2 ,14783, 2 , 0 , 0 , 0 ,,
     2.5     2.5
     400     444
     2.5     2.5
     400     444
Pier Skew, UpSta & Num, DnSta & Num=  ,14862, 2 ,14862, 2 , 0 , 0 , 0 ,,
     2.5     2.5
     400     444
     2.5     2.5
     400     444
Pier Skew, UpSta & Num, DnSta & Num=  ,15233, 2 ,15233, 2 , 0 , 0 , 0 ,,
       3       3
     400     444
       3       3
     400     444
Pier Skew, UpSta & Num, DnSta & Num=  ,15328, 2 ,15328, 2 , 0 , 0 , 0 ,,
       3       3
     400     444
       3       3
     400     444
BR Coef=-1 , 0 , 0 ,, 0 ,,,0.8,-1,,1,
WSPro=,,,, 1 ,,,, 0 ,,,, 0 ,,,,-1 ,-1 ,-1 , 0 , 0 , 0 , 0 , 0
BC Design=,, 0 ,, 0 ,,,,,,
BC HTab HWMax=454.8
BC Use User HTab Curves=0
BC User HTab FreeFlow(D)= 0

Type RM Length L Ch R = 1 ,44216   ,56,75,75
BEGIN DESCRIPTION:
This cross section corresponds to cross section 44232 of the non-georeferenced CDC model which was the source of this model.
Belt Line Road downstream bounding cross-section.
CDC GP080808-1 Belt Line West Reclamation
Cross-section 44232 - 55761
Located in LOB.
-----------------------------------------
-------------------------------------------------------
CDC IRV120304-1 Belt Line Road from IH30 to Rock Island
-------------------------------------------------------
END DESCRIPTION:
XS GIS Cut Line= 6
  2431124.406487 6978083.6410307 2431134.5770704 6977312.3341743
 2431134.5770704 6972896.8479266 2431148.5235648 6969272.4381807
 2431172.6019287 6963012.1170399 2431175.4516606 6962265.3324442
#Sta/Elev= 30
    1000   458.9    3492     447    3533     431    3598     431    3658     447
    5543   450.9  5552.3     442    5797     442    5827     434    5937     442
  6182.3     442    6191     451   13040   445.5   13040   438.5   13161   426.9
   13276   438.3   13276   446.3   14704   446.7   14704   440.4   14861   431.4
   14940   441.6   14940   447.9   15138   448.9   15138   441.4   15268     406
   15423   439.6   15423   448.7   16690   440.9   16691   449.5   16808   465.2
#Mann= 11 ,-1,0
    1000     .03       0    3492     .05       0    3658     .03       0
    5797     .05       0    5937     .03       0   13040    .055       0
   13276     .03       0   14704     .05       0   14940     .03       0
   15138     .05       0   15423     .03       0
#XS Ineff= 2 , 0
       0                   15423       0   448.7
Permanent Ineff=
       F       T
Bank Sta=15138,15423
XS Rating Curve= 0 ,0
Exp/Cntr=0.3,0.1

Type RM Length L Ch R = 1 ,44141   ,764,784,790
BEGIN DESCRIPTION:
This cross section corresponds to cross section 44153 of the non-georeferenced CDC model which was the source of this model.
END DESCRIPTION:
XS GIS Cut Line= 6
  2431194.921402 6978653.9746285 2431223.4400817 6970733.3109151
 2431276.7490302 6969573.8358718  2431298.960928 6967747.9960196
 2431245.6519795 6966495.2301524 2431255.9631441  6962666.794463
#Sta/Elev= 30
    1355   454.9    2855   443.8    4257   446.3    4500   444.2    4530     432
    4600     440    6491   441.4    6800     436    8075     438    8444   442.7
   13950     445   14019   426.9   14197   426.9   14255   441.2   14764   446.4
   14821   441.7   15549   441.3   15657   423.9   15884   424.8   16002   441.2
   16130   434.6   16230     405   16283   405.2   16317   418.4   16338   434.2
   17090   433.2   17143   435.4   17197   446.1   17278     446   17345   461.9
#Mann= 3 ,-1,0
    1355    .055       0    6800     .05       0    8075     .08       0
#XS Ineff= 2 ,-1
   13954   16130     436   16450   17209   441.7
Permanent Ineff=
       F       T
Bank Sta=16130,16338
XS Rating Curve= 0 ,0
Exp/Cntr=0.3,0.1