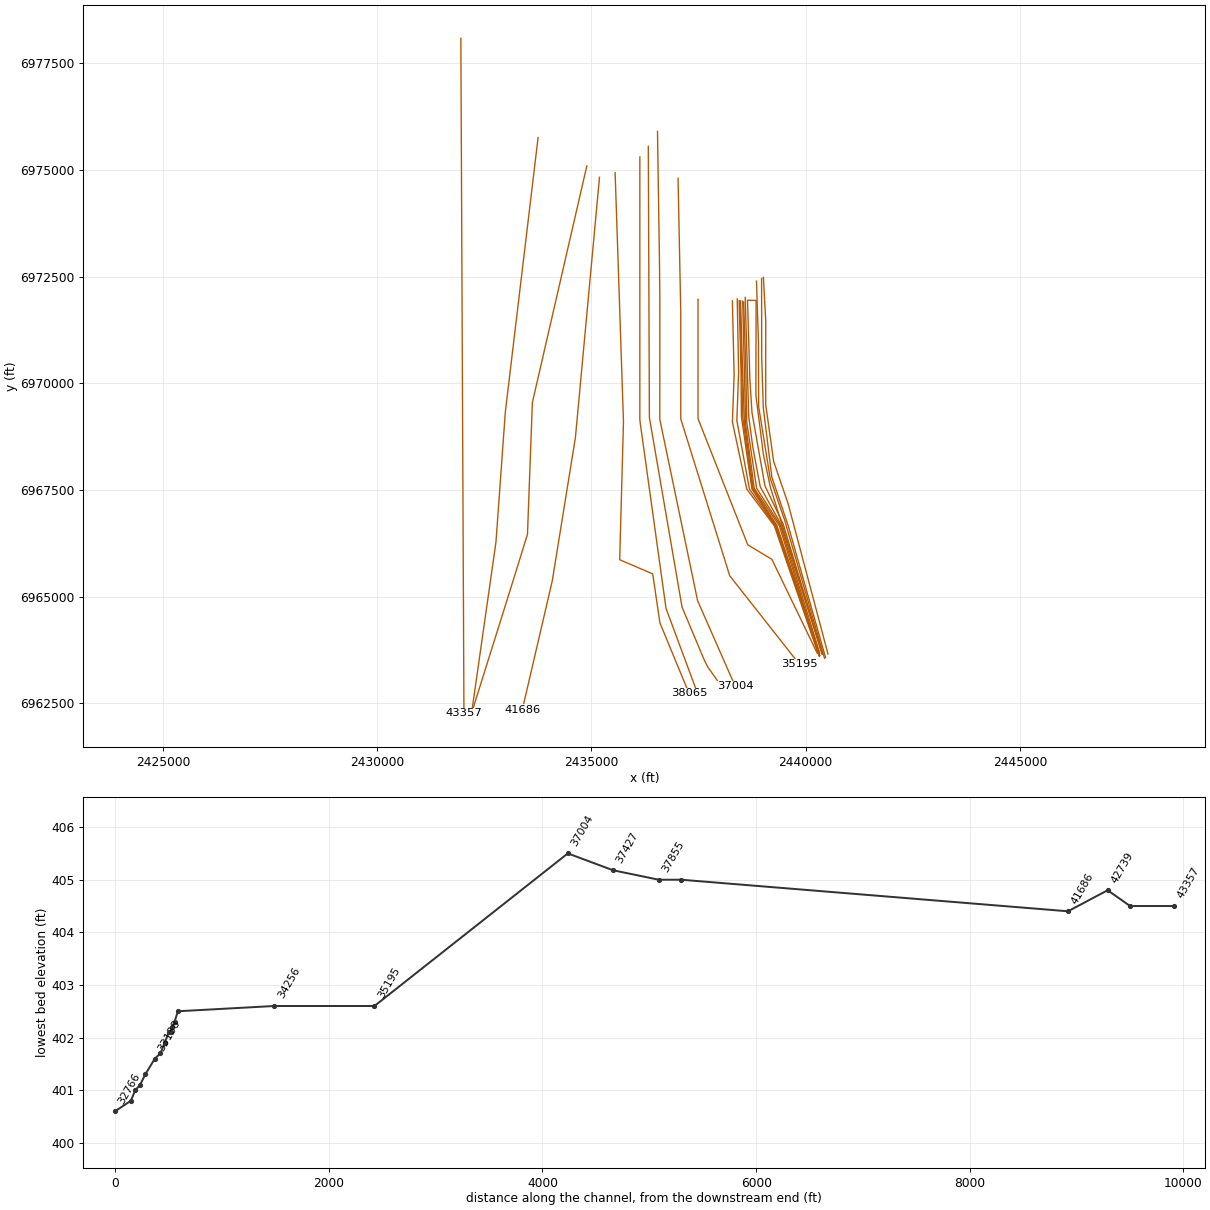
HEC-RAS study CDC_Consolidated_Model.prj: Upper Trinity CDC Consolidated Model

--- CDC_Consolidated_Model.g04 (geometry) --- (continued)

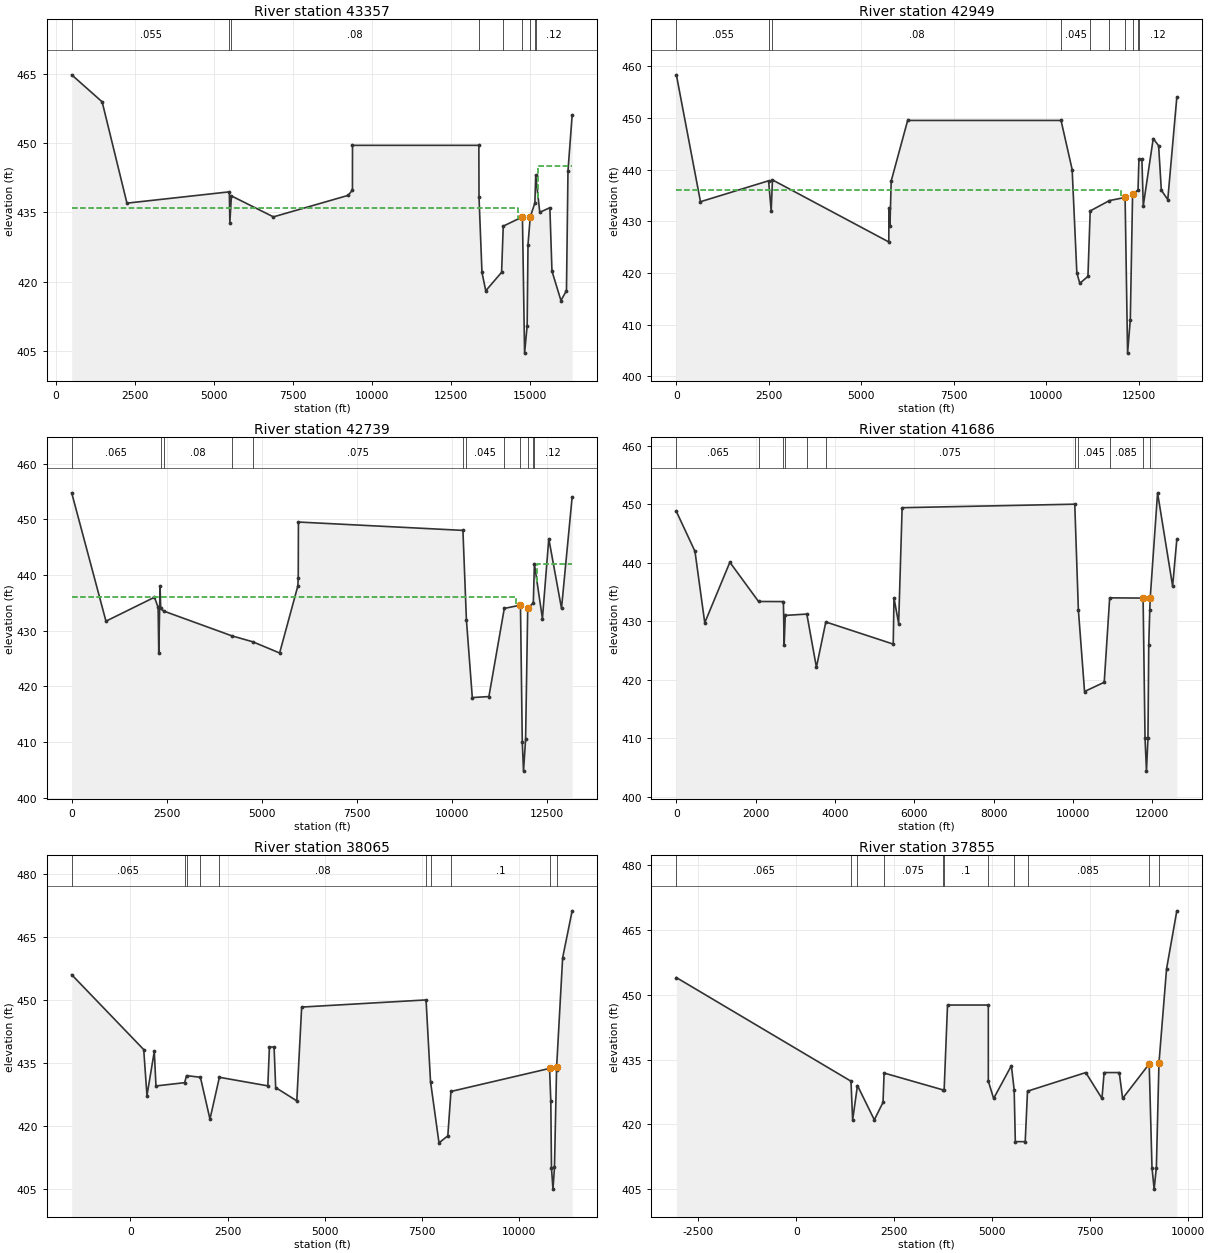
Type RM Length L Ch R = 1 ,43357   ,1524,408,390
BEGIN DESCRIPTION:
This cross section corresponds to cross section 43369 of the non-georeferenced CDC model which was the source of this model.
END DESCRIPTION:
XS GIS Cut Line= 6
  2431954.349471 6978088.4298544 2431962.0452317 6976397.8681555
 2431973.5291327 6973874.3981368 2431990.9772605 6970038.7263462
 2432008.8751906 6966102.1187339 2432026.3049457 6962266.4528488
#Sta/Elev= 30
  502.22  464.77 1465.36  458.92 2249.31  436.98 5486.05  439.43 5502.55  432.76
 5551.55  438.55 6880.06  434.01 9241.59  438.66 9378.37  439.81    9380   449.5
   13375   449.5   13380   438.3 13473.4     42213592.98     41814093.83     422
14146.09     43214752.67     434 14820.7   404.514902.11  410.4214928.83     428
14999.68     434 15145.7     437 15172.7     443 15300.7     43515620.13     436
15686.37  422.2715970.38  415.8916144.95  418.0316192.98     44416324.36     456
#Mann= 9 ,-1,0
  502.22    .055       0 5486.05     .05       0 5551.55     .08       0
   13380    .045       014146.09    .065       014752.67     .05       0
14999.68     .12       0 15145.7     .06       0 15172.7     .12       0
#XS Ineff= 2 , 0
       014620.61     436 15249.7       0     445
Permanent Ineff=
       F       T
Bank Sta=14752.67,14999.68
XS Rating Curve= 0 ,0
Exp/Cntr=0.3,0.1

Type RM Length L Ch R = 1 ,42949   ,959,210,80
BEGIN DESCRIPTION:
This cross section corresponds to cross section 42961 of the non-georeferenced CDC model which was the source of this model.
END DESCRIPTION:
XS GIS Cut Line= 6
  2433756.997022 6975764.3681102 2433380.5187728 6972596.3711653
 2432992.1888408 6969329.3809802 2432773.6699208 6966280.6098467
 2432482.0799528 6964227.1884287   2432204.33707   6962271.55192
#Sta/Elev= 30
       0  458.32  651.49  433.78 2493.22  437.83 2563.56     432 2597.63     438
 5743.17     426 5746.48  432.47 5774.92  429.14 5808.16  437.78  6252.6   449.5
   10400   449.510700.38     44010827.49     42010907.34     41811127.15  419.34
11188.12     43211707.37     43412131.79  434.61   12199   404.512272.56  410.98
12334.37  435.31   12481     436   12506     442   12586     442   12623     433
12892.35     44613038.21   444.6 13111.5     43613285.71  434.1913530.27     454
#Mann= 10 ,-1,0
       0    .055       0 2493.22     .05       0 2597.63     .08       0
   10400    .045       011188.12     .06       011707.37    .075       0
12131.79     .05       012334.37     .12       0   12481     .06       0
   12506     .12       0
#XS Ineff= 2 , 0
       012021.51     436   12586       0     442
Permanent Ineff=
       F       T
Bank Sta=12131.79,12334.37
XS Rating Curve= 0 ,0
Exp/Cntr=0.3,0.1

Type RM Length L Ch R = 1 ,42739   ,295,371,363
BEGIN DESCRIPTION:
This cross section corresponds to cross section 42751 of the non-georeferenced CDC model which was the source of this model.
END DESCRIPTION:
XS GIS Cut Line= 6
   2434894.38169 6975098.5194684 2433623.2600852 6969551.4290925
 2433619.7614045 6969451.9460237 2433509.1149722 6966463.8066588
 2433107.9458271 6965164.6596508 2432206.9518942 6962279.9246067
#Sta/Elev= 30
       0  454.74  901.57  431.71 2177.29     436 2273.31  434.17 2290.27     426
 2323.98     438 2341.81     434 2421.07  433.52 4211.51  429.08 4766.46     428
 5468.73     426 5946.82     438 5958.78  439.45  5963.2   449.510289.95     448
10381.16     43210536.37     41810973.11  418.1811378.03     43411803.32  434.59
11851.23     410 11883.5   404.811938.17  410.5511994.12     434 12141.5     435
 12169.5     44212380.89  432.1712548.39  446.5112882.52     43413162.44     454
#Mann= 12 ,-1,0
       0    .065       0 2341.81     .05       0 2421.07     .08       0
 4211.51     .05       0 4766.46    .075       010289.95    .035       0
10381.16    .045       011378.03    .085       011803.32     .05       0
11994.12     .12       0 12141.5     .06       0 12169.5     .12       0
#XS Ineff= 2 , 0
       0 11679.3     436 12241.5       0     442
Permanent Ineff=
       F       T
Bank Sta=11803.32,11994.12
XS Rating Curve= 0 ,0
Exp/Cntr=0.3,0.1

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
Type RM Length L Ch R = 1 ,41686   ,703,3622,3928
BEGIN DESCRIPTION:
This cross section corresponds to cross section 416973 of the non-georeferenced CDC model which was the source of this model.
-----------------------------------------------------
LOMR # 16-06-2467P Running Bear Park Levee reflected in LOB.
END DESCRIPTION:
XS GIS Cut Line= 6
  2435190.386695 6974832.8061043 2434905.2466944 6971739.3092312
 2434627.8902938 6968730.9185944 2434087.7909803 6965372.5119254
 2433727.3727378 6963816.1361012 2433389.4469045 6962357.0379695
#Sta/Elev= 30
       0  448.76     469  441.95  716.11  429.74  1349.4  440.08 2072.76  433.38
 2699.91  433.36    2719     426    2747     431 3290.84  431.23    3533  422.14
 3769.76  429.88 5470.74   426.1 5489.52     434 5607.24   429.6 5695.09   449.4
10050.02     450 10140.5     432 10296.7     41810793.14  419.5810930.77     434
 11773.7  433.9611822.75     410 11858.7   404.411896.72  410.0711916.56     426
11942.83     43211953.44     43412139.03  451.9412518.51     436 12624.6     444
#Mann= 11 ,-1,0
       0    .065       0 2072.76     .08       0 2699.91     .05       0
    2747    .075       0 3290.84     .04       0 3769.76    .075       0
10050.02    .035       0 10140.5    .045       010930.77    .085       0
 11773.7     .05       011942.83     .06       0
#XS Ineff= 2 , 0
       0 11773.7  433.96               0
Permanent Ineff=
       F       F
#Block Obstruct= 2 , 0
       0                   12136       0   451.7
Bank Sta=11773.7,11953.44
XS Rating Curve= 0 ,0
Exp/Cntr=0.3,0.1

Type RM Length L Ch R = 1 ,38065   ,770,209,217
BEGIN DESCRIPTION:
This cross section corresponds to cross section 38059 of the non-georeferenced CDC model which was the source of this model.
END DESCRIPTION:
XS GIS Cut Line= 6
2435554.826474776974938.42010256 2435749.6282077  6969102.156369
 2435661.4889483  6965868.123467 2436432.5313695 6965535.1343036
 2436599.6320852 6964389.3009653 2437280.4043457 6962733.3626761
#Sta/Elev= 30
   -1508     456  343.27  438.19  426.76  427.24  615.23  437.76  658.13  429.54
 1394.74  430.32    1444     432  1800.4   431.6    2046  421.65  2288.4   431.6
 3533.25  429.56    3574   438.8    3694   438.8 3734.96  429.15 4277.66     426
 4403.05   448.3    7600     450 7714.85  430.58 7932.69     416 8159.45  417.68
 8240.12  428.2310774.35  433.7110806.32  425.9910823.78     41010862.19     405
 10900.6  410.1510954.14  433.3910955.89     43411110.31     46011354.83  471.19
#Mann= 10 ,-1,0
   -1508    .065       0 1394.74     .05       0    1444     .08       0
  1800.4     .04       0  2288.4     .08       0    7600    .035       0
 7714.85    .045       0 8240.12      .1       010774.35    .055       0
10954.14    .065       0
#XS Ineff= 2 , 0
       010774.35  433.71               0
Permanent Ineff=
       F       F
Bank Sta=10774.35,10955.89
XS Rating Curve= 0 ,0
Exp/Cntr=0.3,0.1

Type RM Length L Ch R = 1 ,37855   ,187,428,428
BEGIN DESCRIPTION:
This cross section corresponds to cross section 37866 of the non-georeferenced CDC model which was the source of this model.
END DESCRIPTION:
XS GIS Cut Line= 6
2436131.889009176975308.98213912 2436131.6080868 6969150.7218887
 2436144.5601607 6969044.5088465 2436457.0890632 6966787.1573901
 2436742.4759596 6964726.1011447 2437486.3639075 6962714.0569405
#Sta/Elev= 30
   -3060     454  1395.6     430 1437.89     421  1560.6     429  1991.1  421.05
  2213.1   425.1 2240.28  431.89 3737.69     428 3772.86     428 3858.86  447.64
    4900  447.64    4900     430  5035.5     426 5488.37   433.6 5559.52     428
 5589.05     416 5841.23     416 5899.89  427.69 7386.27     432  7799.7     426
 7854.91     432 8241.02     432 8326.98     426 9004.99     434 9076.18     410
    9131     405 9187.95     410 9254.37  434.22 9447.76     456 9710.02  469.46
#Mann= 11 ,-1,0
   -3060    .065       0  1395.6     .05       0  1560.6     .04       0
 2240.28    .075       0 3737.69    .065       0 3772.86      .1       0
    4900    .085       0 5559.52    .045       0 5899.89    .085       0
 9004.99    .055       0 9254.37    .065       0
#XS Ineff= 2 , 0
       0 9004.99     434               0
Permanent Ineff=
       F       F
Bank Sta=9004.99,9254.37
XS Rating Curve= 0 ,0
Exp/Cntr=0.3,0.1

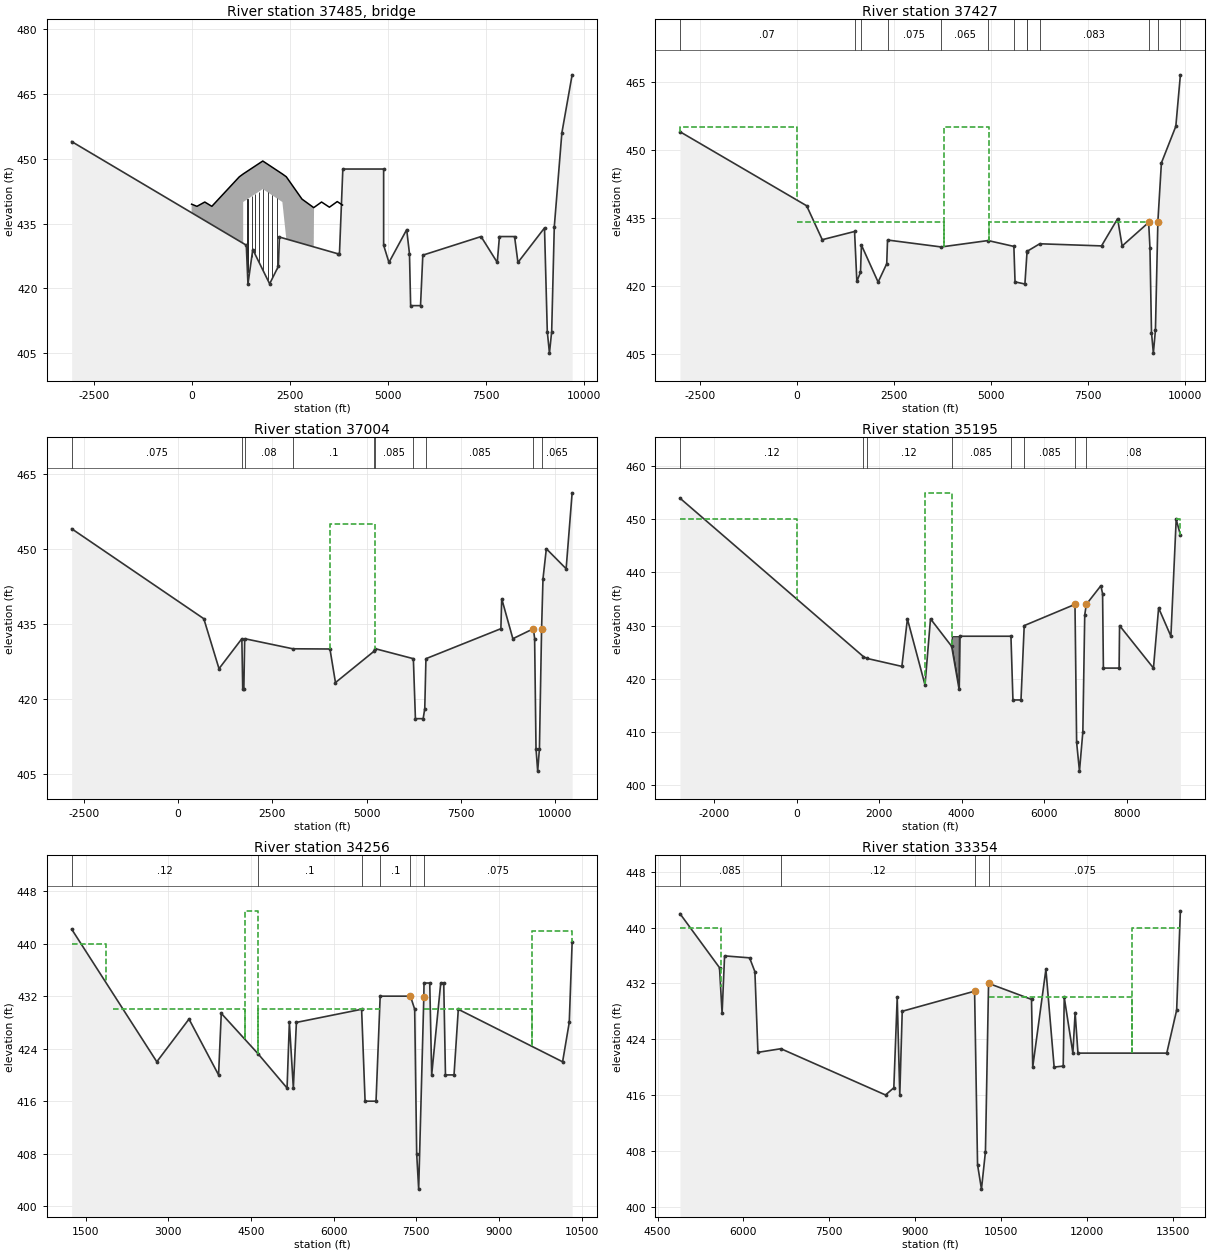
Type RM Length L Ch R = 3 ,37485   ,,,
BEGIN DESCRIPTION:
Hunter Ferrell Road
END DESCRIPTION:
Node Name=Hunter Ferrell R
Bridge Culvert--1,0,-1,-1, 0
Deck Dist Width WeirC Skew NumUp NumDn MinLoCord MaxHiCord MaxSubmerge Is_Ogee
92,115,2.6,0, 17, 17, , , 0.95, 0, 0,0,,
       0     136     336   516.1  1216.1  1316.1  1316.1  1816.1  2316.1  2316.1
  2416.1  2816.1  3116.1  3316.1  3516.1  3716.1  3851.1
   439.5     439     440     439  445.83   446.5   446.5   449.5   446.5   446.5
  445.85  440.68   438.7     440   438.8   440.1  439.29
                                                     440     443     440
       0     136     336  642.15 1342.15 1442.15 1442.15 1942.15 2442.15 2442.15
 2542.15 2942.15 3242.15 3442.15 3642.15 3842.15 3977.15
   439.5     439     440     439  445.83   446.5   446.5   449.5   446.5   446.5
  445.85  440.68   438.7     440   438.8   440.1  439.29
                                                     440     443     440
Pier Skew, UpSta & Num, DnSta & Num=  ,1425.1, 2 ,1529.5, 2 , 0 , 0 , 0 ,,
       3       3
     415     443
       3       3
     415     443
Pier Skew, UpSta & Num, DnSta & Num=  ,1535.1, 2 ,1639.5, 2 , 0 , 0 , 0 ,,
       3       3
     415     443
       3       3
     415     443
Pier Skew, UpSta & Num, DnSta & Num=  ,1607.26, 2 ,1711.66, 2 , 0 , 0 , 0 ,,
       3       3
     415     443
       3       3
     415     443
Pier Skew, UpSta & Num, DnSta & Num=  ,1721.26, 2 ,1825.66, 2 , 0 , 0 , 0 ,,
       3       3
     415     443
       3       3
     415     443
Pier Skew, UpSta & Num, DnSta & Num=  ,1824, 2 ,1928.4, 2 , 0 , 0 , 0 ,,
       3       3
     415     443
       3       3
     415     443
Pier Skew, UpSta & Num, DnSta & Num=  ,1942, 2 ,2046.43, 2 , 0 , 0 , 0 ,,
       3       3
     415     443
       3       3
     415     443
Pier Skew, UpSta & Num, DnSta & Num=  ,2060, 2 ,2164.43, 2 , 0 , 0 , 0 ,,
       3       3
     415     443
       3       3
     415     443
Pier Skew, UpSta & Num, DnSta & Num=  ,2178, 2 ,2282.43, 2 , 0 , 0 , 0 ,,
       3       3
     415     443
       3       3
     415     443
Abutment Skew #Up #Dn= , 2 , 2
  1316.1  1396.1
     440     420
 1442.15 1522.15
     440     420
Abutment Skew #Up #Dn= , 2 , 2
    2236  2316.1
     420     440
 2362.15 2442.15
     420     440
BR Coef=-1 , 0 , 0 ,, 0 ,,,0.8,0,1.2,0,
WSPro=,,,, 1 ,,,, 0 ,,,, 0 ,,,,-1 ,-1 ,-1 , 0 , 0 , 0 , 0 , 0
BC Design=,, 0 ,, 0 ,,,,,,
BC Use User HTab Curves=0
BC User HTab FreeFlow(D)= 0

Type RM Length L Ch R = 1 ,37427   ,423,423,423
BEGIN DESCRIPTION:
This cross section corresponds to cross section 37566 of the non-georeferenced CDC model which was the source of this model.
-------------------------------------------------
CDC IRV081607-01 Hunter Ferrell Road Improvements
Cross-section 37566 - 41697
-------------------------------------------------
END DESCRIPTION:
XS GIS Cut Line= 6
2436329.184343616975557.11367137     2436354.375     6969200.773
     2437116.528     6964755.894     2437642.492     6963499.962
     2437719.337     6963350.069     2438012.405     6962933.117
#Sta/Elev= 30
   -3015     454  252.59  437.67  654.85  430.19  1488.2     432    1547     421
    1641     423    1665     429  2095.5  420.84  2317.5  424.89 2338.42  430.12
 3721.44  428.59 4930.73     430 5596.53  428.71 5626.32  420.89  5880.7  420.42
 5935.55  427.48 5939.87  427.64 6263.96  429.29 7856.31  428.82 8271.45  434.82
  8388.2   428.8 9072.14     434 9105.54   428.4 9145.31  409.72 9193.43  405.18
 9247.12  410.28 9309.74  434.14 9400.59  447.11 9772.67  455.19 9890.54  466.54
#Mann= 13 ,-1,0
   -3015     .07       0  1488.2     .05       0    1665     .04       0
 2338.42    .075       0 3721.44    .065       0 4930.73    .085       0
 5596.53     .05       0 5935.55    .071       0 5939.87    .071       0
 6263.96    .083       0 9072.14    .055       0 9309.74    .065       0
 9890.54    .065       0
#XS Ineff= 4 ,-1
       0    3800     434    3800    4948     455    4948 9072.14     434
   -3015       0     455
Permanent Ineff=
       F       F       F       F
Bank Sta=9072.14,9309.74
XS Rating Curve= 0 ,0
Exp/Cntr=0.3,0.1

Type RM Length L Ch R = 1 ,37004   ,732,1810,1504
BEGIN DESCRIPTION:
This cross section corresponds to cross section 37015 of the non-georeferenced CDC model which was the source of this model.
END DESCRIPTION:
XS GIS Cut Line= 6
2436543.657249816975906.95023638 2436589.3968694 6972878.6783435
 2436597.8515769 6972023.9274283 2436597.6829421 6969156.6519949
  2437479.554866 6964906.8940902 2438355.5619722 6962905.7901528
#Sta/Elev= 30
   -2825     454  680.82     436 1084.36     426  1690.5     432 1713.73     422
 1743.65     422 1766.01     432    3044  429.98 4028.45  429.94 4174.51  423.22
    5200   429.5    5230     430 6241.83     428  6296.2     416  6501.7     416
 6544.24     418 6575.47     428 8564.02     434 8586.23     440 8882.11     432
 9428.39     434  9459.4     432 9496.32     410    9541   405.5 9587.13     410
 9644.33     434 9681.73     444 9770.36     45010295.96     44610454.99  461.19
#Mann= 10 ,-1,0
   -2825    .075       0  1690.5     .05       0 1766.01     .08       0
    3044      .1       0    5200      .1       0    5230    .085       0
 6241.83    .045       0 6575.47    .085       0 9428.39    .055       0
 9644.33    .065       0
#XS Ineff= 1 ,-1
    4030    5230     455
Permanent Ineff=
       F
Bank Sta=9428.39,9644.33
XS Rating Curve= 0 ,0
Exp/Cntr=0.3,0.1

Type RM Length L Ch R = 1 ,35195   ,411,938,901
BEGIN DESCRIPTION:
This cross section corresponds to cross section 35205 of the non-georeferenced CDC model which was the source of this model.
END DESCRIPTION:
XS GIS Cut Line= 6
2437023.32523453 6974807.8117066 2437086.9480397 6971651.6624248
 2437087.0700867 6969165.9708739 2437672.7779048 6967281.6327791
 2438229.2610438  6965491.521858 2439856.7000461 6963416.2750242
#Sta/Elev= 30
   -2825     454 1621.39  424.16 1703.39  423.83 2553.24  422.32 2687.39  431.26
 3113.89  418.83 3246.96  431.28    3760  426.09 3940.26     418 3952.48     428
  5196.6     428 5244.83     416 5439.96     416 5518.02     430 6748.51     434
 6788.34     408    6857   402.6 6938.95     410 6984.78     432 7023.02     434
 7375.95  437.51 7417.23     436 7436.85     422 7817.63     422 7828.68     430
 8650.17     422 8775.02  433.32 9072.88     428  9201.1     450 9302.89  447.09
#Mann= 8 ,-1,0
   -2825     .12       0 1621.39    .055       0 1703.39     .12       0
    3760    .085       0  5196.6    .045       0 5518.02    .085       0
 6748.51    .055       0 7023.02     .08       0
#XS Ineff= 3 ,-1
    3110    3760     455  9201.1 9302.89     450   -2825       0     450
Permanent Ineff=
       F       T       F
#Block Obstruct= 1 ,-1
    3760    3953     428
Bank Sta=6748.51,7023.02
XS Rating Curve= 0 ,0
Exp/Cntr=0.3,0.1

Type RM Length L Ch R = 1 ,34256   ,672,902,305
BEGIN DESCRIPTION:
This cross section corresponds to cross section 34268 of the non-georeferenced CDC model which was the source of this model.
STATIONS 7543-7573 ADDED FROM EFFECTIVE SECTION
FOR FLOWLINE
END DESCRIPTION:
XS GIS Cut Line= 6
  2437489.231482 6971974.3446556 2437489.3931009 6969173.6319478
 2438052.3463713 6967740.4245124 2438650.5371041 6966217.6529516
 2439213.2738395 6965876.4180698 2440272.3609602 6963674.9818559
#Sta/Elev= 30
    1249   442.2 2793.01     422 3376.86  428.51  3913.3     420 3962.13  429.38
 4627.69  423.24 5155.75     418 5197.43     428 5269.62     418 5325.11     428
 6507.97     430    6571     416 6769.38     416 6844.63     432 7393.73     432
 7470.61     430 7506.88     408    7543   402.6 7636.07  431.81 7639.87     434
 7743.76     434 7778.93     420 7943.02     434 7997.58     434 8028.91     420
 8184.18     420 8261.76     43010153.69     42210274.37     42810326.63   440.2
#Mann= 6 ,-1,0
    1249     .12       0 4627.69      .1       0 6507.97    .045       0
 6844.63      .1       0 7393.73    .055       0 7639.87    .075       0
#XS Ineff= 6 ,-1
    1249    1878     440 2003.31    4389     430 4389.04 4626.26     445
 4626.26    6844     430    7639    9600     430    960010326.63     442
Permanent Ineff=
       F       F       T       F       F       F
Bank Sta=7393.73,7636.07
XS Rating Curve= 0 ,0
Exp/Cntr=0.3,0.1

Type RM Length L Ch R = 1 ,33354   ,37,31,7
BEGIN DESCRIPTION:
This cross section corresponds to cross section 33382 of the non-georeferenced CDC model which was the source of this model.
END DESCRIPTION:
XS GIS Cut Line= 6
2438291.259691846971935.47088762  2438331.631902 6970196.5311487
 2438292.5693161 6969094.1006108 2438626.7707474 6967522.9200262
  2439270.000104  6966664.413213  2440310.726369 6963618.0446338
#Sta/Elev= 30
    4890     442 5581.54  434.25 5626.66  427.69 5669.97  435.94 6107.35  435.66
 6199.87  433.68 6253.14  422.11 6654.71  422.63 8482.86     416 8628.25  417.03
  8687.4  429.99 8732.44     416 8775.09     42810039.77  430.8810091.57     406
   10160   402.510229.52  407.8710283.96     432 11034.7   429.711056.13     420
11286.22     43411430.16     42011589.17  420.1411606.73     43011757.83     422
11797.07  427.8111846.53     42213398.52     422 13571.5  428.1613636.92   442.4
#Mann= 4 ,-1,0
    4890    .085       0 6654.71     .12       010039.77    .055       0
10283.96    .075       0
#XS Ineff= 4 ,-1
    4895    5601     440    6137    9895     430   10283   12790     430
   12790   13636     440
Permanent Ineff=
       T       F       F       F
Bank Sta=10039.77,10283.96
XS Rating Curve= 0 ,0
Exp/Cntr=0.3,0.1

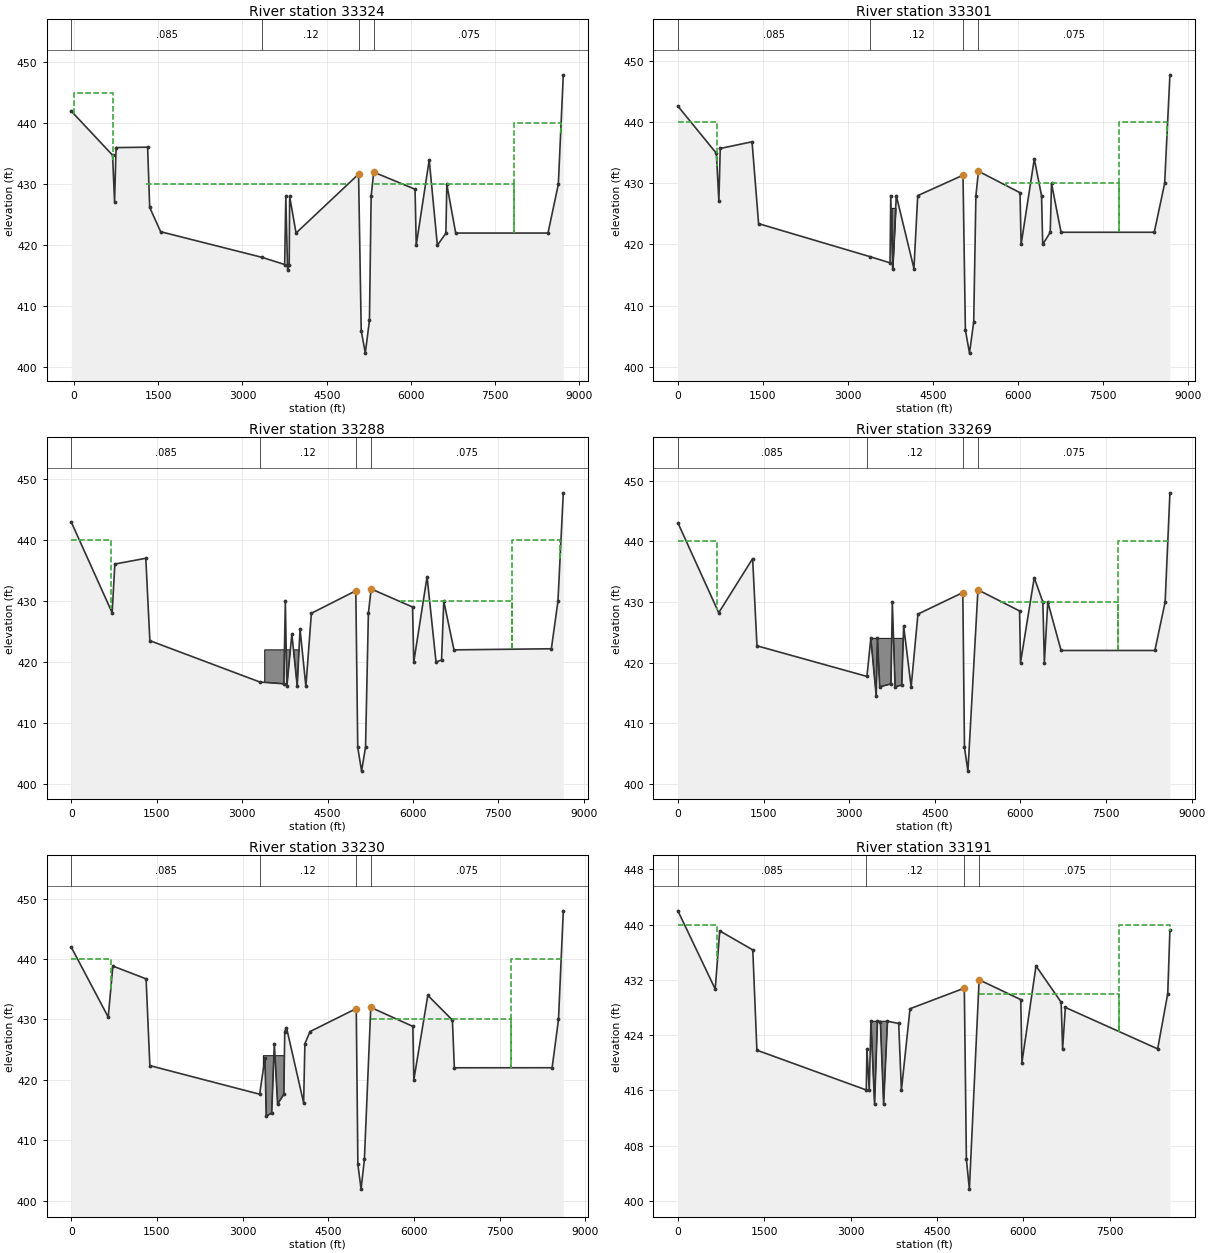
Type RM Length L Ch R = 1 ,33324   ,57,23,13
BEGIN DESCRIPTION:
This cross section corresponds to cross section 33335 of the non-georeferenced CDC model which was the source of this model.
END DESCRIPTION:
XS GIS Cut Line= 6
2438404.312439446971980.21623686  2438437.076573 6970272.2472047
 2438395.8440439 6969130.7540808 2438688.8126181 6967524.8511246
  2439284.515823 6966668.7314458 2440320.4317302 6963618.9268499
#Sta/Elev= 30
     -50     442  685.59  434.78  721.21  427.12  748.19  436.02 1310.33  436.09
 1346.95  426.21 1542.07  422.22 3354.07     418 3751.43  416.84 3771.72     428
 3803.44     416  3832.1   416.7 3840.67     428    3954     422 5068.05  431.67
 5115.05     406    5188   402.3 5261.81   407.7 5291.99     428 5337.17     432
 6074.34  429.19 6095.09     420 6326.51     434 6471.56     420 6623.51  421.96
 6640.13     430 6798.23     422 8442.34     422 8626.45     430 8714.93  447.96
#Mann= 4 ,-1,0
     -50    .085       0 3354.07     .12       0 5068.05    .055       0
 5337.17    .075       0
#XS Ineff= 4 ,-1
     -.5     690     445    1288    4867     430    5337    7840     430
    7840    8667     440
Permanent Ineff=
       T       F       F       F
Bank Sta=5068.05,5337.17
XS Rating Curve= 0 ,0
Exp/Cntr=0.3,0.1

Type RM Length L Ch R = 1 ,33301   ,34,13,9
BEGIN DESCRIPTION:
This cross section corresponds to cross section 33313 of the non-georeferenced CDC model which was the source of this model.
END DESCRIPTION:
XS GIS Cut Line= 6
  2438449.083438 6971937.8288472 2438492.4862391 6970352.5423197
 2438502.2519676 6969218.6446531  2438747.477527 6967524.8511246
 2439295.4377172 6966671.9866886 2440324.8431387 6963618.9268499
#Sta/Elev= 30
       0  442.66  678.57  434.94  722.84  427.09  747.05  435.73 1307.99  436.82
 1423.46  423.41 3390.11     418 3742.22  416.99  3754.7     428 3788.34     416
 3852.63     428 4163.98  416.06 4230.62     428 5029.25  431.35 5071.39     406
    5144   402.2  5217.9   407.3 5256.99     428 5302.07     432 6034.87  428.48
 6054.32     420 6286.96     434 6414.76     428 6435.46     420 6568.16  421.99
  6590.6     430 6758.66     422 8403.08     422 8586.15     430 8679.42  447.79
#Mann= 4 ,-1,0
       0    .085       0 3390.11     .12       0 5029.25    .055       0
 5302.07    .075       0
#XS Ineff= 4 ,-1
       0     690     440    1325    4795     430    5795    7789     430
    7789    8627     440
Permanent Ineff=
       T       F       F       F
#Block Obstruct= 1 ,-1
    3770    3839     426
Bank Sta=5029.25,5302.07
XS Rating Curve= 0 ,0
Exp/Cntr=0.3,0.1

Type RM Length L Ch R = 1 ,33288   ,29,18,17
BEGIN DESCRIPTION:
This cross section corresponds to cross section 33294 of the non-georeferenced CDC model which was the source of this model.
END DESCRIPTION:
XS GIS Cut Line= 6
  2438466.397708 6971932.2832547 2438536.9011765 6969172.1270296
 2438759.4706132 6967536.5367968  2439181.315242 6966872.0099106
 2439316.3395782  6966666.023446 2440325.2043584 6963620.2086715
#Sta/Elev= 30
       0  442.98   717.8  428.09   765.3  436.08 1308.83  437.03 1380.07  423.51
  3310.3  416.73 3732.68  416.43 3759.42     430 3786.24     416 3874.24   424.6
  3967.7  416.06 4017.49  425.41  4120.3     416 4216.51     428 4996.94   431.7
 5030.93     406  5098.5   402.1 5167.67  406.06 5217.83     428  5266.5     432
 5993.88  429.03 6014.47     420 6248.52     434 6405.88     420 6502.63  420.34
 6541.85     430 6720.75     422 8431.15  422.18  8546.9     430 8640.66  447.77
#Mann= 4 ,-1,0
       0    .085       0  3310.3     .12       0 4996.94    .055       0
  5266.5    .075       0
#XS Ineff= 4 ,-1
       0     690     440    1322    4814     430    5795    7745     430
    7745    8582     440
Permanent Ineff=
       T       F       F       F
#Block Obstruct= 1 ,-1
    3398    4017     422
Bank Sta=4996.94,5266.5
XS Rating Curve= 0 ,0
Exp/Cntr=0.3,0.1

Type RM Length L Ch R = 1 ,33269   ,35,39,21
BEGIN DESCRIPTION:
This cross section corresponds to cross section 33267 of the non-georeferenced CDC model which was the source of this model.
END DESCRIPTION:
XS GIS Cut Line= 6
  2438482.626678 6971933.4085805 2438526.8975876 6970412.5753361
 2438571.1681683 6969087.0543651 2438774.2934182 6967542.7835035
 2439328.9806291  6966672.991936 2440325.7256828 6963620.6916101
#Sta/Elev= 30
       0  443.06  715.21  428.22 1309.13  437.15 1384.98  422.77 3311.17  417.72
 3379.19     424  3473.6  414.57 3495.88     424 3534.83     416 3732.06  416.49
    3756     430 3804.84     416  3921.5   416.3 3954.56     426 4085.74     416
  4204.4     428 4990.42  431.55 5019.67     406    5080   402.1 5255.59     432
 5984.58  428.52  6001.4     420 6241.36     434 6392.41     430 6418.87     420
  6478.8     430 6711.57     422 8354.55     422 8534.31     430 8618.13     448
#Mann= 4 ,-1,0
       0    .085       0 3311.17     .12       0 4990.42    .055       0
 5255.59    .075       0
#XS Ineff= 4 ,-1
       0     690     440    1301    4782     430    5645    7714     430
    7714    8580     440
Permanent Ineff=
       T       F       F       F
#Block Obstruct= 1 ,-1
    3378    3953     424
Bank Sta=4990.42,5255.59
XS Rating Curve= 0 ,0
Exp/Cntr=0.3,0.1

Type RM Length L Ch R = 1 ,33230   ,76,39,24
BEGIN DESCRIPTION:
This cross section corresponds to cross section 33220 of the non-georeferenced CDC model which was the source of this model.
END DESCRIPTION:
XS GIS Cut Line= 6
  2438532.237143 6971926.2183062 2438601.6815588 6969031.2532956
 2438801.3343747 6967542.5377691 2439387.2718511 6966661.4614472
 2440174.6144365 6964094.3209122 2440326.7896571 6963622.5708715
#Sta/Elev= 30
       0  441.98  647.03   430.4   728.1  438.85  1309.7  436.73 1375.63  422.36
 3297.73  417.62 3390.82  423.64 3412.93     414 3508.32  414.49 3554.53     426
 3611.89     416 3720.65  417.58 3737.11     428 3767.38  428.66 4067.54  416.19
 4089.48     426 4179.87     428 4988.64  431.81 5016.95     406    5073   401.9
 5130.83  406.81 5242.89     432 5979.18  428.86 5996.39     420 6241.17     434
 6671.55   429.9 6705.82     422 8417.35  422.01 8528.57     430 8612.74     448
#Mann= 4 ,-1,0
       0    .085       0 3297.73     .12       0 4988.64    .055       0
 5242.89    .075       0
#XS Ineff= 4 ,-1
       0     687     440    1320    4853     430    5243    7705     430
    7705    8573     440
Permanent Ineff=
       T       F       F       F
#Block Obstruct= 1 ,-1
    3362    3737     424
Bank Sta=4988.64,5242.89
XS Rating Curve= 0 ,0
Exp/Cntr=0.3,0.1

Type RM Length L Ch R = 1 ,33191   ,121,53,26
BEGIN DESCRIPTION:
This cross section corresponds to cross section 33188 of the non-georeferenced CDC model which was the source of this model.
END DESCRIPTION:
XS GIS Cut Line= 6
  2438555.120912 6971901.7966485 2438606.0217732 6970289.9338491
 2438627.7231733 6969083.3365247 2438857.7581463 6967542.5377691
 2439413.3134657 6966670.1422042 2440331.1514135 6963676.4437544
#Sta/Elev= 30
       0  441.98  647.84  430.66  726.52  439.08 1300.35  436.32 1371.67  421.81
  3271.2  416.05 3282.27     422 3321.97  416.01 3352.08     426 3414.85     414
 3465.11     426 3516.09  425.95    3572     414 3639.22     426 3833.73  425.68
 3880.52     416 4030.41  427.81 4973.02  430.79 5009.14     406    5061   401.7
 5230.03     432 5953.65  429.13 5973.27     420 6217.76     434 6654.42  428.75
 6679.69     422 6727.25     428 8329.99     422 8504.98     430 8542.89  439.24
#Mann= 4 ,-1,0
       0    .085       0  3271.2     .12       0 4973.02    .055       0
 5230.03    .075       0
#XS Ineff= 4 ,-1
       0     687     440    1320    4973     430    5230    7662     430
    7662    8542     440
Permanent Ineff=
       T       F       F       F
#Block Obstruct= 1 ,-1
    3352    3639     426
Bank Sta=4973.02,5230.03
XS Rating Curve= 0 ,0
Exp/Cntr=0.3,0.1

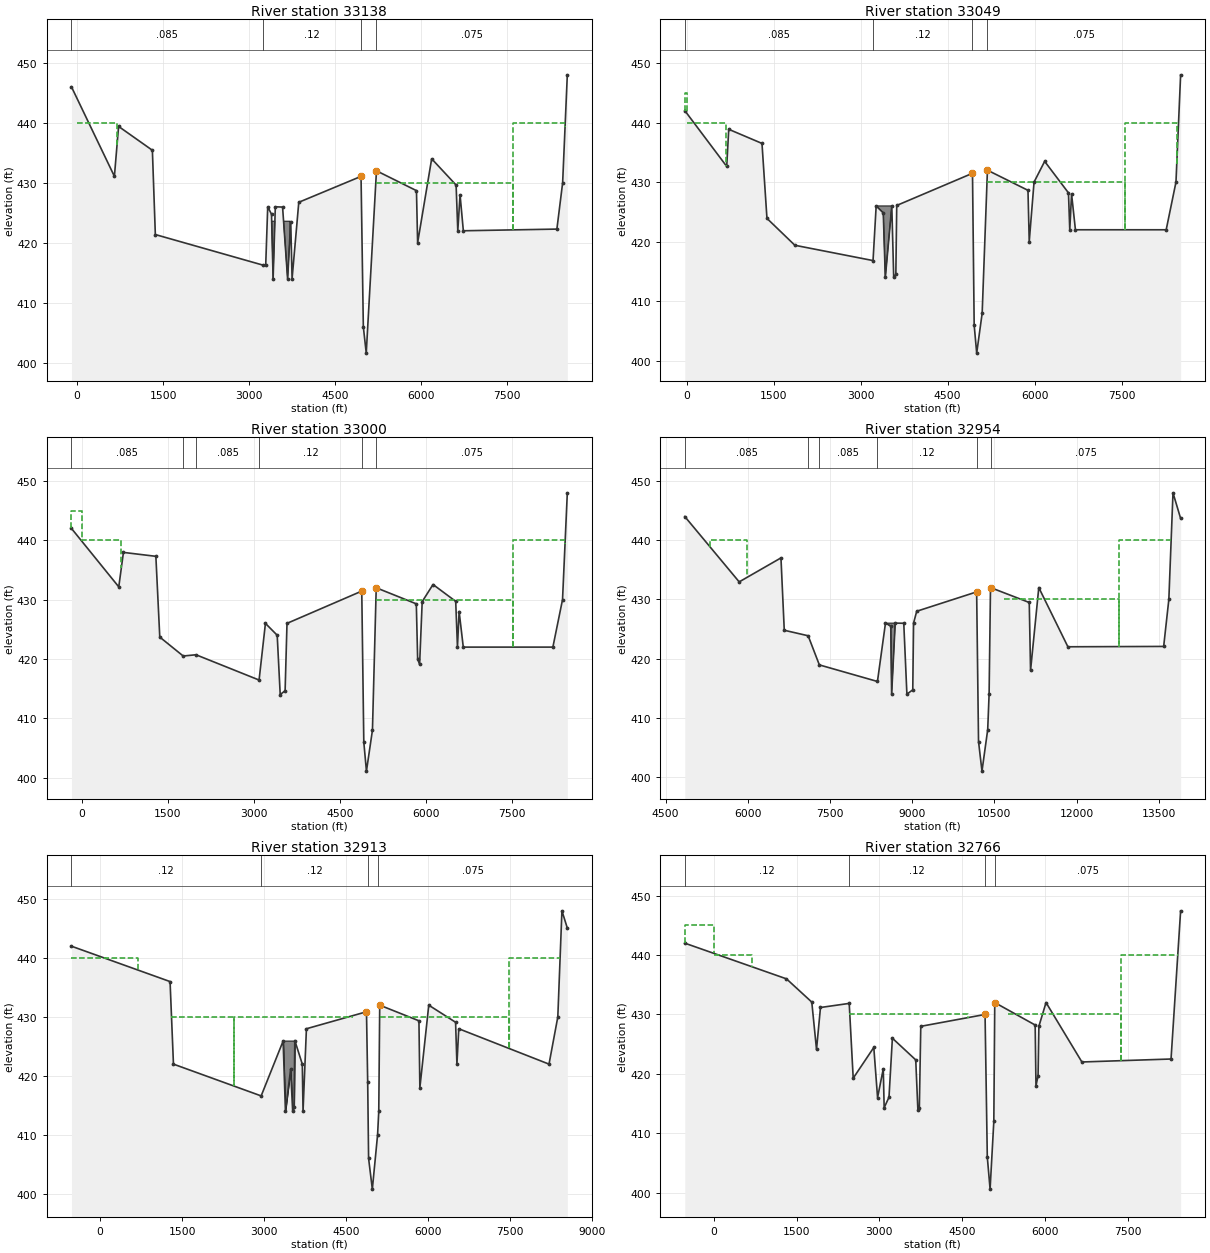
Type RM Length L Ch R = 1 ,33138   ,221,89,30
BEGIN DESCRIPTION:
This cross section corresponds to cross section 33136 of the non-georeferenced CDC model which was the source of this model.
END DESCRIPTION:
XS GIS Cut Line= 6
2438590.401429576972015.51360178 2438673.4770188 6969220.4169592
 2438767.2271594 6968512.0837302 2438941.7061412 6967577.1876342
 2439436.4978025 6966676.1461292 2440386.2980214  6963652.287014
#Sta/Elev= 30
    -100     446  649.96  431.08  722.97   439.4 1313.22  435.42 1364.85  421.37
 3241.53  416.28 3292.24  416.23 3327.43     426 3393.52  424.76 3421.65     414
 3460.22     426 3586.96  425.95 3674.75     414  3729.4  423.52 3752.83     414
  3869.9  426.75 4957.16  431.07 4997.22     406    5048   401.6 5226.59     432
 5924.98  428.69  5945.4     420 6190.62     434  6617.3  429.62 6646.77     422
 6686.18     428  6743.7     422 8377.38  422.28 8477.76     430 8559.47     448
#Mann= 4 ,-1,0
    -100    .085       0 3241.53     .12       0 4957.16    .055       0
 5226.59    .075       0
#XS Ineff= 4 ,-1
       0     693     440    1300    4815     430    5227    7618     430
    7618    8520     440
Permanent Ineff=
       T       F       F       F
#Block Obstruct= 1 ,-1
    3327    3717   423.6
Bank Sta=4957.16,5226.59
XS Rating Curve= 0 ,0
Exp/Cntr=0.3,0.1

Type RM Length L Ch R = 1 ,33049   ,196,49,21
BEGIN DESCRIPTION:
This cross section corresponds to cross section 33062 of the non-georeferenced CDC model which was the source of this model.
END DESCRIPTION:
XS GIS Cut Line= 6
2438644.562984596971946.22990404 2438699.5186334 6970095.4168496
 2438748.9978652 6969314.1670998 2439051.0812505 6967600.6252513
 2439478.1643858 6966699.5837463 2440390.0312769  6963658.915321
#Sta/Elev= 30
     -30     442  693.06  432.63  727.78  438.86 1301.06  436.49 1386.77  423.91
 1867.57   419.4 3215.26  416.83 3269.16     426 3391.74  424.83 3426.82     414
 3538.61  425.96 3571.63     414  3608.2  414.51 3623.64  426.08 4929.56  431.48
 4958.48     406    5002   401.3 5096.21     408 5187.05     432 5885.88  428.62
 5907.44     420 5990.47     430 6173.44  433.48 6583.87  428.19 6606.15     422
 6637.21     428 6703.77     422  8268.2     422 8436.84     430 8516.96     448
#Mann= 4 ,-1,0
     -30    .085       0 3215.26     .12       0 4929.56    .055       0
 5187.05    .075       0
#XS Ineff= 5 ,-1
       0     683     440    1300    4929     430    5187    7559     430
    7559    8450     440     -30       0     445
Permanent Ineff=
       T       F       F       F       F
#Block Obstruct= 1 ,-1
    3269 3533.41     426
Bank Sta=4929.56,5187.05
XS Rating Curve= 0 ,0
Exp/Cntr=0.3,0.1

Type RM Length L Ch R = 1 ,33000   ,58,45,23
BEGIN DESCRIPTION:
This cross section corresponds to cross section 33014 of the non-georeferenced CDC model which was the source of this model.
END DESCRIPTION:
XS GIS Cut Line= 6
      2438665.14     6971948.509 2438845.4033841 6971945.8300519
 2438840.1436802 6969725.6252664 2439012.0186646 6968353.2293892
  2439178.685326 6967561.5626654 2440395.8313012 6963661.4534976
#Sta/Elev= 30
    -182     442  643.82  432.15  724.93  437.96 1291.08   437.3 1359.37  423.69
 1768.05   420.5 1991.42  420.71 3092.42  416.45 3203.19     426 3408.66     424
 3461.08     414 3546.68  414.65 3579.51     426 4884.41  431.44 4919.89     406
    4966   401.1 5070.81     408 5136.79     432 5836.33  429.29 5859.65     420
 5893.81  419.08 5939.06  429.67 6127.95  432.55 6523.96  429.71  6554.5     422
 6583.38     428 6656.08     422 8219.81     422 8388.13     430 8471.68     448
#Mann= 6 ,-1,0
    -182    .085       0 1768.05    .065       0 1991.42    .085       0
 3092.42     .12       0 4884.41    .055       0 5136.79    .075       0
#XS Ineff= 5 ,-1
       0     688     440    1300    4884     430    5137    7516     430
    7516    8432     440    -182       0     445
Permanent Ineff=
       T       F       F       F       F
Bank Sta=4884.41,5136.79
XS Rating Curve= 0 ,0
Exp/Cntr=0.3,0.1

Type RM Length L Ch R = 1 ,32954   ,46,41,52
BEGIN DESCRIPTION:
This cross section corresponds to cross section 32967 of the non-georeferenced CDC model which was the source of this model.
END DESCRIPTION:
XS GIS Cut Line= 6
2438854.218760676972396.93526111 2438900.0395578 6970957.3960968
 2438905.2478808 6969452.1878212 2439173.4770031 6967777.7085586
 2439514.6229743 6966785.5212385 2440441.6494056 6963559.0698902
#Sta/Elev= 30
    4850     444 5842.93  432.96 6605.26  437.01 6665.52  424.79 7101.22  423.86
 7305.64  418.94 8365.91  416.14 8512.22     426 8609.06  425.49 8624.53     414
 8689.68     426    8846  425.97 8903.09     414  9010.2  414.73 9024.68     426
 9082.24     42810175.69  431.2710210.15     406   10273     40110377.47     408
10403.06     41410428.55     43211135.59  429.48 11159.4     41811309.65     432
11840.67     42213588.32  422.0613682.71     43013758.38     44813897.58  443.68
#Mann= 6 ,-1,0
    4850    .085       0 7101.22    .065       0 7305.64    .085       0
 8365.91     .12       010175.69    .055       010428.55    .075       0
#XS Ineff= 4 ,-1
    5308    5983     440   12779   13731     440    6610    9837     430
   10683   12779     430
Permanent Ineff=
       T       F       F       F
#Block Obstruct= 1 ,-1
    8512    8689     426
Bank Sta=10175.69,10428.55
XS Rating Curve= 0 ,0
Exp/Cntr=0.3,0.1

Type RM Length L Ch R = 1 ,32913   ,134,147,196
BEGIN DESCRIPTION:
This cross section corresponds to cross section 32919 of the non-georeferenced CDC model which was the source of this model.
END DESCRIPTION:
XS GIS Cut Line= 6
2438972.929437126972460.76498729 2438975.5604042 6970621.4584485
 2439012.0186646 6969439.1668498  2439212.539589 6967803.7501732
  2439597.956141  6966652.708512 2440465.1437111 6963577.1877601
#Sta/Elev= 30
    -525     442    1279     436    1341     422 2945.45  416.61 3347.44  425.92
 3389.73     414 3484.52  421.11 3522.11     414 3548.44   414.8 3561.24     426
 3698.19     422  3711.7     414 3773.53     428 4872.32  430.88  4894.5  418.94
 4911.08     406  4979.5   400.8 5075.35     410 5097.11     414 5114.63     432
 5831.98  429.35 5849.12     418 6011.78     432 6502.42   429.1 6526.95     422
 6560.82     428 8211.74     422 8372.67     430 8448.03     448 8546.57  445.08
#Mann= 4 ,-1,0
    -525     .12       0 2945.45     .12       0  4894.5    .055       0
 5075.35    .075       0
#XS Ineff= 5 ,-1
    -525     693     440    5114    7482     430    7482    8415     440
    2453    4633     430    1300    2453     430
Permanent Ineff=
       T       F       F       F       T
#Block Obstruct= 1 ,-1
    3347    3561     426
Bank Sta=4872.32,5114.63
XS Rating Curve= 0 ,0
Exp/Cntr=0.3,0.1

Type RM Length L Ch R = 1 ,32766   ,176,103,118
BEGIN DESCRIPTION:
This cross section corresponds to cross section 32814 of the non-georeferenced CDC model which was the source of this model.
END DESCRIPTION:
XS GIS Cut Line= 6
 2439014.77803796972486.83075892 2439069.3102167 6971483.4380237
 2439069.3102167 6969501.6670529 2439254.2061723 6968173.5420845
 2439592.7478181 6967178.7504389 2440522.4352632 6963657.9169294
#Sta/Elev= 30
    -525     442 1317.69  435.99 1776.04  432.08 1861.67  424.11 1933.43  431.17
 2453.98  431.86 2526.28  419.27 2899.42  424.45 2967.76     416 3070.86  420.84
 3087.14   414.3 3174.71  416.07 3236.11     426 3659.15  422.35 3697.63     414
  3724.3  414.18 3750.49     428 4914.83     430 4955.55     406 5005.95   400.6
 5073.61     412 5090.65     432 5822.57  428.22 5837.23     418 5874.99  419.67
 5889.75     428 6019.54     432 6668.99     422 8283.91   422.5 8457.54  447.44
#Mann= 4 ,-1,0
    -525     .12       0 2453.98     .12       0 4914.83    .055       0
 5090.65    .075       0
#XS Ineff= 6 ,-1
       0     692     440 2453.98    4614     430    5322    7377     430
    7377    8408     440    1300 2453.98  431.86    -525       0     445
Permanent Ineff=
       T       F       F       F       T       F
Bank Sta=4914.83,5090.65
XS Rating Curve= 0 ,0
Exp/Cntr=0.3,0.1