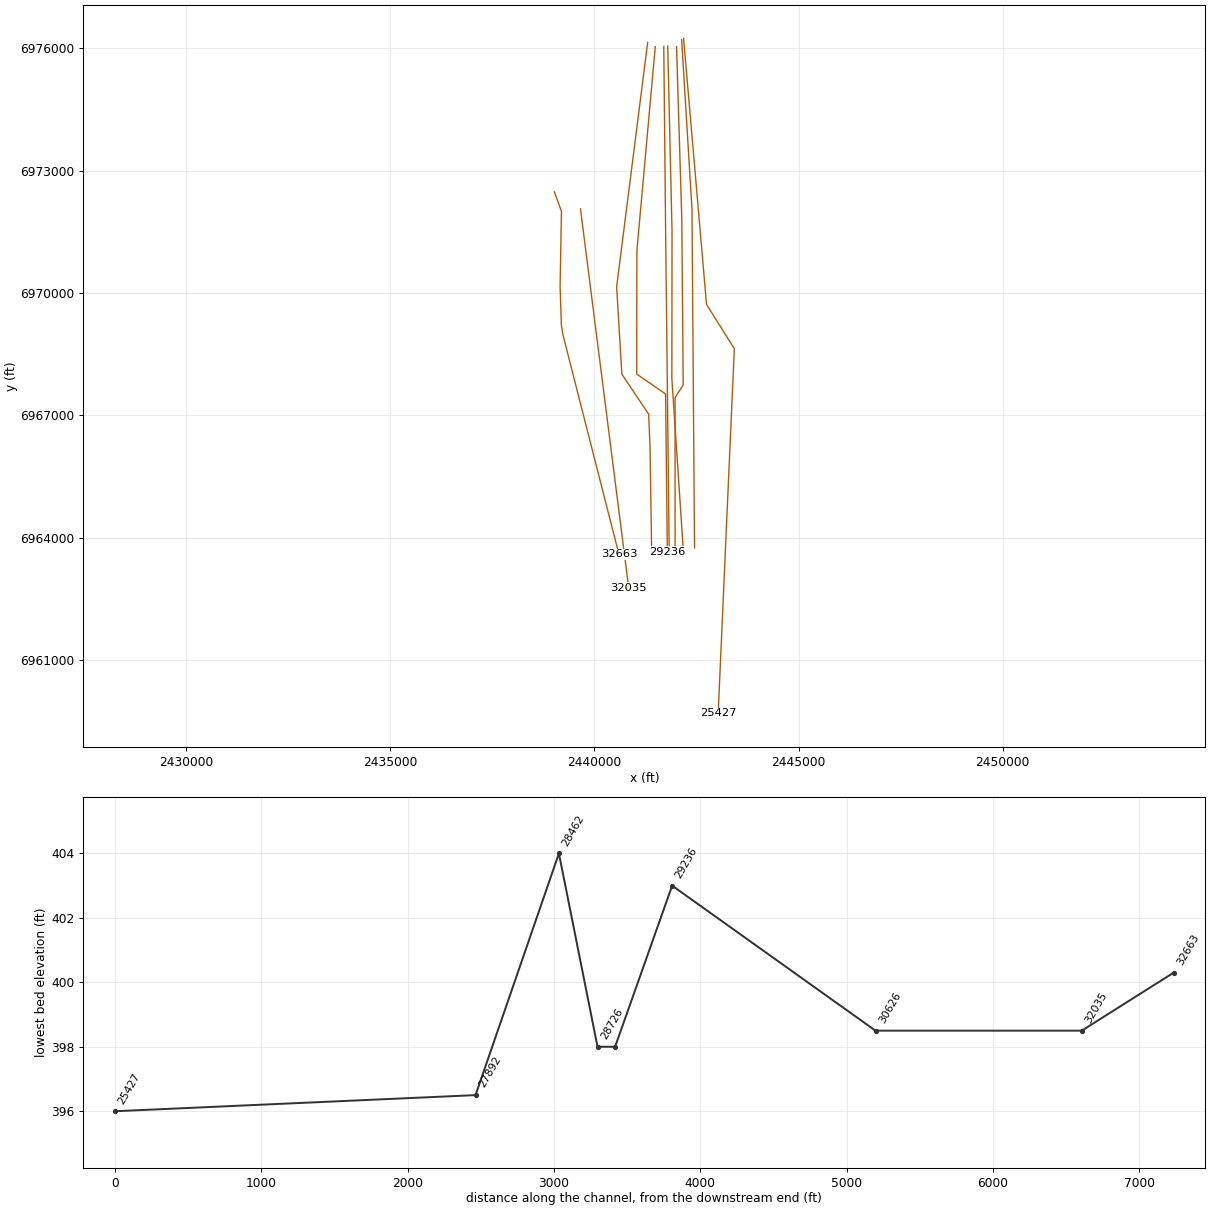
HEC-RAS study CDC_Consolidated_Model.prj: Upper Trinity CDC Consolidated Model

--- CDC_Consolidated_Model.g04 (geometry) --- (continued)

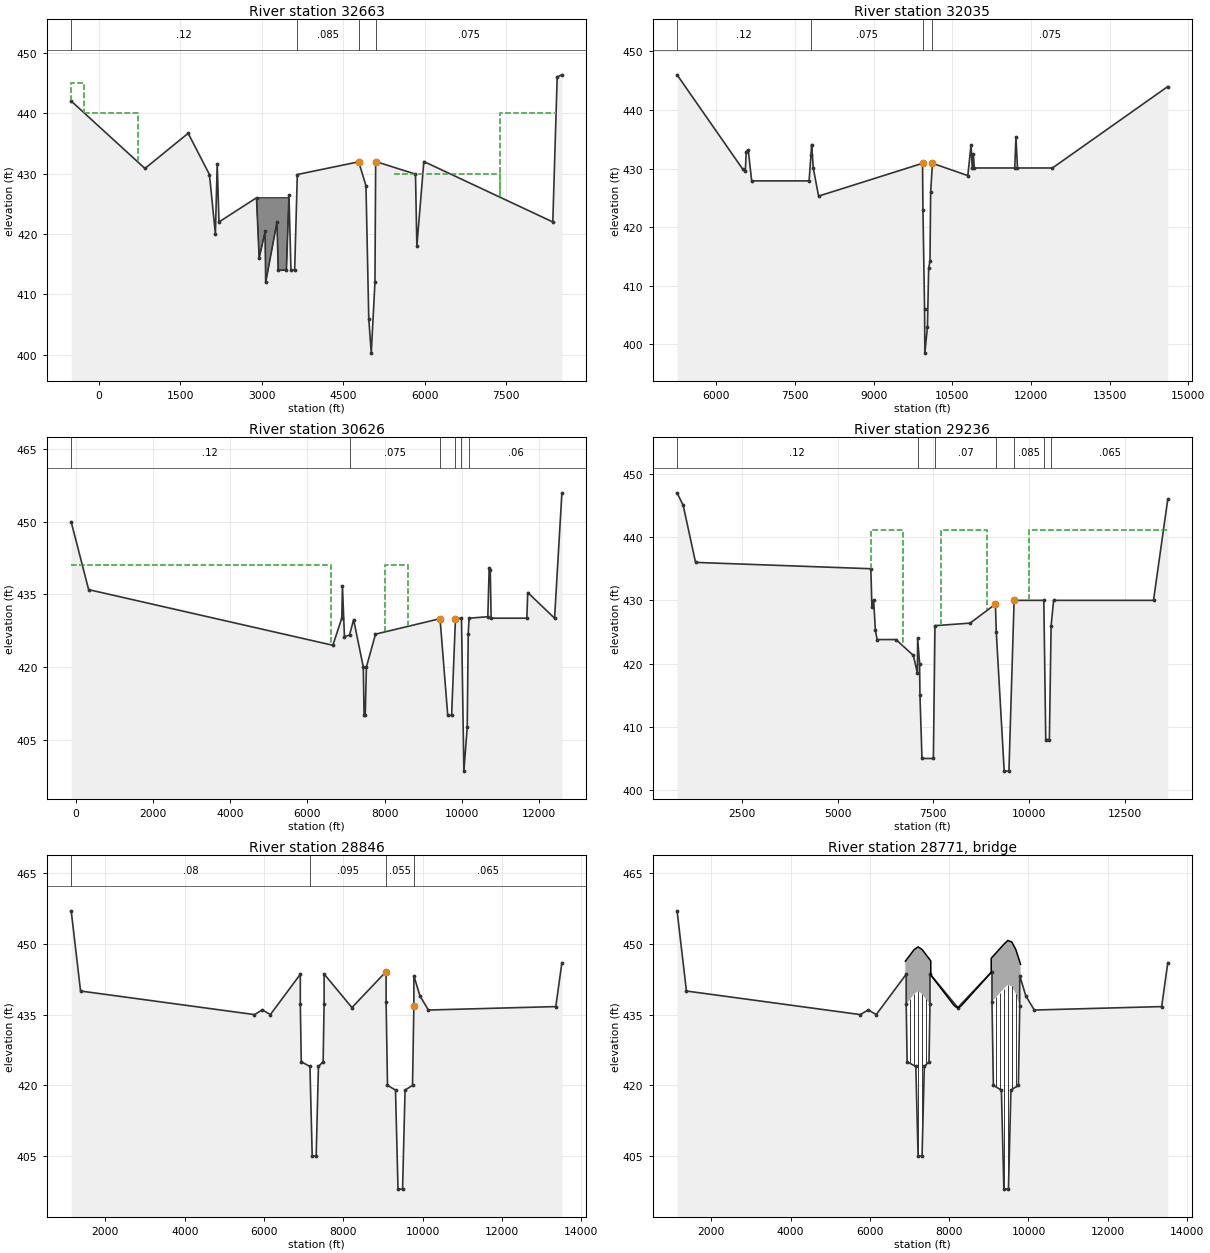
Type RM Length L Ch R = 1 ,32663   ,776,628,455
BEGIN DESCRIPTION:
This cross section corresponds to cross section 32718 of the non-georeferenced CDC model which was the source of this model.
END DESCRIPTION:
XS GIS Cut Line= 6
      2439018.98      6972477.57 2439192.3162043 6971998.1794483
 2439159.3300498 6970154.1401574 2439189.7122068 6969225.3204927
 2439228.7744647 6968973.5844477 2440599.9662976 6963593.9700993
#Sta/Elev= 30
    -509     442  849.46  430.85 1645.33  436.67  2037.3  429.85  2146.9  420.04
 2180.41  431.63 2213.04     422  2904.5     426 2953.14     416 3062.87  420.43
 3073.18     412 3282.16     422 3304.16     414  3454.8  414.03 3502.41  426.43
 3539.08     414 3607.21  414.05 3656.02  429.85 4786.47  431.95 4920.76     428
 4972.12     406    5018   400.3  5086.1     412 5099.32     432 5832.82  429.91
  5857.9     418 5986.64     432 8361.98     422 8442.62     446 8529.56  446.34
#Mann= 4 ,-1,0
    -509     .12       0 3656.02    .085       0 4786.47    .055       0
 5099.32    .075       0
#XS Ineff= 5 ,-1
    1874    4500     430    5432    7383     430    7383    8423     440
    -274     725     440    -509    -274     445
Permanent Ineff=
       F       F       F       F       F
#Block Obstruct= 1 ,-1
    2904    3503     426
Bank Sta=4786.47,5099.32
XS Rating Curve= 0 ,0
Exp/Cntr=0.3,0.1

Type RM Length L Ch R = 1 ,32035   ,3250,1410,783
BEGIN DESCRIPTION:
This cross section corresponds to cross section 32042 of the non-georeferenced CDC model which was the source of this model.
END DESCRIPTION:
XS GIS Cut Line= 6
2439658.527059786972060.99871692 2439938.8406298 6969855.1692987
  2440179.903796  6967958.402751 2440408.3026174 6966161.4683527
 2440560.5811842 6964963.5130715 2440839.11548416962772.23042939
#Sta/Elev= 30
    5250     446    6502   429.9    6552   429.6    6569   432.9    6607   433.2
    6673   427.9    7768   427.9    7805   432.4    7816   434.1    7848   430.1
    7949   425.3    9932   430.9    9940   422.9    9971     406    9976   398.5
   10026     403   10049     413   10074   414.2   10087     426   10121   430.9
   10796   428.8   10857     434   10881   430.1   10902   432.5   10919   430.1
   11691   430.1   11714   435.4   11743   430.1   12410   430.1   14610     444
#Mann= 4 ,-1,0
    5250     .12       0    7805    .075       0    9932    .055       0
   10121    .075       0
Bank Sta=9932,10121
XS Rating Curve= 0 ,0
Exp/Cntr=0.3,0.1

Type RM Length L Ch R = 1 ,30626   ,881,1390,1762
BEGIN DESCRIPTION:
This cross section corresponds to cross section 31471 of the non-georeferenced CDC model which was the source of this model.
END DESCRIPTION:
XS GIS Cut Line= 6
     2441304.614      6976140.39 2440544.5814227 6970150.1791222
 2440672.5176402 6968008.9325056 2441328.7016952 6967027.2966736
 2441361.8945423  6966244.823501 2441401.8879891 6963659.1551386
#Sta/Elev= 30
    -125     450     327     436    6660   424.5    6892   430.1    6909   436.8
    6961   426.3    7092   426.6    7199   429.8    7450     420    7470     410
    7500     410    7530     420    7766   426.8    9440     430    9640     410
    9740     410    9840     430    9996   430.1   10058   398.5   10145   407.6
   10171   426.9   10193   430.1   10679   430.4   10714   440.4   10742   440.1
   10765   430.1   11691   430.1   11714   435.4   12410   430.1   12600     456
#Mann= 6 ,-1,0
    -125     .12       0    7092    .075       0    9440    .055       0
    9840    .075       0    9996    .055       0   10193     .06       0
#XS Ineff= 2 ,-1
    -125    6600  441.15    8000    8600  441.15
Permanent Ineff=
       F       F
Bank Sta=9440,9840
XS Rating Curve= 0 ,0
Exp/Cntr=0.3,0.1

Type RM Length L Ch R = 1 ,29236   ,390,390,390
BEGIN DESCRIPTION:
This cross section corresponds to cross section 29040 of the non-georeferenced CDC model which was the source of this model.
END DESCRIPTION:
XS GIS Cut Line= 6
     2441490.812     6976037.525 2441040.2742875 6971030.8631456
 2441035.6173077 6968011.3668839 2441427.7700667 6967740.2296309
 2441743.5768497 6967521.8783616 2441785.6132057 6963652.5172093
#Sta/Elev= 30
     817     447     977     445    1299     436    5870     435    5897   428.9
    5941   430.1    5988   425.3    6033   423.8    6525   423.8    6978   421.3
    7083   418.5    7090     424    7140     420    7150     415    7203     405
    7500     405    7542     426    8458   426.4    9118   429.4    9140     425
    9347     403    9470     403    9605     430   10380     430   10430     408
   10525     408   10570     426   10635     430   13240     430   13612     446
#Mann= 7 ,-1,0
     817     .12       0    7090    .055       0    7542     .07       0
    9140    .055       0    9605    .085       0   10380    .055       0
   10570    .065       0
#XS Ineff= 3 ,-1
    5870    6700  441.15    7700    8900  441.15   10000   13612  441.15
Permanent Ineff=
       F       F       F
Bank Sta=9118,9605
XS Rating Curve= 0 ,0
Exp/Cntr=0.3,0.1

Type RM Length L Ch R = 1 ,28846   ,120,120,120
BEGIN DESCRIPTION:
This cross section corresponds to cross section 28841 of the non-georeferenced CDC model which was the source of this model.
Upstream bounding cross section for meyers Road/MacArthur Blvd bridge (West Fork Trinity River and Bear Creek bridges modeled).
END DESCRIPTION:
XS GIS Cut Line= 6
     2441699.145      6976044.47  2441744.505981 6971501.2473713
 2441768.6063272 6969341.9049052  2441793.243089 6967134.3607639
 2441795.3976122 6966941.3316224 2441831.9126051 6963667.7350793
#Sta/Elev= 30
    1137     457    1373     440    5760     435    5960     436    6160     435
    6916  443.55    6916  437.15    6940     425    7159     424    7216     405
    7316     405    7373     424  7491.6     425    7516  437.21    7516  443.61
    8218  436.49    9080  444.13    9080  437.72    9115     420    9317     419
    9380     398    9495     398    9558     419    9746     420    9780  436.83
    9780  443.24    9935  438.93   10147  435.97   13360   436.7   13514     446
#Mann= 4 ,-1,0
    1137     .08       0    7159    .095       0    9080    .055       0
    9780    .065       0
#XS Ineff= 2 , 0
       0    5680           10300       0
Permanent Ineff=
       F       F
Bank Sta=9080,9780
XS Rating Curve= 0 ,0
Exp/Cntr=0.3,0.1

Type RM Length L Ch R = 3 ,28771   ,,,
BEGIN DESCRIPTION:
Meyers Road/MacArthur Boulevard
---------------------------------------
CDC DC040803-1 Meyers Road
---------------------------------------
END DESCRIPTION:
Node Name=Meyers Road
Bridge Culvert--1,0,-1,-1, 0
Deck Dist Width WeirC Skew NumUp NumDn MinLoCord MaxHiCord MaxSubmerge Is_Ogee
1,90,2.6,0, 26, 26, , , 0.95, 0, 0,0,,
    6896    6916    7016    7116    7216    7316    7416    7516    7536    7536
    8110    8160    8218    8260    8310    9060    9060    9080    9180    9280
    9380    9480    9580    9680    9780    9800
  446.32  446.55  447.66  448.78  449.36   448.8   447.7  446.61  446.39  443.39
  437.08  436.66  436.49  436.58  436.92  443.94  446.94  447.13  448.05  448.99
  449.92  450.71   450.4  448.82  446.23  445.67
  437.15  437.15  438.26  439.38  439.96   439.4   438.3  437.21  437.21  443.39
  437.08  436.66  436.49  436.58  436.92  443.94  437.72  437.72  438.65  439.59
  440.52  441.31     441  439.42  436.83  436.83
    6896    6916    7016    7116    7216    7316    7416    7516    7536    7536
    8110    8160    8218    8260    8310    9060    9060    9080    9180    9280
    9380    9480    9580    9680    9780    9800
  446.32  446.55  447.66  448.78  449.36   448.8   447.7  446.61  446.39  443.39
  437.08  436.66  436.49  436.58  436.92  443.94  446.94  447.13  448.05  448.99
  449.92  450.71   450.4  448.82  446.23  445.67
  437.15  437.15  438.26  439.38  439.96   439.4   438.3  437.21  437.21  443.39
  437.08  436.66  436.49  436.58  436.92  443.94  437.72  437.72  438.65  439.59
  440.52  441.31     441  439.42  436.83  436.83
Pier Skew, UpSta & Num, DnSta & Num=  ,7016, 2 ,7016, 2 , 0 , 0 , 0 ,,
       3       3
     400     440
       3       3
     400     440
Pier Skew, UpSta & Num, DnSta & Num=  ,7116, 2 ,7116, 2 , 0 , 0 , 0 ,,
       3       3
     400     440
       3       3
     400     440
Pier Skew, UpSta & Num, DnSta & Num=  ,7216, 2 ,7216, 2 , 0 , 0 , 0 ,,
       4       4
     400     440
       4       4
     400     440
Pier Skew, UpSta & Num, DnSta & Num=  ,7316, 2 ,7316, 2 , 0 , 0 , 0 ,,
       4       4
     400     440
       4       4
     400     440
Pier Skew, UpSta & Num, DnSta & Num=  ,7416, 2 ,7416, 2 , 0 , 0 , 0 ,,
       3       3
     400     440
       3       3
     400     440
Pier Skew, UpSta & Num, DnSta & Num=  ,9180, 2 ,9180, 2 , 0 , 0 , 0 ,,
       3       3
     390     445
       3       3
     390     445
Pier Skew, UpSta & Num, DnSta & Num=  ,9280, 2 ,9280, 2 , 0 , 0 , 0 ,,
       3       3
     390     445
       3       3
     390     445
Pier Skew, UpSta & Num, DnSta & Num=  ,9380, 2 ,9380, 2 , 0 , 0 , 0 ,,
       4       4
     390     445
       4       4
     390     445
Pier Skew, UpSta & Num, DnSta & Num=  ,9480, 2 ,9480, 2 , 0 , 0 , 0 ,,
       4       4
     390     445
       4       4
     390     445
Pier Skew, UpSta & Num, DnSta & Num=  ,9580, 2 ,9580, 2 , 0 , 0 , 0 ,,
       3       3
     390     445
       3       3
     390     445
Pier Skew, UpSta & Num, DnSta & Num=  ,9680, 2 ,9680, 2 , 0 , 0 , 0 ,,
       3       3
     390     445
       3       3
     390     445
BR Coef=-1 , 0 , 0 ,, 0 ,,,0.8,-1,,1,
WSPro=,,,, 1 ,,,, 0 ,,,, 0 ,,,,-1 ,-1 ,-1 , 0 , 0 , 0 , 0 , 0
BR Coef=-1 , 0 , 0 ,, 0 ,,,0.8,-1,,1,
WSPro=,,,, 1 ,,,, 0 ,,,, 0 ,,,,-1 ,-1 ,-1 , 0 , 0 , 0 , 0 , 0
BR Coef=-1 , 0 , 0 ,, 0 ,,,0.8,-1,,1,
WSPro=,,,, 1 ,,,, 0 ,,,, 0 ,,,,-1 ,-1 ,-1 , 0 , 0 , 0 , 0 , 0
BR Coef=-1 , 0 , 0 ,, 0 ,,,0.8,-1,,1,
WSPro=,,,, 1 ,,,, 0 ,,,, 0 ,,,,-1 ,-1 ,-1 , 0 , 0 , 0 , 0 , 0
BC Design=,, 0 ,, 0 ,,,,,,
BC HTab HWMax=444.13
BC Use User HTab Curves=0
BC User HTab FreeFlow(D)= 0

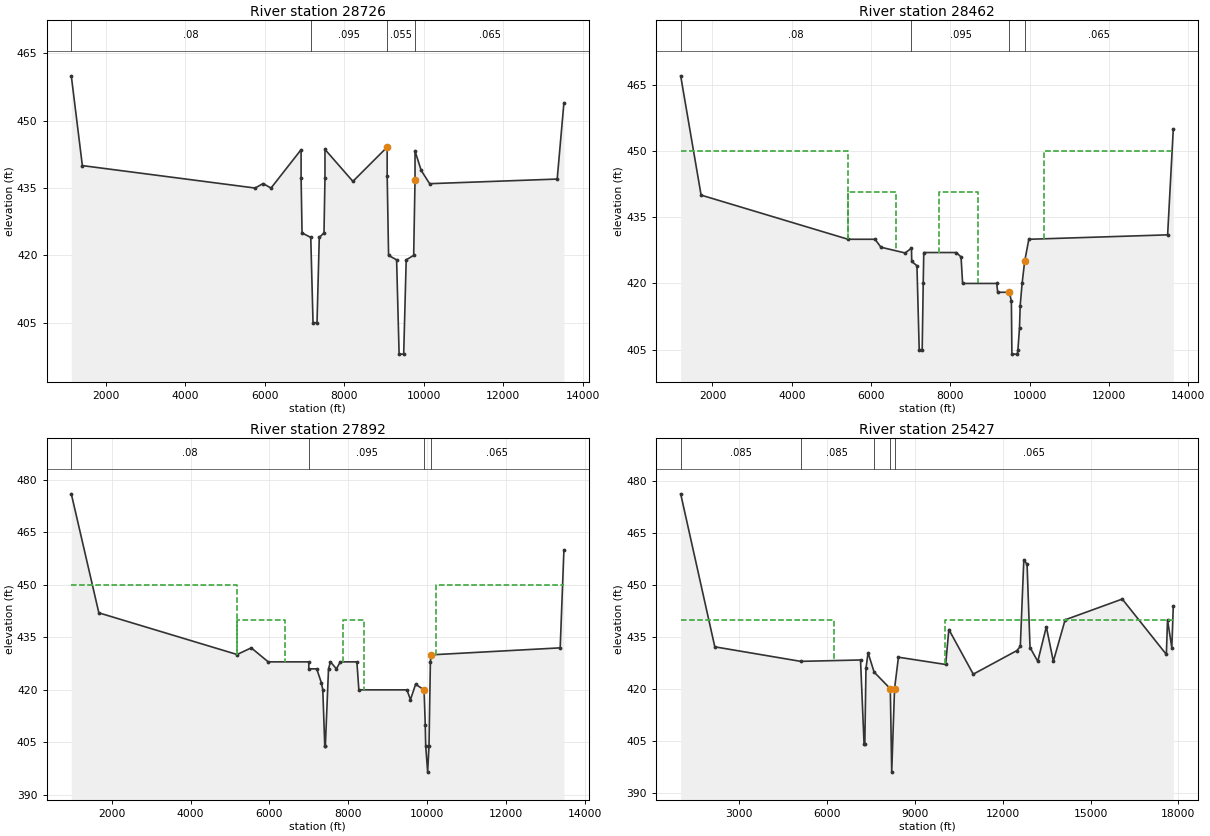
Type RM Length L Ch R = 1 ,28726   ,265,264,80
BEGIN DESCRIPTION:
This cross section corresponds to cross section 28749 of the non-georeferenced CDC model which was the source of this model.
Downstream bounding cross-section for Meyers Road/MacArthur Blvd bridge (West Fork Trinity River and Bear Creek bridges modeled).
END DESCRIPTION:
XS GIS Cut Line= 6
     2441796.368     6976051.414  2441901.458751 6971510.9005672
 2441899.2107248 6969683.3090781 2441897.0138788 6967899.9330517
  2441963.557709 6966902.5570937 2442178.6922069 6963677.6408459
#Sta/Elev= 30
    1139     460    1417     440    5760     435    5960     436    6160     435
    6916  443.55    6916  437.15    6940     425    7159     424    7216     405
    7316     405    7373     424  7491.6     425    7516  437.21    7516  443.61
    8218  436.49    9080  444.13    9080  437.72    9115     420    9317     419
    9380     398    9495     398    9558     419    9746     420    9780  436.83
    9780  443.24    9935  438.93   10147  435.97   13354     437   13523     454
#Mann= 4 ,-1,0
    1139     .08       0    7159    .095       0    9080    .055       0
    9780    .065       0
#XS Ineff= 2 , 0
       0    5680           10300       0
Permanent Ineff=
       F       F
Bank Sta=9080,9780
XS Rating Curve= 0 ,0
Exp/Cntr=0.3,0.1

Type RM Length L Ch R = 1 ,28462   ,442,570,241
BEGIN DESCRIPTION:
This cross section corresponds to cross section 28450 of the non-georeferenced CDC model which was the source of this model.
END DESCRIPTION:
XS GIS Cut Line= 6
     2442011.645     6976037.525  2442140.807833 6971816.5667829
 2442159.2472782 6969630.3101683 2442175.1340575 6967746.4979911
 2441975.8631306 6967431.0950786 2441975.8631306 6963672.2279581
#Sta/Elev= 30
    1198     467    1713     440    5420     430    6100     430    6250   428.2
    6860   426.9    7020     428    7026     425    7158     424    7215     405
    7290     405    7316     420    7330     427    8150     427    8270     426
    8310     420    9170     420    9195     418    9490     418    9540     416
    9553     404    9690     404    9705     405    9745     410    9762     415
    9810     420    9875     425    9980     430   13481     431   13624     455
#Mann= 4 ,-1,0
    1198     .08       0    7020    .095       0    9490    .055       0
    9875    .065       0
#XS Ineff= 4 ,-1
    5420    6640   440.6    7720    8700   440.6   10360   13624     450
    1198    5420     450
Permanent Ineff=
       F       F       F       F
Bank Sta=9490,9875
XS Rating Curve= 0 ,0
Exp/Cntr=0.3,0.1

Type RM Length L Ch R = 1 ,27892   ,302,2464,1208
BEGIN DESCRIPTION:
This cross section corresponds to cross section 27882 of the non-georeferenced CDC model which was the source of this model.
END DESCRIPTION:
XS GIS Cut Line= 6
     2442136.645     6976211.137  2442390.208591 6972055.5217222
 2442403.7139809 6970257.8112099 2442415.6841013 6968664.2914311
 2442420.1726094  6968066.721432 2442452.6118165 6963747.6683451
#Sta/Elev= 30
     973     476    1672     442    5180   430.1    5540     432    5970     428
    7000     428    7000     426    7200     426    7320     422    7355     420
    7405     404    7420     404    7500     426    7550     428    7700     426
    7800     428    8220     428    8270     420    9490     420    9580   417.2
    9710   421.6    9925     420    9955     410    9966     404   10016   396.5
   10050     404   10085     428   10099     430   13379     432 13473.6     460
#Mann= 4 ,-1,0
     973     .08       0    7000    .095       0    9925    .055       0
   10099    .065       0
#XS Ineff= 4 ,-1
    5180    6400     440    7870    8400     440   10232 13473.6     450
     973    5180     450
Permanent Ineff=
       F       F       F       F
Bank Sta=9925,10099
XS Rating Curve= 0 ,0
Exp/Cntr=0.3,0.1

Type RM Length L Ch R = 1 ,25427   ,659,551,100
BEGIN DESCRIPTION:
This cross section corresponds to cross section 25434 of the non-georeferenced CDC model which was the source of this model.
LOMR # 16-06-1120P reflected in ROB as inneffective flow area.
END DESCRIPTION:
XS GIS Cut Line= 6
  2442184.330413 6976241.3780159 2442600.5111595  6971410.458839
 2442746.2710386 6969718.6390599 2443087.0049372 6969175.5358154
 2443427.7503187 6968632.43650792443032.110400466959692.26328079
#Sta/Elev= 30
    1000   476.4    2166   432.2    5100     428    7144   428.4    7265     404
    7290     404    7330     426    7401   430.5    7608   424.9    8161   420.1
    8209     396    8306   420.1    8439   429.2   10052   427.1   10161   437.2
   10995   424.3   12482   431.1   12602   432.3   12722   457.4   12833     456
   12934     432   13199     428   13491     438   13730     428   14133     440
   16085     446   17591     430   17631     440   17777     432   17828     444
#Mann= 5 ,-1,0
    1000    .085       0    5100    .085       0    7608    .095       0
    8161    .055       0    8306    .065       0
#XS Ineff= 2 , 0
       0    6250     440   10040       0     440
Permanent Ineff=
       F       F
Bank Sta=8161,8306
XS Rating Curve= 0 ,0
Exp/Cntr=0.3,0.1