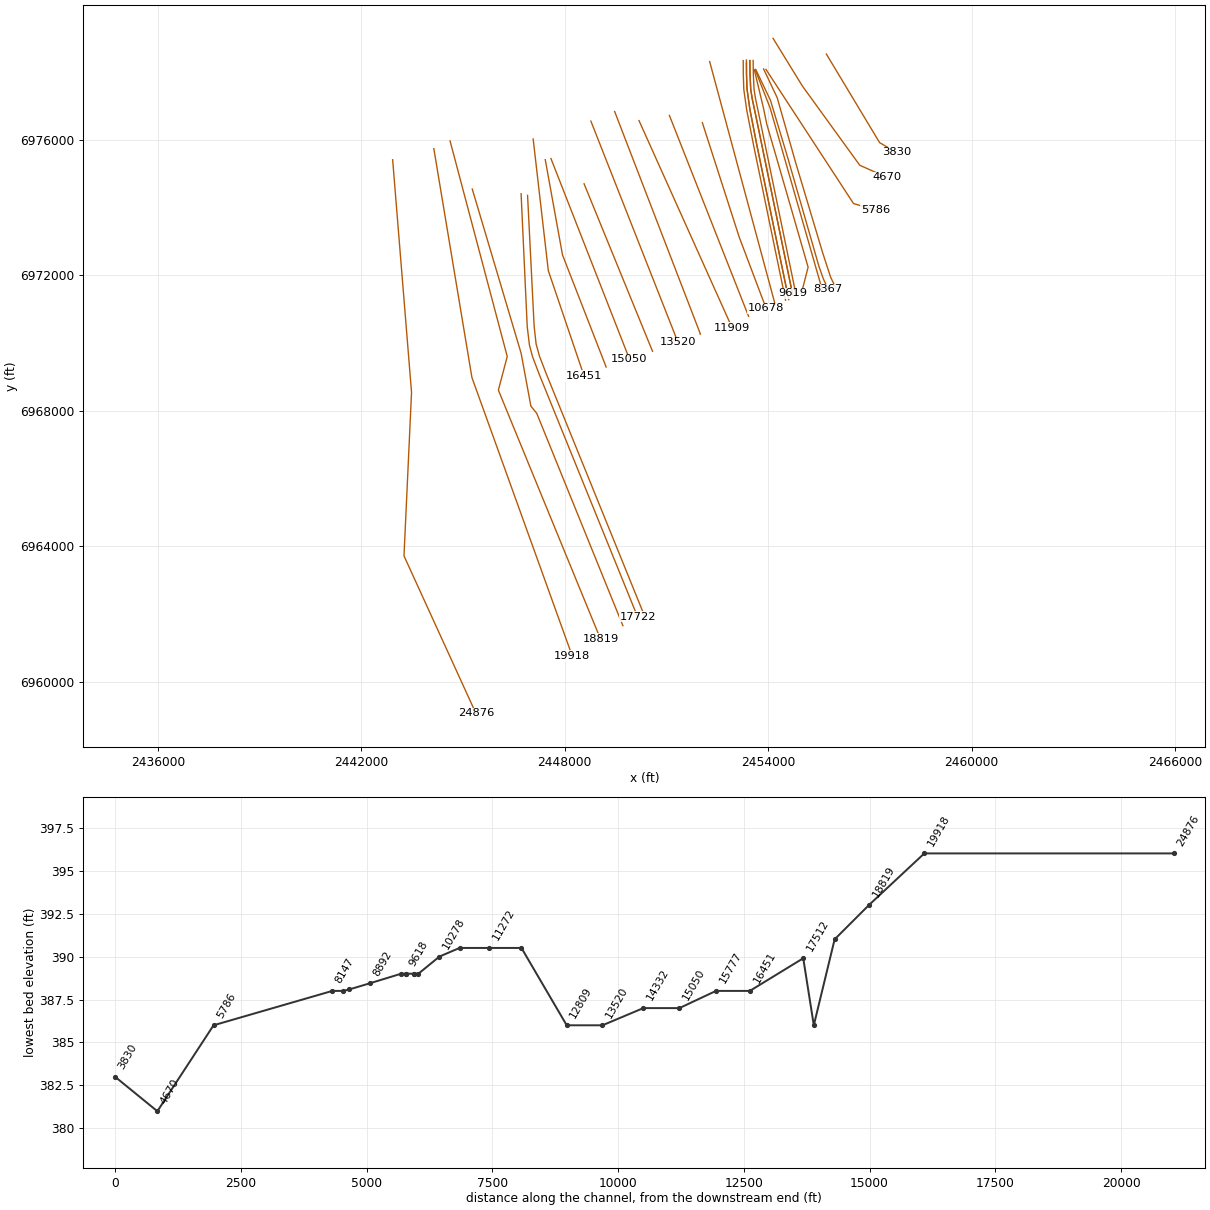
HEC-RAS study CDC_Consolidated_Model.prj: Upper Trinity CDC Consolidated Model

--- CDC_Consolidated_Model.g04 (geometry) --- (continued)

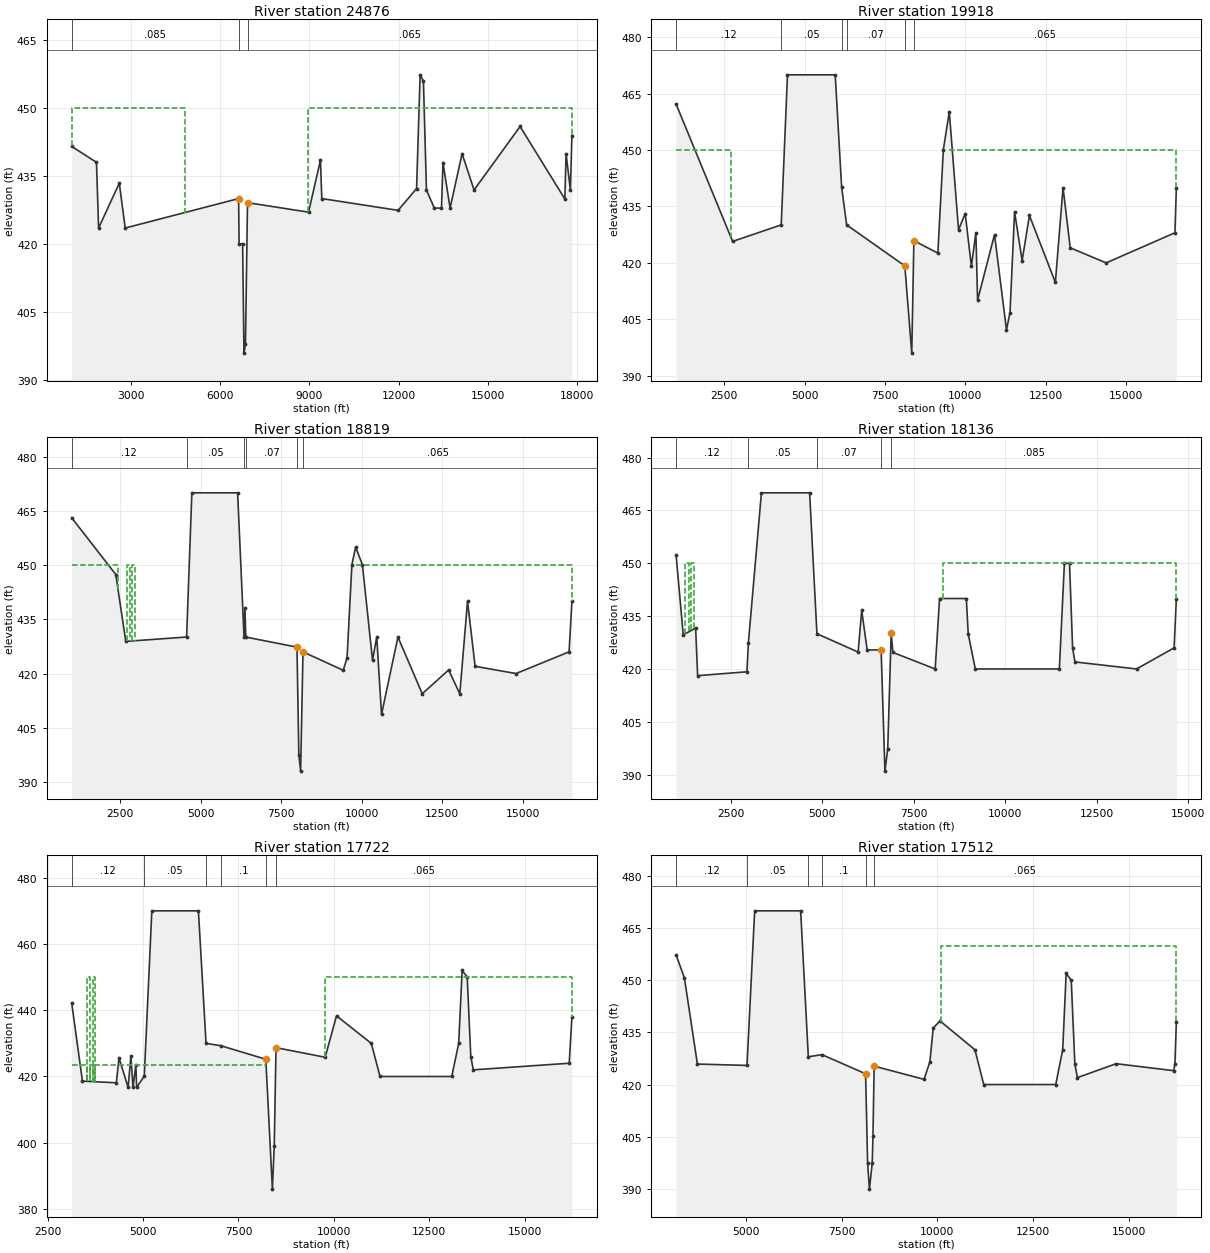
Type RM Length L Ch R = 1 ,24876   ,1720,4958,2260
BEGIN DESCRIPTION:
This cross section corresponds to cross section 24882 of the non-georeferenced CDC model which was the source of this model.
LOMR # 16-06-1120P reflected in ROB as inneffective flow area.
END DESCRIPTION:
XS GIS Cut Line= 6
  2442922.173902 6975416.6788449 2443204.8055546 6971933.6290525
 2443479.4099923 6968550.1000584  2443256.811028 6963722.4059736
 2444690.0890013 6960582.4752457  2445378.724107 6959073.9651393
#Sta/Elev= 30
    1000   441.6    1834   438.1    1906   423.6    2602   433.5    2801   423.6
    6616   430.1    6632   420.1    6751   420.1    6796     396    6846     398
    6915   429.2    8969   427.1    9369   438.6    9414   430.1   11981   427.5
   12602   432.3   12722   457.4   12833     456   12934     432   13199     428
   13440     428   13491     438   13730     428   14133     440   14536     432
   16085     446   17591     430   17631     440   17777     432   17828     444
#Mann= 3 ,-1,0
    1000    .085       0    6616    .055       0    6915    .065       0
#XS Ineff= 2 , 0
       0    4800     450    8960       0     450
Permanent Ineff=
       F       F
Bank Sta=6616,6915
XS Rating Curve= 0 ,0
Exp/Cntr=0.3,0.1

Type RM Length L Ch R = 1 ,19918   ,1048,1099,659
BEGIN DESCRIPTION:
This cross section corresponds to cross section 19924 of the non-georeferenced CDC model which was the source of this model.
LOMR # 16-06-1120P reflected in ROB as inneffective flow area.
END DESCRIPTION:
XS GIS Cut Line= 6
  2444136.963139 6975743.7369178 2444690.6339477 6972414.3213326
 2445260.6980963 6968986.9938697 2446155.2074622 6966502.6425391
 2447016.7119727 6964110.3290823 2448218.9280722 6960769.0329434
#Sta/Elev= 30
    1000   462.2    2758   425.7    4270   430.1    4465     470    5950     470
    6150   440.1    6306   430.1    8116   419.2    8332     396    8398   425.9
    9144   422.6    9315   450.1    9500   460.2    9787   428.8    9995   433.1
   10187   419.1   10327     428   10380   410.1   10907   427.5   11279   402.2
   11389   406.8   11531   433.6   11766   420.6   11993   432.6   12800   414.8
   13039     440   13263     424   14381     420   16521     428   16565     440
#Mann= 6 ,-1,0
    1000     .12       0    4270     .05       0    6150     .12       0
    6306     .07       0    8116    .055       0    8398    .065       0
#XS Ineff= 4 ,-1
    1000    2700     450    2700    8116   419.2    8398    9500   425.9
    9500   16565     450
Permanent Ineff=
       F       F       F       F
Bank Sta=8116,8398
XS Rating Curve= 0 ,0
Exp/Cntr=0.3,0.1

Type RM Length L Ch R = 1 ,18819   ,400,684,781
BEGIN DESCRIPTION:
This cross section corresponds to cross section 18823 of the non-georeferenced CDC model which was the source of this model.
LOMR # 16-06-1120P reflected in ROB as inneffective flow area.
END DESCRIPTION:
XS GIS Cut Line= 6
  2444615.869989 6975971.5100843 2445484.6330159 6972693.2394099
 2446302.4450286 6969607.8318668 2446040.9501447 6968615.0891016
 2447811.1880741 6964296.3890777 2449053.0779787 6961269.5168506
#Sta/Elev= 30
    1000   463.1    2369   447.4    2679   428.9    4567   430.1    4730     470
    6150     470    6350   430.1    6377     438    6405   430.1    7993   427.3
    8050   397.6    8105     393    8180     426    9426   420.9    9547   424.3
    9697   450.1    9814     455   10023   450.1   10337   423.7   10468   430.1
   10617   408.7   11126   430.1   11881   414.4   12700     421   13046   414.4
   13286     440   13522     422   14792     420   16438     426   16526     440
#Mann= 6 ,-1,0
    1000     .12       0    4567     .05       0    6350     .12       0
    6405     .07       0    7993    .045       0    8180    .065       0
#XS Ineff= 8 ,-1
    1000    2450     450    2450    2730     425    2730    2800     450
    2800    2870     425    2870    2950     450    2950    7993     425
    8180    9814   425.7    9814   16526     450
Permanent Ineff=
       F       F       F       F       F       F       F       F
Bank Sta=7993,8180
XS Rating Curve= 0 ,0
Exp/Cntr=0.3,0.1

Type RM Length L Ch R = 1 ,18136   ,430,414,500
BEGIN DESCRIPTION:
This cross section corresponds to cross section 18140 of the non-georeferenced CDC model which was the source of this model.
END DESCRIPTION:
XS GIS Cut Line= 6
  2445269.988104 6974552.3088545 2446004.8301382 6972080.7127478
 2446711.5101553 6969704.1948631 2446999.3150259 6968145.0050681
 2447173.3789823 6967928.3499896 2449713.4519861 6961663.0478877
#Sta/Elev= 30
    1000   452.3    1194   429.7    1534   431.6    1588   418.1    2936   419.2
    2975   427.3    3332     470    4650     470    4850     430    5976   424.8
    6074   436.6    6224   425.4    6605   425.4    6709     391    6786   397.4
    6880   430.2    6927   424.7  8083.3     420  8202.6     440  8934.6     440
  8986.2     430  9179.3     420   11478     420   11616     450   11756     450
   11840     426   11904     422   13588     420   14616     426   14677     440
#Mann= 5 ,-1,0
    1000     .12       0    2975     .05       0    4850     .07       0
    6605    .039       0    6880    .085       0
#XS Ineff= 7 ,-1
    1000    1250   425.4    1250    1350     450    1350    1420   425.4
    1420    1500     450    1500    6605   425.4    6880    8300   424.7
    8300   14677     450
Permanent Ineff=
       F       F       F       F       F       F       F
Bank Sta=6605,6880
XS Rating Curve= 0 ,0
Exp/Cntr=0.3,0.1

Type RM Length L Ch R = 1 ,17722   ,197,210,197
BEGIN DESCRIPTION:
This cross section corresponds to cross section 17726 of the non-georeferenced CDC model which was the source of this model.
END DESCRIPTION:
XS GIS Cut Line= 6
  2446711.175223 6974412.5544618 2446891.7358447 6970487.4928372
  2446957.909925 6969941.9440595 2447051.1131507 6969593.9851097
  2447262.373883 6969040.9799822 2450145.1591279 6961928.9981432
#Sta/Elev= 30
    3130   442.2    3412   418.6    4300   418.1    4370   425.6    4608   416.7
    4682   426.2    4736   416.7    4811   423.5    4831   416.7    5032   420.1
    5230     470    6450     470    6650     430    7034   429.3    8216   425.2
    8388     386    8437   399.1    8483   428.7    9770   425.8   10068   438.3
   10979     430   11208     420   13087     420   13269     430   13359     452
   13492     450   13586     426   13652     422   16165     424   16235     438
#Mann= 6 ,-1,0
    3130     .12       0    5032     .05       0    6650     .15       0
    7034      .1       0    8216    .039       0    8483    .065       0
#XS Ineff= 7 ,-1
    3130    3520   423.5    3520    3600     450    3600    3700   423.5
    3700    3750     450    3750    8216   423.5    8483    9770   425.5
    9770   16235     450
Permanent Ineff=
       F       F       F       F       F       F       F
Bank Sta=8216,8483
XS Rating Curve= 0 ,0
Exp/Cntr=0.3,0.1

Type RM Length L Ch R = 1 ,17512   ,850,1062,1060
BEGIN DESCRIPTION:
This cross section corresponds to cross section 17516 of the non-georeferenced CDC model which was the source of this model.
END DESCRIPTION:
XS GIS Cut Line= 6
  2446902.064564 6974364.7472217 2447095.8509221 6970501.4731242
 2447153.6368958 6969979.2251529 2447256.1599847 6969609.5188713
 2447454.9939046 6969093.79483722450362.421485316961924.84744545
#Sta/Elev= 30
    3180   457.3    3396   450.7    3735   425.9    5030   425.5    5230     470
    6430     470    6630     428    6987   428.6    8125   423.1    8178   397.3
    8225   389.9    8297   397.3    8317   405.2    8348   425.3    9650   421.5
    9802   426.5    9890   436.3   10068   438.3   10979     430   11208     420
   13087     420   13269     430   13359     452   13492     450   13586     426
   13652     422   14664     426   16165     424   16198     426   16235     438
#Mann= 6 ,-1,0
    3180     .12       0    5030     .05       0    6630     .15       0
    6987      .1       0    8125    .039       0    8348    .065       0
#XS Ineff= 2 , 0
       0                   10100       0     460
Permanent Ineff=
       F       F
Bank Sta=8125,8348
XS Rating Curve= 0 ,0
Exp/Cntr=0.3,0.1

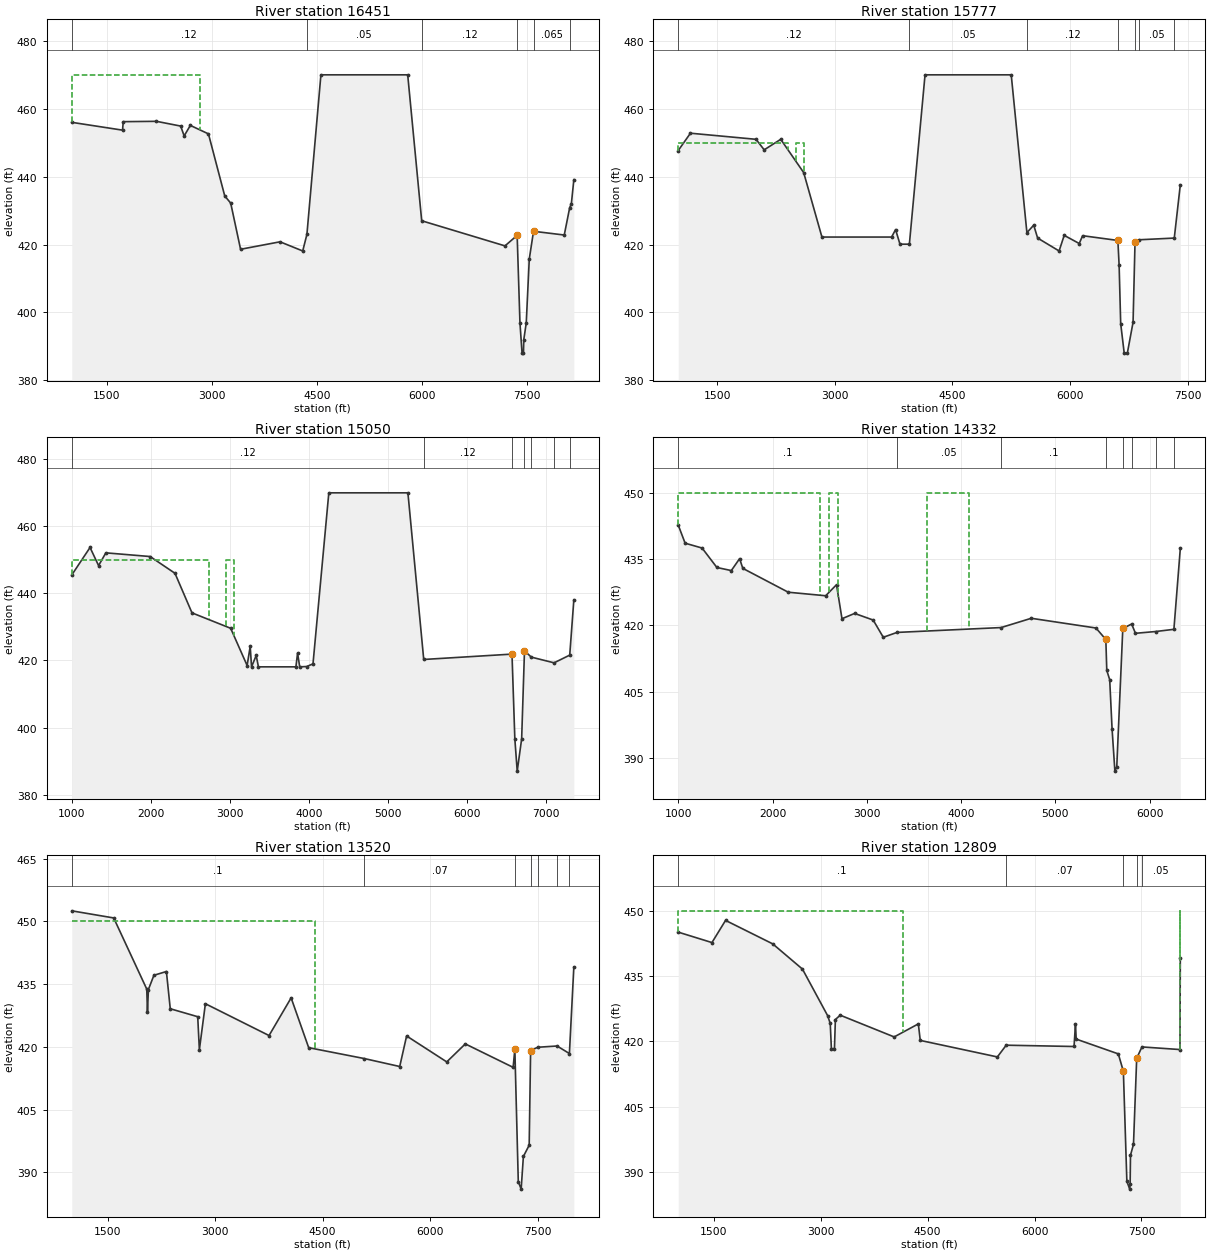
Type RM Length L Ch R = 1 ,16451   ,630,673,679
BEGIN DESCRIPTION:
This cross section corresponds to cross section 16454 of the non-georeferenced CDC model which was the source of this model.
END DESCRIPTION:
XS GIS Cut Line= 6
   2447066.84409  6976028.362989 2447295.9240128 6974035.9982073
 2447513.5728557 6972143.2539613 2448040.6879432 6970588.7314798
 2448288.7589693 6969857.1945571 2448567.8519151 6969034.2178566
#Sta/Elev= 30
    1000     456    1725   453.7    1736   456.2    2210   456.3    2556   454.9
    2606     452    2694   455.1    2953   452.6    3186   434.3    3271   432.2
    3412   418.6    3976   420.8    4300   418.1    4360     423    4560     470
    5800     470    6000     427    7190   419.6    7364   422.7    7404   396.9
    7434     388    7454     388    7459     392    7494   396.9    7537   415.7
    7598   423.9    8037   422.8    8115   430.9    8138   431.9    8174   439.1
#Mann= 6 ,-1,0
    1000     .12       0    4360     .05       0    6000     .12       0
    7364    .039       0    7598    .065       0    8115     .03       0
#XS Ineff= 3 ,-1
    1000    2830     470    2830    7364   422.7    7598    8174   423.9
Permanent Ineff=
       F       F       F
Bank Sta=7364,7598
XS Rating Curve= 0 ,0
Exp/Cntr=0.3,0.1

Type RM Length L Ch R = 1 ,15777   ,732,727,732
BEGIN DESCRIPTION:
This cross section corresponds to cross section 15780 of the non-georeferenced CDC model which was the source of this model.
END DESCRIPTION:
XS GIS Cut Line= 6
  2447423.560896 6975418.2769388  2447686.750987 6973963.8635091
 2447932.4148657   6972606.41314 2448290.0217621 6971687.1830231
 2448576.1215836 6970951.8019479 2449219.8919496 6969297.2038792
#Sta/Elev= 30
    1000   447.7    1156   452.8    1993     451    2097   447.9    2308     451
    2601   441.2    2834   422.2    3723   422.2    3774   424.4    3830   420.1
    3950   420.1    4150     470    5250     470    5450   423.5    5537   425.7
    5587   421.9    5861   418.1    5926   422.7    6118   420.3    6161   422.6
    6611   421.2    6627   413.9    6647   396.7    6692     388    6732     388
    6805   397.1    6830   420.7    6881   421.4    7331   421.9    7408   437.6
#Mann= 7 ,-1,0
    1000     .12       0    3950     .05       0    5450     .12       0
    6611    .039       0    6830     .15       0    6881     .05       0
    7331     .03       0
#XS Ineff= 5 ,-1
    1000    2400     450    2400    2500   421.2    2500    2600     450
    2600    6611   421.2    6830    7408   420.7
Permanent Ineff=
       F       F       F       F       F
Bank Sta=6611,6830
XS Rating Curve= 0 ,0
Exp/Cntr=0.3,0.1

Type RM Length L Ch R = 1 ,15050   ,718,718,718
BEGIN DESCRIPTION:
This cross section corresponds to cross section 15055 of the non-georeferenced CDC model which was the source of this model.
END DESCRIPTION:
XS GIS Cut Line= 6
  2447591.801045 6975450.3221503 2448126.3550947 6974083.7422063
 2448447.1087183 6973263.7989643 2448767.8777618 6972443.8586751
 2449373.8181509 6970895.0920876 2449908.5178689 6969528.5429834
#Sta/Elev= 30
    1000   445.5    1231   453.7    1339   448.3    1431   452.1    1991     451
    2305     446    2520   434.2    3009   429.6    3217   418.5    3256   424.2
    3273   418.1    3332   421.5    3360   418.1    3834   418.1    3855   422.2
    3882   418.1    3971   418.2    4050     419    4250     470    5250     470
    5450   420.3    6566   421.9    6602   396.6    6632     387    6688   396.6
    6724   422.9    6810     421    7098   419.3    7296   421.6    7348   438.1
#Mann= 7 ,-1,0
    1000     .12       0    5450     .12       0    6566    .039       0
    6724     .15       0    6810     .08       0    7098     .05       0
    7296     .03       0
#XS Ineff= 5 ,-1
    1000    2730     450    2730    2950   421.9    2950    3050     450
    3050    6566   421.9    6724    7348   422.9
Permanent Ineff=
       F       F       F       F       F
Bank Sta=6566,6724
XS Rating Curve= 0 ,0
Exp/Cntr=0.3,0.1

Type RM Length L Ch R = 1 ,14332   ,840,812,812
BEGIN DESCRIPTION:
This cross section corresponds to cross section 14335 of the non-georeferenced CDC model which was the source of this model.
END DESCRIPTION:
XS GIS Cut Line= 6
  2448569.195088 6974705.2590079 2448789.3705009 6974165.9818712
  2449082.948982 6973446.9485324 2449560.0408756 6972278.5246882
 2450073.8695723 6971020.2306168 2450587.7369829 6969761.9450757
#Sta/Elev= 30
    1000   442.7    1073   438.6    1253   437.5    1410   433.1    1563   432.4
    1651   435.1    1685   432.9    2167   427.5    2564   426.7    2679   429.2
    2737   421.5    2871   422.7    3068   421.2    3175   417.3    3321   418.4
    4425   419.5    4745   421.6    5431   419.4    5536   416.8    5546   409.8
    5577   407.7    5602   396.6    5632     387    5652     388    5716   419.3
    5810   420.3    5850   418.2    6063   418.6    6258   419.1    6326   437.4
#Mann= 8 ,-1,0
    1000      .1       0    3321     .05       0    4425      .1       0
    5536    .039       0    5716     .15       0    5810     .08       0
    6063     .05       0    6258     .03       0
#XS Ineff= 7 ,-1
    1000    2500     450    2500    2600   416.8    2600    2700     450
    2700    3635   416.8    3635    4088     450    4088    5536   416.8
    5716    6326   419.3
Permanent Ineff=
       F       F       F       F       F       F       F
Bank Sta=5536,5716
XS Rating Curve= 0 ,0
Exp/Cntr=0.3,0.1

Type RM Length L Ch R = 1 ,13520   ,739,711,709
BEGIN DESCRIPTION:
This cross section corresponds to cross section 13523 of the non-georeferenced CDC model which was the source of this model.
END DESCRIPTION:
XS GIS Cut Line= 6
  2448769.481105 6976555.8999917 2449447.8586853 6974831.8775211
 2450054.8876549 6973289.3435327 2450661.9720707 6971746.8216833
 2451019.1068551 6970839.4616214 2451340.5448605 6970022.8408793
#Sta/Elev= 30
    1000   452.5    1585   450.8    2046   433.8    2056   428.3    2069   433.7
    2146   437.1    2320     438    2374   429.1    2757   427.2    2780   419.3
    2864   430.3    3752   422.7    4060   431.7    4305   419.8    5081   417.2
    5575   415.3    5671   422.6    6231   416.4    6490   420.7    7157   415.1
    7181   419.4    7229   387.8    7269     386    7300   393.8    7381   396.5
    7401   419.1    7500   419.9    7770   420.2    7942   418.4    8004   439.1
#Mann= 7 ,-1,0
    1000      .1       0    5081     .07       0    7181    .039       0
    7401     .15       0    7500     .08       0    7770     .05       0
    7942     .03       0
#XS Ineff= 2 , 0
       0    4400     450               0
Permanent Ineff=
       F       F
Bank Sta=7181,7401
XS Rating Curve= 0 ,0
Exp/Cntr=0.3,0.1

Type RM Length L Ch R = 1 ,12809   ,810,900,920
BEGIN DESCRIPTION:
This cross section corresponds to cross section 12811 of the non-georeferenced CDC model which was the source of this model.
-------------------------------------------------
CDC GP042800-02 West Fork Relief Interceptor WF-1
Cross-section 12811 - 15780
Project located in ROB.
-------------------------------------------------
END DESCRIPTION:
XS GIS Cut Line= 6
  2449470.713954  6976839.625146 2450137.9124233 6975106.7162102
 2450770.0587967 6973465.0265802 2451367.1429044 6971914.5536313
 2451999.4100126 6970272.88893572451993.664301816970267.32168461
#Sta/Elev= 30
    1000   445.1    1473   442.7    1664   447.8    2326   442.4    2743   436.6
    3096   425.9    3133   424.1    3149   418.3    3192   418.3    3205     425
    3273     426    4030     421    4369     424    4396   420.2    5478   416.4
    5602   419.1    6554   418.8    6574     424    6584   420.5    7175   417.1
    7246   413.1    7295   387.8    7335     386    7341   387.2    7346   393.8
    7388   396.3    7433   416.1    7507   418.7    8040   418.1    8045   439.1
#Mann= 5 ,-1,0
    1000      .1       0    5602     .07       0    7246    .039       0
    7433     .15       0    7507     .05       0
#XS Ineff= 2 , 0
       0    4150     450    8040       0     450
Permanent Ineff=
       F       F
Bank Sta=7246,7433
XS Rating Curve= 0 ,0
Exp/Cntr=0.3,0.1

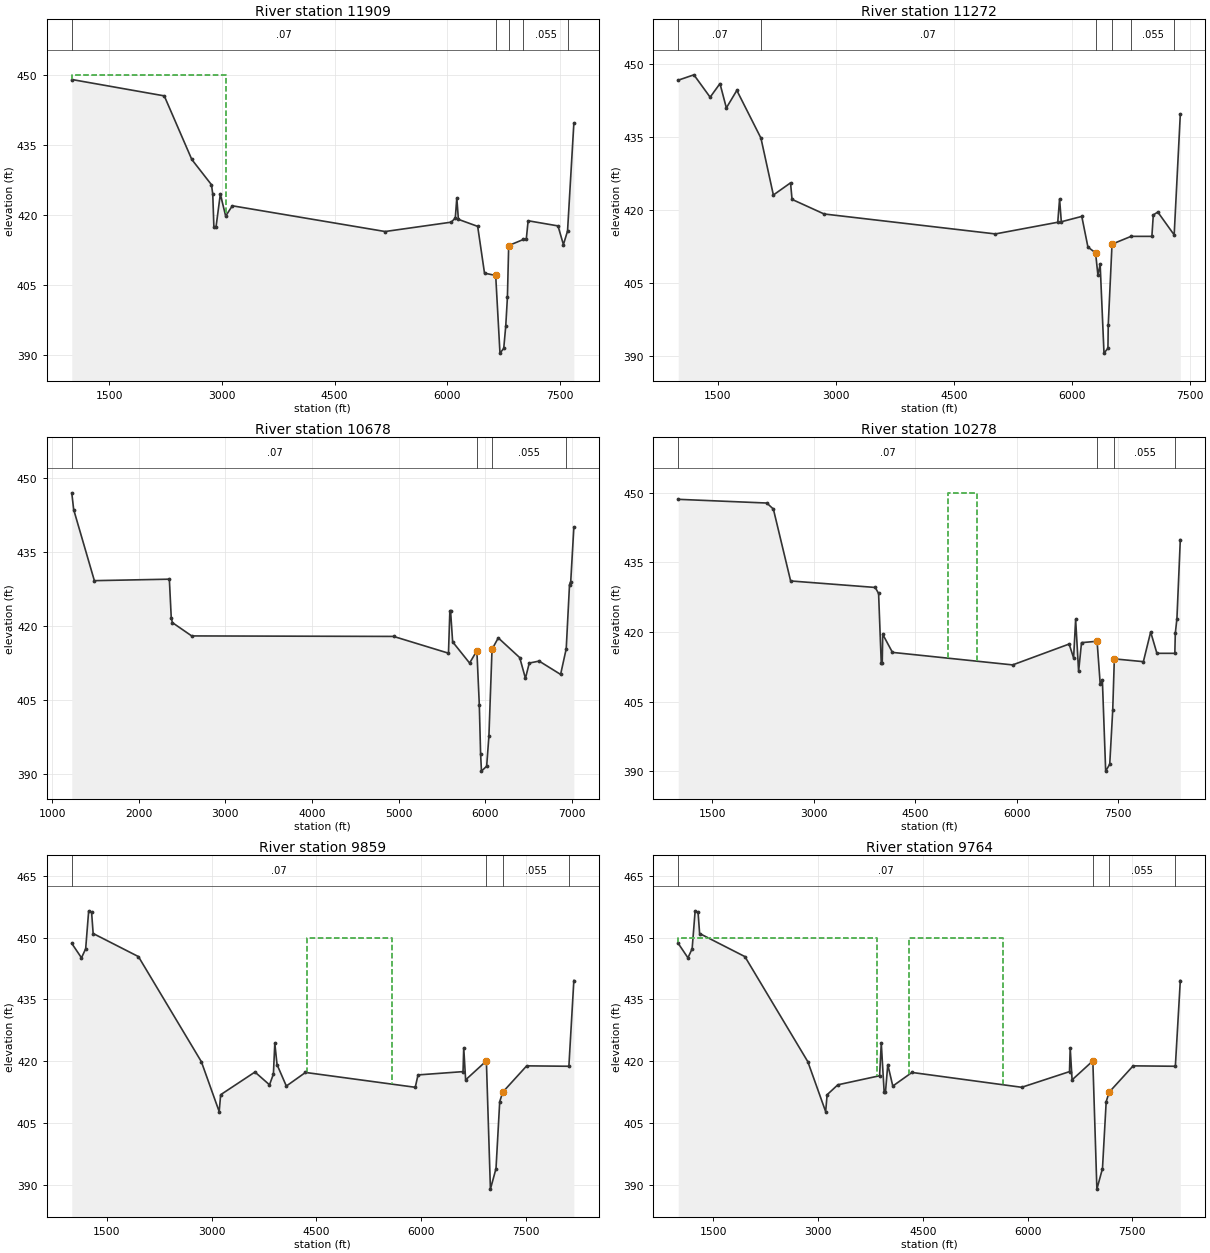
Type RM Length L Ch R = 1 ,11909   ,710,637,600
BEGIN DESCRIPTION:
This cross section corresponds to cross section 11911 of the non-georeferenced CDC model which was the source of this model.
END DESCRIPTION:
XS GIS Cut Line= 6
   2450189.07505 6976570.9688592 2450825.2620984 6975154.2098817
 2451541.0375697  6973560.371862 2452217.1103646  6972055.095345
  2452575.056171 6971258.1901147 2452933.0190378 6970461.2891494
#Sta/Elev= 30
    1000     449    2232   445.5    2599   431.9    2861   426.5    2878   424.5
    2893   417.5    2921   417.4    2979   424.5    3050   419.8    3139     422
    5174   416.5    6055   418.5    6109   419.4    6129   423.7    6150   419.1
    6407   417.6    6498   407.6    6647   407.1    6704   390.5    6754   391.5
    6781   396.3    6803   402.4    6820   413.5    7016   414.8    7054   414.8
    7079   418.8    7477   417.7    7549   413.7    7604   416.6    7688   439.6
#Mann= 5 ,-1,0
    1000     .07       0    6647    .039       0    6820     .09       0
    7016    .055       0    7604     .03       0
#XS Ineff= 2 , 0
       0    3050     450    6820       0   413.5
Permanent Ineff=
       F       F
Bank Sta=6647,6820
XS Rating Curve= 0 ,0
Exp/Cntr=0.3,0.1

Type RM Length L Ch R = 1 ,11272   ,620,593,600
BEGIN DESCRIPTION:
This cross section corresponds to cross section 11274 of the non-georeferenced CDC model which was the source of this model.
END DESCRIPTION:
XS GIS Cut Line= 6
2451085.70544404 6976723.8714473 2451766.0174348 6974996.2551451
 2452305.8880742 6973625.3924012 2452845.8030048 6972254.5391718
  2453133.775526 6971523.4212115 2453421.7608424 6970792.3058758
#Sta/Elev= 30
    1000   446.6    1199   447.7    1405   443.1    1530   445.9    1611   440.9
    1744   444.5    2050   434.7    2208     423    2426   425.5    2445   422.1
    2852   419.1    5027     415    5819   417.4    5842   422.2    5864   417.5
    6124   418.6    6202   412.3    6299   411.1    6329   406.5    6357   408.8
    6406   390.5    6456   391.5    6460   396.3    6508   412.9    6750   414.5
    7014   414.5    7032   418.9    7089   419.5    7297   414.8    7375   439.6
#Mann= 6 ,-1,0
    1000     .07       0    2050     .07       0    6299    .039       0
    6508     .09       0    6750    .055       0    7297     .03       0
Bank Sta=6299,6508
XS Rating Curve= 0 ,0
Exp/Cntr=0.3,0.1

Type RM Length L Ch R = 1 ,10678   ,529,400,404
BEGIN DESCRIPTION:
This cross section corresponds to cross section 10681 of the non-georeferenced CDC model which was the source of this model.
END DESCRIPTION:
XS GIS Cut Line= 6
  2452057.817323 6976508.8306834 2452313.3129281 6975715.2054788
 2452611.1148259 6974790.2178275 2453147.1990556 6973125.2480603
 2453560.7503938 6972029.7315506 2453939.8631527 6971025.5130866
#Sta/Elev= 30
    1226   446.9    1248   443.5    1487   429.1    2353   429.4    2375   421.6
    2388   420.6    2611   417.9    4943   417.8    5577   414.4    5593     423
    5601     423    5625   416.7    5821   412.4    5905   414.9    5933     404
    5948     394    5958   390.5    6018   391.5    6044   397.6    6080   415.2
    6152   417.5    6400   413.5    6466   409.3    6510   412.4    6624   412.8
    6872   410.1    6937   415.3    6975   428.3    6989   428.9    7025   439.9
#Mann= 4 ,-1,0
    1226     .07       0    5905    .039       0    6080    .055       0
    6937     .03       0
Bank Sta=5905,6080
XS Rating Curve= 0 ,0
Exp/Cntr=0.3,0.1

Type RM Length L Ch R = 1 ,10278   ,350,419,300
BEGIN DESCRIPTION:
This cross section corresponds to cross section 10280 of the non-georeferenced CDC model which was the source of this model.
END DESCRIPTION:
XS GIS Cut Line= 6
  2452273.229018 6978313.8298747 2452736.8901649 6976592.1141581
 2453226.3609707 6974774.7555881 2453509.7626349 6973722.6044772
 2453741.6496383 6972861.7554771 2454205.4590782 6971140.0630543
#Sta/Elev= 30
    1000   448.6    2309   447.8    2406   446.5    2661     431    3911   429.6
    3961   428.3    4000   413.4    4015   413.4    4022   419.5    4166   415.6
    5942   412.9    6777   417.4    6843   414.4    6873   422.7    6917   411.5
    6960   417.7    7190     418    7236   408.8    7268   409.7    7317     390
    7377   391.5    7421   403.1    7445   414.2    7874   413.6    7982     420
    8074   415.4    8339   415.4    8346   419.7    8370   422.9    8420   439.9
#Mann= 4 ,-1,0
    1000     .07       0    7190    .039       0    7445    .055       0
    8346     .03       0
#XS Ineff= 1 ,-1
    4990    5420     450
Permanent Ineff=
       F
Bank Sta=7190,7445
XS Rating Curve= 0 ,0
Exp/Cntr=0.3,0.1

Type RM Length L Ch R = 1 ,9859    ,95,95,95
BEGIN DESCRIPTION:
This cross section corresponds to cross section 9861 of the non-georeferenced CDC model which was the source of this model.
END DESCRIPTION:
XS GIS Cut Line= 6
   2453263.27986 6978342.9840159 2453265.7769024 6977926.0721201
 2453280.2880282 6977491.1920843 2453365.6480937 6976885.8921138
 2453572.3409218 6975826.5900986 2454511.7839248 6971270.0529518
#Sta/Elev= 30
    1000   448.6    1139   445.1    1199   447.3    1242   456.5    1284   456.1
    1306     451    1954   445.4    2855   419.9    3110   407.8    3131   411.9
    3622   417.4    3830   414.3    3886   416.9    3906   424.4    3938   419.2
    4071     414    4345   417.3    5916   413.7    5956   416.7    6600   417.5
    6610   423.3    6637   415.5    6934   420.1    6992     389    7072     394
    7125   410.2    7167   412.5    7511   418.9    8115   418.8    8186   439.6
#Mann= 4 ,-1,0
    1000     .07       0    6934    .039       0    7167    .055       0
    8115     .03       0
#XS Ineff= 1 ,-1
    4360    5577     450
Permanent Ineff=
       F
Bank Sta=6934,7167
XS Rating Curve= 0 ,0
Exp/Cntr=0.3,0.1

Type RM Length L Ch R = 1 ,9764    ,1,1,1
BEGIN DESCRIPTION:
This cross section corresponds to cross section 9764 of the non-georeferenced CDC model which was the source of this model.
END DESCRIPTION:
XS GIS Cut Line= 6
  2453357.112677 6978358.5043261   2453359.60972 6977941.5924302
 2453374.1208458 6977506.7123945 2453459.4809113  6976901.412424
 2453666.1737394 6975842.1104087 2454605.6167424  6971285.573262
#Sta/Elev= 30
    1000   448.6    1139   445.1    1199   447.3    1242   456.5    1284   456.1
    1306     451    1954   445.4    2855   419.9    3110   407.8    3131   411.9
    3284   414.3    3882   416.5    3906   424.4    3947   412.6    3966   412.5
    3999   419.2    4071     414    4345   417.3    5916   413.7    6600   417.5
    6610   423.3    6637   415.5    6934   420.1    6992     389    7072     394
    7125   410.2    7167   412.5    7511   418.9    8115   418.8    8186   439.6
#Mann= 4 ,-1,0
    1000     .07       0    6934    .039       0    7167    .055       0
    8115     .03       0
#XS Ineff= 2 ,-1
    4300    5650     450    1000    3850     450
Permanent Ineff=
       F       F
Bank Sta=6934,7167
XS Rating Curve= 0 ,0
Exp/Cntr=0.3,0.1

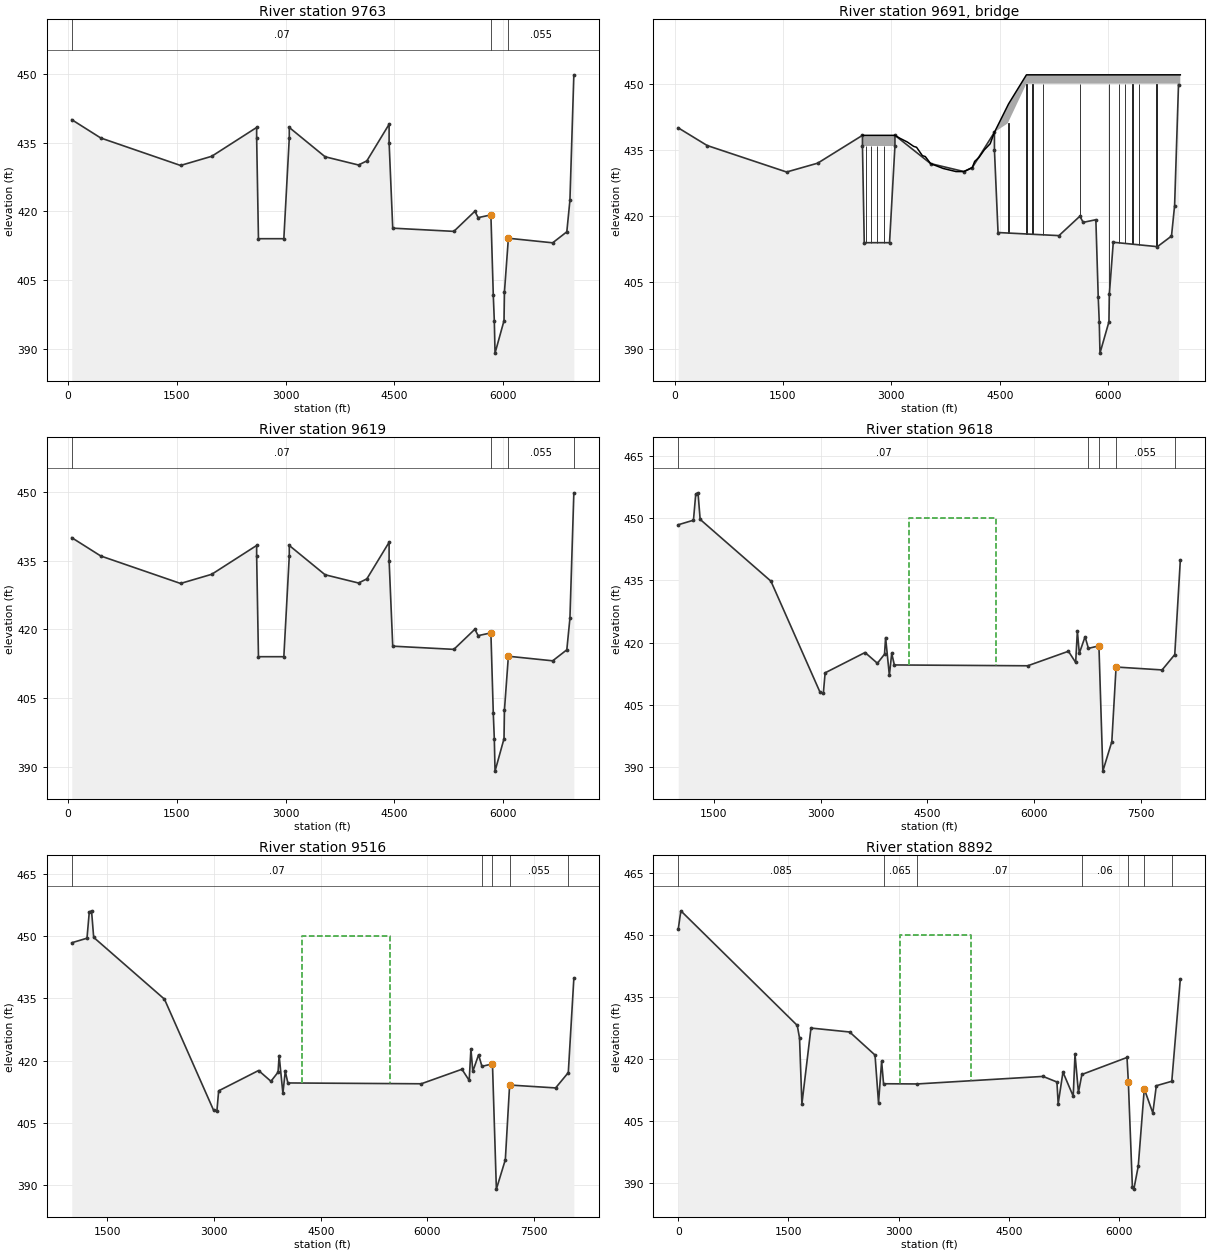
Type RM Length L Ch R = 1 ,9763    ,145,145,145
BEGIN DESCRIPTION:
This cross section corresponds to cross section 9763 of the non-georeferenced CDC model which was the source of this model.
END DESCRIPTION:
XS GIS Cut Line= 6
  2453358.799234 6978272.9224443 2453360.5795343 6977941.7374431
 2453375.0906602 6977506.8574073 2453460.4507257 6976901.5574368
 2453667.1435537 6975842.2554216      2454583.68      6971397.84
#Sta/Elev= 30
      50     440     450     436    1550     430    1980     432    2600   438.3
    2600     436    2625     414    2975     414    3050     436    3050   438.3
    3544   431.9    4005   430.1    4120     431    4427     439    4427     435
    4477   416.3    5320   415.6    5610     420    5655   418.6    5831   419.2
    5864   401.6    5878   396.1    5888     389    6012   396.1    6018   402.4
    6072   414.1    6683   413.1    6878   415.5    6921   422.4    6975   449.8
#Mann= 3 ,-1,0
      50     .07       0    5831    .039       0    6072    .055       0
Bank Sta=5831,6072
XS Rating Curve= 0 ,0
Exp/Cntr=0.5,0.3

Type RM Length L Ch R = 3 ,9691    ,,,
BEGIN DESCRIPTION:
Loop 12
END DESCRIPTION:
Node Name=Loop 12
Bridge Culvert--1,0,-1,-1, 0
Deck Dist Width WeirC Skew NumUp NumDn MinLoCord MaxHiCord MaxSubmerge Is_Ogee
0.5,144,2.6,0, 23, 23, , , 0.95, 0, ,,,
    2600    3050    3050    3123    3220    3309    3349    3430    3470    3544
    3718    3895    4005    4120    4153    4213    4286    4368    4427    4610
    4622    4870    7000
   438.3   438.3   438.3   437.6   436.8   435.8   435.6   433.7   433.5   431.9
   430.8   430.1   430.1     431   432.4   433.3     435   436.4     439     445
   445.4     452     452
     436     436   438.3   437.6   436.8   435.8   435.6   433.7   433.5   431.9
   430.8   430.1   430.1     431   432.4   433.3     435   436.4     439     441
   441.4     450     450
    2600    3050    3050    3123    3220    3309    3349    3430    3470    3544
    3718    3895    4005    4120    4153    4213    4286    4368    4427    4610
    4622    4870    7000
   438.3   438.3   438.3   437.6   436.8   435.8   435.6   433.7   433.5   431.9
   430.8   430.1   430.1     431   432.4   433.3     435   436.4     439     445
   445.4     452     452
     436     436   438.3   437.6   436.8   435.8   435.6   433.7   433.5   431.9
   430.8   430.1   430.1     431   432.4   433.3     435   436.4     439     441
   441.4     450     450
Pier Skew, UpSta & Num, DnSta & Num=  ,2647, 2 ,2647, 2 , 0 , 0 , 0 ,,
       4       4
     410     437
       4       4
     410     437
Pier Skew, UpSta & Num, DnSta & Num=  ,2722, 2 ,2722, 2 , 0 , 0 , 0 ,,
       4       4
     410     437
       4       4
     410     437
Pier Skew, UpSta & Num, DnSta & Num=  ,2802, 2 ,2802, 2 , 0 , 0 , 0 ,,
       4       4
     410     437
       4       4
     410     437
Pier Skew, UpSta & Num, DnSta & Num=  ,2902, 2 ,2902, 2 , 0 , 0 , 0 ,,
       4       4
     410     437
       4       4
     410     437
Pier Skew, UpSta & Num, DnSta & Num=  ,4616, 2 ,4616, 2 , 0 , 0 , 0 ,,
      12      12
     415   441.4
      12      12
     415   441.4
Pier Skew, UpSta & Num, DnSta & Num=  ,4870.5, 2 ,4870.5, 2 , 0 , 0 , 0 ,,
      15      15
     415   450.5
      15      15
     415   450.5
Pier Skew, UpSta & Num, DnSta & Num=  ,4954.5, 2 ,4954.5, 2 , 0 , 0 , 0 ,,
      15      15
     415   450.5
      15      15
     415   450.5
Pier Skew, UpSta & Num, DnSta & Num=  ,5102.5, 2 ,5102.5, 2 , 0 , 0 , 0 ,,
       5       5
     415   450.5
       5       5
     415   450.5
Pier Skew, UpSta & Num, DnSta & Num=  ,5613, 2 ,5613, 2 , 0 , 0 , 0 ,,
       6       6
     415   450.5
       6       6
     415   450.5
Pier Skew, UpSta & Num, DnSta & Num=  ,6015, 2 ,6015, 2 , 0 , 0 , 0 ,,
       6       6
     400   450.5
       6       6
     400   450.5
Pier Skew, UpSta & Num, DnSta & Num=  ,6152.5, 2 ,6152.5, 2 , 0 , 0 , 0 ,,
       5       5
     400   450.5
       5       5
     400   450.5
Pier Skew, UpSta & Num, DnSta & Num=  ,6231, 2 ,6231, 2 , 0 , 0 , 0 ,,
       6       6
     400   450.5
       6       6
     400   450.5
Pier Skew, UpSta & Num, DnSta & Num=  ,6337, 2 ,6337, 2 , 0 , 0 , 0 ,,
       6       6
     400   450.5
       6       6
     400   450.5
Pier Skew, UpSta & Num, DnSta & Num=  ,6432, 2 ,6432, 2 , 0 , 0 , 0 ,,
       6       6
     400   450.5
       6       6
     400   450.5
Pier Skew, UpSta & Num, DnSta & Num=  ,6675.5, 2 ,6675.5, 2 , 0 , 0 , 0 ,,
      15      15
     400   450.5
      15      15
     400   450.5
BR Coef= 1 , 0 , 0 ,1.05, 0 ,,,0.8,-1,0.5,1,
WSPro=,,,, 1 ,,,, 0 ,,,, 0 ,,,,-1 ,-1 ,-1 , 0 , 0 , 0 , 0 , 0
BC Design=,, 0 ,, 0 ,,,,,,
BC HTab HWMax=449.8
BC Use User HTab Curves=0
BC User HTab FreeFlow(D)= 0

Type RM Length L Ch R = 1 ,9619    ,1,1,1
BEGIN DESCRIPTION:
This cross section corresponds to cross section 9617 of the non-georeferenced CDC model which was the source of this model.
END DESCRIPTION:
XS GIS Cut Line= 6
      2453457.93      6978342.09 2453463.7686324 6977931.0238818
 2453483.8056658 6977494.2570388 2453528.5217837 6977213.2848317
 2453657.7045963 6976600.2529213       2454713.8      6971470.59
#Sta/Elev= 30
      50     440     450     436    1550     430    1980     432    2600   438.3
    2600     436    2625     414    2975     414    3050     436    3050   438.3
    3544   431.9    4005   430.1    4120     431    4427     439    4427     435
    4477   416.3    5320   415.6    5610     420    5655   418.6    5831   419.2
    5864   401.6    5878   396.1    5888     389    6012   396.1    6018   402.4
    6072   414.1    6683   413.1    6878   415.5    6921   422.4    6975   449.8
#Mann= 4 ,-1,0
      50     .07       0    5831    .039       0    6072    .055       0
    6975     .03       0
Bank Sta=5831,6072
XS Rating Curve= 0 ,0
Exp/Cntr=0.5,0.3

Type RM Length L Ch R = 1 ,9618    ,102,102,102
BEGIN DESCRIPTION:
This cross section corresponds to cross section 9616 of the non-georeferenced CDC model which was the source of this model.
END DESCRIPTION:
XS GIS Cut Line= 6
  2453458.497317 6978343.0883464 2453464.7384467 6977931.1682385
 2453484.7754802 6977494.4017236 2453529.4915981 6977213.4291884
 2453658.6744106  6976600.397278 2454729.2444479 6971402.4985531
#Sta/Elev= 30
    1000   448.4    1214   449.5    1246   455.8    1278   456.1    1308   449.7
    2303   434.8    2994     408    3040   407.8    3065   412.7    3626   417.6
    3800     415    3900   417.2    3915   421.2    3968   412.1    4001   417.4
    4038   414.6    5913   414.4    6485   417.9    6587   415.2    6611   422.8
    6638   417.4    6719   421.4    6766   418.6    6914   419.2    6969     389
    7095   396.1    7155   414.1    7802   413.4    7980   417.1    8058   439.8
#Mann= 5 ,-1,0
    1000     .07       0    6766     .06       0    6914    .039       0
    7155    .055       0    7980     .03       0
#XS Ineff= 1 ,-1
    4240    5467     450
Permanent Ineff=
       F
Bank Sta=6914,7155
XS Rating Curve= 0 ,0
Exp/Cntr=0.3,0.1

Type RM Length L Ch R = 1 ,9516    ,405,625,364
BEGIN DESCRIPTION:
This cross section corresponds to cross section 9520 of the non-georeferenced CDC model which was the source of this model.
END DESCRIPTION:
XS GIS Cut Line= 6
  2453555.368842 6978346.7290871 2453561.6099722 6977934.8089792
 2453581.6470056 6977498.0421362 2453626.3631235 6977217.0699292
  2453755.545936 6976604.0380187 2454826.1159733 6971406.1389657
#Sta/Elev= 30
    1000   448.4    1214   449.5    1246   455.8    1278   456.1    1308   449.7
    2303   434.8    2994     408    3040   407.8    3065   412.7    3626   417.6
    3800     415    3900   417.2    3915   421.2    3968   412.1    4001   417.4
    4038   414.6    5913   414.4    6485   417.9    6587   415.2    6611   422.8
    6638   417.4    6719   421.4    6766   418.6    6914   419.2    6969     389
    7095   396.1    7155   414.1    7802   413.4    7980   417.1    8058   439.8
#Mann= 5 ,-1,0
    1000     .07       0    6766     .06       0    6914    .039       0
    7155    .055       0    7980     .03       0
#XS Ineff= 1 ,-1
    4240    5467     450
Permanent Ineff=
       F
Bank Sta=6914,7155
XS Rating Curve= 0 ,0
Exp/Cntr=0.3,0.1

Type RM Length L Ch R = 1 ,8892    ,224,402,479
BEGIN DESCRIPTION:
This cross section corresponds to cross section 8884 of the non-georeferenced CDC model which was the source of this model.
END DESCRIPTION:
XS GIS Cut Line= 6
  2453590.094167 6978074.2020732 2453862.8373881 6976928.0836305
 2453959.7135067 6976458.6072072 2454301.0153175 6975282.6807533
 2455177.3711763 6972243.7527761 2454974.6766998  6971456.820951
#Sta/Elev= 30
       0  451.47   35.51  455.94 1619.87  428.15 1650.75  425.11 1683.29  409.11
  1806.6  427.51 2332.93  426.55 2678.33  420.96 2726.08  409.33  2768.2  419.45
 2794.51     414 3252.14  413.95 4965.23  415.78 5154.32  414.42 5171.16  409.13
 5236.28  416.82 5375.99  410.98 5400.26  421.14 5447.12  411.88 5493.85  416.25
 6107.99  420.37  6126.2  414.44 6181.13     389 6201.13  388.44 6261.13     394
 6343.02  412.74 6459.48  406.92 6507.06  413.52  6717.6   414.6 6833.56  439.37
#Mann= 7 ,-1,0
       0    .085       0 2794.51    .065       0 3252.14     .07       0
 5493.85     .06       0  6126.2    .039       0 6343.02    .055       0
  6717.6     .03       0
#XS Ineff= 1 ,-1
    3025    3990     450
Permanent Ineff=
       F
Bank Sta=6126.2,6343.02
XS Rating Curve= 0 ,0
Exp/Cntr=0.3,0.1

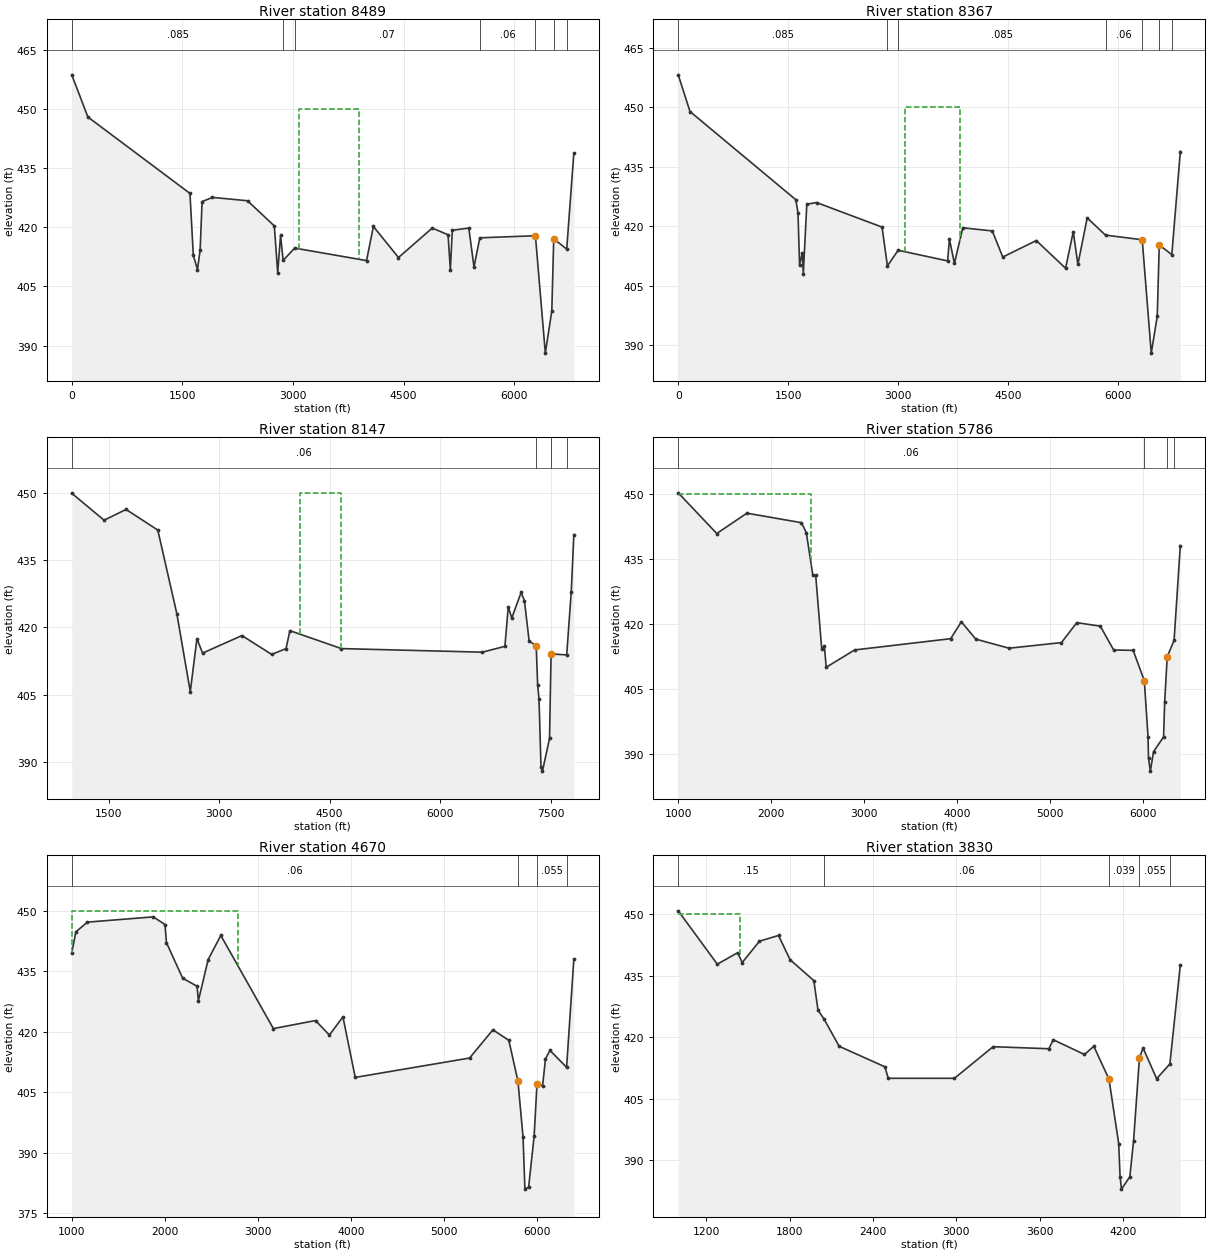
Type RM Length L Ch R = 1 ,8489    ,121,122,163
BEGIN DESCRIPTION:
This cross section corresponds to cross section 8469 of the non-georeferenced CDC model which was the source of this model.
END DESCRIPTION:
XS GIS Cut Line= 3
   2453615.43073 6978075.6925557 2454058.1490053 6976939.7771767
 2455591.3073563 6971586.4571746
#Sta/Elev= 30
       0  458.59  218.64   447.9 1602.62  428.55    1648   412.9  1704.4  409.27
 1740.56  414.18 1766.97  426.48 1908.12  427.54 2382.99  426.69 2746.47  420.31
 2792.23  408.47 2830.96  417.93 2866.02  411.57 3022.16   414.7 3996.56  411.53
 4090.06  420.17 4429.96  412.31 4887.92  419.77 5102.22  418.07 5133.41  409.21
 5159.88  419.21 5383.61  419.77 5453.88  409.91 5532.59   417.3 6286.71  417.83
 6421.13  388.09 6508.89  398.78 6535.11  417.04 6711.22  414.45 6807.84  438.78
#Mann= 7 ,-1,0
       0    .085       0 2866.02    .065       0 3022.16     .07       0
 5532.59     .06       0 6286.71    .039       0 6535.11    .055       0
 6711.22     .03       0
#XS Ineff= 1 ,-1
    3080    3900     450
Permanent Ineff=
       F
Bank Sta=6286.71,6535.11
XS Rating Curve= 0 ,0
Exp/Cntr=0.3,0.1

Type RM Length L Ch R = 1 ,8367    ,223,219,233
BEGIN DESCRIPTION:
This cross section corresponds to cross section 8375 of the non-georeferenced CDC model which was the source of this model.
END DESCRIPTION:
XS GIS Cut Line= 6
   2453632.43693  6978080.906128 2454067.2198533 6977168.4679922
 2454570.4179939 6975495.1839372  2455497.999144 6972263.8049013
 2455631.3771581 6971887.9231072 2455772.8240537 6971592.1681212
#Sta/Elev= 30
       0  458.17   160.3  448.92 1603.26  426.69 1633.46  423.39 1655.12  410.24
 1692.37   413.3 1705.81     408  1753.7  425.53 1887.04  425.97 2779.81  419.78
 2853.47     410 2999.54  413.94 3674.74  411.25 3699.04  416.74 3767.15  410.61
 3881.34   419.6 4283.86  418.81 4426.48  412.23 4883.62  416.38 5283.17  409.41
 5388.22  418.61 5451.24  410.35 5578.19   422.1 5827.93  417.75 6328.82  416.59
    6452     388 6533.87  397.29  6561.2   415.3  6732.5  412.83 6848.38  438.82
#Mann= 7 ,-1,0
       0    .085       0 2853.47    .065       0 2999.54    .085       0
 5827.93     .06       0 6328.82    .039       0  6561.2    .055       0
  6732.5     .03       0
#XS Ineff= 1 ,-1
    3090    3840     450
Permanent Ineff=
       F
Bank Sta=6328.82,6561.2
XS Rating Curve= 0 ,0
Exp/Cntr=0.3,0.1

Type RM Length L Ch R = 1 ,8147    ,1200,2361,2600
BEGIN DESCRIPTION:
This cross section corresponds to cross section 8149 of the non-georeferenced CDC model which was the source of this model.
-------------------------------------
CDC IRV030300-1 Farrow Addition
CDC IRV081211-1 Trailer Storage Site
Cross-section 8149 - 9520
Located in LOB.
-------------------------------------
END DESCRIPTION:
XS GIS Cut Line= 6
  2453864.572948 6978094.9940263 2454264.8490512 6977247.2201313
 2454816.5480791 6975307.1800482 2455604.6888912 6972676.0009273
 2455841.1310037 6971948.4859782  2455998.194994 6971627.8150316
#Sta/Elev= 30
    1000   449.9    1439   443.9    1737   446.3    2168   441.7    2426   423.1
    2609   405.7    2699   417.5    2776   414.3    3310   418.2    3714     414
    3909   415.3    3961   419.3    4660   415.3    6574   414.5    6880   415.8
    6926   424.6    6973   422.1    7100   427.8    7145     426    7209     417
    7305   415.9    7325   407.1    7343   404.1    7370     389    7390     388
    7486   395.3    7507   414.1    7719   413.9    7781     428    7816   440.7
#Mann= 4 ,-1,0
    1000     .06       0    7305    .039       0    7507    .055       0
    7719     .03       0
#XS Ineff= 1 ,-1
    4100    4660     450
Permanent Ineff=
       F
Bank Sta=7305,7507
XS Rating Curve= 0 ,0
Exp/Cntr=0.3,0.1

Type RM Length L Ch R = 1 ,5786    ,860,1117,1050
BEGIN DESCRIPTION:
This cross section corresponds to cross section 5788 of the non-georeferenced CDC model which was the source of this model.
END DESCRIPTION:
XS GIS Cut Line= 6
  2453934.336917 6978081.8500237 2454553.8652055 6977131.8378162
 2455276.6934843 6976023.5050591 2455896.2992004 6975073.5190982
 2456515.9410057 6974123.5449482 2457167.6270383 6973927.6129254
#Sta/Elev= 30
    1000   450.3    1414   440.9    1738   445.6    2325   443.4    2377   441.1
    2447   431.3    2478   431.2    2543   414.2    2571   414.9    2591     410
    2897     414    3929   416.6    4044   420.5    4199   416.5    4557   414.4
    5120   415.7    5285   420.3    5538   419.5    5681     414    5891   413.9
    6011   406.9    6051   393.9    6056     389    6076     386    6110   390.5
    6218   393.9    6230     402    6257   412.4    6331   416.2    6398   438.1
#Mann= 4 ,-1,0
    1000     .06       0    6011    .039       0    6257    .055       0
    6331     .03       0
#XS Ineff= 2 , 0
       0    2430     450               0
Permanent Ineff=
       F       F
Bank Sta=6011,6257
XS Rating Curve= 0 ,0
Exp/Cntr=0.3,0.1

Type RM Length L Ch R = 1 ,4670    ,1049,839,829
BEGIN DESCRIPTION:
This cross section corresponds to cross section 4671 of the non-georeferenced CDC model which was the source of this model.
END DESCRIPTION:
XS GIS Cut Line= 6
  2454143.389976  6978999.297992 2454621.3942699 6978220.9973832
 2455003.8141087 6977598.3621456  2455879.415704 6976387.9187003
   2456700.35107 6975253.1499725 2457491.4170732   6974899.32194
#Sta/Elev= 30
    1000   439.6    1044   444.8    1169   447.2    1877   448.5    2002   446.6
    2018   442.1    2192   433.3    2347   431.3    2361   427.7    2466   437.9
    2602   443.9    3167   420.8    3620   422.8    3769   419.2    3915   423.7
    4047   408.7    5276   413.5    5527   420.5    5698   417.9    5796   407.8
    5851   393.9    5871     381    5911   381.5    5970   394.1    6001   407.1
    6061   406.6    6092   413.3    6140   415.4    6319   411.2    6397     438
#Mann= 4 ,-1,0
    1000     .06       0    5796    .039       0    6001    .055       0
    6319     .03       0
#XS Ineff= 2 , 0
       0    2790     450               0
Permanent Ineff=
       F       F
Bank Sta=5796,6001
XS Rating Curve= 0 ,0
Exp/Cntr=0.3,0.1

Type RM Length L Ch R = 1 ,3830    ,420,508,510
BEGIN DESCRIPTION:
This cross section corresponds to cross section 3831 of the non-georeferenced CDC model which was the source of this model.
END DESCRIPTION:
XS GIS Cut Line= 6
  2455714.583028 6978536.5180777 2456156.7386402 6977800.7049167
 2456500.6513382 6977228.4101296  2456893.708951 6976574.3635374
 2457286.7819837 6975920.3218665 2457775.2160462 6975634.8729623
#Sta/Elev= 30
    1000   450.8    1281   437.8    1427   440.6    1460   438.2    1584   443.4
    1721   444.8    1804   438.9    1975   433.8    2005   426.6    2049   424.4
    2157   417.8    2486   412.8    2510     410    2986     410    3264   417.7
    3665   417.2    3696   419.4    3921   415.8    3988   417.8    4097   409.8
    4167   394.1    4177     386    4187     383    4247     386    4274   394.8
    4316   414.9    4342   417.4    4440   409.9    4535   413.5    4610   437.6
#Mann= 5 ,-1,0
    1000     .15       0    2049     .06       0    4097    .039       0
    4316    .055       0    4535     .03       0
#XS Ineff= 2 , 0
       0    1445     450               0
Permanent Ineff=
       F       F
Bank Sta=4097,4316
XS Rating Curve= 0 ,0
Exp/Cntr=0.3,0.1