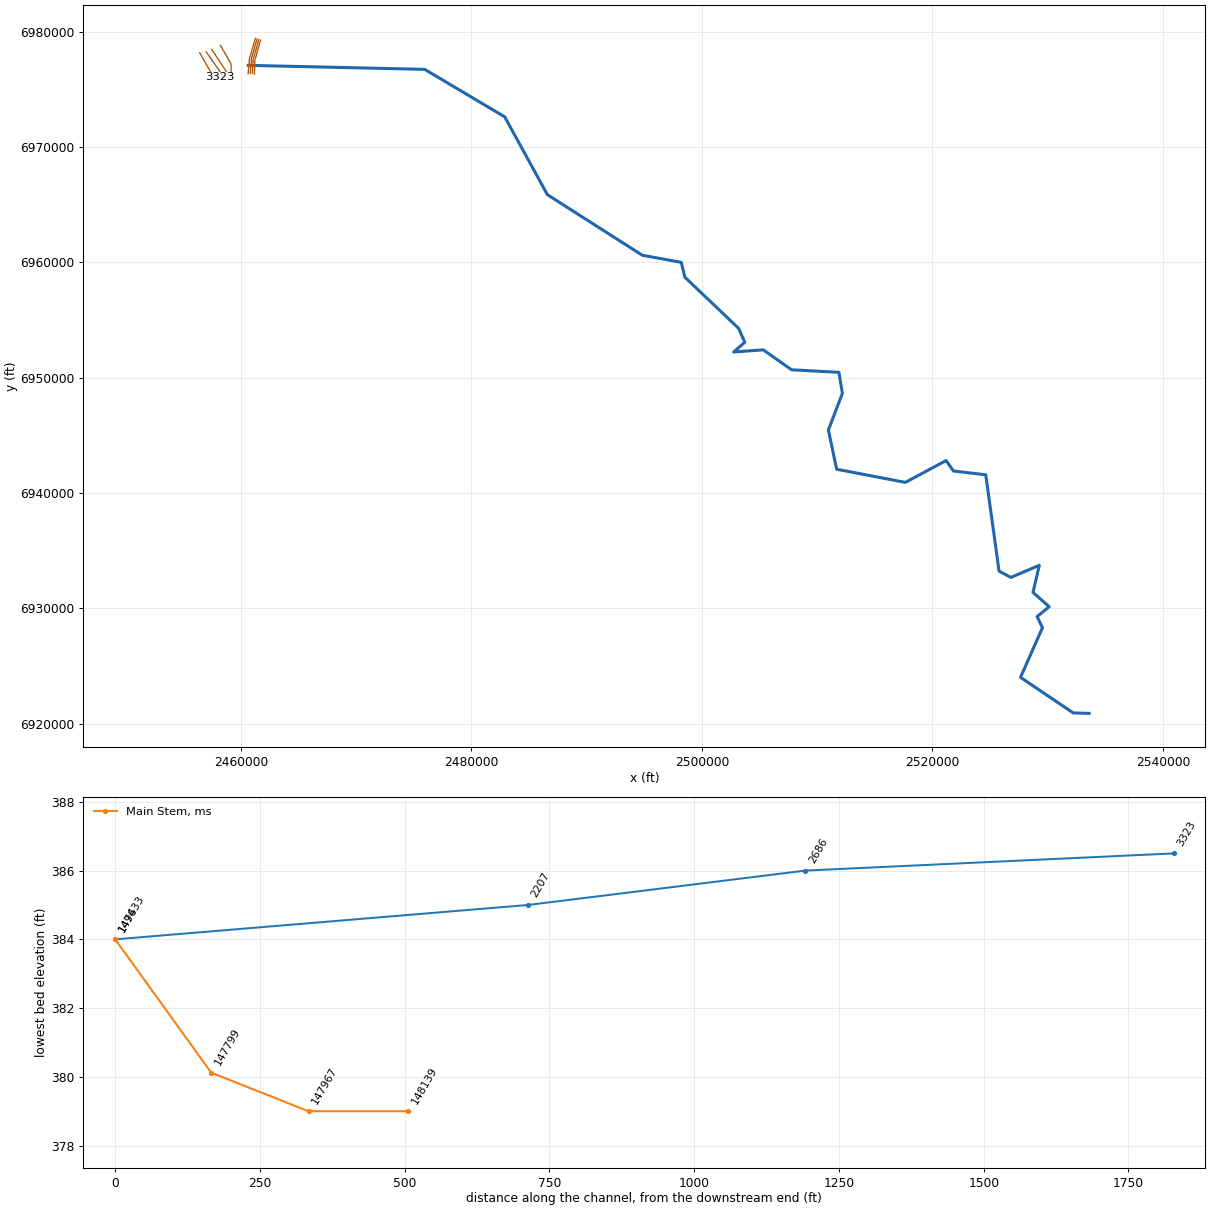
HEC-RAS study CDC_Consolidated_Model.prj: Upper Trinity CDC Consolidated Model

--- CDC_Consolidated_Model.g04 (geometry) --- (continued)

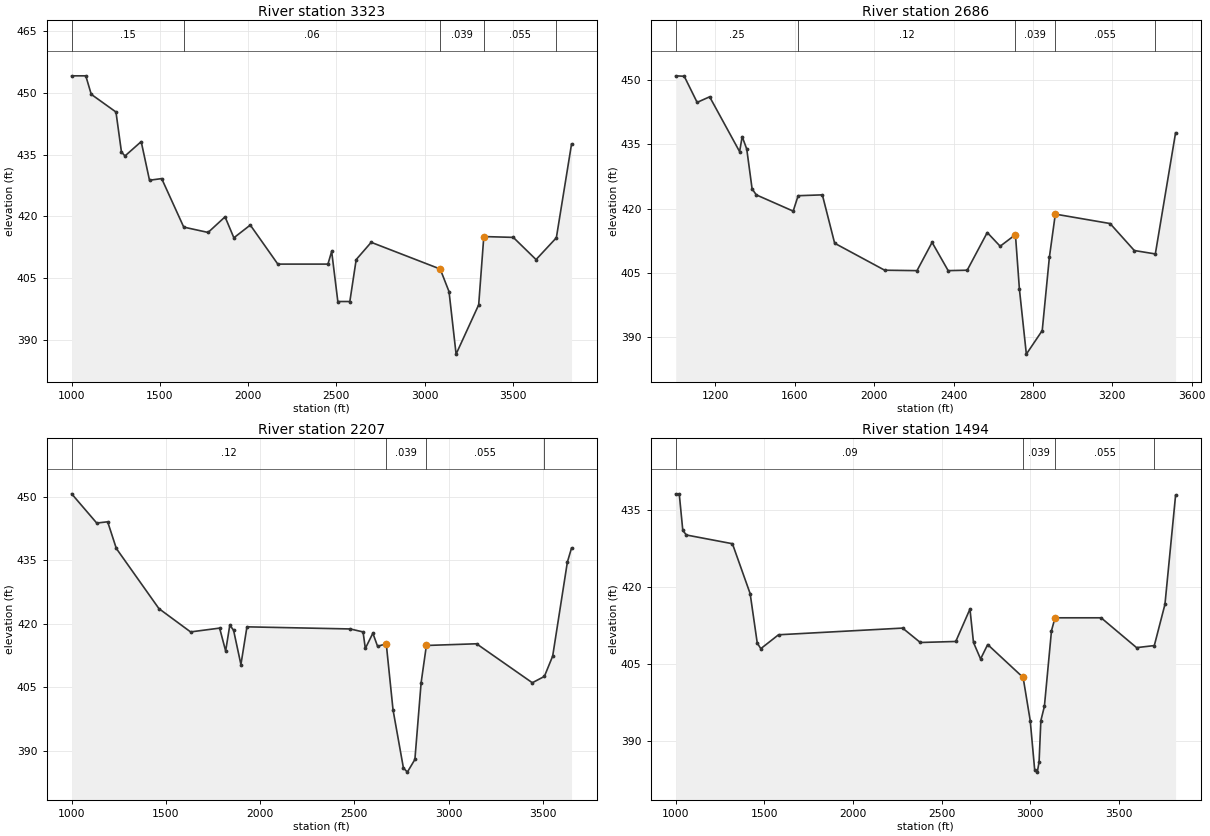
Type RM Length L Ch R = 1 ,3323    ,620,636,430
BEGIN DESCRIPTION:
This cross section corresponds to cross section 3323 of the non-georeferenced CDC model which was the source of this model.
END DESCRIPTION:
XS GIS Cut Line= 6
  2456438.118982 6978157.4850431 2456667.1680655 6977756.3920132
 2456942.0343137 6977275.0826084 2457216.9087639 6976793.7755002
 2457445.9768753 6976392.6880477 2458166.4659199 6976025.6559734
#Sta/Elev= 30
    1000   454.2    1080   454.2    1111   449.7    1251   445.4    1282   435.7
    1302   434.7    1394   438.2    1441   428.8    1510   429.2    1635   417.4
    1773   416.1    1869   419.9    1919   414.8    2012   417.9    2168   408.4
    2452   408.4    2473   411.5    2508   399.3    2576   399.3    2612   409.5
    2697   413.7    3088   407.2    3138   401.7    3178   386.5    3306   398.5
    3335   415.1    3502   414.9    3631   409.5    3746   414.8    3832   437.6
#Mann= 5 ,-1,0
    1000     .15       0    1635     .06       0    3088    .039       0
    3335    .055       0    3746     .03       0
#Block Obstruct= 2 , 0
            2729   414.1
Bank Sta=3088,3335
XS Rating Curve= 0 ,0
Exp/Cntr=0.5,0.3

Type RM Length L Ch R = 1 ,2686    ,480,479,480
BEGIN DESCRIPTION:
This cross section corresponds to cross section 2687 of the non-georeferenced CDC model which was the source of this model.
END DESCRIPTION:
XS GIS Cut Line= 6
  2456998.734003 6978241.2548887 2457373.5990673 6977703.7891001
 2457587.8128777 6977396.6676671 2457748.4759423 6977166.3279047
 2458069.8092891 6976705.6500202 2458444.7091298 6976168.1970269
#Sta/Elev= 30
    1000     451    1043   450.9    1108   444.8    1171   446.1    1322   433.3
    1335   436.8    1358   433.9    1385   424.6    1406   423.2    1592   419.4
    1617     423    1739   423.2    1801   411.9    2053   405.6    2216   405.5
    2292   412.1    2373   405.5    2469   405.6    2570   414.4    2635   411.2
    2712   413.9    2732   401.2    2767     386    2847   391.5    2883   408.6
    2913   418.7    3189   416.5    3311   410.2    3417   409.4    3519   437.7
#Mann= 5 ,-1,0
    1000     .25       0    1617     .12       0    2712    .039       0
    2913    .055       0    3417     .03       0
#Block Obstruct= 2 , 0
            2570   414.4
Bank Sta=2712,2913
XS Rating Curve= 0 ,0
Exp/Cntr=0.5,0.3

Type RM Length L Ch R = 1 ,2207    ,849,713,499
BEGIN DESCRIPTION:
This cross section corresponds to cross section 2208 of the non-georeferenced CDC model which was the source of this model.
END DESCRIPTION:
XS GIS Cut Line= 6
  2457478.800956 6978447.4578883 2457847.0571099 6977893.3622117
 2458215.3257303 6977339.2708002  2458373.158748 6977101.8044117
 2458583.6064898 6976785.1839819 2458951.9000446 6976231.1011006
#Sta/Elev= 30
    1000   450.7    1133   443.8    1191   444.1    1237   437.8    1463   423.6
    1631   418.1    1785     419    1817   413.6    1839   419.7    1859   418.5
    1898   410.4    1930   419.3    2478   418.8    2546   418.1    2558   414.2
    2598   417.8    2623   414.7    2669   415.3    2705   399.7    2760     386
    2781     385    2821     388    2854   406.1    2882   414.9    3148   415.3
    3444   406.1    3508   407.6    3552   412.4    3630   434.6    3652   437.9
#Mann= 4 ,-1,0
    1000     .12       0    2669    .039       0    2882    .055       0
    3508     .03       0
#Block Obstruct= 2 , 0
            1930   419.3
Bank Sta=2669,2882
XS Rating Curve= 0 ,0
Exp/Cntr=0.5,0.3

Type RM Length L Ch R = 1 ,1494    ,1494,1494,1494
BEGIN DESCRIPTION:
This cross section corresponds to cross section 1494 of the non-georeferenced CDC model which was the source of this model.
END DESCRIPTION:
XS GIS Cut Line= 6
  2458223.312919 6978824.4259664 2458635.0010721 6978109.9168967
 2459046.7069416 6977395.4130764 2459133.1421362 6977230.1118978
 2459164.8340019 6977120.8440717  2459164.834001 6976250.4111013
#Sta/Elev= 30
    1000   438.1    1020   438.1    1040     431    1060   430.1    1320   428.4
    1420   418.7    1460   409.1    1480     408    1580   410.7    2280     412
    2380   409.2    2580   409.4    2660   415.7    2680   409.2    2720     406
    2760   408.8    2960   402.4    3000     394    3025   384.5    3040     384
    3050     386    3060     394    3080   396.8    3120   411.5    3140     414
    3400     414    3600   408.2    3700   408.6    3760   416.6    3820   437.8
#Mann= 4 ,-1,0
    1000     .09       0    2960    .039       0    3140    .055       0
    3700     .03       0
Bank Sta=2960,3140
XS Rating Curve= 0 ,0
Exp/Cntr=0.5,0.3

River Reach=Main Stem       ,ms
Reach XY= 30
       2460651.9      6977070.51      2475956.02        6976723.
      2482902.21      6972603.81      2486601.03      6965861.25
      2494841.05      6960609.03      2498218.33      6959996.81
      2498526.81      6958713.48      2503198.36      6954269.99
      2503727.53      6953066.56      2502765.36      6952229.44
      2505335.43      6952409.66      2507789.67       6950684.6
      2511891.32      6950462.85      2512197.38      6948638.96
      2510979.79      6945468.76      2511698.66      6942064.93
      2517657.38      6940924.33      2521195.08      6942816.26
      2521824.01      6941912.62      2524634.19      6941582.52
      2525786.79      6933236.59      2526809.67      6932685.92
       2529281.6      6933737.03      2528731.26      6931389.82
      2530135.73      6930151.29      2529089.21      6929289.76
      2529552.65      6928333.05      2527652.49        6924023.
       2532218.2      6920945.83      2533600.64      6920903.28

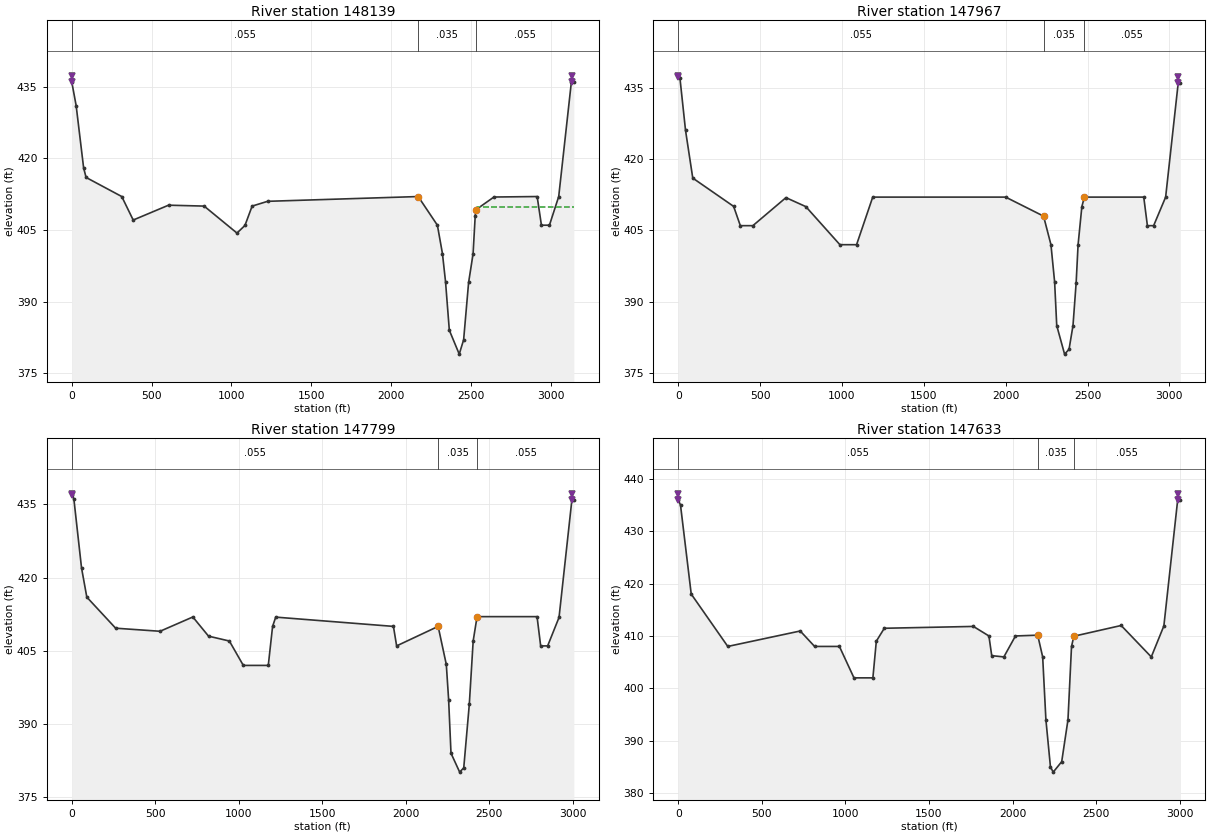
Type RM Length L Ch R = 1 ,148139  ,167,172,175
BEGIN DESCRIPTION:
148136.  148136
Confluence of Elm Fork and West Fork
END DESCRIPTION:
XS GIS Cut Line= 3
2461264.280915836979412.294868132460759.000102256977671.00012238
2460636.75592417 6976344.2032353
#Sta/Elev= 30
       0     436   27.42  431.05   74.28     418   89.61     416  313.24     412
  384.89  407.08  606.27  410.19  829.29     410 1035.02  404.35 1085.06  405.95
 1129.96     410 1227.08     411 2170.34     412 2290.62     406 2322.29  400.07
 2341.66  394.16 2365.42     384 2427.49     379 2455.02     382 2486.18     394
 2514.23     400 2527.64     408 2533.03  409.26 2644.86   411.9 2915.71     412
 2942.45     406 2992.59     406 3050.72     412 3130.08     436 3145.54     436
#Mann= 3 ,0,0
       0    .055       0 2170.34    .035       0 2533.03    .055       0
Levee=-1,0,437.28,-1,3131,437.28,,
#XS Ineff= 2 , 0
       0 2290.62     406 2540.55       0  409.88
Permanent Ineff=
       F       F
Bank Sta=2170.34,2533.03
XS Rating Curve= 0 ,0
Exp/Cntr=0.3,0.1

Type RM Length L Ch R = 1 ,147967  ,163,168,171
BEGIN DESCRIPTION:
This cross section corresponds to cross section 147969 of the non-georeferenced CDC model which was the source of this model.
END DESCRIPTION:
XS GIS Cut Line= 3
2461413.161851676979361.517738712460918.000112336977632.00020038
2460822.115789686976367.85607514
#Sta/Elev= 30
       0  437.49   10.47     437   44.64     426   88.74     416  338.39  410.05
  379.26     406   455.9     406  657.92  411.89  779.46     410  987.48     402
 1089.32     402    1188     412 1999.98     412 2231.44     408 2276.59     402
 2299.04  394.18 2311.97     385  2359.8     379 2387.04     380 2411.26     385
 2430.53     394 2442.25  401.95 2465.38     410 2480.93     412 2843.47     412
 2865.69     406 2903.83     406 2977.13     412 3053.97     436 3066.78     436
#Mann= 3 ,0,0
       0    .055       0 2231.44    .035       0 2480.93    .055       0
Levee=-1,0,437.23,-1,3054,437.23,,
#XS Ineff= 2 , 0
       0 2231.44     408 2480.93       0     412
Permanent Ineff=
       F       F
Bank Sta=2231.44,2480.93
XS Rating Curve= 0 ,0
Exp/Cntr=0.3,0.1

Type RM Length L Ch R = 1 ,147799  ,161,166,169
BEGIN DESCRIPTION:
This cross section corresponds to cross section 147802 of the non-georeferenced CDC model which was the source of this model.
END DESCRIPTION:
XS GIS Cut Line= 4
2461561.133012416979303.910242382461081.019143256977606.52912271
2461065.812152686977522.079160382461008.404459096976367.38986872
#Sta/Elev= 30
       0     437   12.43  436.17   58.38     422   90.06     416  262.61  409.63
  528.52     409   724.8  411.93  818.76     408  943.54     407 1027.03     402
 1176.51     402 1202.32     410 1221.06   411.9 1925.82     410 1944.87     406
 2193.43     410 2242.35  402.19 2256.17     395 2270.41     384 2322.33  380.12
 2346.76     381 2379.99     394 2403.15     407 2426.46     412 2785.63     412
 2807.23     406 2849.02     406 2917.22  411.84 2994.39     436  3005.9     436
#Mann= 3 ,0,0
       0    .055       0 2193.43    .035       0 2426.46    .055       0
Levee=-1,0,437.18,-1,2995,437.18,,
#XS Ineff= 2 , 0
       0 2193.43     410 2426.46       0     412
Permanent Ineff=
       F       F
Bank Sta=2193.43,2426.46
XS Rating Curve= 0 ,0
Exp/Cntr=0.3,0.1

Type RM Length L Ch R = 1 ,147633  ,156,160,164
BEGIN DESCRIPTION:
This cross section corresponds to cross section 147635 of the non-georeferenced CDC model which was the source of this model.
END DESCRIPTION:
XS GIS Cut Line= 4
2461708.768871996979249.326690142461239.662854856977567.40518522
2461220.866960676977484.465062382461186.256465586976313.02547613
#Sta/Elev= 30
       0     436   13.56     435    77.7     418  296.37     408  729.72  410.95
  815.68     408  964.02     408 1051.07     402 1164.27     402 1184.81     409
  1232.6  411.47 1765.53  411.82 1858.28     410  1875.1  406.24 1947.74     406
 2017.08     410 2150.12  410.15 2179.83     406 2199.16     394 2226.34     385
 2242.93     384 2293.67     386 2331.18     394  2352.4     408 2366.46  409.95
 2649.35     412 2829.49     406 2904.78  411.92 2987.45     436 3003.11     436
#Mann= 3 ,0,0
       0    .055       0 2150.12    .035       0 2366.46    .055       0
Levee=-1,0,437.14,-1,2988,437.14,,
#XS Ineff= 2 , 0
       0 2179.83     406  2352.4       0     408
Permanent Ineff=
       F       F
Bank Sta=2150.12,2366.46
XS Rating Curve= 0 ,0
Exp/Cntr=0.3,0.1