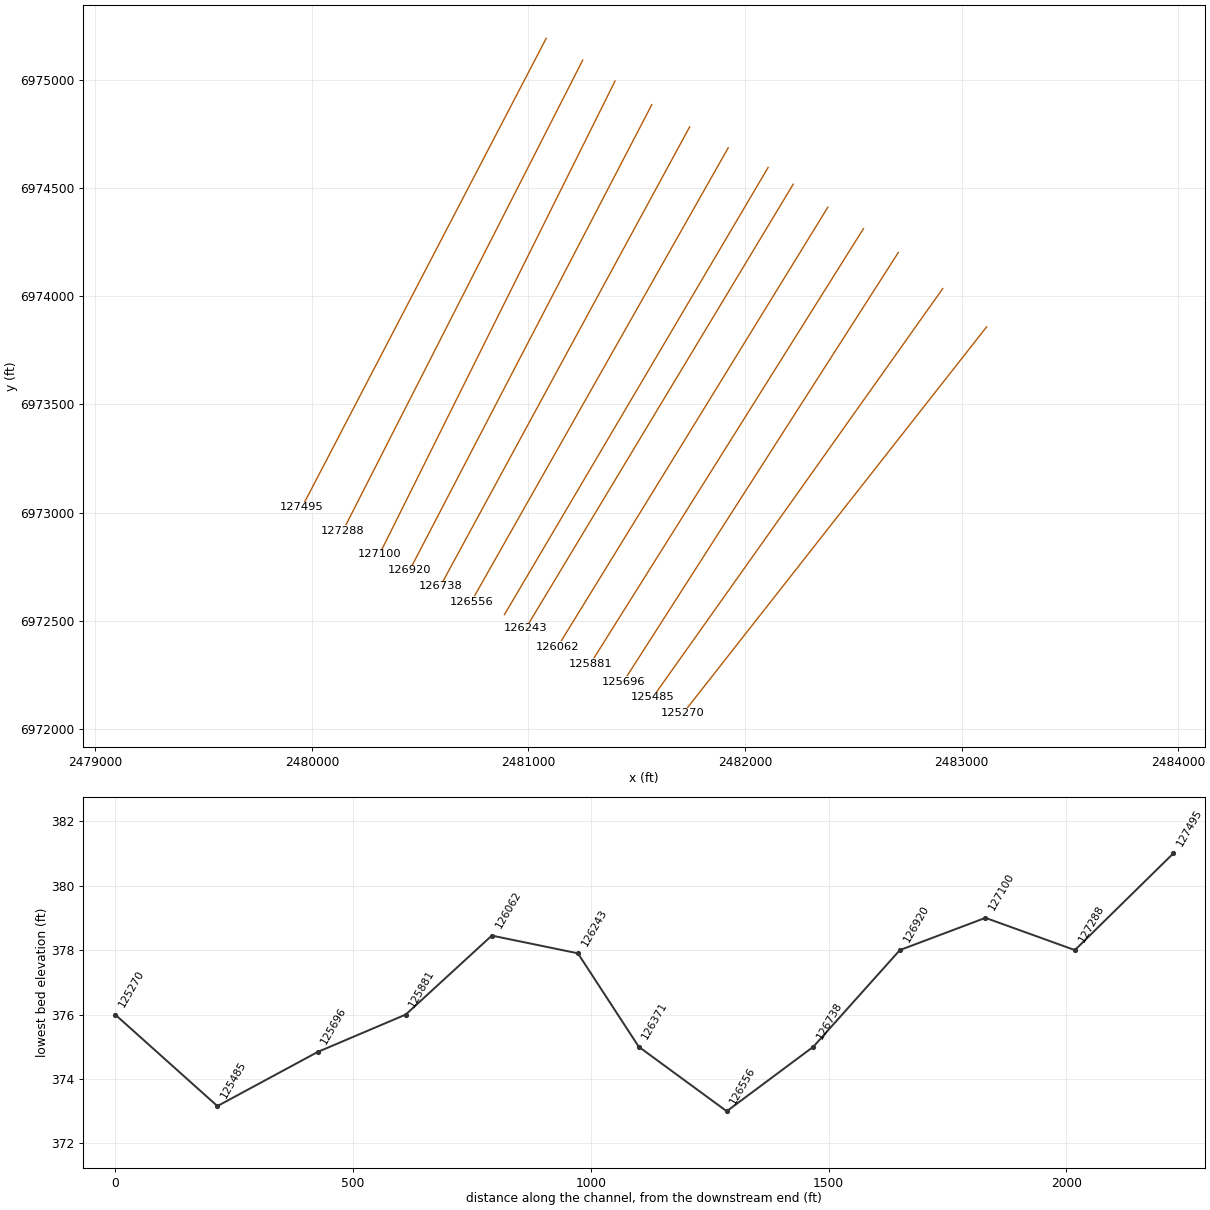
HEC-RAS study CDC_Consolidated_Model.prj: Upper Trinity CDC Consolidated Model

--- CDC_Consolidated_Model.g04 (geometry) --- (continued)

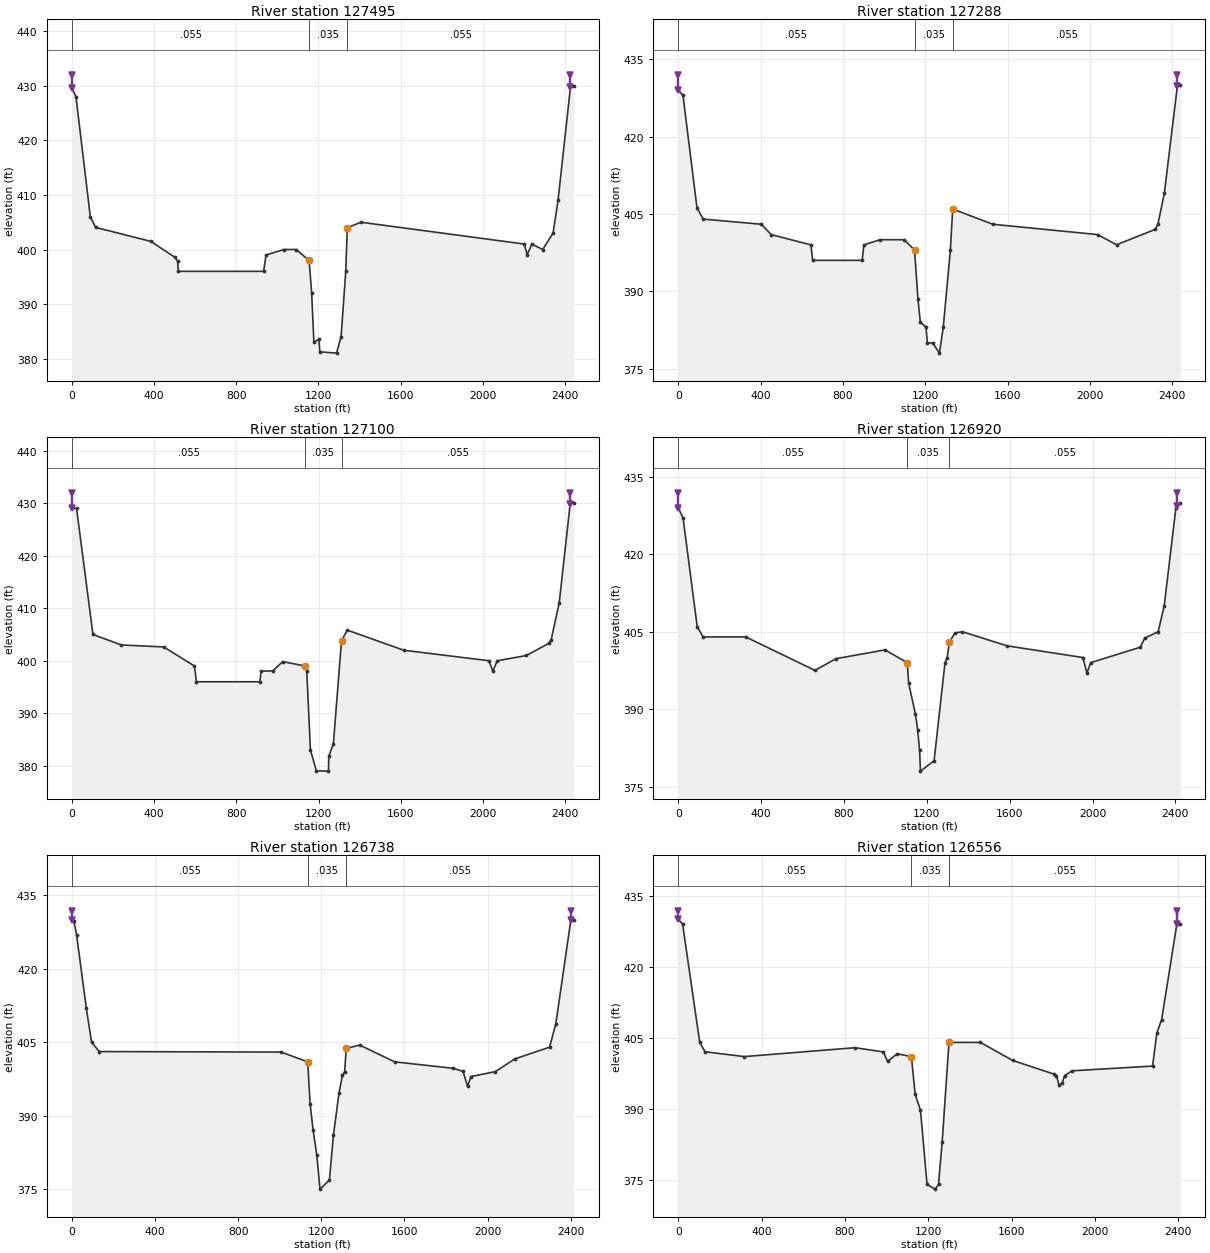
Type RM Length L Ch R = 1 ,127495  ,207,207,207
BEGIN DESCRIPTION:
This cross section corresponds to cross section 127549 of the non-georeferenced CDC model which was the source of this model.
END DESCRIPTION:
XS GIS Cut Line= 2
     2481082.152     6975191.303     2479953.925      6973023.83
#Sta/Elev= 30
       0  429.63   20.59     428   90.24  406.02  116.18  404.05   384.7  401.49
  502.85  398.55  514.82  397.87  518.95     396  933.86     396  945.38     399
 1032.49     400 1091.81     400 1155.08     398 1167.56     392 1178.33     383
  1202.3  383.54 1207.54  381.24 1288.82     381  1310.7     384 1333.48     396
 1340.93     404 1407.63     405 2202.45     401 2216.41  399.01 2238.72     401
 2291.87     400  2342.3     403  2366.6     409 2427.72     430 2443.53     430
#Mann= 3 ,0,0
       0    .055       0 1155.08    .035       0 1340.93    .055       0
Levee=-1,0,432.03,-1,2427,432.03,,
#XS Ineff= 2 , 0
       0 1155.08     398 1340.93       0     404
Permanent Ineff=
       F       F
Bank Sta=1155.08,1340.93
XS Rating Curve= 0 ,0
Exp/Cntr=0.3,0.1

Type RM Length L Ch R = 1 ,127288  ,188,188,188
BEGIN DESCRIPTION:
This cross section corresponds to cross section 127352 of the non-georeferenced CDC model which was the source of this model.
END DESCRIPTION:
XS GIS Cut Line= 2
     2481250.969     6975090.898     2480144.082     6972917.049
#Sta/Elev= 30
       0     429   23.07     428   91.03   406.2   121.2     404  404.11     403
  451.13     401  644.84     399  652.91     396  893.67     396  901.99     399
   980.9     400 1098.21     400    1148     398 1164.73   388.5 1176.11  384.07
 1203.67     383 1210.73     380 1236.74  379.96 1269.14     378 1287.66     383
 1322.16  397.94 1333.55  405.95 1528.27     403 2037.25     401 2129.48  399.02
 2317.06     402 2330.57     403 2361.83     409 2425.68     430 2439.43     430
#Mann= 3 ,0,0
       0    .055       0    1148    .035       0 1333.55    .055       0
Levee=-1,0,431.99,-1,2425,431.99,,
#XS Ineff= 2 , 0
       0    1148     398 1333.55       0  405.95
Permanent Ineff=
       F       F
Bank Sta=1148,1333.55
XS Rating Curve= 0 ,0
Exp/Cntr=0.3,0.1

Type RM Length L Ch R = 1 ,127100  ,180,180,180
BEGIN DESCRIPTION:
This cross section corresponds to cross section 127155 of the non-georeferenced CDC model which was the source of this model.
END DESCRIPTION:
XS GIS Cut Line= 2
      2481400.01     6974993.947     2480312.725     6972808.295
#Sta/Elev= 30
       0  428.99    23.3     429  102.95     405  240.96     403  446.97  402.63
  596.46     399  606.23     396  914.32     396  920.83     398  977.78  398.09
 1025.51  399.83 1135.44     399 1142.52  398.06 1160.42     383 1189.43  379.05
 1248.19     379 1249.65  381.83 1271.94  384.18 1311.57  403.84 1339.77  405.83
 1614.04     402 2028.74     400 2047.24     398 2068.69     400 2210.08     401
 2320.98  403.34 2330.95     404 2370.02     411 2423.66     430 2441.16     430
#Mann= 3 ,0,0
       0    .055       0 1135.44    .035       0 1311.57    .055       0
Levee=-1,0,431.95,-1,2423,431.95,,
#XS Ineff= 2 , 0
       0 1135.44     399 1311.57       0  403.84
Permanent Ineff=
       F       F
Bank Sta=1135.44,1311.57
XS Rating Curve= 0 ,0
Exp/Cntr=0.3,0.1

Type RM Length L Ch R = 1 ,126920  ,182,182,182
BEGIN DESCRIPTION:
This cross section corresponds to cross section 126973 of the non-georeferenced CDC model which was the source of this model.
END DESCRIPTION:
XS GIS Cut Line= 2
     2481569.844     6974884.842     2480451.952     6972734.401
#Sta/Elev= 30
       0     429   23.42     427   91.44     406  119.72     404  325.38     404
  660.06  397.51  761.45  399.78  998.33  401.48 1105.83     399 1111.99   395.1
 1145.25     389 1155.74     386 1165.13     382 1169.37     378 1235.04     380
  1287.8     399  1298.3     400 1308.88     403  1336.2  404.76 1371.84     405
 1587.14  402.27 1953.34     400 1972.99     397  1990.5     399 2230.43     402
 2251.87  403.76 2316.81     405  2345.9     410 2402.44     429 2423.65     430
#Mann= 3 ,0,0
       0    .055       0 1105.83    .035       0 1308.88    .055       0
Levee=-1,0,431.9,-1,2408,431.9,,
#XS Ineff= 2 , 0
       0 1105.83     399 1308.88       0     403
Permanent Ineff=
       F       F
Bank Sta=1105.83,1308.88
XS Rating Curve= 0 ,0
Exp/Cntr=0.3,0.1

Type RM Length L Ch R = 1 ,126738  ,182,182,182
BEGIN DESCRIPTION:
This cross section corresponds to cross section 126791 of the non-georeferenced CDC model which was the source of this model.
END DESCRIPTION:
XS GIS Cut Line= 2
     2481744.598     6974782.275     2480593.281     6972660.014
#Sta/Elev= 30
       0     430   10.42  429.69   23.08     427   69.81     412   95.19     405
  132.34   403.1 1006.61     403 1134.74     401 1145.99  392.47 1160.64     387
 1178.23     382 1193.78     375 1238.99  376.86 1258.32     386 1284.85  394.55
 1301.27  398.23 1312.32     399 1319.86  403.76 1385.21  404.42  1552.2     401
 1834.87  399.68 1881.95  399.04  1903.3     396 1919.76     398 2036.72     399
  2130.6   401.6  2297.8     404 2327.77  408.77  2400.1     430 2414.44     430
#Mann= 3 ,0,0
       0    .055       0 1134.74    .035       0 1319.86    .055       0
Levee=-1,0,431.85,-1,2400,431.85,,
#XS Ineff= 2 , 0
       0 1134.74     401 1319.86       0  403.76
Permanent Ineff=
       F       F
Bank Sta=1134.74,1319.86
XS Rating Curve= 0 ,0
Exp/Cntr=0.3,0.1

Type RM Length L Ch R = 1 ,126556  ,186,185,186
BEGIN DESCRIPTION:
This cross section corresponds to cross section 126609 of the non-georeferenced CDC model which was the source of this model.
END DESCRIPTION:
XS GIS Cut Line= 2
     2481922.692     6974685.741     2480736.192       6972588.3
#Sta/Elev= 30
       0     430    20.9     429  103.18     404  128.58  402.02  316.87     401
  847.99  402.88  984.09     402  1004.9     400 1050.84   401.6  1119.3     401
 1137.01     393 1162.65  389.69 1194.21     374  1232.9     373 1249.18     374
  1266.9     383 1299.49     404 1450.58     404 1604.91  400.19 1803.54   397.3
  1815.1     397 1827.92     395 1842.03  395.33 1854.56     397  1890.5     398
 2276.55     399 2297.26     406 2320.27  408.83 2393.15     429 2409.78     429
#Mann= 3 ,0,0
       0    .055       0  1119.3    .035       0 1299.49    .055       0
Levee=-1,0,431.8,-1,2393,431.8,,
#XS Ineff= 2 , 0
       0  1119.3     401 1299.49       0     404
Permanent Ineff=
       F       F
Bank Sta=1119.3,1299.49
XS Rating Curve= 0 ,0
Exp/Cntr=0.3,0.1

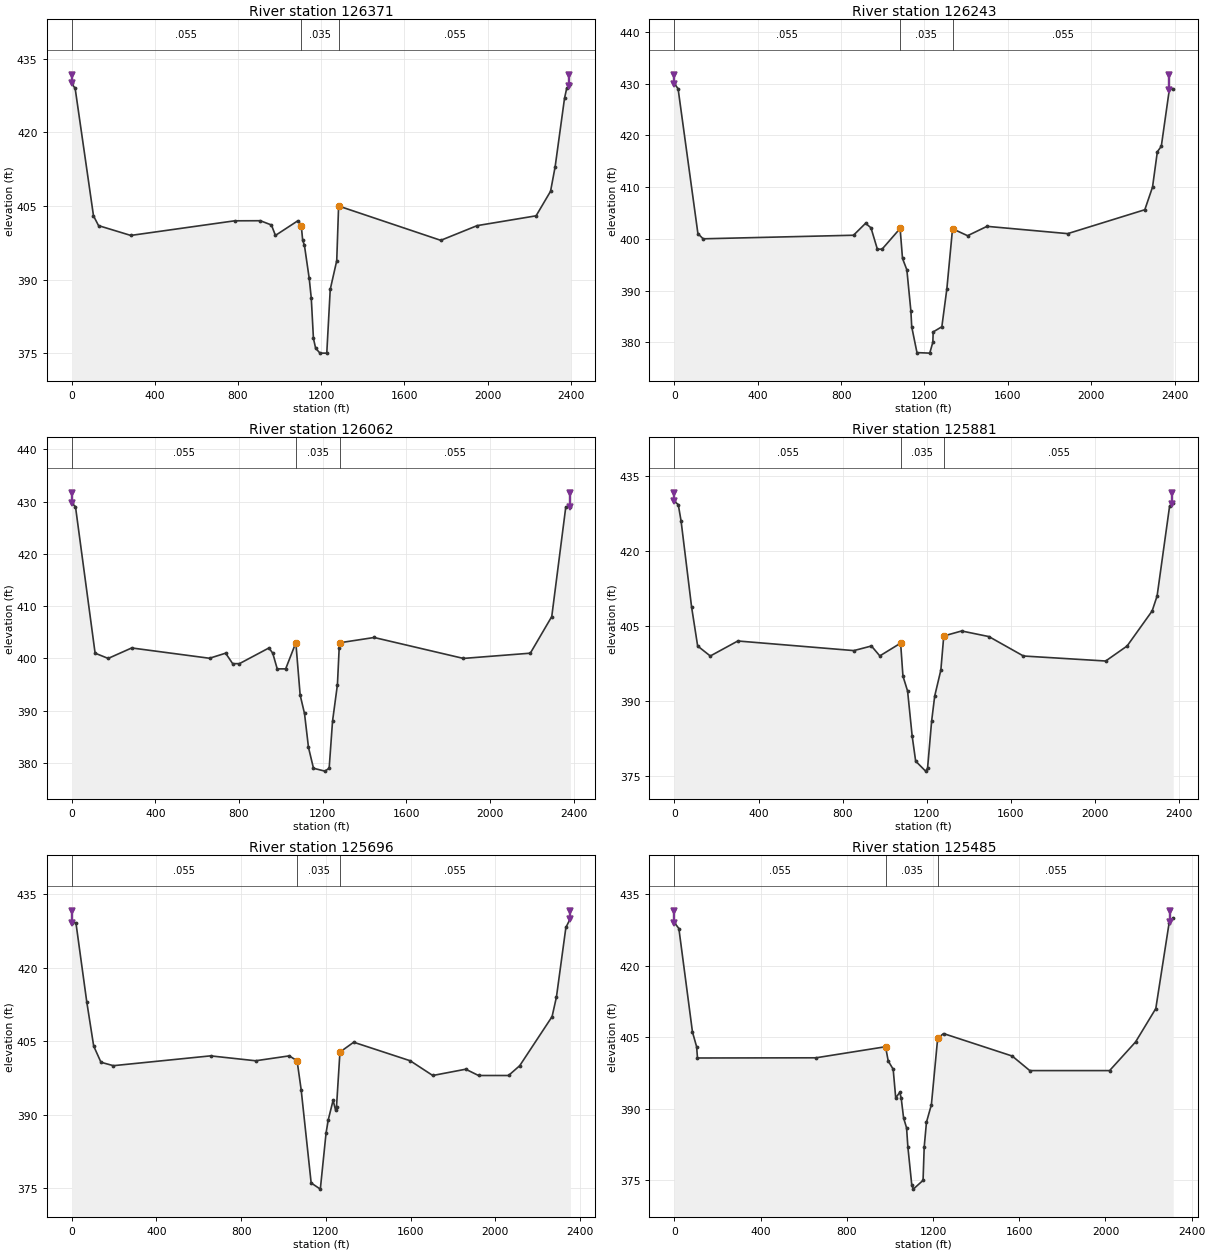
Type RM Length L Ch R = 1 ,126371  ,129,128,127
BEGIN DESCRIPTION:
This cross section corresponds to cross section 126428 of the non-georeferenced CDC model which was the source of this model.
END DESCRIPTION:
XS GIS Cut Line= 2
     2482106.809     6974594.653     2480889.298     6972528.481
#Sta/Elev= 30
       0     430   17.01     429  105.24     403  129.53     401  284.45     399
  783.69  401.98  907.43     402  960.81  401.13  979.98     399 1088.25     402
 1104.26     401 1111.04     398 1119.41     397 1142.57  390.22 1152.37  386.22
 1162.79     378 1173.34     376 1194.32     375 1226.93     375 1243.56     388
 1274.82  393.85 1283.77     405    1775     398    1950     401 2233.37     403
 2302.87     408 2324.96     413 2370.04  426.96 2380.55     429 2398.21  429.88
#Mann= 3 ,0,0
       0    .055       0 1104.26    .035       0 1283.77    .055       0
Levee=-1,0,431.75,-1,2390,431.75,,
#XS Ineff= 2 , 0
       0 1104.26     401 1283.77       0     405
Permanent Ineff=
       F       F
Bank Sta=1104.26,1283.77
XS Rating Curve= 0 ,0
Exp/Cntr=0.3,0.1

Type RM Length L Ch R = 1 ,126243  ,183,181,180
BEGIN DESCRIPTION:
This cross section corresponds to cross section 126246 of the non-georeferenced CDC model which was the source of this model.
END DESCRIPTION:
XS GIS Cut Line= 2
2482222.759011926974517.456560722480988.643369916972466.37142405
#Sta/Elev= 30
       0     430   17.59     429  112.69     401  137.71     400  859.38  400.69
   917.4     403   943.3  402.12  973.88     398  996.55     398 1083.09     402
 1094.54  396.21 1115.46     394 1134.86     386 1138.74     383 1163.98     378
 1225.32   377.9 1240.11     380 1241.78     382 1283.38     383  1307.4  390.32
 1334.68  401.94 1406.91   400.6 1500.08  402.41 1887.32     401 2257.46  405.62
 2294.48     410 2317.63  416.83  2336.6  417.89 2375.67     429 2393.74     429
#Mann= 3 ,0,0
       0    .055       0 1083.09    .035       0 1334.68    .055       0
Levee=-1,0,431.7,-1,2375,431.7,,
#XS Ineff= 2 , 0
       0 1083.09     402 1334.68       0  401.94
Permanent Ineff=
       F       F
Bank Sta=1083.09,1334.68
XS Rating Curve= 0 ,0
Exp/Cntr=0.3,0.1

Type RM Length L Ch R = 1 ,126062  ,183,181,180
BEGIN DESCRIPTION:
This cross section corresponds to cross section 126065 of the non-georeferenced CDC model which was the source of this model.
END DESCRIPTION:
XS GIS Cut Line= 2
2482382.731132926974411.261891222481134.383892096972378.97560146
#Sta/Elev= 30
       0  429.74    18.6     429   112.4     401  174.88     400  287.28     402
  659.41  400.03  736.54     401  770.14     399  802.56     399  943.62     402
  961.81     401  983.27     398 1023.61     398 1072.27     403 1092.88     393
  1113.7  389.47 1132.67     383 1156.59     379 1210.99  378.45 1231.61     379
 1247.75     388 1271.16     395 1279.49     402 1283.27     403 1446.72     404
 1873.47     400 2193.54     401 2296.03     408 2363.27     429 2385.07     429
#Mann= 3 ,0,0
       0    .055       0 1072.27    .035       0 1283.27    .055       0
Levee=-1,0,431.66,-1,2385.07,431.66,,
#XS Ineff= 2 , 0
       0 1072.27     403 1283.27       0     403
Permanent Ineff=
       F       F
Bank Sta=1072.27,1283.27
XS Rating Curve= 0 ,0
Exp/Cntr=0.3,0.1

Type RM Length L Ch R = 1 ,125881  ,187,185,184
BEGIN DESCRIPTION:
This cross section corresponds to cross section 125884 of the non-georeferenced CDC model which was the source of this model.
END DESCRIPTION:
XS GIS Cut Line= 2
 2482547.0582321 6974312.0183233 2481286.24185616972301.66571672
#Sta/Elev= 30
       0  429.89   18.21  429.25   31.53     426   81.68  408.77  110.46     401
  170.51     399  301.57     402  853.52  400.08  937.28     401  977.14  399.02
 1076.11  401.57 1087.16     395 1109.26     392 1131.05     383 1147.65     378
 1194.91     376 1204.31  376.59 1223.67     386 1238.26     391 1267.52  396.19
 1281.37     403  1366.4     404 1496.14  402.88 1660.43     399 2051.73     398
 2153.66     401  2272.8     408 2296.41     411 2355.99     429 2373.01  429.53
#Mann= 3 ,0,0
       0    .055       0 1076.11    .035       0 1281.37    .055       0
Levee=-1,0,431.6,-1,2365,431.6,,
#XS Ineff= 2 , 0
       0 1076.11  401.57 1281.37       0     403
Permanent Ineff=
       F       F
Bank Sta=1076.11,1281.37
XS Rating Curve= 0 ,0
Exp/Cntr=0.3,0.1

Type RM Length L Ch R = 1 ,125696  ,230,211,191
BEGIN DESCRIPTION:
This cross section corresponds to cross section 125703 of the non-georeferenced CDC model which was the source of this model.
END DESCRIPTION:
XS GIS Cut Line= 2
2482708.258040936974202.146823882481438.91838801 6972219.1189658
#Sta/Elev= 30
       0  429.18   20.36  429.14   71.37  413.06  104.23     404  138.57   400.7
  197.03     400  655.75     402  868.54     401 1027.43     402 1064.42     401
 1083.61  395.11 1130.79   376.1 1174.11  374.84 1201.27  386.31 1211.77     389
 1234.43  392.95 1245.82     391 1250.51  391.63 1266.74  402.77  1331.6  404.78
 1598.39     401 1704.78     398  1860.4  399.28 1920.85     398 2062.59     398
  2115.4     400 2268.09     410 2288.73     414 2333.29  428.17 2354.49     430
#Mann= 3 ,0,0
       0    .055       0 1064.42    .035       0 1266.74    .055       0
Levee=-1,0,431.56,-1,2354,431.56,,
#XS Ineff= 2 , 0
       0 1064.42     401 1266.74       0  402.77
Permanent Ineff=
       F       F
Bank Sta=1064.42,1266.74
XS Rating Curve= 0 ,0
Exp/Cntr=0.3,0.1

Type RM Length L Ch R = 1 ,125485  ,236,215,196
BEGIN DESCRIPTION:
This cross section corresponds to cross section 125487 of the non-georeferenced CDC model which was the source of this model.
END DESCRIPTION:
XS GIS Cut Line= 2
2482913.179875176974035.094008392481574.781305256972147.21884713
#Sta/Elev= 30
       0     429    20.6  427.77   83.68  406.08  102.92     403  106.93  400.64
  656.51  400.68  979.48     403     992     400 1014.87  398.29 1026.66  392.28
 1045.57  393.45 1052.05  392.25 1063.23  388.07 1077.03     386 1083.07     382
 1101.23     374 1108.18  373.16 1153.54     375 1158.82  381.96  1169.3  387.17
 1192.21  390.86 1221.31  404.75 1248.39  405.76 1567.11  401.05  1648.7     398
    2019     398 2139.51     404 2233.38     411 2295.41     429 2314.17     430
#Mann= 3 ,0,0
       0    .055       0  979.48    .035       0 1221.31    .055       0
Levee=-1,0,431.48,-1,2299,431.48,,
#XS Ineff= 2 , 0
       0  979.48     403 1221.31       0  404.75
Permanent Ineff=
       F       F
Bank Sta=979.48,1221.31
XS Rating Curve= 0 ,0
Exp/Cntr=0.3,0.1

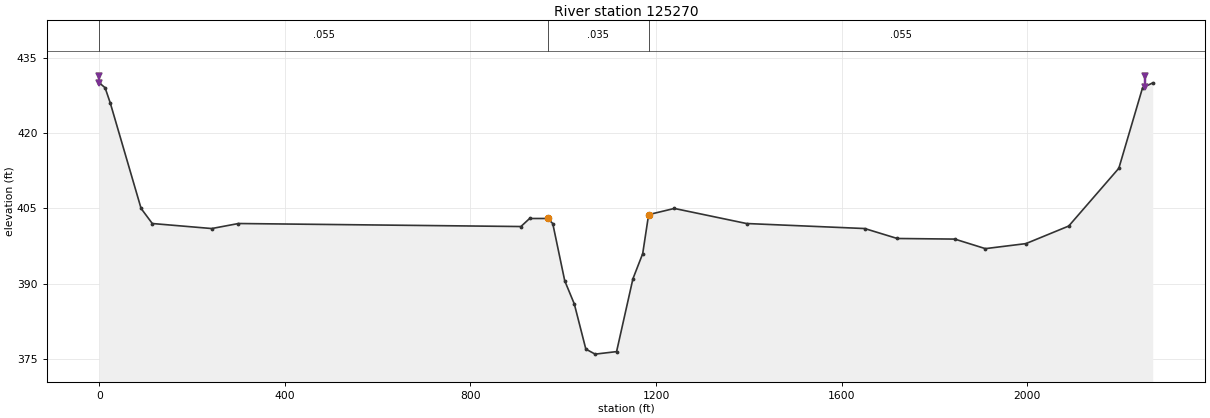
Type RM Length L Ch R = 1 ,125270  ,237,217,197
BEGIN DESCRIPTION:
This cross section corresponds to cross section 125272 of the non-georeferenced CDC model which was the source of this model.
END DESCRIPTION:
XS GIS Cut Line= 2
2483115.78576916 6973858.38734082481713.872234436972072.37188397
#Sta/Elev= 30
       0     430   12.39  429.03   23.55     426   90.01     405  114.13     402
  242.27     401  299.81     402  908.66   401.4   927.4     403  966.16     403
  977.28     402 1003.14  390.59 1023.71     386 1048.62     377 1068.67     376
 1114.87   376.5  1150.1     391 1171.15     396 1183.92  403.77 1239.35     405
 1394.93     402  1649.7     401 1719.82  399.02 1843.78   398.9 1909.76     397
 1997.11     398 2089.45   401.5 2197.42     413 2248.48     429 2270.51     430
#Mann= 3 ,0,0
       0    .055       0  966.16    .035       0 1183.92    .055       0
Levee=-1,0,431.4,-1,2253,431.4,,
#XS Ineff= 2 , 0
       0  966.16     403 1183.92       0  403.77
Permanent Ineff=
       F       F
Bank Sta=966.16,1183.92
XS Rating Curve= 0 ,0
Exp/Cntr=0.3,0.1