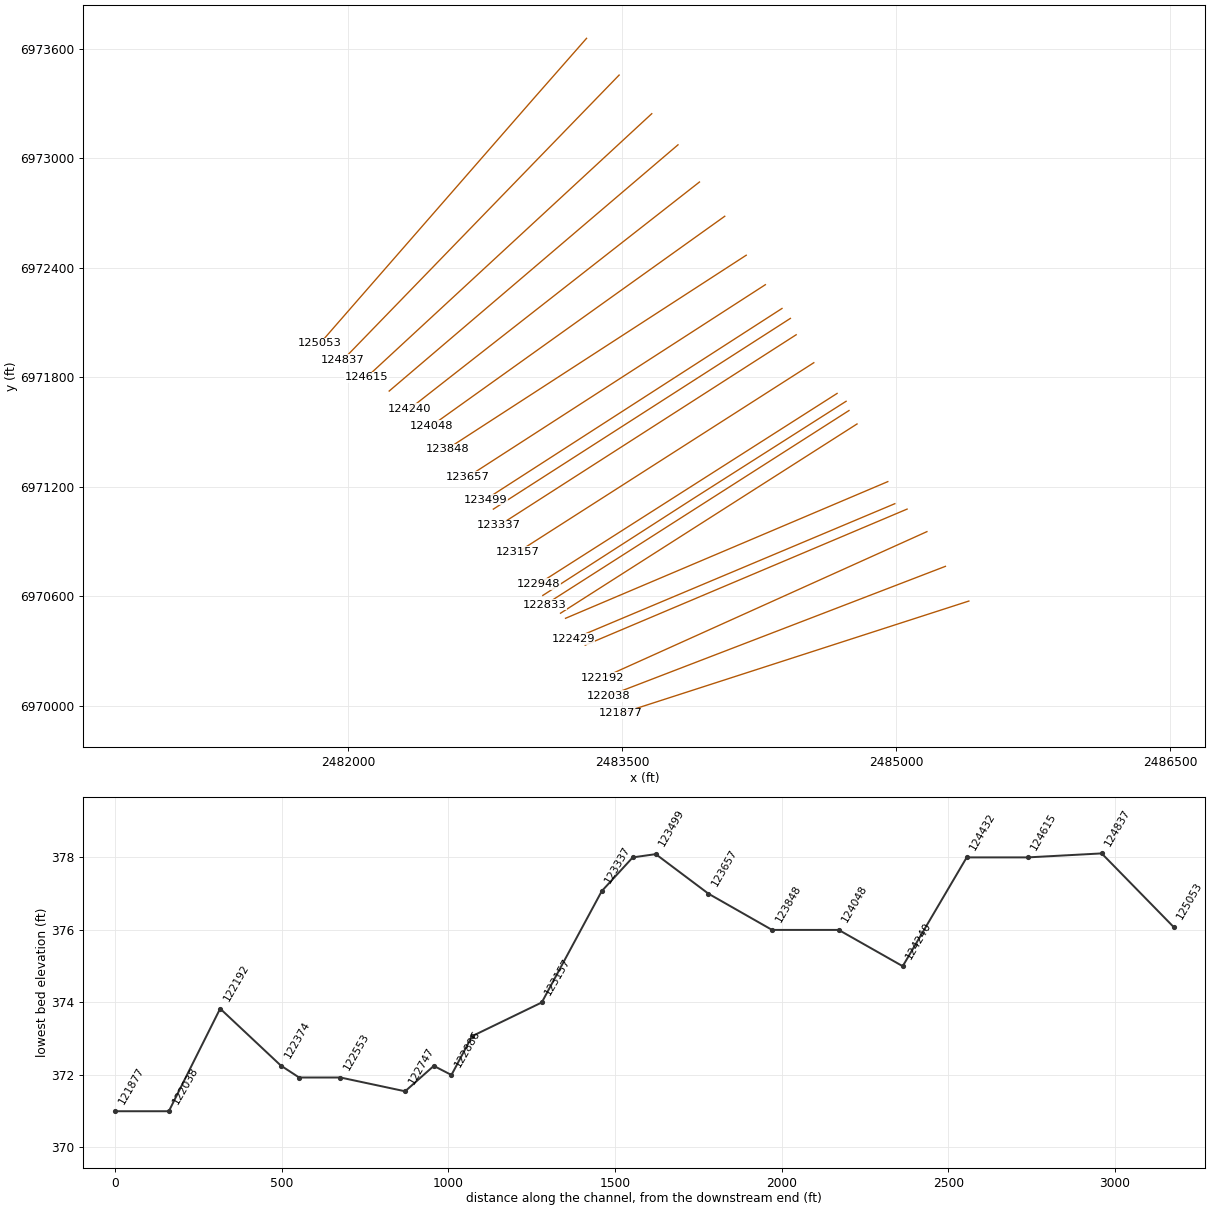
HEC-RAS study CDC_Consolidated_Model.prj: Upper Trinity CDC Consolidated Model

--- CDC_Consolidated_Model.g04 (geometry) --- (continued)

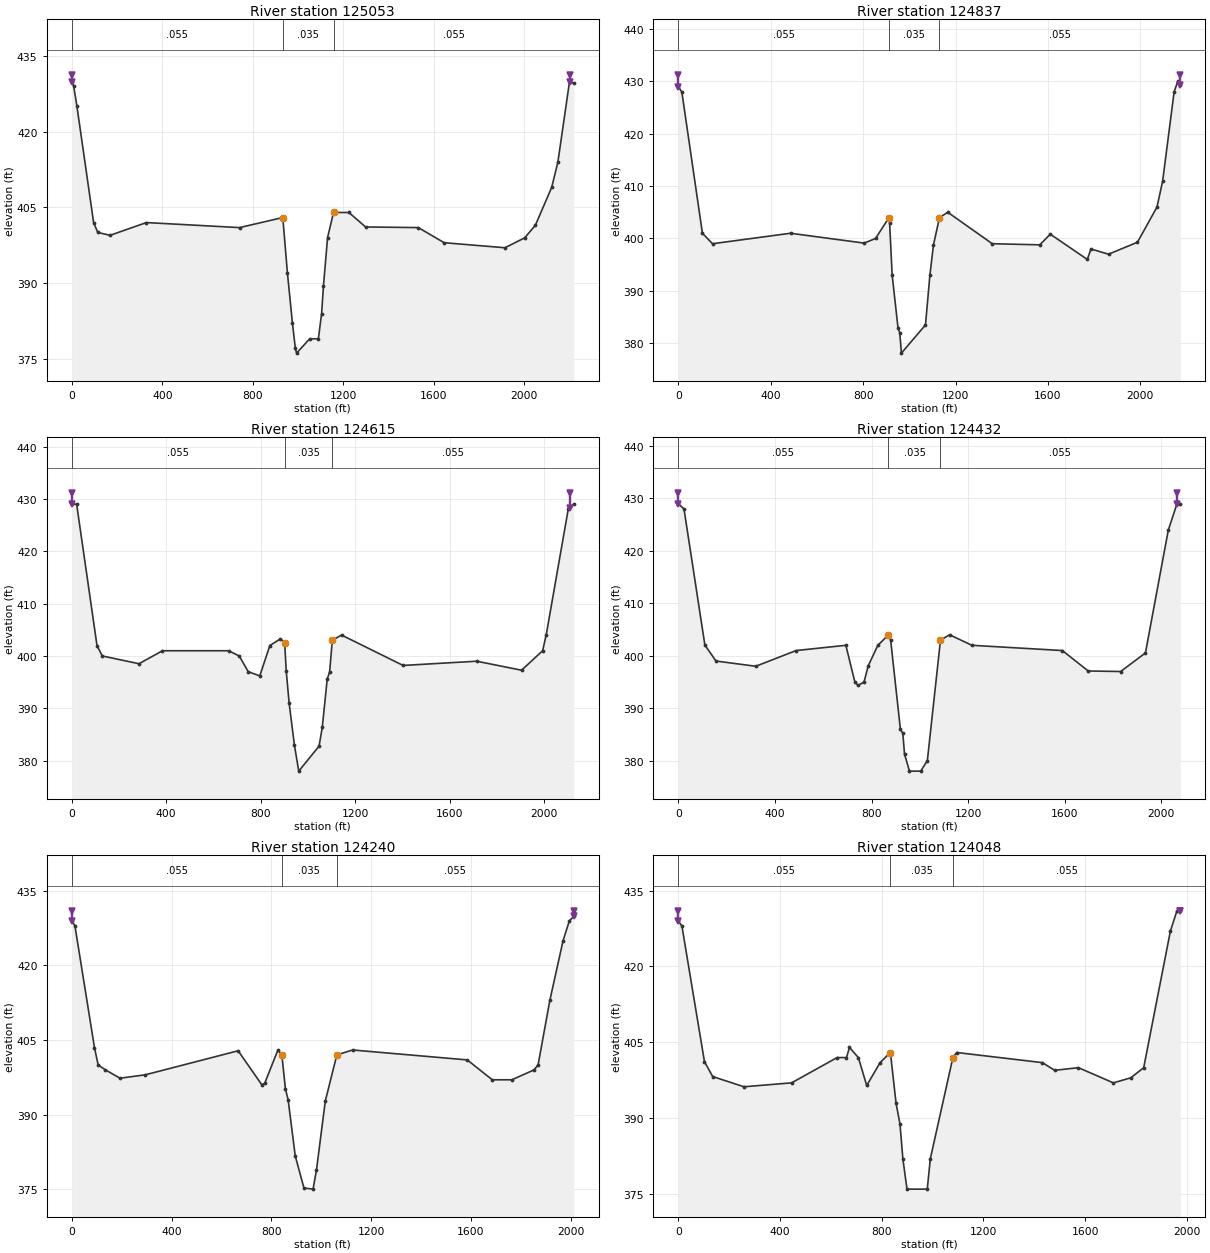
Type RM Length L Ch R = 1 ,125053  ,237,216,197
BEGIN DESCRIPTION:
This cross section corresponds to cross section 125056 of the non-georeferenced CDC model which was the source of this model.
END DESCRIPTION:
XS GIS Cut Line= 3
2483303.535393696973657.967137962483017.832881096973332.51109597
2481844.329978766971986.26674122
#Sta/Elev= 30
       0  429.98    8.23   429.1   22.41  425.21    96.5     402   115.1  400.04
  169.51  399.47  329.75     402  741.42     401  932.67     403  953.04  392.02
  975.14  382.07  988.24     377  993.51  376.08 1051.74  378.93 1089.85  378.92
 1104.19  383.93 1112.26  389.36  1130.5     399 1156.83     404 1224.75     404
 1298.63  401.13  1531.8     401  1645.9     398 1914.37     397 2001.84  398.97
 2049.16  401.48 2121.12     409 2148.47     414 2199.95     430 2218.98  429.68
#Mann= 3 ,0,0
       0    .055       0  932.67    .035       0 1156.83    .055       0
Levee=-1,0,431.33,-1,2200,431.33,,
#XS Ineff= 2 , 0
       0  932.67     403 1156.83       0     404
Permanent Ineff=
       F       F
Bank Sta=932.67,1156.83
XS Rating Curve= 0 ,0
Exp/Cntr=0.3,0.1

Type RM Length L Ch R = 1 ,124837  ,243,222,202
BEGIN DESCRIPTION:
This cross section corresponds to cross section 124841 of the non-georeferenced CDC model which was the source of this model.
END DESCRIPTION:
XS GIS Cut Line= 2
2483481.850325766973456.607632552481970.100724586971896.13896872
#Sta/Elev= 30
       0     429   15.54     428  104.63     401  148.33     399  485.87     401
   804.3  399.12  853.79     400  911.21  403.94  914.65     403  925.73     393
   950.9     383  958.58     382  965.68  378.11 1069.99   383.5 1088.94  392.96
  1104.5  398.76 1130.49     404  1166.5     405 1359.12     399  1564.5  398.79
 1610.14  400.82 1770.24     396 1785.81     398 1862.11     397 1987.09  399.28
 2071.75     406 2096.29  410.98 2145.89     428 2161.61     430 2172.66  429.32
#Mann= 3 ,0,0
       0    .055       0  911.21    .035       0 1130.49    .055       0
Levee=-1,0,431.25,-1,2172,431.25,,
#XS Ineff= 2 , 0
       0  911.21  403.94 1130.49       0     404
Permanent Ineff=
       F       F
Bank Sta=911.21,1130.49
XS Rating Curve= 0 ,0
Exp/Cntr=0.3,0.1

Type RM Length L Ch R = 1 ,124615  ,200,183,167
BEGIN DESCRIPTION:
This cross section corresponds to cross section 124626 of the non-georeferenced CDC model which was the source of this model.
END DESCRIPTION:
XS GIS Cut Line= 2
2483660.513026186973245.091979462482099.492198086971800.90261063
#Sta/Elev= 30
       0     429   20.63     429  106.81     402  129.28     400  284.84  398.52
  384.27     401  664.14     401  709.48     400  747.38     397  796.39  396.19
  839.02     402  883.51  403.26  901.61  402.57  908.43  397.11  920.68     391
  942.93     383  961.38     378 1047.42  382.77 1061.15  386.39 1081.98  395.58
 1092.17  396.95 1103.57     403 1142.68     404 1403.34  398.19 1714.97     399
 1905.16  397.28 1994.36     401 2009.47     404 2102.74     428 2126.61     429
#Mann= 3 ,0,0
       0    .055       0  901.61    .035       0 1103.57    .055       0
Levee=-1,0,431.17,-1,2109,431.17,,
#XS Ineff= 2 , 0
       0  901.61  402.57 1103.57       0     403
Permanent Ineff=
       F       F
Bank Sta=901.61,1103.57
XS Rating Curve= 0 ,0
Exp/Cntr=0.3,0.1

Type RM Length L Ch R = 1 ,124432  ,211,192,176
BEGIN DESCRIPTION:
This cross section corresponds to cross section 124434 of the non-georeferenced CDC model which was the source of this model.
END DESCRIPTION:
XS GIS Cut Line= 2
2483804.166282186973074.455509722482223.224562176971725.38340472
#Sta/Elev= 30
       0     429   23.87     428   110.3  402.05  156.21     399  320.79     398
  488.11     401  693.85     402  731.06     395  744.63  394.34  769.08     395
  786.73  398.11  826.32     402  870.26     404  879.26     403  919.56     386
  929.71  385.19  936.75  381.21  957.25     378 1003.67     378  1031.2     380
 1085.58     403 1123.54     404 1215.58     402 1589.96     401 1697.14   397.1
 1831.23     397 1933.96  400.54 2028.55  423.96 2064.59     429 2078.31     429
#Mann= 3 ,0,0
       0    .055       0  870.26    .035       0 1085.58    .055       0
Levee=-1,0,431.08,-1,2064,431.08,,
#XS Ineff= 2 , 0
       0  870.26     404 1085.58       0     403
Permanent Ineff=
       F       F
Bank Sta=870.26,1085.58
XS Rating Curve= 0 ,0
Exp/Cntr=0.3,0.1

Type RM Length L Ch R = 1 ,124240  ,211,192,176
BEGIN DESCRIPTION:
This cross section corresponds to cross section 124243 of the non-georeferenced CDC model which was the source of this model.
END DESCRIPTION:
XS GIS Cut Line= 2
2483921.602727096972870.755129712482336.794544996971629.19232413
#Sta/Elev= 30
       0     429   12.62     428   90.99  403.49  105.75     400   134.9     399
   193.2  397.32  294.45     398  667.11  402.84  762.01     396  773.37  396.26
   826.6     403   842.5     402  856.72  395.15  867.55     393  895.99  381.71
  930.99  375.22  967.54     375  981.14  378.82 1016.58  392.72 1062.86     402
 1126.05     403 1585.82     401 1686.18     397 1764.77     397 1853.82     399
 1869.86     400 1917.05     413 1970.08     425 1995.34     429 2013.23  429.89
#Mann= 3 ,0,0
       0    .055       0   842.5    .035       0 1062.86    .055       0
Levee=-1,0,431,-1,2013,431,,
#XS Ineff= 2 , 0
       0   842.5     402 1062.86       0     402
Permanent Ineff=
       F       F
Bank Sta=842.5,1062.86
XS Rating Curve= 0 ,0
Exp/Cntr=0.3,0.1

Type RM Length L Ch R = 1 ,124048  ,220,200,183
BEGIN DESCRIPTION:
This cross section corresponds to cross section 124052 of the non-georeferenced CDC model which was the source of this model.
END DESCRIPTION:
XS GIS Cut Line= 2
2484060.052909496972683.077027382482453.743458096971534.35393113
#Sta/Elev= 30
       0     429   14.46     428  103.16  401.19  135.44  398.25  258.43  396.23
  445.73     397  624.84     402   661.7     402  673.62     404  708.46     402
  741.31  396.48  794.01     401  834.44     403  856.72     393  872.26  388.83
  883.53     382   899.7     376  979.51     376  991.54     382 1080.29     402
 1095.34     403 1432.32     401 1480.51  399.48  1574.2     400 1711.39     397
 1780.08     398 1830.77     400 1935.77     427 1961.05  430.93 1974.79     431
#Mann= 3 ,0,0
       0    .055       0  834.44    .035       0 1080.29    .055       0
Levee=-1,0,430.91,-1,1974,430.91,,
#XS Ineff= 2 , 0
       0  834.44     403 1080.29       0     402
Permanent Ineff=
       F       F
Bank Sta=834.44,1080.29
XS Rating Curve= 0 ,0
Exp/Cntr=0.3,0.1

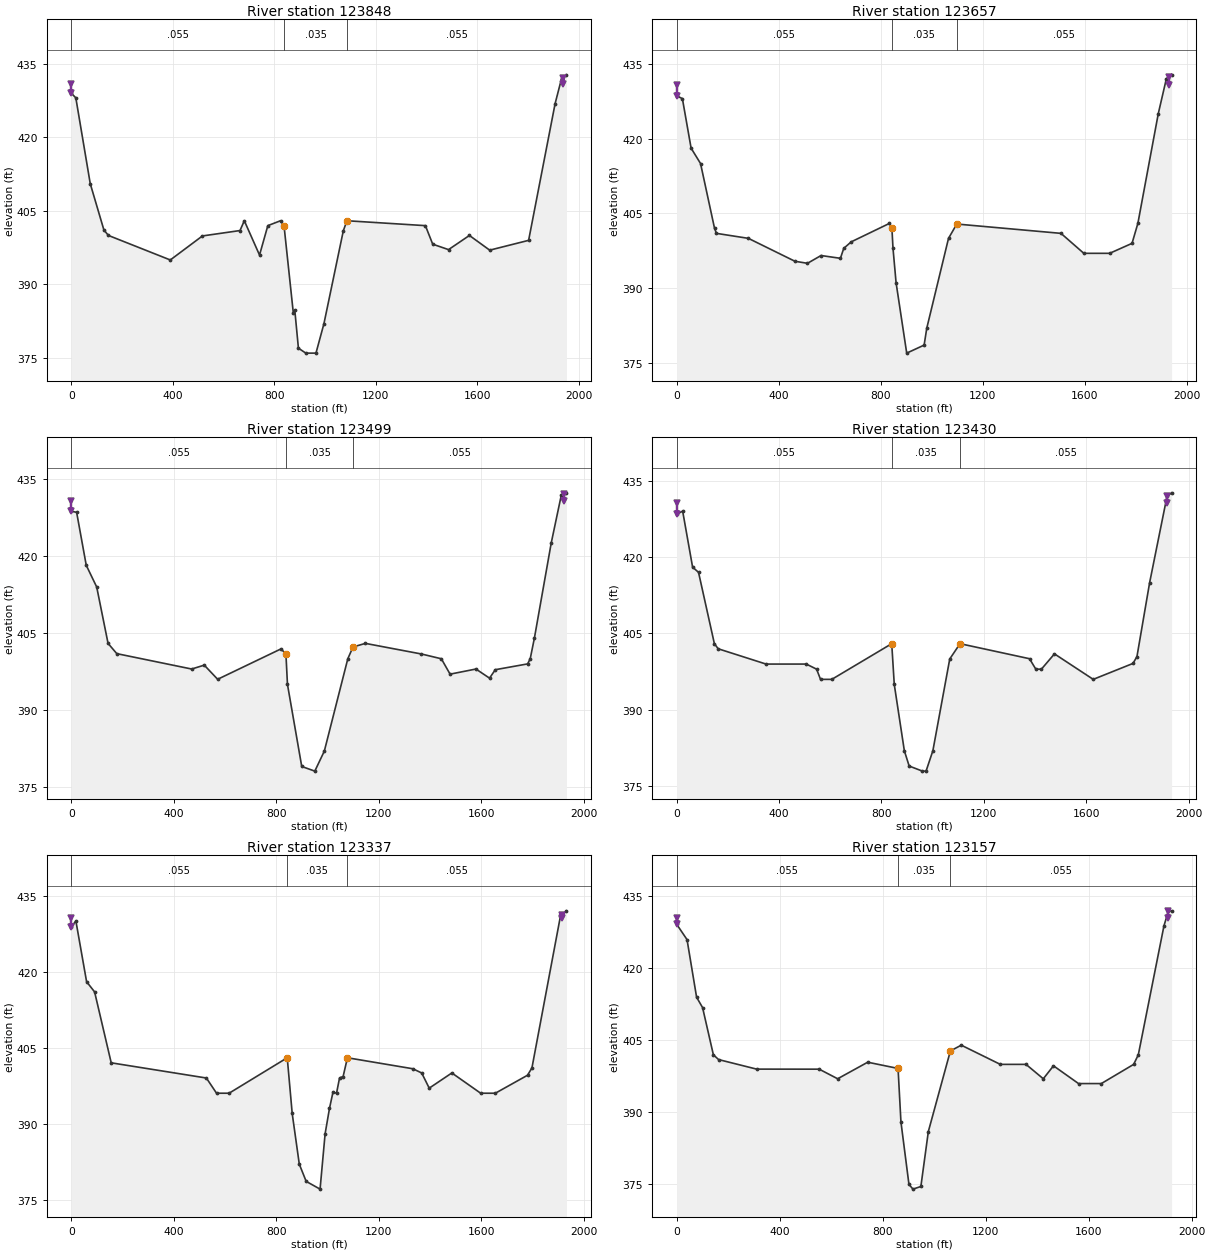
Type RM Length L Ch R = 1 ,123848  ,191,191,191
BEGIN DESCRIPTION:
This cross section corresponds to cross section 123861 of the non-georeferenced CDC model which was the source of this model.
END DESCRIPTION:
XS GIS Cut Line= 2
2484177.643553586972469.601076382482540.137642266971407.27971022
#Sta/Elev= 30
       0     429   17.38  428.06   74.29  410.55  128.09  401.11  145.95     400
  389.83     395  516.55   399.9  664.69     401  681.67     403  741.68     396
   774.4     402  824.37     403  838.25     402  874.93  384.18  880.81  384.71
  895.01  377.01  924.17     376  964.22     376   995.6     382 1072.08  400.96
 1086.37     403 1395.65     402 1424.54  398.22 1486.91  397.11  1569.2     400
 1649.23     397 1802.64     399 1907.12  426.89 1932.53     432 1951.91  432.76
#Mann= 3 ,0,0
       0    .055       0  838.25    .035       0 1086.37    .055       0
Levee=-1,0,430.83,-1,1938,430.83,,
#XS Ineff= 2 , 0
       0  824.37     403 1086.37       0     403
Permanent Ineff=
       F       F
Bank Sta=838.25,1086.37
XS Rating Curve= 0 ,0
Exp/Cntr=0.3,0.1

Type RM Length L Ch R = 1 ,123657  ,158,158,158
BEGIN DESCRIPTION:
This cross section corresponds to cross section 123661 of the non-georeferenced CDC model which was the source of this model.
END DESCRIPTION:
XS GIS Cut Line= 2
2484282.355286426972308.107632962482652.965828696971255.20127422
#Sta/Elev= 30
       0  428.58   22.93     428    57.1  418.07   94.03     415  148.94     402
  156.34     401  281.56     400  463.89  395.41  513.09     395  566.28  396.56
  642.19     396  655.29     398  684.55   399.3  834.38     403  843.96  402.05
  848.17  398.05  860.29  391.12  901.97     377  970.22  378.61  980.59     382
  1065.8     400 1098.14  402.87 1506.55     401 1596.03     397 1697.24     397
 1784.96     399 1807.83     403 1887.85     425 1919.53     432 1939.98  432.77
#Mann= 3 ,0,0
       0    .055       0  843.96    .035       0 1098.14    .055       0
Levee=-1,0,430.76,-1,1930,430.76,,
#XS Ineff= 2 , 0
       0  843.96  402.05 1098.14       0  402.87
Permanent Ineff=
       F       F
Bank Sta=843.96,1098.14
XS Rating Curve= 0 ,0
Exp/Cntr=0.3,0.1

Type RM Length L Ch R = 1 ,123499  ,69,69,69
BEGIN DESCRIPTION:
This cross section corresponds to cross section 123511 of the non-georeferenced CDC model which was the source of this model.
END DESCRIPTION:
XS GIS Cut Line= 2
2484373.445655446972177.868064052482749.959729166971130.54994872
#Sta/Elev= 30
       0  428.79   20.38  428.55   57.87  418.23   98.65     414     143     403
  177.09     401  469.29     398  518.45  398.76  570.69     396  817.27  401.91
  837.03     401  843.15     395  898.85     379  949.87  378.09  987.03     382
 1078.63     400 1098.89   402.3 1147.29     403 1366.07  400.93 1443.69     400
 1477.78     397 1578.69     398 1631.77  396.22 1654.24  397.87 1780.33     399
 1790.49     400 1806.69     404  1872.7  422.63  1912.2     432 1931.99  432.36
#Mann= 3 ,0,0
       0    .055       0  837.03    .035       0 1098.89    .055       0
Levee=-1,0,430.7,-1,1923,430.7,,
#XS Ineff= 2 , 0
       0  837.03     401 1098.89       0   402.3
Permanent Ineff=
       F       F
Bank Sta=837.03,1098.89
XS Rating Curve= 0 ,0
Exp/Cntr=0.3,0.1

Type RM Length L Ch R = 1 ,123430  ,93,93,93
BEGIN DESCRIPTION:
This cross section corresponds to cross section 123441 of the non-georeferenced CDC model which was the source of this model.
END DESCRIPTION:
XS GIS Cut Line= 2
2484419.400287936972123.47315972 2482793.39402556971078.38765147
#Sta/Elev= 30
       0  428.36   23.87     429   62.75     418   85.83     417  147.75     403
  162.58     402  349.47     399  506.63     399  546.84     398  562.18     396
  606.21     396  840.19     403  850.09     395  889.43     382  908.21     379
  960.09     378  974.22     378 1000.82     382 1066.73     400 1106.87     403
 1378.13  400.05  1402.8     398 1424.59     398 1475.56     401 1626.94     396
 1782.36  399.13 1797.63  400.47 1847.24     415 1915.02   431.9  1932.9  432.59
#Mann= 3 ,0,0
       0    .055       0  840.19    .035       0 1106.87    .055       0
Levee=-1,0,430.68,-1,1915,430.68,,
#XS Ineff= 2 , 0
       0  840.19     403 1106.87       0     403
Permanent Ineff=
       F       F
Bank Sta=840.19,1106.87
XS Rating Curve= 0 ,0
Exp/Cntr=0.3,0.1

Type RM Length L Ch R = 1 ,123337  ,180,180,180
BEGIN DESCRIPTION:
This cross section corresponds to cross section 123341 of the non-georeferenced CDC model which was the source of this model.
END DESCRIPTION:
XS GIS Cut Line= 2
2484450.962888846972033.776488722482824.870012436970988.82451038
#Sta/Elev= 30
       0  428.88   17.44     430   59.31     418    90.5     416  155.37     402
  526.96     399  566.62     396  615.64     396   842.7     403  862.02     392
  889.71     382   916.6   378.6  970.86  377.07  990.54     388 1007.59     393
 1021.23  396.21 1035.11     396 1046.84     399 1060.86   399.3 1077.65     403
 1332.82  400.83 1367.56     400 1397.04     397 1485.37     400 1597.88     396
 1655.21     396 1780.86  399.55 1798.08     401 1909.49  430.99  1932.9     432
#Mann= 3 ,0,0
       0    .055       0   842.7    .035       0 1077.65    .055       0
Levee=-1,0,430.64,-1,1916,430.64,,
#XS Ineff= 2 , 0
       0   842.7     403 1077.65       0     403
Permanent Ineff=
       F       F
Bank Sta=842.7,1077.65
XS Rating Curve= 0 ,0
Exp/Cntr=0.3,0.1

Type RM Length L Ch R = 1 ,123157  ,209,209,209
BEGIN DESCRIPTION:
This cross section corresponds to cross section 123161 of the non-georeferenced CDC model which was the source of this model.
END DESCRIPTION:
XS GIS Cut Line= 2
2484547.569651016971880.619642792482929.25136533 6970843.9386453
#Sta/Elev= 30
       0  429.24   40.76     426   77.83     414  101.07  411.83  142.99     402
  163.25     401  310.96  399.01  553.85     399  625.49     397  742.12  400.45
  858.26  399.17  860.39  398.73  871.16     388  902.23     375  917.77     374
  948.55  374.55  977.52     386 1063.09   402.8 1105.41     404 1256.91     400
 1356.72     400 1423.79     397 1463.39   399.7 1560.57     396 1649.11     396
 1774.66     400 1792.69     402  1892.3  428.88  1909.7     432 1921.89     432
#Mann= 3 ,0,0
       0    .055       0  858.26    .035       0 1063.09    .055       0
Levee=-1,0,430.58,-1,1909,430.58,,
#XS Ineff= 2 , 0
       0  858.26  399.17 1063.09       0   402.8
Permanent Ineff=
       F       F
Bank Sta=858.26,1063.09
XS Rating Curve= 0 ,0
Exp/Cntr=0.3,0.1

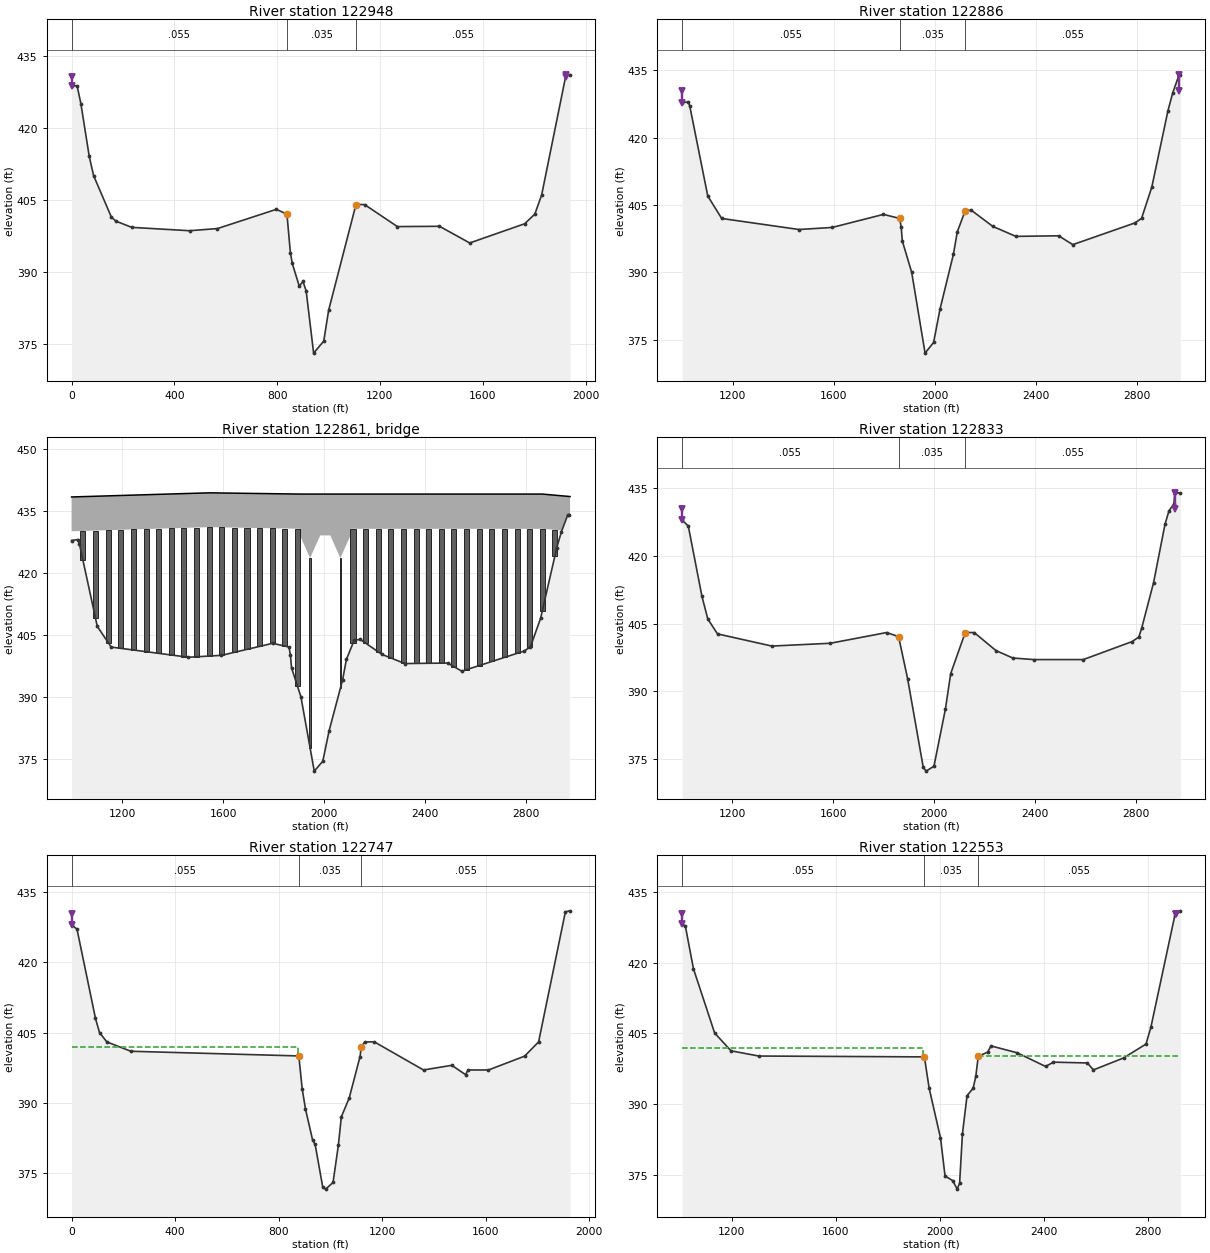
Type RM Length L Ch R = 1 ,122948  ,62,62,62
BEGIN DESCRIPTION:
This cross section corresponds to cross section 122961 of the non-georeferenced CDC model which was the source of this model.
END DESCRIPTION:
XS GIS Cut Line= 2
2484674.958175756971712.272866642483039.899109936970668.48919305
#Sta/Elev= 30
       0  428.71   21.36  428.73   36.18     425   68.72     414   85.77     410
  154.34  401.45  171.91  400.56   233.9  399.25  459.03  398.55  567.73     399
  796.81     403  838.09     402  851.41     394  858.76  391.74  886.07     387
  900.42     388  912.88     386  941.92  373.07  981.26  375.57 1000.35     382
 1106.63     404 1139.99     404  1267.9  399.41 1431.71  399.47 1549.36     396
 1763.13     400 1802.71     402 1829.32     406 1924.05     431 1939.82     431
#Mann= 3 ,0,0
       0    .055       0  838.09    .035       0 1106.63    .055       0
Levee=-1,0,430.51,-1,1924,430.51,,
#XS Ineff= 2 , 0
       0  838.09     402 1106.63       0     404
Permanent Ineff=
       F       F
Bank Sta=838.09,1106.63
XS Rating Curve= 0 ,0
Exp/Cntr=0.3,0.1

Type RM Length L Ch R = 1 ,122886  ,53,53,53
BEGIN DESCRIPTION:
This cross section corresponds to cross section 122886 of the non-georeferenced CDC model which was the source of this model.
END DESCRIPTION:
XS GIS Cut Line= 3
2484724.366213416971669.354973472483889.88559893 6971137.4951448
2483064.119205836970605.48111697
#Sta/Elev= 30
    1000  427.77 1024.62     428  1030.8     427 1101.83     407 1156.98     402
 1462.67  399.54 1593.93     400 1796.95  402.91 1861.45     402 1867.17     400
 1871.39     397 1908.54     390 1961.47     372 1995.29  374.39 2020.29  381.75
 2073.53     394 2088.85     399 2119.76  403.67 2143.92  403.85 2229.23  400.24
  2320.5  398.01 2489.74  398.14 2546.06  396.17  2791.3     401 2817.74     402
 2858.48     409  2922.1  425.96 2940.95  429.94 2966.27     434 2971.87     434
#Mann= 3 ,0,0
    1000    .055       0 1861.45    .035       0 2119.76    .055       0
Levee=-1,1000,430.48,-1,2966,430.48,,
#XS Ineff= 2 , 0
       0 1861.45     402 2119.76       0  403.67
Permanent Ineff=
       F       F
Bank Sta=1861.45,2119.76
XS Rating Curve= 0 ,0
Exp/Cntr=0.3,0.1

Type RM Length L Ch R = 3 ,122861  ,,,
BEGIN DESCRIPTION:
122860  Continental Avenue
END DESCRIPTION:
Node Name=Continental Ave.
Bridge Culvert--1,0,-1,-1, 0
Deck Dist Width WeirC Skew NumUp NumDn MinLoCord MaxHiCord MaxSubmerge Is_Ogee
1.5,48,2.6,0, 12, 12, , , 0.95, 0, ,,,
    1000    1545    1905    1905    1945    1985    2025    2065    2105    2105
    2865    2975
   438.3   439.3     439     439     439     439     439     439     439     439
     439   438.4
     430     431   430.6     429   423.5     429     429   423.5     429   430.6
   430.6     430
    1000    1545    1905    1905    1945    1985    2025    2065    2105    2105
    2865    2975
   438.3   439.3     439     439     439     439     439     439     439     439
     439   438.4
     430     431   430.6     429   423.5     429     429   423.5     429   430.6
   430.6     430
Pier Skew, UpSta & Num, DnSta & Num=  ,1045, 5 ,1045, 5 , 3 , 3 , 0 ,,
     5.5     2.5     3.5     3.5      20
     390     426     426   427.6   430.2
     5.5     2.5     3.5     3.5      20
     390     426     426   427.6   430.2
Pier Skew, UpSta & Num, DnSta & Num=  ,1095, 5 ,1095, 5 , 3 , 3 , 0 ,,
     5.5     2.5     3.5     3.5      20
   390.1   426.1   426.1   427.7   430.3
     5.5     2.5     3.5     3.5      20
   390.1   426.1   426.1   427.7   430.3
Pier Skew, UpSta & Num, DnSta & Num=  ,1145, 5 ,1145, 5 , 3 , 3 , 0 ,,
     5.5     2.5     3.5     3.5      20
   390.2   426.2   426.2   427.8   430.4
     5.5     2.5     3.5     3.5      20
   390.2   426.2   426.2   427.8   430.4
Pier Skew, UpSta & Num, DnSta & Num=  ,1195, 5 ,1195, 5 , 3 , 3 , 0 ,,
     5.5     2.5     3.5     3.5      20
   390.3   426.3   426.3   427.9   430.5
     5.5     2.5     3.5     3.5      20
   390.3   426.3   426.3   427.9   430.5
Pier Skew, UpSta & Num, DnSta & Num=  ,1245, 5 ,1245, 5 , 3 , 3 , 0 ,,
     5.5     2.5     3.5     3.5      20
   390.4   426.4   426.4     428   430.6
     5.5     2.5     3.5     3.5      20
   390.4   426.4   426.4     428   430.6
Pier Skew, UpSta & Num, DnSta & Num=  ,1295, 5 ,1295, 5 , 3 , 3 , 0 ,,
     5.5     2.5     3.5     3.5      20
   390.4   426.4   426.4     428   430.6
     5.5     2.5     3.5     3.5      20
   390.4   426.4   426.4     428   430.6
Pier Skew, UpSta & Num, DnSta & Num=  ,1345, 5 ,1345, 5 , 3 , 3 , 0 ,,
     5.5     2.5     3.5     3.5      20
   390.5   426.5   426.5   428.1   430.7
     5.5     2.5     3.5     3.5      20
   390.5   426.5   426.5   428.1   430.7
Pier Skew, UpSta & Num, DnSta & Num=  ,1395, 5 ,1395, 5 , 3 , 3 , 0 ,,
     5.5     2.5     3.5     3.5      20
   390.6   426.6   426.6   428.2   430.8
     5.5     2.5     3.5     3.5      20
   390.6   426.6   426.6   428.2   430.8
Pier Skew, UpSta & Num, DnSta & Num=  ,1445, 5 ,1445, 5 , 3 , 3 , 0 ,,
     5.5     2.5     3.5     3.5      20
   390.7   426.7   426.7   428.3   430.9
     5.5     2.5     3.5     3.5      20
   390.7   426.7   426.7   428.3   430.9
Pier Skew, UpSta & Num, DnSta & Num=  ,1495, 5 ,1495, 5 , 3 , 3 , 0 ,,
     5.5     2.5     3.5     3.5      20
   390.8   426.8   426.8   428.4     431
     5.5     2.5     3.5     3.5      20
   390.8   426.8   426.8   428.4     431
Pier Skew, UpSta & Num, DnSta & Num=  ,1545, 5 ,1545, 5 , 3 , 3 , 0 ,,
     5.5     2.5     3.5     3.5      20
   390.9   426.9   426.9   428.5   431.1
     5.5     2.5     3.5     3.5      20
   390.9   426.9   426.9   428.5   431.1
Pier Skew, UpSta & Num, DnSta & Num=  ,1595, 5 ,1595, 5 , 3 , 3 , 0 ,,
     5.5     2.5     3.5     3.5      20
   390.8   426.8   426.8   428.4     431
     5.5     2.5     3.5     3.5      20
   390.8   426.8   426.8   428.4     431
Pier Skew, UpSta & Num, DnSta & Num=  ,1645, 5 ,1645, 5 , 3 , 3 , 0 ,,
     5.5     2.5     3.5     3.5      20
   390.8   426.8   426.8   428.4     431
     5.5     2.5     3.5     3.5      20
   390.8   426.8   426.8   428.4     431
Pier Skew, UpSta & Num, DnSta & Num=  ,1695, 5 ,1695, 5 , 3 , 3 , 0 ,,
     5.5     2.5     3.5     3.5      20
   390.7   426.7   426.7   428.3   430.9
     5.5     2.5     3.5     3.5      20
   390.7   426.7   426.7   428.3   430.9
Pier Skew, UpSta & Num, DnSta & Num=  ,1745, 5 ,1745, 5 , 3 , 3 , 0 ,,
     5.5     2.5     3.5     3.5      20
   390.7   426.7   426.7   428.3   430.9
     5.5     2.5     3.5     3.5      20
   390.7   426.7   426.7   428.3   430.9
Pier Skew, UpSta & Num, DnSta & Num=  ,1795, 5 ,1795, 5 , 3 , 3 , 0 ,,
     5.5     2.5     3.5     3.5      20
   390.6   426.6   426.6   428.2   430.8
     5.5     2.5     3.5     3.5      20
   390.6   426.6   426.6   428.2   430.8
Pier Skew, UpSta & Num, DnSta & Num=  ,1845, 5 ,1845, 5 , 3 , 3 , 0 ,,
     5.5     2.5     3.5     3.5      20
   390.6   426.6   426.6   428.2   430.8
     5.5     2.5     3.5     3.5      20
   390.6   426.6   426.6   428.2   430.8
Pier Skew, UpSta & Num, DnSta & Num=  ,1895, 5 ,1895, 5 , 3 , 3 , 0 ,,
     5.5     2.5     3.5     3.5      20
   390.5   426.5   426.5   428.1   430.7
     5.5     2.5     3.5     3.5      20
   390.5   426.5   426.5   428.1   430.7
Pier Skew, UpSta & Num, DnSta & Num=  ,1945, 6 ,1945, 6 , 5 , 5 , 0 ,,
       6       6    5.25     2.5     3.5     3.5
     370   387.5   387.5   420.5   420.5     425
       6       6    5.25     2.5     3.5     3.5
     370   387.5   387.5   420.5   420.5     425
Pier Skew, UpSta & Num, DnSta & Num=  ,2065, 6 ,2065, 6 , 5 , 5 , 0 ,,
       6       6    5.25     2.5     3.5     3.5
     370   387.5   387.5   420.5   420.5     425
       6       6    5.25     2.5     3.5     3.5
     370   387.5   387.5   420.5   420.5     425
Pier Skew, UpSta & Num, DnSta & Num=  ,2115, 5 ,2115, 5 , 3 , 3 , 0 ,,
     5.5     2.5     3.5     3.5      20
   390.5   426.5   426.5   428.1   430.7
     5.5     2.5     3.5     3.5      20
   390.5   426.5   426.5   428.1   430.7
Pier Skew, UpSta & Num, DnSta & Num=  ,2165, 5 ,2165, 5 , 3 , 3 , 0 ,,
     5.5     2.5     3.5     3.5      20
   390.5   426.5   426.5   428.1   430.7
     5.5     2.5     3.5     3.5      20
   390.5   426.5   426.5   428.1   430.7
Pier Skew, UpSta & Num, DnSta & Num=  ,2215, 5 ,2215, 5 , 3 , 3 , 0 ,,
     5.5     2.5     3.5     3.5      20
   390.5   426.5   426.5   428.1   430.7
     5.5     2.5     3.5     3.5      20
   390.5   426.5   426.5   428.1   430.7
Pier Skew, UpSta & Num, DnSta & Num=  ,2265, 5 ,2265, 5 , 3 , 3 , 0 ,,
     5.5     2.5     3.5     3.5      20
   390.5   426.5   426.5   428.1   430.7
     5.5     2.5     3.5     3.5      20
   390.5   426.5   426.5   428.1   430.7
Pier Skew, UpSta & Num, DnSta & Num=  ,2315, 5 ,2315, 5 , 3 , 3 , 0 ,,
     5.5     2.5     3.5     3.5      20
   390.5   426.5   426.5   428.1   430.7
     5.5     2.5     3.5     3.5      20
   390.5   426.5   426.5   428.1   430.7
Pier Skew, UpSta & Num, DnSta & Num=  ,2365, 5 ,2365, 5 , 3 , 3 , 0 ,,
     5.5     2.5     3.5     3.5      20
   390.5   426.5   426.5   428.1   430.7
     5.5     2.5     3.5     3.5      20
   390.5   426.5   426.5   428.1   430.7
Pier Skew, UpSta & Num, DnSta & Num=  ,2415, 5 ,2415, 5 , 3 , 3 , 0 ,,
     5.5     2.5     3.5     3.5      20
   390.5   426.5   426.5   428.1   430.7
     5.5     2.5     3.5     3.5      20
   390.5   426.5   426.5   428.1   430.7
Pier Skew, UpSta & Num, DnSta & Num=  ,2465, 5 ,2465, 5 , 3 , 3 , 0 ,,
     5.5     2.5     3.5     3.5      20
   390.5   426.5   426.5   428.1   430.7
     5.5     2.5     3.5     3.5      20
   390.5   426.5   426.5   428.1   430.7
Pier Skew, UpSta & Num, DnSta & Num=  ,2515, 5 ,2515, 5 , 3 , 3 , 0 ,,
     5.5     2.5     3.5     3.5      20
   390.5   426.5   426.5   428.1   430.7
     5.5     2.5     3.5     3.5      20
   390.5   426.5   426.5   428.1   430.7
Pier Skew, UpSta & Num, DnSta & Num=  ,2565, 5 ,2565, 5 , 3 , 3 , 0 ,,
     5.5     2.5     3.5     3.5      20
   390.5   426.5   426.5   428.1   430.7
     5.5     2.5     3.5     3.5      20
   390.5   426.5   426.5   428.1   430.7
Pier Skew, UpSta & Num, DnSta & Num=  ,2615, 5 ,2615, 5 , 3 , 3 , 0 ,,
     5.5     2.5     3.5     3.5      20
   390.5   426.5   426.5   428.1   430.7
     5.5     2.5     3.5     3.5      20
   390.5   426.5   426.5   428.1   430.7
Pier Skew, UpSta & Num, DnSta & Num=  ,2665, 5 ,2665, 5 , 3 , 3 , 0 ,,
     5.5     2.5     3.5     3.5      20
   390.5   426.5   426.5   428.1   430.7
     5.5     2.5     3.5     3.5      20
   390.5   426.5   426.5   428.1   430.7
Pier Skew, UpSta & Num, DnSta & Num=  ,2715, 5 ,2715, 5 , 3 , 3 , 0 ,,
     5.5     2.5     3.5     3.5      20
   390.5   426.5   426.5   428.1   430.7
     5.5     2.5     3.5     3.5      20
   390.5   426.5   426.5   428.1   430.7
Pier Skew, UpSta & Num, DnSta & Num=  ,2765, 5 ,2765, 5 , 3 , 3 , 0 ,,
     5.5     2.5     3.5     3.5      20
   390.5   426.5   426.5   428.1   430.7
     5.5     2.5     3.5     3.5      20
   390.5   426.5   426.5   428.1   430.7
Pier Skew, UpSta & Num, DnSta & Num=  ,2815, 5 ,2815, 5 , 3 , 3 , 0 ,,
     5.5     2.5     3.5     3.5      20
   390.5   426.5   426.5   428.1   430.7
     5.5     2.5     3.5     3.5      20
   390.5   426.5   426.5   428.1   430.7
Pier Skew, UpSta & Num, DnSta & Num=  ,2865, 5 ,2865, 5 , 3 , 3 , 0 ,,
     5.5     2.5     3.5     3.5      20
   390.5   426.5   426.5   428.1   430.7
     5.5     2.5     3.5     3.5      20
   390.5   426.5   426.5   428.1   430.7
Pier Skew, UpSta & Num, DnSta & Num=  ,2915, 5 ,2915, 5 , 3 , 3 , 0 ,,
     5.5     2.5     3.5     3.5      20
   390.3   426.3   426.3   427.9   430.5
     5.5     2.5     3.5     3.5      20
   390.3   426.3   426.3   427.9   430.5
BR Coef= 1 , 1 , 1 ,0.9, 0 ,,,0.8,-1,0.33,1,
WSPro=,,,, 1 ,,,, 0 ,,,, 0 ,,,,-1 ,-1 ,-1 , 0 , 0 , 0 , 0 , 0
BC Design=,, 0 ,, 0 ,,,,,,
BC HTab HWMax=432
BC Use User HTab Curves=0
BC User HTab FreeFlow(D)= 0

Type RM Length L Ch R = 1 ,122833  ,86,86,86
BEGIN DESCRIPTION:
This cross section corresponds to cross section 122834 of the non-georeferenced CDC model which was the source of this model.
END DESCRIPTION:
XS GIS Cut Line= 2
2484740.22707409 6971618.61426132483075.269446026970553.79716522
#Sta/Elev= 30
    1000  427.97 1024.84  426.63  1079.1     411 1102.22     406 1140.66   402.7
 1356.11     400 1587.92  400.62 1811.19     403 1858.61   402.1 1894.47  392.75
 1956.41   373.1 1967.82  372.25 1998.86  373.34 2044.21     386 2065.27  393.89
 2122.85     403 2158.44     403 2244.62     399 2311.43  397.35 2394.45     397
 2591.01     397 2784.71     401 2811.03     402 2822.12   403.9 2869.72   414.1
 2914.87     427 2930.58     430 2949.98  431.54 2954.24     434 2976.34     434
#Mann= 3 ,0,0
    1000    .055       0 1858.61    .035       0 2122.85    .055       0
Levee=-1,1000,430.46,-1,2954,430.46,,
#XS Ineff= 2 , 0
       0 1858.61   402.1 2122.85       0     403
Permanent Ineff=
       F       F
Bank Sta=1858.61,2122.85
XS Rating Curve= 0 ,0
Exp/Cntr=0.3,0.1

Type RM Length L Ch R = 1 ,122747  ,255,194,137
BEGIN DESCRIPTION:
This cross section corresponds to cross section 122760 of the non-georeferenced CDC model which was the source of this model.
END DESCRIPTION:
XS GIS Cut Line= 2
2484784.139387856971545.035340222483161.140993426970508.11779463
#Sta/Elev= 30
       0     428   20.88  427.08   92.37     408  107.86     405   136.2     403
  229.15     401  878.01     400   890.9     393  903.76  388.64  930.98   382.1
  941.03  381.09  970.32     372  981.58  371.55 1010.24  372.98 1030.93     381
 1042.29     387 1072.54     391 1114.49  399.85 1119.01  401.86 1132.56     403
 1169.92     403 1359.72     397 1468.86     398 1522.36     396 1531.54     397
  1610.6     397 1750.44  399.96 1804.38     403 1907.95   430.8 1925.96     431
#Mann= 3 ,0,0
       0    .055       0  878.01    .035       0 1119.01    .055       0
Levee=-1,0,430.42,-1,1926,430.42,,
#XS Ineff= 2 , 0
       0     873     402 1119.01       0  401.86
Permanent Ineff=
       F       F
Bank Sta=878.01,1119.01
XS Rating Curve= 0 ,0
Exp/Cntr=0.3,0.1

Type RM Length L Ch R = 1 ,122553  ,124,124,124
BEGIN DESCRIPTION:
This cross section corresponds to cross section 122562 of the non-georeferenced CDC model which was the source of this model.
--------------------------------------------------------------------
CDC DAL051805-1 Woodall Rogers Extension (Margaret Hunt Hill Bridge)
--------------------------------------------------------------------
END DESCRIPTION:
XS GIS Cut Line= 2
     2484952.587     6971229.092     2483188.578      6970480.22
#Sta/Elev= 30
    1009  428.17 1022.05   427.7 1052.84  418.72 1134.25  405.08 1196.96  401.29
    1304  400.18 1940.35     400 1958.72  393.32 2002.27  382.81 2019.78  374.72
 2049.41  373.73 2066.38  371.93 2075.75  373.21 2086.59  383.66 2104.25  391.76
 2127.69  393.34  2137.9  395.86 2147.41  400.14  2183.7  401.01 2196.13  402.33
 2296.92  400.87 2405.91  397.97 2436.36  398.88 2566.83  398.71  2589.9  397.23
 2705.59  399.77 2792.02  402.72 2810.77  406.29 2903.41  430.18 2924.53     431
#Mann= 3 ,0,0
    1009    .055       0 1940.35    .035       0 2147.41    .055       0
Levee=-1,1009,430.25,-1,2907,430.25,,
#XS Ineff= 2 , 0
         1934.17401.7998 2147.41        400.1407
Permanent Ineff=
       F       F
Bank Sta=1940.35,2147.41
XS Rating Curve= 0 ,0
Exp/Cntr=0.3,0.1

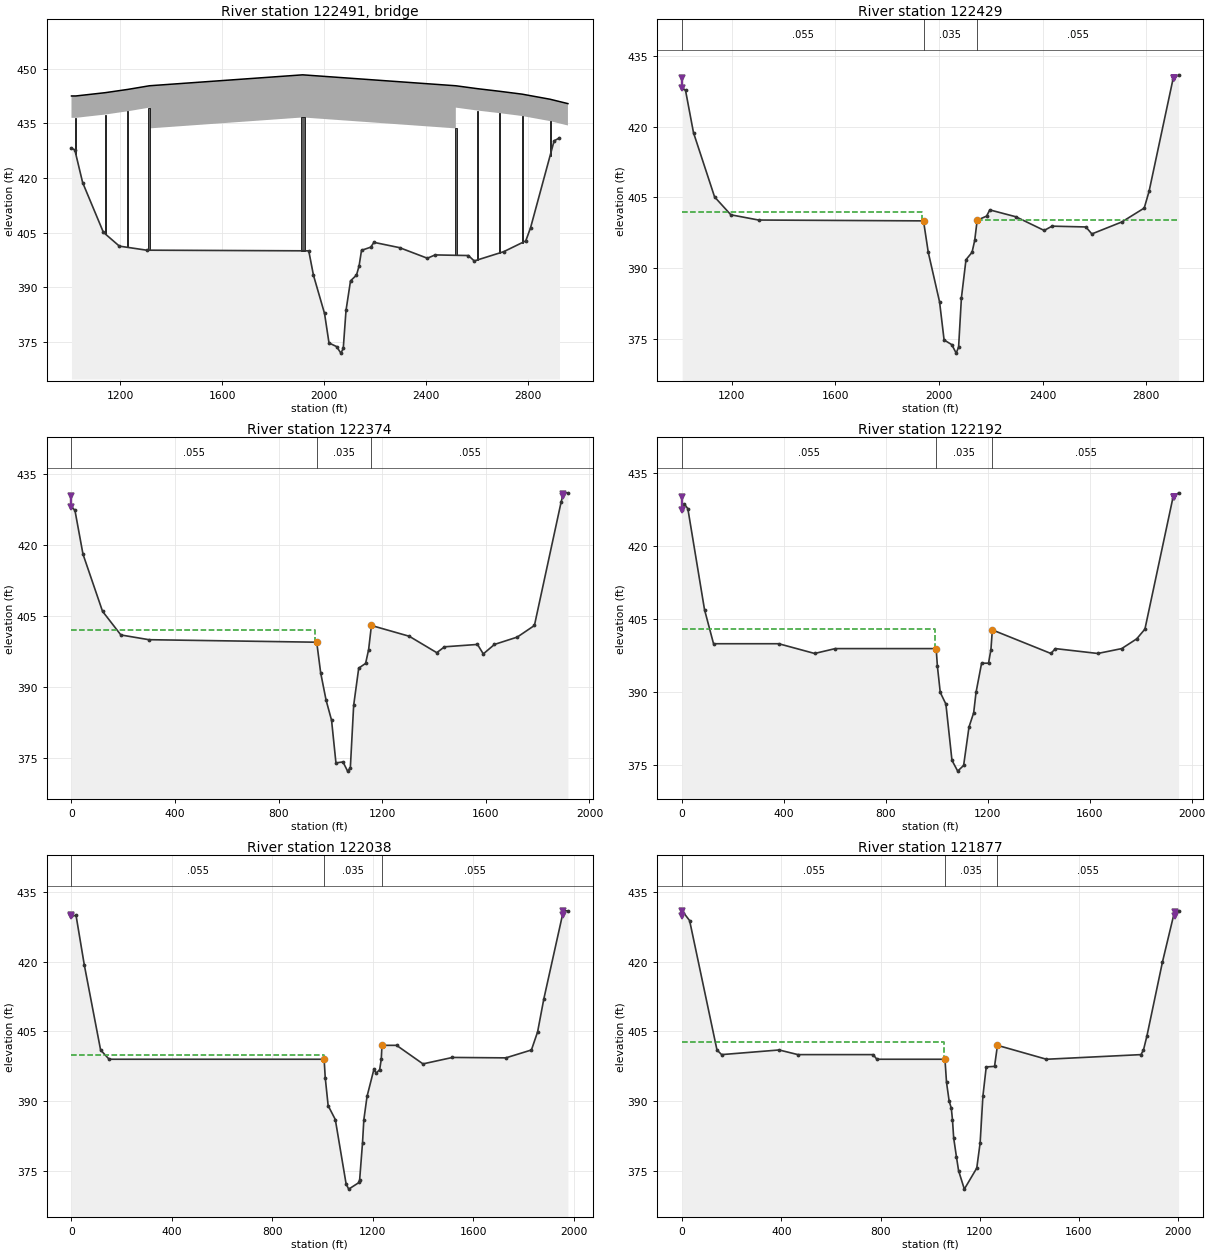
Type RM Length L Ch R = 3 ,122491  ,,,
BEGIN DESCRIPTION:
122500  Woodall Rodgers Freeway
-----------------------------------------------------------------------
CDC DAL051805-1 Woodall Rogers Extension (Margaret Hunt Hill Bridge)
-----------------------------------------------------------------------
END DESCRIPTION:
Node Name=Woodall Rogers
Bridge Culvert--1,0,-1,-1, 0
Deck Dist Width WeirC Skew NumUp NumDn MinLoCord MaxHiCord MaxSubmerge Is_Ogee
2,120,2.6,0, 14, 14, , , 0.95, 0, 0,0,,
    1009    1026    1141    1230    1315    1315  1916.3  2517.6  2517.6  2602.6
  2687.6  2777.6  2887.6  2957.6
   442.5   442.5   443.4   444.3   445.3   445.3   448.3   445.3   445.3   444.5
   443.8     443   441.6   440.4
   436.5   436.5   437.4   438.3   439.3   433.6   436.6   433.6   439.3   438.5
   437.8     437   435.6   434.4
    1009    1026    1141    1230    1315    1315  1916.3  2517.6  2517.6  2602.6
  2687.6  2777.6  2887.6  2957.6
   442.5   442.5   443.4   444.3   445.3   445.3   448.3   445.3   445.3   444.5
   443.8     443   441.6   440.4
   436.5   436.5   437.4   438.3   439.3   433.6   436.6   433.6   439.3   438.5
   437.8     437   435.6   434.4
Pier Skew, UpSta & Num, DnSta & Num=  ,1026, 2 ,1026, 2 , 0 , 0 , 0 ,,
     3.5     3.5
       0     440
     3.5     3.5
       0     440
Pier Skew, UpSta & Num, DnSta & Num=  ,1141, 2 ,1141, 2 , 0 , 0 , 0 ,,
     3.5     3.5
       0     440
     3.5     3.5
       0     440
Pier Skew, UpSta & Num, DnSta & Num=  ,1230, 2 ,1230, 2 , 0 , 0 , 0 ,,
     3.5     3.5
       0     440
     3.5     3.5
       0     440
Pier Skew, UpSta & Num, DnSta & Num=  ,1315, 2 ,1315, 2 , 0 , 0 , 0 ,,
       8       8
       0     440
       8       8
       0     440
Pier Skew, UpSta & Num, DnSta & Num=  ,1916.3, 2 ,1916.3, 2 , 0 , 0 , 0 ,,
      16      16
       0     440
      16      16
       0     440
Pier Skew, UpSta & Num, DnSta & Num=  ,2517.6, 2 ,2517.6, 2 , 0 , 0 , 0 ,,
       8       8
       0     440
       8       8
       0     440
Pier Skew, UpSta & Num, DnSta & Num=  ,2602.6, 2 ,2602.6, 2 , 0 , 0 , 0 ,,
     3.5     3.5
       0     440
     3.5     3.5
       0     440
Pier Skew, UpSta & Num, DnSta & Num=  ,2687.6, 2 ,2687.6, 2 , 0 , 0 , 0 ,,
     3.5     3.5
       0     440
     3.5     3.5
       0     440
Pier Skew, UpSta & Num, DnSta & Num=  ,2777.6, 2 ,2777.6, 2 , 0 , 0 , 0 ,,
     3.5     3.5
       0     440
     3.5     3.5
       0     440
Pier Skew, UpSta & Num, DnSta & Num=  ,2887.6, 2 ,2887.6, 2 , 0 , 0 , 0 ,,
     3.5     3.5
       0     440
     3.5     3.5
       0     440
BR Coef=-1 , 1 , 1 ,1.05, 0 ,,,0.8,-1,1.2,1,
WSPro=,,,, 1 ,,,, 0 ,,,, 0 ,,,,-1 ,-1 ,-1 , 0 , 0 , 0 , 0 , 0
BC Design=,, 0 ,, 0 ,,,,,,
BC Use User HTab Curves=0
BC User HTab FreeFlow(D)= 0

Type RM Length L Ch R = 1 ,122429  ,29,55,81
BEGIN DESCRIPTION:
This cross section corresponds to cross section 122438 of the non-georeferenced CDC model which was the source of this model.
-----------------------------------------------------------------------
CDC DAL051805-1 Woodall Rogers Extension (Margaret Hunt Hill Bridge)
-----------------------------------------------------------------------
END DESCRIPTION:
XS GIS Cut Line= 2
     2484991.108     6971108.173     2483229.875     6970366.883
#Sta/Elev= 30
    1009  428.17 1022.05   427.7 1052.84  418.72 1134.25  405.08 1196.96  401.29
    1304  400.18 1940.35     400 1958.72  393.32 2002.27  382.81 2019.78  374.72
 2049.41  373.73 2066.38  371.93 2075.75  373.21 2086.59  383.66 2104.25  391.76
 2127.69  393.34  2137.9  395.86 2147.41  400.14  2183.7  401.01 2196.13  402.33
 2296.92  400.87 2405.91  397.97 2436.36  398.88 2566.83  398.71  2589.9  397.23
 2705.59  399.77 2792.02  402.72 2810.77  406.29 2903.41  430.18 2924.53     431
#Mann= 3 ,0,0
    1009    .055       0 1940.35    .035       0 2147.41    .055       0
Levee=-1,1009,430.25,-1,2907,430.25,,
#XS Ineff= 2 , 0
         1934.17401.7998 2147.41        400.1407
Permanent Ineff=
       F       F
Bank Sta=1940.35,2147.41
XS Rating Curve= 0 ,0
Exp/Cntr=0.3,0.1

Type RM Length L Ch R = 1 ,122374  ,201,182,168
BEGIN DESCRIPTION:
This cross section corresponds to cross section 122390 of the non-georeferenced CDC model which was the source of this model.
END DESCRIPTION:
XS GIS Cut Line= 2
     2485058.354     6971078.629     2483296.379     6970333.178
#Sta/Elev= 30
       0     428   13.24  427.33   44.47  418.04  119.83     406  190.68     401
  299.26     400  946.94  399.47  962.23     393  983.05  387.25 1004.24     383
 1021.14     374 1048.35   374.2  1066.1  372.26 1076.74  372.93 1089.58  386.14
 1109.12     394 1135.73     395 1147.34  397.91 1158.14     403 1304.12  400.73
 1410.54  397.26 1440.27   398.5 1567.66     399 1590.19     397 1633.22     399
 1721.26  400.55 1787.53     403 1890.44     429 1899.58  430.93 1916.91     431
#Mann= 3 ,0,0
       0    .055       0  946.94    .035       0 1158.14    .055       0
Levee=-1,0,430.23,-1,1899,430.23,,
#XS Ineff= 2 , 0
       0  938.54  402.08 1158.14       0     403
Permanent Ineff=
       F       F
Bank Sta=946.94,1158.14
XS Rating Curve= 0 ,0
Exp/Cntr=0.3,0.1

Type RM Length L Ch R = 1 ,122192  ,179,154,137
BEGIN DESCRIPTION:
This cross section corresponds to cross section 122206 of the non-georeferenced CDC model which was the source of this model.
END DESCRIPTION:
XS GIS Cut Line= 2
2485166.659620176970954.970575472483390.683841416970153.37080072
#Sta/Elev= 30
       0  427.43    8.47  428.72   22.46  427.73   87.84     407  123.25     400
  379.15     400  519.95     398  601.04     399     997     399 1001.99  395.33
 1013.11     390 1035.27   387.6 1059.04  376.06 1081.55  373.83 1104.84     375
 1125.92  382.89 1144.34  385.83 1153.51     390 1175.38     396 1202.55     396
 1211.98   398.8 1217.55  402.84 1447.39     398  1464.9     399 1631.46     398
 1725.26     399 1784.13     401 1816.42     403 1926.28  429.98  1948.5     431
#Mann= 3 ,0,0
       0    .055       0     997    .035       0 1217.55    .055       0
Levee=-1,0,430.13,-1,1931,430.13,,
#XS Ineff= 2 , 0
       0  993.03     403 1217.55       0  402.84
Permanent Ineff=
       F       F
Bank Sta=997,1217.55
XS Rating Curve= 0 ,0
Exp/Cntr=0.3,0.1

Type RM Length L Ch R = 1 ,122038  ,187,161,144
BEGIN DESCRIPTION:
This cross section corresponds to cross section 122045 of the non-georeferenced CDC model which was the source of this model.
END DESCRIPTION:
XS GIS Cut Line= 2
2485267.943538346970764.867609222483422.764485936970054.74173288
#Sta/Elev= 30
       0   429.9    18.2     430   50.89  419.38  115.93     401     150     399
 1006.15     399 1010.65     395 1022.17     389 1050.72     386 1093.72  372.12
  1104.1     371 1145.39  372.44 1147.66     373 1159.09     381 1164.32  385.94
  1177.1     391 1204.37  396.81 1213.43     396 1227.39  396.77 1233.73     399
 1236.57     402 1294.76     402 1399.84     398 1517.43  399.39  1729.9   399.3
 1831.74     401 1856.32  404.89 1881.11     412 1959.09     431 1977.11     431
#Mann= 3 ,0,0
       0    .055       0 1006.15    .035       0 1236.57    .055       0
Levee=-1,0,430.03,-1,1959,430.03,,
#XS Ineff= 2 , 0
       0 1005.13     400 1236.57       0     402
Permanent Ineff=
       F       F
Bank Sta=1006.15,1236.57
XS Rating Curve= 0 ,0
Exp/Cntr=0.3,0.1

Type RM Length L Ch R = 1 ,121877  ,197,170,151
BEGIN DESCRIPTION:
This cross section corresponds to cross section 121884 of the non-georeferenced CDC model which was the source of this model.
END DESCRIPTION:
XS GIS Cut Line= 2
2485396.303845916970574.726913382483491.89623743 6969959.2652178
#Sta/Elev= 30
       0     431   30.15  428.89  140.45     401  159.13     400  391.05     401
  466.82     400     770     400     785     399 1059.57     399 1065.88     394
 1076.43     390 1085.12  388.44  1089.8     386 1094.78     382 1105.68  378.03
 1114.41     375 1137.64     371  1187.8  375.54 1201.42     381 1212.47     391
 1225.95  397.35 1259.45  397.46 1271.26     402 1468.78     399 1849.86     400
  1859.9     401 1873.69     404 1936.56     420 1985.86     431 2001.39     431
#Mann= 3 ,0,0
       0    .055       0 1059.57    .035       0 1271.26    .055       0
Levee=-1,0,429.93,-1,1985,429.93,,
#XS Ineff= 2 , 0
       0 1055.09  402.73 1271.26       0     402
Permanent Ineff=
       F       F
Bank Sta=1059.57,1271.26
XS Rating Curve= 0 ,0
Exp/Cntr=0.3,0.1