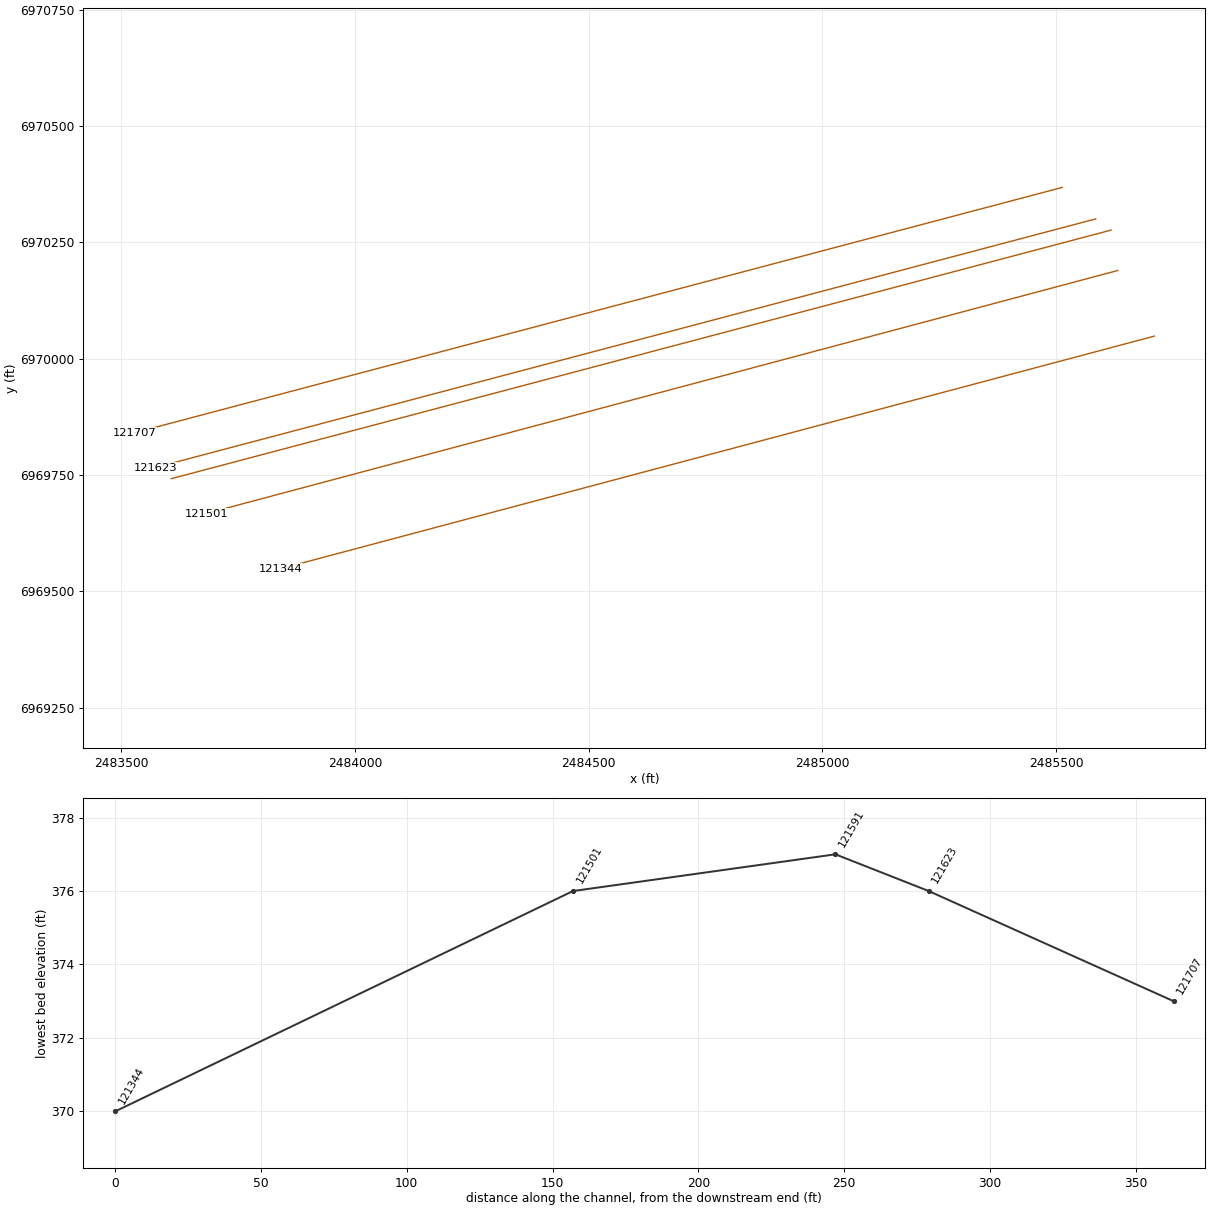
HEC-RAS study CDC_Consolidated_Model.prj: Upper Trinity CDC Consolidated Model

--- CDC_Consolidated_Model.g04 (geometry) --- (continued)

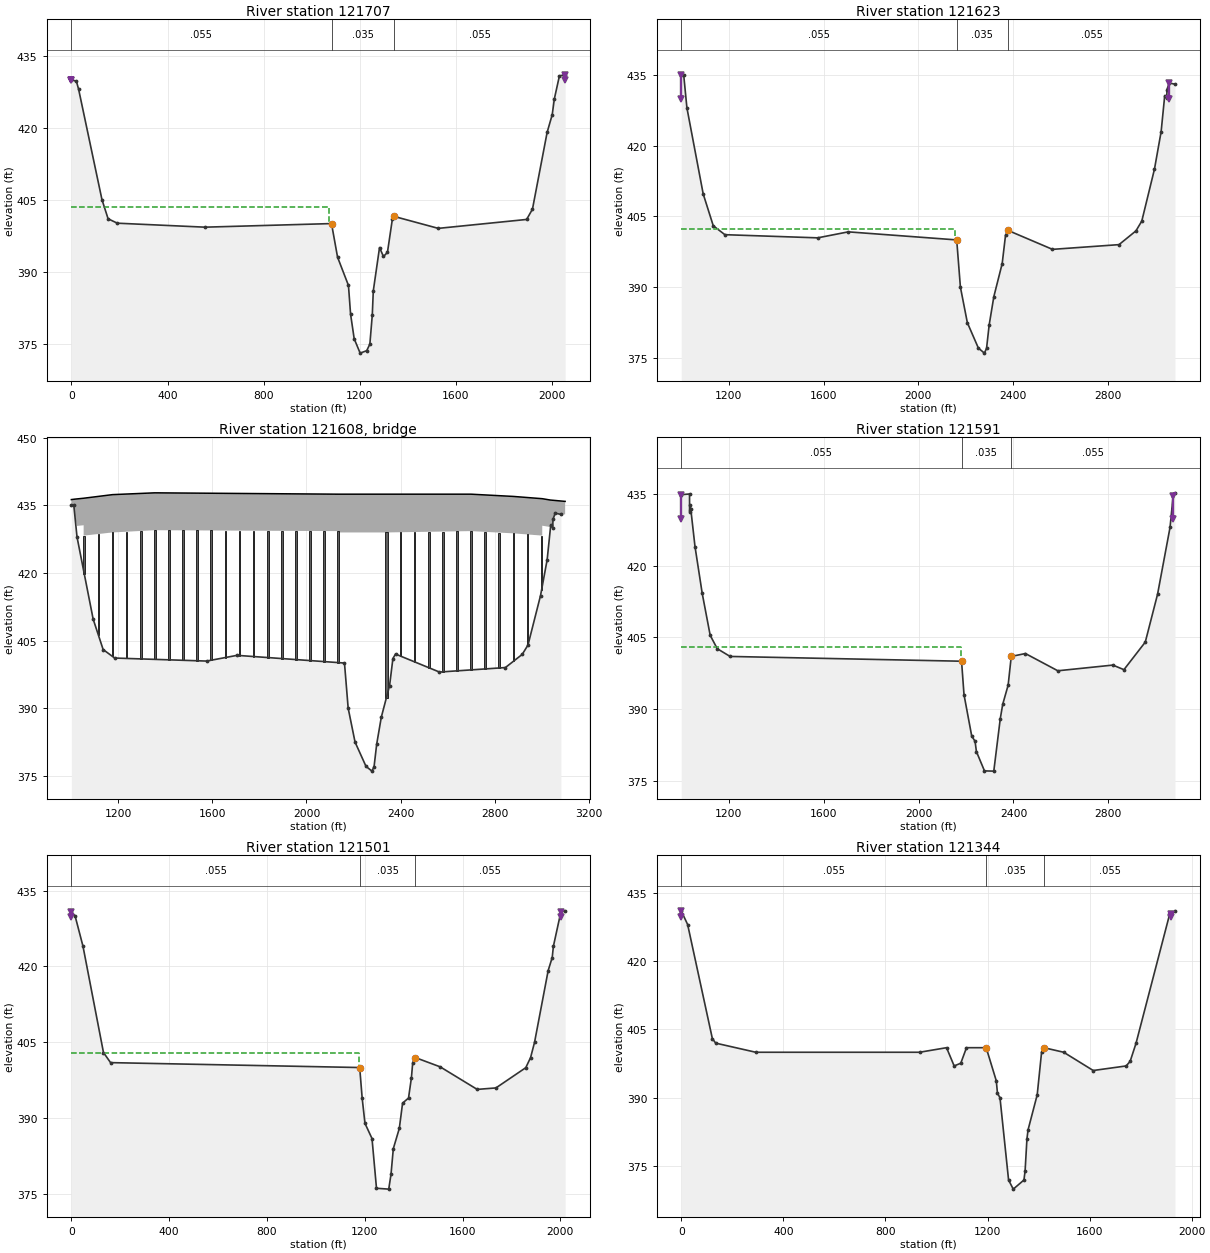
Type RM Length L Ch R = 1 ,121707  ,84,84,84
BEGIN DESCRIPTION:
This cross section corresponds to cross section 121723 of the non-georeferenced CDC model which was the source of this model.
END DESCRIPTION:
XS GIS Cut Line= 2
 2485513.56607866970368.026211312483528.103842176969840.84091397
#Sta/Elev= 30
       0     430   21.01  429.65   30.17     428  127.29     405  152.83     401
  191.26  400.08  555.91  399.25 1082.36     400  1107.5     393 1152.88   387.1
 1161.63  381.12 1176.68     376 1201.46     373 1228.82  373.51 1241.95  374.89
 1252.04     381 1256.14  385.96 1282.11     395 1298.47  393.14 1315.09     394
 1335.75     401 1341.41  401.51  1526.6     399 1894.11  400.86 1918.35     403
 1979.35     419 2000.59   422.7 2009.46     426 2030.58  430.79 2054.26     431
#Mann= 3 ,0,0
       0    .055       0 1082.36    .035       0 1341.41    .055       0
Levee=-1,0,429.83,-1,2054,429.83,,
#XS Ineff= 2 , 0
       0  1070.6  403.49 1341.41       0  401.51
Permanent Ineff=
       F       F
Bank Sta=1082.36,1341.41
XS Rating Curve= 0 ,0
Exp/Cntr=0.3,0.1

Type RM Length L Ch R = 1 ,121623  ,32,32,32
BEGIN DESCRIPTION:
This cross section corresponds to cross section 121639 of the non-georeferenced CDC model which was the source of this model.
END DESCRIPTION:
XS GIS Cut Line= 2
  2485584.9770256970300.325887382483572.689054856969766.23738863
#Sta/Elev= 30
    1000     435 1010.47     435 1024.07     428 1092.75  409.75 1135.19     403
 1184.24  401.11 1575.47  400.44 1704.48  401.71 2161.61     400 2177.23     390
 2206.55  382.45 2253.03  377.07 2278.37     376 2287.46     377  2298.6     382
 2318.31     388 2353.45     395 2367.54     401 2378.65     402 2565.48     398
 2845.96     399 2917.49  401.92 2942.04     404 2995.46     415 3023.62  422.96
 3038.72   430.6 3047.41     430 3048.23  431.88 3057.79  433.28 3081.96  433.01
#Mann= 3 ,0,0
    1000    .055       0 2161.61    .035       0 2378.65    .055       0
Levee=-1,1000,429.78,-1,3058,429.78,,
#XS Ineff= 2 , 0
       0 2154.78  402.31 2378.65       0     402
Permanent Ineff=
       F       F
Bank Sta=2161.61,2378.65
XS Rating Curve= 0 ,0
Exp/Cntr=0.3,0.1

Type RM Length L Ch R = 3 ,121608  ,,,
BEGIN DESCRIPTION:
121623  Union Pacific Railroad
END DESCRIPTION:
Node Name=UP Railroad
Bridge Culvert--1,0,-1,-1, 0
Deck Dist Width WeirC Skew NumUp NumDn MinLoCord MaxHiCord MaxSubmerge Is_Ogee
1,28,2.6,0, 16, 16, , , 0.95, 0, ,,,
    1000    1015 1052.25 1052.25    1175    1355    2135    2135    2340    2700
    2880 3002.75 3002.75    3037    3037    3100
   436.3   436.4   436.6   436.6   437.4   437.8   437.5   437.5   437.5   437.5
     437   436.5   436.5   436.2   436.2   435.9
   430.2   430.4   430.6   428.3     429   429.5   429.3     429     429   429.3
   428.8   428.3   430.5   430.2     405     405
    1000    1015 1052.25 1052.25    1175    1355    2135    2135    2340    2700
    2880 3002.75 3002.75    3037    3037    3100
   436.3   436.4   436.6   436.6   437.4   437.8   437.5   437.5   437.5   437.5
     437   436.5   436.5   436.2   436.2   435.9
   430.2   430.4   430.6   428.3     429   429.5   429.3     429     429   429.3
   428.8   428.3   430.5   430.2     405     405
Pier Skew, UpSta & Num, DnSta & Num=  ,1055, 4 ,1055, 4 , 3 , 3 , 0 ,,
       7     4.7     5.5     5.5
   397.6   425.2   425.2     435
       7     4.7     5.5     5.5
   397.6   425.2   425.2     435
Pier Skew, UpSta & Num, DnSta & Num=  ,1115, 4 ,1115, 4 , 3 , 3 , 0 ,,
       7     4.7     5.5     5.5
   397.9   425.5   425.5     432
       7     4.7     5.5     5.5
   397.9   425.5   425.5     432
Pier Skew, UpSta & Num, DnSta & Num=  ,1175, 4 ,1175, 4 , 3 , 3 , 0 ,,
       7     4.7     5.5     5.5
   398.4     426     426     432
       7     4.7     5.5     5.5
   398.4     426     426     432
Pier Skew, UpSta & Num, DnSta & Num=  ,1235, 4 ,1235, 4 , 3 , 3 , 0 ,,
       7     4.7     5.5     5.5
   398.4     426     426     432
       7     4.7     5.5     5.5
   398.4     426     426     432
Pier Skew, UpSta & Num, DnSta & Num=  ,1295, 4 ,1295, 4 , 3 , 3 , 0 ,,
       7     4.7     5.5     5.5
   398.6   426.2   426.2     432
       7     4.7     5.5     5.5
   398.6   426.2   426.2     432
Pier Skew, UpSta & Num, DnSta & Num=  ,1355, 4 ,1355, 4 , 3 , 3 , 0 ,,
       7     4.7     5.5     5.5
   398.8   426.4   426.4     432
       7     4.7     5.5     5.5
   398.8   426.4   426.4     432
Pier Skew, UpSta & Num, DnSta & Num=  ,1415, 4 ,1415, 4 , 3 , 3 , 0 ,,
       7     4.7     5.5     5.5
   398.8   426.4   426.4     432
       7     4.7     5.5     5.5
   398.8   426.4   426.4     432
Pier Skew, UpSta & Num, DnSta & Num=  ,1475, 4 ,1475, 4 , 3 , 3 , 0 ,,
       7     4.7     5.5     5.5
   398.8   426.4   426.4     432
       7     4.7     5.5     5.5
   398.8   426.4   426.4     432
Pier Skew, UpSta & Num, DnSta & Num=  ,1535, 4 ,1535, 4 , 3 , 3 , 0 ,,
       7     4.7     5.5     5.5
   398.8   426.4   426.4     432
       7     4.7     5.5     5.5
   398.8   426.4   426.4     432
Pier Skew, UpSta & Num, DnSta & Num=  ,1595, 4 ,1595, 4 , 3 , 3 , 0 ,,
       7     4.7     5.5     5.5
   398.8   426.4   426.4     432
       7     4.7     5.5     5.5
   398.8   426.4   426.4     432
Pier Skew, UpSta & Num, DnSta & Num=  ,1655, 4 ,1655, 4 , 3 , 3 , 0 ,,
       7     4.7     5.5     5.5
   398.8   426.4   426.4     432
       7     4.7     5.5     5.5
   398.8   426.4   426.4     432
Pier Skew, UpSta & Num, DnSta & Num=  ,1715, 4 ,1715, 4 , 3 , 3 , 0 ,,
       7     4.7     5.5     5.5
   398.8   426.4   426.4     432
       7     4.7     5.5     5.5
   398.8   426.4   426.4     432
Pier Skew, UpSta & Num, DnSta & Num=  ,1775, 4 ,1775, 4 , 3 , 3 , 0 ,,
       7     4.7     5.5     5.5
   398.8   426.4   426.4     432
       7     4.7     5.5     5.5
   398.8   426.4   426.4     432
Pier Skew, UpSta & Num, DnSta & Num=  ,1835, 4 ,1835, 4 , 3 , 3 , 0 ,,
       7     4.7     5.5     5.5
   398.8   426.4   426.4     432
       7     4.7     5.5     5.5
   398.8   426.4   426.4     432
Pier Skew, UpSta & Num, DnSta & Num=  ,1895, 4 ,1895, 4 , 3 , 3 , 0 ,,
       7     4.7     5.5     5.5
   398.8   426.4   426.4     432
       7     4.7     5.5     5.5
   398.8   426.4   426.4     432
Pier Skew, UpSta & Num, DnSta & Num=  ,1955, 4 ,1955, 4 , 3 , 3 , 0 ,,
       7     4.7     5.5     5.5
   398.8   426.4   426.4     432
       7     4.7     5.5     5.5
   398.8   426.4   426.4     432
Pier Skew, UpSta & Num, DnSta & Num=  ,2015, 4 ,2015, 4 , 3 , 3 , 0 ,,
       7     4.7     5.5     5.5
   398.8   426.4   426.4     432
       7     4.7     5.5     5.5
   398.8   426.4   426.4     432
Pier Skew, UpSta & Num, DnSta & Num=  ,2075, 4 ,2075, 4 , 3 , 3 , 0 ,,
       7     4.7     5.5     5.5
   398.8   426.4   426.4     432
       7     4.7     5.5     5.5
   398.8   426.4   426.4     432
Pier Skew, UpSta & Num, DnSta & Num=  ,2135, 4 ,2135, 4 , 3 , 3 , 0 ,,
      10     7.7     8.5     8.5
   394.4     422     422     432
      10     7.7     8.5     8.5
   394.4     422     422     432
Pier Skew, UpSta & Num, DnSta & Num=  ,2340, 4 ,2340, 4 , 3 , 3 , 0 ,,
      10     7.7     8.5     8.5
   394.4     422     422     432
      10     7.7     8.5     8.5
   394.4     422     422     432
Pier Skew, UpSta & Num, DnSta & Num=  ,2400, 4 ,2400, 4 , 3 , 3 , 0 ,,
       7     4.7     5.5     5.5
   398.7   426.3   426.3     432
       7     4.7     5.5     5.5
   398.7   426.3   426.3     432
Pier Skew, UpSta & Num, DnSta & Num=  ,2460, 4 ,2460, 4 , 3 , 3 , 0 ,,
       7     4.7     5.5     5.5
   398.7   426.3   426.3     432
       7     4.7     5.5     5.5
   398.7   426.3   426.3     432
Pier Skew, UpSta & Num, DnSta & Num=  ,2520, 4 ,2520, 4 , 3 , 3 , 0 ,,
       7     4.7     5.5     5.5
   398.7   426.3   426.3     432
       7     4.7     5.5     5.5
   398.7   426.3   426.3     432
Pier Skew, UpSta & Num, DnSta & Num=  ,2580, 4 ,2580, 4 , 3 , 3 , 0 ,,
       7     4.7     5.5     5.5
   398.7   426.3   426.3     432
       7     4.7     5.5     5.5
   398.7   426.3   426.3     432
Pier Skew, UpSta & Num, DnSta & Num=  ,2640, 4 ,2640, 4 , 3 , 3 , 0 ,,
       7     4.7     5.5     5.5
   398.7   426.3   426.3     432
       7     4.7     5.5     5.5
   398.7   426.3   426.3     432
Pier Skew, UpSta & Num, DnSta & Num=  ,2700, 4 ,2700, 4 , 3 , 3 , 0 ,,
       7     4.7     5.5     5.5
   398.7   426.3   426.3     432
       7     4.7     5.5     5.5
   398.7   426.3   426.3     432
Pier Skew, UpSta & Num, DnSta & Num=  ,2760, 4 ,2760, 4 , 3 , 3 , 0 ,,
       7     4.7     5.5     5.5
   398.5   426.1   426.1     432
       7     4.7     5.5     5.5
   398.5   426.1   426.1     432
Pier Skew, UpSta & Num, DnSta & Num=  ,2820, 4 ,2820, 4 , 3 , 3 , 0 ,,
       7     4.7     5.5     5.5
   398.4     426     426     432
       7     4.7     5.5     5.5
   398.4     426     426     432
Pier Skew, UpSta & Num, DnSta & Num=  ,2880, 4 ,2880, 4 , 3 , 3 , 0 ,,
       7     4.7     5.5     5.5
   398.2   425.8   425.8     432
       7     4.7     5.5     5.5
   398.2   425.8   425.8     432
Pier Skew, UpSta & Num, DnSta & Num=  ,2940, 4 ,2940, 4 , 3 , 3 , 0 ,,
       7     4.7     5.5     5.5
   397.9   425.5   425.5     432
       7     4.7     5.5     5.5
   397.9   425.5   425.5     432
Pier Skew, UpSta & Num, DnSta & Num=  ,3000, 4 ,3000, 4 , 3 , 3 , 0 ,,
       7     4.7     5.5     5.5
   397.6   425.2   425.2     435
       7     4.7     5.5     5.5
   397.6   425.2   425.2     435
BR Coef= 1 , 1 , 1 ,0.9, 0 ,,,0.8,0,1.2,1,
WSPro=,,,, 1 ,,,, 0 ,,,, 0 ,,,,-1 ,-1 ,-1 , 0 , 0 , 0 , 0 , 0
BC Design=,, 0 ,, 0 ,,,,,,
BC HTab HWMax=430.2
BC Use User HTab Curves=0
BC User HTab FreeFlow(D)= 0

Type RM Length L Ch R = 1 ,121591  ,90,90,90
BEGIN DESCRIPTION:
This cross section corresponds to cross section 121607 of the non-georeferenced CDC model which was the source of this model.
END DESCRIPTION:
XS GIS Cut Line= 2
2485617.802418686970276.276066722483606.862870996969742.28861763
#Sta/Elev= 30
    1000  434.85  1035.1     435 1035.38  431.32 1037.76  432.61 1040.26  431.88
 1058.13     424 1088.53   414.2 1122.14  405.42  1151.9  402.62 1206.05     401
 2181.36     400 2191.68     393  2224.2  384.33 2238.23  383.25 2243.95  381.09
 2277.91  377.05 2317.17     377 2344.54     388 2354.87     391 2377.68     395
 2390.73     401 2450.41  401.61 2586.98     398  2818.9  399.19 2865.53  398.23
  2955.5     404 3007.18     414 3059.82     428 3073.83     435 3080.63  435.24
#Mann= 3 ,0,0
    1000    .055       0 2181.36    .035       0 2390.73    .055       0
Levee=-1,1000,429.76,-1,3073,429.76,,
#XS Ineff= 2 , 0
       0  2177.7     403 2390.73       0     401
Permanent Ineff=
       F       F
Bank Sta=2181.36,2390.73
XS Rating Curve= 0 ,0
Exp/Cntr=0.3,0.1

Type RM Length L Ch R = 1 ,121501  ,159,157,159
BEGIN DESCRIPTION:
This cross section corresponds to cross section 121517 of the non-georeferenced CDC model which was the source of this model.
END DESCRIPTION:
XS GIS Cut Line= 2
2485632.313544516970189.548877972483681.686212186969667.45149697
#Sta/Elev= 30
       0  430.71   15.24     430   47.56     424  131.34     403  160.29     401
 1179.17  400.03 1189.26     394  1200.7     389 1229.51     386 1247.86  376.17
 1297.94     376 1307.26  378.94 1316.68     384 1341.19     388 1354.57     393
 1378.85     394 1390.68     398 1396.01     401 1406.62     402 1508.18  400.17
 1659.67  395.71 1736.36     396 1858.35     400 1878.01     402 1894.19     405
 1949.96   419.2 1966.49  421.77 1971.34     424 2002.93     431 2019.29     431
#Mann= 3 ,0,0
       0    .055       0 1179.17    .035       0 1406.62    .055       0
Levee=-1,0,429.73,-1,2002,429.73,,
#XS Ineff= 2 , 0
       0 1174.65     403 1406.62       0     402
Permanent Ineff=
       F       F
Bank Sta=1179.17,1406.62
XS Rating Curve= 0 ,0
Exp/Cntr=0.3,0.1

Type RM Length L Ch R = 1 ,121344  ,174,170,174
BEGIN DESCRIPTION:
This cross section corresponds to cross section 121345 of the non-georeferenced CDC model which was the source of this model.
END DESCRIPTION:
XS GIS Cut Line= 2
2485710.568965446970048.576718972483841.74297866 6969549.1065893
#Sta/Elev= 30
       0     431   25.19     428  122.05     403  135.08     402  292.21     400
  933.89     400 1039.55     401 1069.35     397 1095.29   397.6 1117.63     401
  1194.8     401 1234.47  393.73 1239.02     391 1248.86  390.04 1282.54     372
 1300.85     370 1342.79     372 1347.27     374 1354.47     381  1358.9     383
 1394.71  390.67 1411.81     400 1421.12     401 1498.49     400 1614.15     396
 1743.11     397 1758.76     398 1781.64  401.93 1912.38     430 1934.42     431
#Mann= 3 ,0,0
       0    .055       0  1194.8    .035       0 1421.12    .055       0
Levee=-1,0,429.65,-1,1919,429.65,,
#XS Ineff= 2 , 0
       0  1194.8     401 1421.12       0     401
Permanent Ineff=
       F       F
Bank Sta=1194.8,1421.12
XS Rating Curve= 0 ,0
Exp/Cntr=0.3,0.1