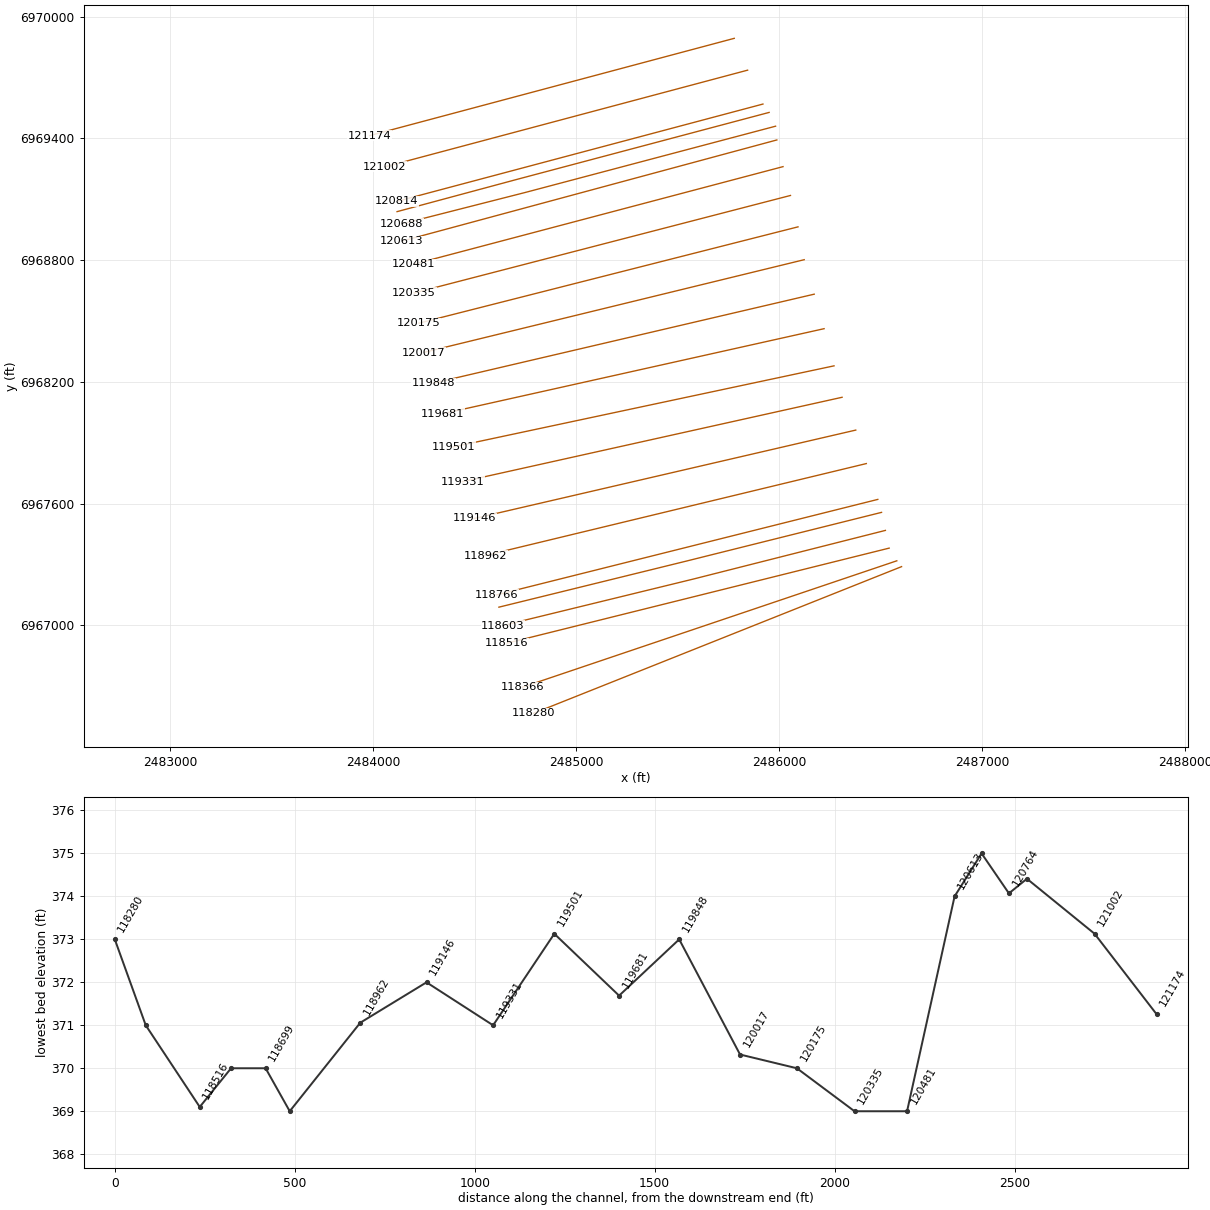
HEC-RAS study CDC_Consolidated_Model.prj: Upper Trinity CDC Consolidated Model

--- CDC_Consolidated_Model.g04 (geometry) --- (continued)

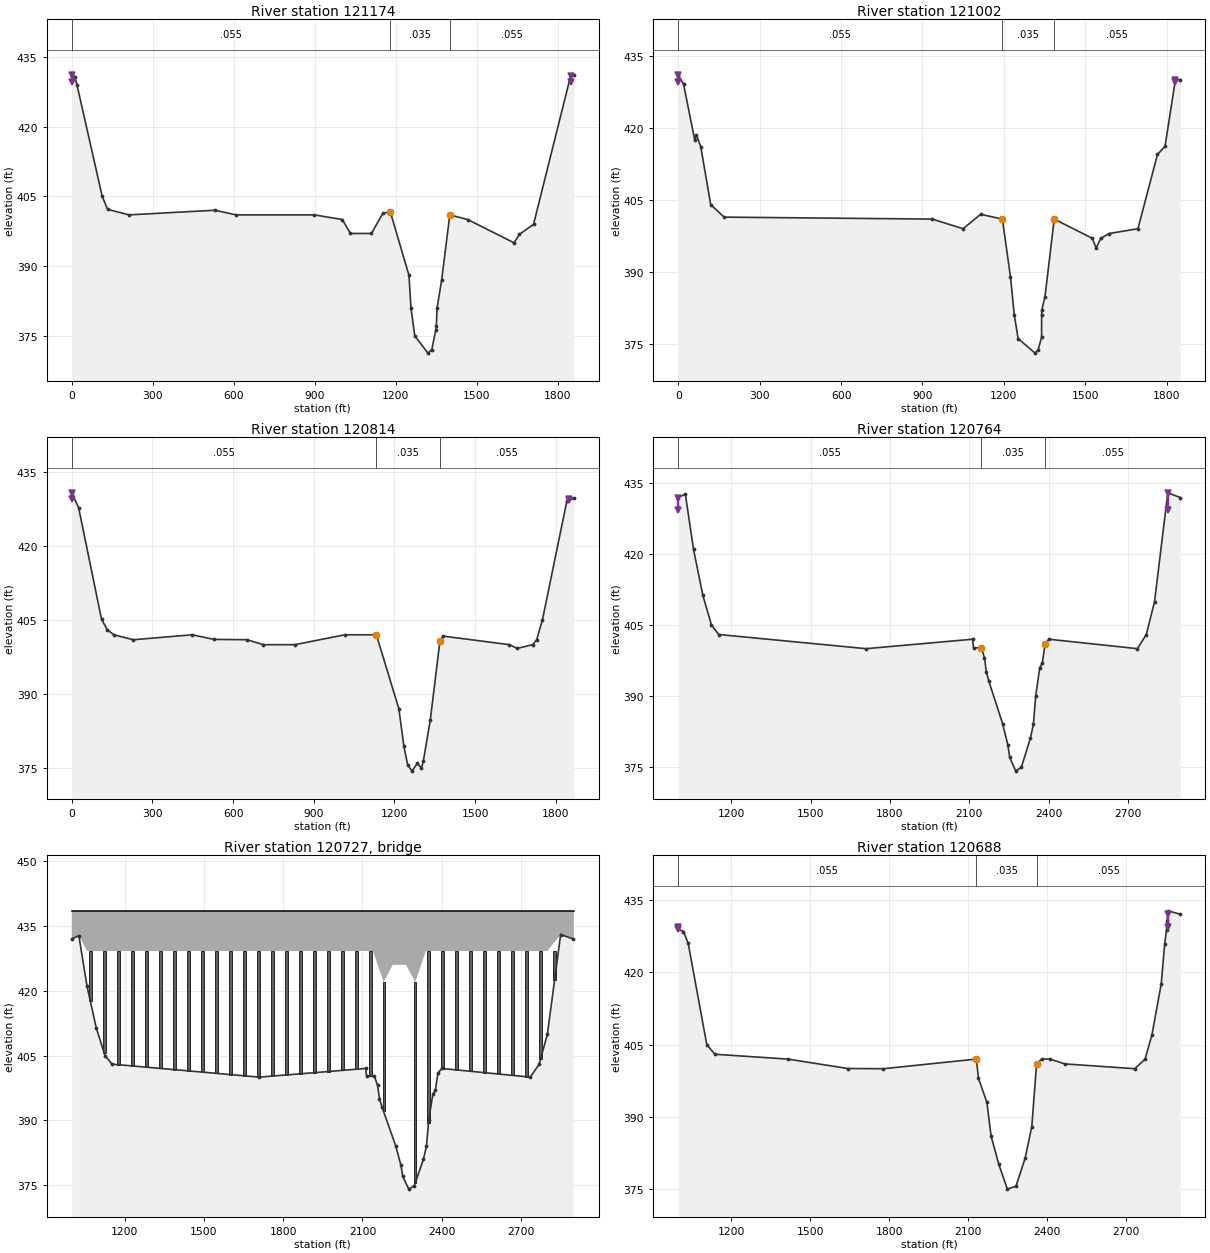
Type RM Length L Ch R = 1 ,121174  ,175,172,175
BEGIN DESCRIPTION:
This cross section corresponds to cross section 121174 of the non-georeferenced CDC model which was the source of this model.
END DESCRIPTION:
XS GIS Cut Line= 2
2485779.53601909 6969892.60590232483983.392957846969413.32208396
#Sta/Elev= 30
       0     431   11.39  430.56   19.14     429  112.55  405.02  132.46  402.19
  212.19     401  529.64     402  608.53     401  898.03     401 1001.61     400
 1031.54     397 1109.54     397 1152.33  401.41 1179.89  401.57 1248.54     388
 1255.92     381 1269.93     375 1318.69  371.26 1332.83     372 1348.08  376.29
 1349.77     377 1352.49  380.88 1369.54     387 1399.66     401 1465.87     400
 1637.31     395 1657.66  396.82 1709.65  398.96 1847.57     431 1858.99  431.13
#Mann= 3 ,0,0
       0    .055       0 1179.89    .035       0 1399.66    .055       0
Levee=-1,0,429.58,-1,1847,429.58,,
#XS Ineff= 2 , 0
       0 1179.89  401.57 1399.66       0     401
Permanent Ineff=
       F       F
Bank Sta=1179.89,1399.66
XS Rating Curve= 0 ,0
Exp/Cntr=0.3,0.1

Type RM Length L Ch R = 1 ,121002  ,193,188,193
BEGIN DESCRIPTION:
This cross section corresponds to cross section 121002 of the non-georeferenced CDC model which was the source of this model.
END DESCRIPTION:
XS GIS Cut Line= 2
2485845.35380083 6969735.79125532484057.748452196969259.30303505
#Sta/Elev= 30
       0     431   19.91     429   60.86  417.42   67.08  418.52   83.16     416
  119.69     404  169.23  401.41  936.15     401 1049.51     399 1114.29     402
 1194.32     401 1224.24     389 1238.23   381.1 1252.39  376.16 1314.81  373.13
  1326.1  373.79 1338.75  376.41 1338.97     381 1339.33     382 1351.33  384.86
 1385.42     401 1525.92     397 1539.74     395 1557.26     397 1587.45     398
 1693.88     399  1765.9  414.45 1793.75  416.12 1831.98     430 1850.02     430
#Mann= 3 ,0,0
       0    .055       0 1194.32    .035       0 1385.42    .055       0
Levee=-1,0,429.51,-1,1832,429.51,,
#XS Ineff= 2 , 0
       0 1194.32     401 1385.42       0     401
Permanent Ineff=
       F       F
Bank Sta=1194.32,1385.42
XS Rating Curve= 0 ,0
Exp/Cntr=0.3,0.1

Type RM Length L Ch R = 1 ,120814  ,50,50,50
BEGIN DESCRIPTION:
This cross section corresponds to cross section 120831 of the non-georeferenced CDC model which was the source of this model.
END DESCRIPTION:
XS GIS Cut Line= 2
2485920.959292686969568.774528972484116.033440596969088.93362513
#Sta/Elev= 30
       0  430.73   25.41  427.74  110.61  405.16  131.82  403.06   156.4     402
  229.22     401  448.25     402   528.5  401.07   651.9     401  712.73     400
  829.76     400  1015.7     402 1133.02     402 1216.91     387  1235.3  379.46
 1249.46   375.7 1265.42  374.41 1285.36     376 1300.79     375 1307.86  376.49
 1333.64  384.76 1369.58  400.77 1380.72  401.74 1628.04     400 1656.88  399.24
 1714.17     400 1729.27     401 1750.72     405 1841.35     429 1867.62  429.61
#Mann= 3 ,0,0
       0    .055       0 1133.02    .035       0 1369.58    .055       0
Levee=-1,0,429.44,-1,1849,429.44,,
#XS Ineff= 2 , 0
       0 1133.02     402 1369.58       0  400.77
Permanent Ineff=
       F       F
Bank Sta=1133.02,1369.58
XS Rating Curve= 0 ,0
Exp/Cntr=0.3,0.1

Type RM Length L Ch R = 1 ,120764  ,76,76,76
BEGIN DESCRIPTION:
This cross section corresponds to cross section 120765 of the non-georeferenced CDC model which was the source of this model.
END DESCRIPTION:
XS GIS Cut Line= 3
2485951.338825086969527.540359472484709.564405776969197.79298747
2484118.11119235 6969038.6489488
#Sta/Elev= 30
    1000     432 1026.88  432.74 1057.86     421  1093.2  411.27 1125.67     405
 1152.91     403 1709.91     400 2112.15     402 2115.92  400.17 2145.42   400.2
 2157.26  398.07 2164.48     395 2174.13  393.06 2225.66  384.14 2245.68  379.59
 2252.57     377 2275.45  374.07 2296.66   374.9 2330.61     381 2342.19     384
 2350.83     390 2366.26     396 2376.02  396.98 2385.87     401 2400.61     402
 2735.14     400 2768.84     403  2799.9  409.95 2850.04     433  2897.3     432
#Mann= 3 ,0,0
    1000    .055       0 2145.42    .035       0 2385.87    .055       0
Levee=-1,1000,429.41,-1,2850,429.41,,
#XS Ineff= 2 , 0
       0 2145.42   400.2 2385.87       0     401
Permanent Ineff=
       F       F
Bank Sta=2145.42,2385.87
XS Rating Curve= 0 ,0
Exp/Cntr=0.3,0.1

Type RM Length L Ch R = 3 ,120727  ,,,
BEGIN DESCRIPTION:
120729  Commerce Street
END DESCRIPTION:
Node Name=Commerce Street
Bridge Culvert--1,0,-1,-1, 0
Deck Dist Width WeirC Skew NumUp NumDn MinLoCord MaxHiCord MaxSubmerge Is_Ogee
3,68,2.6,0, 8, 8, , , 0.95, 0, ,,,
    1000    2140    2180    2215    2265    2300    2340    2900
   438.5   438.5   438.5   438.5   438.5   438.5   438.5   438.5
   429.2   429.2     422     426     426     422   429.2   429.2
    1000    2140    2180    2215    2265    2300    2340    2900
   438.5   438.5   438.5   438.5   438.5   438.5   438.5   438.5
   429.2   429.2     422     426     426     422   429.2   429.2
Pier Skew, UpSta & Num, DnSta & Num=  ,1070, 5 ,1070, 5 , 3 , 3 , 0 ,,
       5     2.5     3.7     3.7      10
   395.5   425.5   425.5     427   429.5
       5     2.5     3.7     3.7      10
   395.5   425.5   425.5     427   429.5
Pier Skew, UpSta & Num, DnSta & Num=  ,1123, 5 ,1123, 5 , 3 , 3 , 0 ,,
       5     2.5     3.7     3.7      10
   395.5   425.5   425.5     427   429.5
       5     2.5     3.7     3.7      10
   395.5   425.5   425.5     427   429.5
Pier Skew, UpSta & Num, DnSta & Num=  ,1176, 5 ,1176, 5 , 3 , 3 , 0 ,,
       5     2.5     3.7     3.7      10
   395.5   425.5   425.5     427   429.5
       5     2.5     3.7     3.7      10
   395.5   425.5   425.5     427   429.5
Pier Skew, UpSta & Num, DnSta & Num=  ,1229, 5 ,1229, 5 , 3 , 3 , 0 ,,
       5     2.5     3.7     3.7      10
   395.5   425.5   425.5     427   429.5
       5     2.5     3.7     3.7      10
   395.5   425.5   425.5     427   429.5
Pier Skew, UpSta & Num, DnSta & Num=  ,1282, 5 ,1282, 5 , 3 , 3 , 0 ,,
       5     2.5     3.7     3.7      10
   395.5   425.5   425.5     427   429.5
       5     2.5     3.7     3.7      10
   395.5   425.5   425.5     427   429.5
Pier Skew, UpSta & Num, DnSta & Num=  ,1335, 5 ,1335, 5 , 3 , 3 , 0 ,,
       5     2.5     3.7     3.7      10
   395.5   425.5   425.5     427   429.5
       5     2.5     3.7     3.7      10
   395.5   425.5   425.5     427   429.5
Pier Skew, UpSta & Num, DnSta & Num=  ,1388, 5 ,1388, 5 , 3 , 3 , 0 ,,
       5     2.5     3.7     3.7      10
   395.5   425.5   425.5     427   429.5
       5     2.5     3.7     3.7      10
   395.5   425.5   425.5     427   429.5
Pier Skew, UpSta & Num, DnSta & Num=  ,1441, 5 ,1441, 5 , 3 , 3 , 0 ,,
       5     2.5     3.7     3.7      10
   395.5   425.5   425.5     427   429.5
       5     2.5     3.7     3.7      10
   395.5   425.5   425.5     427   429.5
Pier Skew, UpSta & Num, DnSta & Num=  ,1494, 5 ,1494, 5 , 3 , 3 , 0 ,,
       5     2.5     3.7     3.7      10
   395.5   425.5   425.5     427   429.5
       5     2.5     3.7     3.7      10
   395.5   425.5   425.5     427   429.5
Pier Skew, UpSta & Num, DnSta & Num=  ,1547, 5 ,1547, 5 , 3 , 3 , 0 ,,
       5     2.5     3.7     3.7      10
   395.5   425.5   425.5     427   429.5
       5     2.5     3.7     3.7      10
   395.5   425.5   425.5     427   429.5
Pier Skew, UpSta & Num, DnSta & Num=  ,1600, 5 ,1600, 5 , 3 , 3 , 0 ,,
       5     2.5     3.7     3.7      10
   395.5   425.5   425.5     427   429.5
       5     2.5     3.7     3.7      10
   395.5   425.5   425.5     427   429.5
Pier Skew, UpSta & Num, DnSta & Num=  ,1653, 5 ,1653, 5 , 3 , 3 , 0 ,,
       5     2.5     3.7     3.7      10
   395.5   425.5   425.5     427   429.5
       5     2.5     3.7     3.7      10
   395.5   425.5   425.5     427   429.5
Pier Skew, UpSta & Num, DnSta & Num=  ,1706, 5 ,1706, 5 , 3 , 3 , 0 ,,
       5     2.5     3.7     3.7      10
   395.5   425.5   425.5     427   429.5
       5     2.5     3.7     3.7      10
   395.5   425.5   425.5     427   429.5
Pier Skew, UpSta & Num, DnSta & Num=  ,1759, 5 ,1759, 5 , 3 , 3 , 0 ,,
       5     2.5     3.7     3.7      10
   395.5   425.5   425.5     427   429.5
       5     2.5     3.7     3.7      10
   395.5   425.5   425.5     427   429.5
Pier Skew, UpSta & Num, DnSta & Num=  ,1812, 5 ,1812, 5 , 3 , 3 , 0 ,,
       5     2.5     3.7     3.7      10
   395.5   425.5   425.5     427   429.5
       5     2.5     3.7     3.7      10
   395.5   425.5   425.5     427   429.5
Pier Skew, UpSta & Num, DnSta & Num=  ,1865, 5 ,1865, 5 , 3 , 3 , 0 ,,
       5     2.5     3.7     3.7      10
   395.5   425.5   425.5     427   429.5
       5     2.5     3.7     3.7      10
   395.5   425.5   425.5     427   429.5
Pier Skew, UpSta & Num, DnSta & Num=  ,1918, 5 ,1918, 5 , 3 , 3 , 0 ,,
       5     2.5     3.7     3.7      10
   395.5   425.5   425.5     427   429.5
       5     2.5     3.7     3.7      10
   395.5   425.5   425.5     427   429.5
Pier Skew, UpSta & Num, DnSta & Num=  ,1971, 5 ,1971, 5 , 3 , 3 , 0 ,,
       5     2.5     3.7     3.7      10
   395.5   425.5   425.5     427   429.5
       5     2.5     3.7     3.7      10
   395.5   425.5   425.5     427   429.5
Pier Skew, UpSta & Num, DnSta & Num=  ,2024, 5 ,2024, 5 , 3 , 3 , 0 ,,
       5     2.5     3.7     3.7      10
   395.5   425.5   425.5     427   429.5
       5     2.5     3.7     3.7      10
   395.5   425.5   425.5     427   429.5
Pier Skew, UpSta & Num, DnSta & Num=  ,2077, 5 ,2077, 5 , 3 , 3 , 0 ,,
       5     2.5     3.7     3.7      10
   395.5   425.5   425.5     427   429.5
       5     2.5     3.7     3.7      10
   395.5   425.5   425.5     427   429.5
Pier Skew, UpSta & Num, DnSta & Num=  ,2130, 5 ,2130, 5 , 3 , 3 , 0 ,,
       5     2.5     3.7     3.7      10
   395.5   425.5   425.5     427   429.5
       5     2.5     3.7     3.7      10
   395.5   425.5   425.5     427   429.5
Pier Skew, UpSta & Num, DnSta & Num=  ,2180, 6 ,2180, 6 , 5 , 5 , 0 ,,
       8       8       6     3.4       5       5
     370     388     388     419     419     425
       8       8       6     3.4       5       5
     370     388     388     419     419     425
Pier Skew, UpSta & Num, DnSta & Num=  ,2300, 6 ,2300, 6 , 5 , 5 , 0 ,,
       8       8       6     3.4       5       5
     370     388     388     419     419     425
       8       8       6     3.4       5       5
     370     388     388     419     419     425
Pier Skew, UpSta & Num, DnSta & Num=  ,2350, 5 ,2350, 5 , 3 , 3 , 0 ,,
       5     2.5     3.7     3.7      10
   395.5   425.5   425.5     427   429.5
       5     2.5     3.7     3.7      10
   395.5   425.5   425.5     427   429.5
Pier Skew, UpSta & Num, DnSta & Num=  ,2403, 5 ,2403, 5 , 3 , 3 , 0 ,,
       5     2.5     3.7     3.7      10
   395.5   425.5   425.5     427   429.5
       5     2.5     3.7     3.7      10
   395.5   425.5   425.5     427   429.5
Pier Skew, UpSta & Num, DnSta & Num=  ,2456, 5 ,2456, 5 , 3 , 3 , 0 ,,
       5     2.5     3.7     3.7      10
   395.5   425.5   425.5     427   429.5
       5     2.5     3.7     3.7      10
   395.5   425.5   425.5     427   429.5
Pier Skew, UpSta & Num, DnSta & Num=  ,2509, 5 ,2509, 5 , 3 , 3 , 0 ,,
       5     2.5     3.7     3.7      10
   395.5   425.5   425.5     427   429.5
       5     2.5     3.7     3.7      10
   395.5   425.5   425.5     427   429.5
Pier Skew, UpSta & Num, DnSta & Num=  ,2562, 5 ,2562, 5 , 3 , 3 , 0 ,,
       5     2.5     3.7     3.7      10
   395.5   425.5   425.5     427   429.5
       5     2.5     3.7     3.7      10
   395.5   425.5   425.5     427   429.5
Pier Skew, UpSta & Num, DnSta & Num=  ,2615, 5 ,2615, 5 , 3 , 3 , 0 ,,
       5     2.5     3.7     3.7      10
   395.5   425.5   425.5     427   429.5
       5     2.5     3.7     3.7      10
   395.5   425.5   425.5     427   429.5
Pier Skew, UpSta & Num, DnSta & Num=  ,2668, 5 ,2668, 5 , 3 , 3 , 0 ,,
       5     2.5     3.7     3.7      10
   395.5   425.5   425.5     427   429.5
       5     2.5     3.7     3.7      10
   395.5   425.5   425.5     427   429.5
Pier Skew, UpSta & Num, DnSta & Num=  ,2721, 5 ,2721, 5 , 3 , 3 , 0 ,,
       5     2.5     3.7     3.7      10
   395.5   425.5   425.5     427   429.5
       5     2.5     3.7     3.7      10
   395.5   425.5   425.5     427   429.5
Pier Skew, UpSta & Num, DnSta & Num=  ,2774, 5 ,2774, 5 , 3 , 3 , 0 ,,
       5     2.5     3.7     3.7      10
   395.5   425.5   425.5     427   429.5
       5     2.5     3.7     3.7      10
   395.5   425.5   425.5     427   429.5
Pier Skew, UpSta & Num, DnSta & Num=  ,2827, 5 ,2827, 5 , 3 , 3 , 0 ,,
       5     2.5     3.7     3.7      10
   395.5   425.5   425.5     427   429.5
       5     2.5     3.7     3.7      10
   395.5   425.5   425.5     427   429.5
Pier Skew, UpSta & Num, DnSta & Num=  ,2847, 2 ,2847, 2 , 0 , 0 , 0 ,,
     3.5     3.5
       0     430
     3.5     3.5
       0     430
Pier Skew, UpSta & Num, DnSta & Num=  ,2867, 2 ,2867, 2 , 0 , 0 , 0 ,,
     3.5     3.5
       0     430
     3.5     3.5
       0     430
BR Coef= 1 , 1 , 1 ,0.9, 0 ,,,0.8,0,1.33,1,
WSPro=,,,, 1 ,,,, 0 ,,,, 0 ,,,,-1 ,-1 ,-1 , 0 , 0 , 0 , 0 , 0
BC Design=,, 0 ,, 0 ,,,,,,
BC HTab HWMax=430.6
BC Use User HTab Curves=0
BC User HTab FreeFlow(D)= 0

Type RM Length L Ch R = 1 ,120688  ,75,75,75
BEGIN DESCRIPTION:
This cross section corresponds to cross section 120693 of the non-georeferenced CDC model which was the source of this model.
END DESCRIPTION:
XS GIS Cut Line= 3
2485983.205231166969459.677962382484749.045954086969132.97520372
2484140.537984766968978.00733779
#Sta/Elev= 30
    1000     429 1019.79  428.46 1037.81  426.01 1108.32     405 1139.22     403
 1415.63     402 1643.53  400.04 1778.07     400 2130.77     402 2139.03     398
 2171.02     393 2186.78     386 2215.84  380.18 2248.46     375 2281.21   375.6
  2316.2  381.46 2341.22     388 2359.35  400.95 2378.33     402 2410.22     402
 2466.25     401 2732.05     400 2770.98     402 2796.84     407 2832.16  417.59
 2845.43  425.95 2852.28  428.82 2854.06  430.57 2858.47  432.78  2904.6  432.07
#Mann= 3 ,0,0
    1000    .055       0 2130.77    .035       0 2359.35    .055       0
Levee=-1,1000,429.39,-1,2857,429.39,,
#XS Ineff= 2 , 0
       0 2130.77     402 2359.35       0  400.95
Permanent Ineff=
       F       F
Bank Sta=2130.77,2359.35
XS Rating Curve= 0 ,0
Exp/Cntr=0.3,0.1

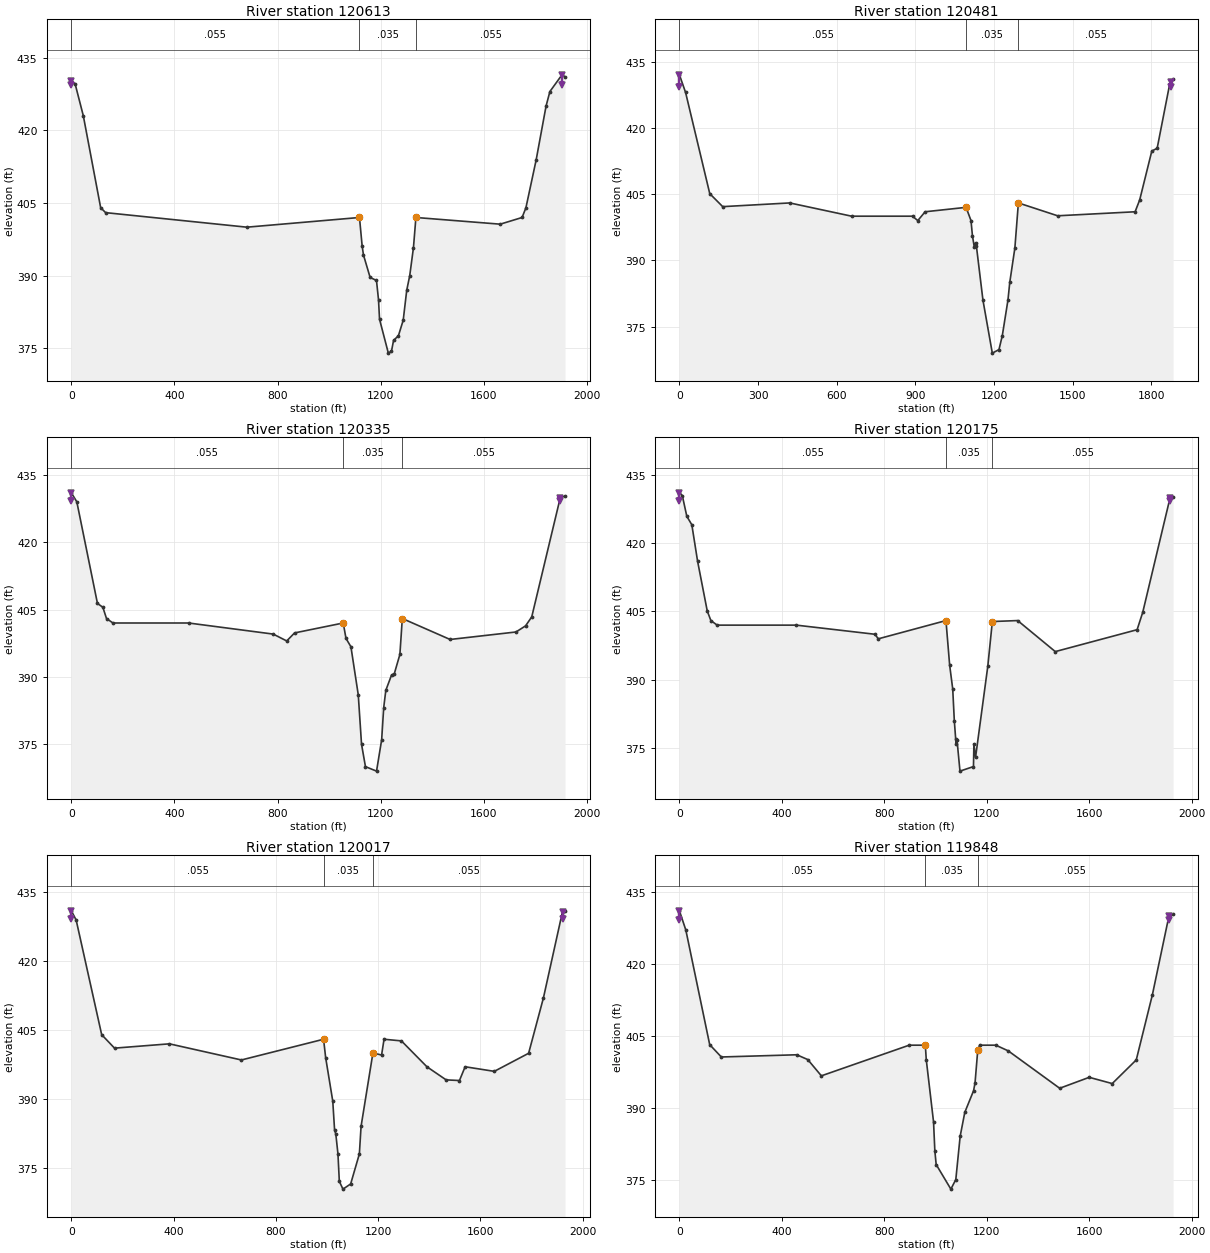
Type RM Length L Ch R = 1 ,120613  ,133,132,127
BEGIN DESCRIPTION:
This cross section corresponds to cross section 120629 of the non-georeferenced CDC model which was the source of this model.
END DESCRIPTION:
XS GIS Cut Line= 2
2485989.374182086969391.878229222484140.178405436968892.95403022
#Sta/Elev= 30
       0  430.14   14.53   429.6   46.41     423  113.73  404.02  133.02     403
  680.96     400 1117.82     402 1128.18  396.11 1133.32  394.26 1159.14  389.62
  1183.8     389 1191.71     385 1195.62     381 1229.79     374 1241.99   374.4
 1250.09  376.63  1268.8  377.58 1287.47  380.78 1301.12  386.97 1312.81     390
 1327.25  395.78 1336.75     402 1663.85  400.62 1748.67     402 1763.53     404
 1803.15  413.85  1841.7     425 1856.55     428 1903.44  431.45 1915.32     431
#Mann= 3 ,0,0
       0    .055       0 1117.82    .035       0 1336.75    .055       0
Levee=-1,0,429.36,-1,1903,429.36,,
#XS Ineff= 2 , 0
       0 1117.82     402 1336.75       0     402
Permanent Ineff=
       F       F
Bank Sta=1117.82,1336.75
XS Rating Curve= 0 ,0
Exp/Cntr=0.3,0.1

Type RM Length L Ch R = 1 ,120481  ,147,146,140
BEGIN DESCRIPTION:
This cross section corresponds to cross section 120483 of the non-georeferenced CDC model which was the source of this model.
END DESCRIPTION:
XS GIS Cut Line= 2
2486019.86854368 6969260.38078882484199.405321096968779.40373239
#Sta/Elev= 30
       0     432    23.5     428  115.71   405.1  165.07  402.16  420.81     403
  656.72     400  888.94     400  909.06     399  937.11     401 1093.25     402
 1112.08     399 1117.48   395.6 1124.58     393 1129.22     394 1132.78  393.17
 1157.61     381 1193.34     369 1218.72   369.8 1231.39  372.94    1253     381
 1259.87     385 1279.39   392.8 1292.76     403 1442.45  400.09 1737.97     401
 1755.37  403.67 1801.57  414.73 1822.14  415.39 1870.17     430 1882.93     431
#Mann= 3 ,0,0
       0    .055       0 1093.25    .035       0 1292.76    .055       0
Levee=-1,0,429.31,-1,1876,429.31,,
#XS Ineff= 2 , 0
       0 1093.25     402 1292.76       0     403
Permanent Ineff=
       F       F
Bank Sta=1093.25,1292.76
XS Rating Curve= 0 ,0
Exp/Cntr=0.3,0.1

Type RM Length L Ch R = 1 ,120335  ,162,160,154
BEGIN DESCRIPTION:
This cross section corresponds to cross section 120337 of the non-georeferenced CDC model which was the source of this model.
END DESCRIPTION:
XS GIS Cut Line= 2
2486056.52857533 6969118.34563982484202.34232309 6968637.9804588
#Sta/Elev= 30
       0     431   21.19     429  101.28  406.36  122.24   405.5  136.38     403
  161.48     402  454.85     402  783.17  399.53  835.63     398  866.07  399.79
 1054.81     402 1065.54  398.57 1084.72   396.7 1113.16     386  1125.8     375
 1141.06     370 1184.07     369 1203.95     376 1211.87  383.15 1220.07     387
 1242.19  390.39 1252.99   390.7 1274.66     395 1284.03     403 1469.49  398.33
 1725.12     400 1762.22  401.36  1786.2  403.36 1897.26     430  1915.4  430.23
#Mann= 3 ,0,0
       0    .055       0 1054.81    .035       0 1284.03    .055       0
Levee=-1,0,429.25,-1,1897,429.25,,
#XS Ineff= 2 , 0
       0 1054.81     402 1284.03       0     403
Permanent Ineff=
       F       F
Bank Sta=1054.81,1284.03
XS Rating Curve= 0 ,0
Exp/Cntr=0.3,0.1

Type RM Length L Ch R = 1 ,120175  ,164,158,152
BEGIN DESCRIPTION:
This cross section corresponds to cross section 120192 of the non-georeferenced CDC model which was the source of this model.
END DESCRIPTION:
XS GIS Cut Line= 2
2486093.731256846968963.693718142484225.652972016968489.22977205
#Sta/Elev= 30
       0     431   11.18  430.41   28.86  425.85    48.4     424   70.93     416
  108.63   405.1  122.78     403  147.32     402  456.25     402  763.22     400
  776.39     399 1040.55     403    1055  393.21 1066.97     388 1073.23     381
 1079.95     376 1080.59     377 1083.83  376.73 1095.25     370 1147.96     371
 1149.64     376 1156.06     373 1203.93     393 1221.62  402.79  1320.5     403
 1467.32   396.2 1786.84     401 1808.85  404.82 1915.85     430 1927.39     430
#Mann= 3 ,0,0
       0    .055       0 1040.55    .035       0 1221.62    .055       0
Levee=-1,0,429.2,-1,1915,429.2,,
#XS Ineff= 2 , 0
       0 1040.55     403 1221.62       0  402.79
Permanent Ineff=
       F       F
Bank Sta=1040.55,1221.62
XS Rating Curve= 0 ,0
Exp/Cntr=0.3,0.1

Type RM Length L Ch R = 1 ,120017  ,176,169,164
BEGIN DESCRIPTION:
This cross section corresponds to cross section 120023 of the non-georeferenced CDC model which was the source of this model.
END DESCRIPTION:
XS GIS Cut Line= 2
2486124.209870436968801.863661212484248.318937186968344.54928714
#Sta/Elev= 30
       0     431   18.77     429   118.6     404  168.81  401.06   383.5     402
  665.14  398.48  986.47     403  994.56     399 1022.42   389.5 1029.46  383.24
 1034.36  382.32 1042.68     378 1048.08     372 1062.28  370.32  1092.4  371.45
 1126.46     378 1133.08     384 1179.43     400 1213.32  399.56 1222.98     403
 1290.88  402.64 1390.61     397 1465.81  394.14 1517.89     394 1540.02     397
 1654.18     396 1788.38  399.94 1846.25     412 1921.56  430.98 1930.83     431
#Mann= 3 ,0,0
       0    .055       0  986.47    .035       0 1179.43    .055       0
Levee=-1,0,429.13,-1,1921,429.13,,
#XS Ineff= 2 , 0
       0  986.47     403 1179.43       0     400
Permanent Ineff=
       F       F
Bank Sta=986.47,1179.43
XS Rating Curve= 0 ,0
Exp/Cntr=0.3,0.1

Type RM Length L Ch R = 1 ,119848  ,172,167,160
BEGIN DESCRIPTION:
This cross section corresponds to cross section 119855 of the non-georeferenced CDC model which was the source of this model.
END DESCRIPTION:
XS GIS Cut Line= 2
 2486173.58444366968632.007701712484296.600008586968193.53088838
#Sta/Elev= 30
       0     431   24.99     427  118.19  403.11   163.6  400.54  458.09     401
  501.11     400  554.18  396.61  897.12     403  960.13     403  963.67     400
  992.17     387  997.19     381 1002.39  378.13 1059.81     373  1079.1     375
 1096.02     384 1114.15     389 1148.41  393.51 1154.19  395.15 1164.68  401.92
  1172.1     403 1235.19     403 1283.96  401.81 1484.68  394.02 1599.93   396.3
 1689.79     395 1783.63  399.93 1846.52  413.49  1911.6     430 1927.52  430.26
#Mann= 3 ,0,0
       0    .055       0  960.13    .035       0 1164.68    .055       0
Levee=-1,0,429.07,-1,1911,429.07,,
#XS Ineff= 2 , 0
       0  960.13     403 1164.68       0  401.92
Permanent Ineff=
       F       F
Bank Sta=960.13,1164.68
XS Rating Curve= 0 ,0
Exp/Cntr=0.3,0.1

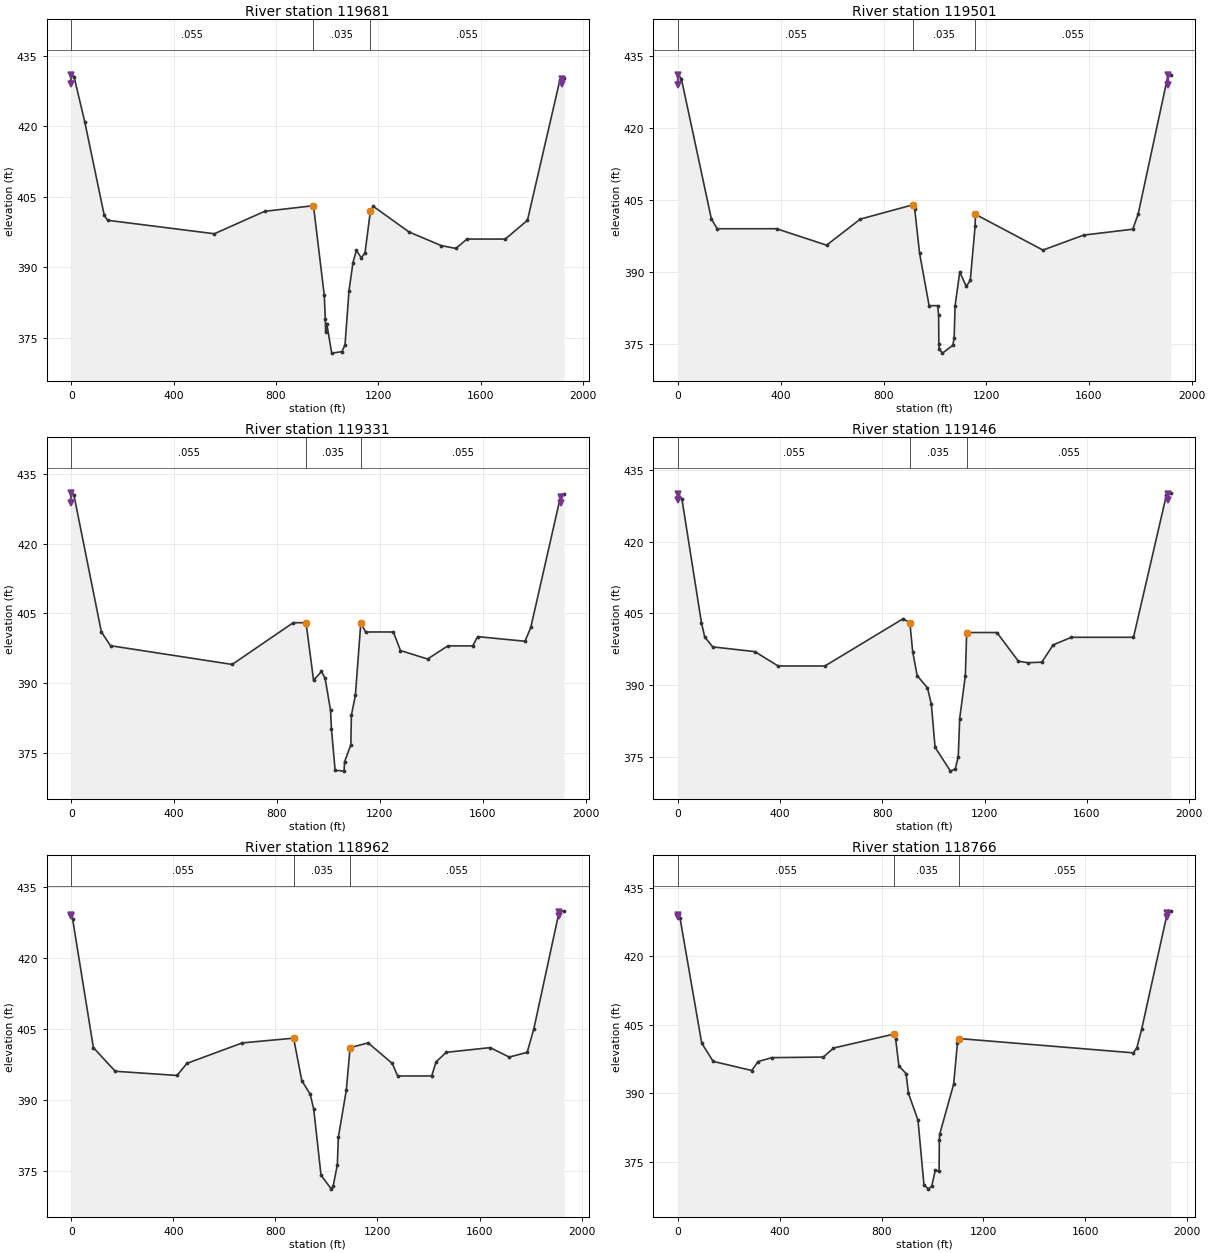
Type RM Length L Ch R = 1 ,119681  ,188,180,174
BEGIN DESCRIPTION:
This cross section corresponds to cross section 119686 of the non-georeferenced CDC model which was the source of this model.
END DESCRIPTION:
XS GIS Cut Line= 2
2486222.250356766968461.946362052484343.134692436968042.82088797
#Sta/Elev= 30
       0     431   10.57  430.63   52.51     421  128.89  401.03  142.29     400
     559  397.13  755.47  401.91  946.14  403.11  988.45     384  992.44   378.9
  993.74  376.19   998.1     378 1017.45  371.69 1057.41     372 1069.48  373.47
 1084.98  384.99 1100.52  390.97 1113.93  393.62 1132.73     392 1147.37     393
  1168.8     402 1180.12  402.97 1319.78   397.5 1445.89   394.6  1502.7     394
 1545.81     396 1695.57     396  1782.3     400 1909.41     430 1925.29  430.43
#Mann= 3 ,0,0
       0    .055       0  946.14    .035       0  1168.8    .055       0
Levee=-1,0,429,-1,1917,429,,
#XS Ineff= 2 , 0
       0  946.14  403.11  1168.8       0     402
Permanent Ineff=
       F       F
Bank Sta=946.14,1168.8
XS Rating Curve= 0 ,0
Exp/Cntr=0.3,0.1

Type RM Length L Ch R = 1 ,119501  ,166,170,176
BEGIN DESCRIPTION:
This cross section corresponds to cross section 119518 of the non-georeferenced CDC model which was the source of this model.
END DESCRIPTION:
XS GIS Cut Line= 2
2486271.157083096968278.820744052484394.622778426967879.26576889
#Sta/Elev= 30
       0     431   12.82   430.2  129.83     401  152.35     399  383.47     399
  578.26  395.58  709.66     401  916.11     404  921.65     403  940.13     394
   977.5     383  1010.7     383 1014.59     381 1015.48     375 1016.85     374
 1029.46  373.13 1069.96  374.77 1074.95   376.3 1078.69     383 1096.86     390
 1122.16     387 1137.79  388.26 1156.53   399.5 1157.73     402 1420.52  394.56
 1579.02  397.67 1770.52   398.9 1791.23     402 1908.09     431  1918.6     431
#Mann= 3 ,0,0
       0    .055       0  916.11    .035       0 1157.73    .055       0
Levee=-1,0,428.94,-1,1908,428.94,,
#XS Ineff= 2 , 0
       0  916.11     404 1157.73       0     402
Permanent Ineff=
       F       F
Bank Sta=916.11,1157.73
XS Rating Curve= 0 ,0
Exp/Cntr=0.3,0.1

Type RM Length L Ch R = 1 ,119331  ,181,185,191
BEGIN DESCRIPTION:
This cross section corresponds to cross section 119334 of the non-georeferenced CDC model which was the source of this model.
END DESCRIPTION:
XS GIS Cut Line= 2
2486310.874195256968123.94835038  2484440.1052996967708.10305347
#Sta/Elev= 30
       0     431   10.29  430.49  116.97     401  152.55  398.04  625.72     394
  863.05     403  912.93     403  942.19   390.6  972.96  392.48  987.22     391
 1008.22  384.11 1011.59  380.15 1026.07   371.2 1060.69     371 1062.74     373
 1087.16  376.68 1089.25     383 1104.81  387.35    1126     403 1144.53     401
 1252.53     401 1280.27     397 1385.51  395.17 1464.32     398 1561.12     398
 1580.36     400 1764.49     399 1786.98  401.97 1901.88     430 1916.43  430.79
#Mann= 3 ,0,0
       0    .055       0  912.93    .035       0    1126    .055       0
Levee=-1,0,428.88,-1,1903,428.88,,
#XS Ineff= 2 , 0
       0  912.93     403    1126       0     403
Permanent Ineff=
       F       F
Bank Sta=912.93,1126
XS Rating Curve= 0 ,0
Exp/Cntr=0.3,0.1

Type RM Length L Ch R = 1 ,119146  ,180,184,190
BEGIN DESCRIPTION:
This cross section corresponds to cross section 119150 of the non-georeferenced CDC model which was the source of this model.
END DESCRIPTION:
XS GIS Cut Line= 2
2486378.220517256967962.264290562484498.580575766967526.63983372
#Sta/Elev= 30
       0     430   14.95     429    91.7     403   104.4  400.08  135.54     398
  300.83     397  391.89     394  575.03     394  881.66   403.9  907.82     403
  918.69     397  936.23     392  976.64  389.41  991.79     386  1006.3     377
 1066.58     372 1085.79  372.49 1097.19  375.05  1102.8     383 1124.92     392
 1130.13     401  1248.5     401  1332.5     395  1370.6  394.68 1424.41   394.8
 1468.74  398.41 1539.85     400 1783.33     400 1912.52  429.83 1929.46  430.23
#Mann= 3 ,0,0
       0    .055       0  907.82    .035       0 1130.13    .055       0
Levee=-1,0,428.82,-1,1920,428.82,,
#XS Ineff= 2 , 0
       0  907.82     403 1130.13       0     401
Permanent Ineff=
       F       F
Bank Sta=907.82,1130.13
XS Rating Curve= 0 ,0
Exp/Cntr=0.3,0.1

Type RM Length L Ch R = 1 ,118962  ,192,196,203
BEGIN DESCRIPTION:
This cross section corresponds to cross section 118966 of the non-georeferenced CDC model which was the source of this model.
END DESCRIPTION:
XS GIS Cut Line= 2
2486430.278484026967797.283321312484552.779614336967344.30686505
#Sta/Elev= 30
       0     429    5.13  428.24   86.49     401  172.01     396  414.46  395.11
  453.27  397.67  670.45     402  871.35     403  903.51     394  936.19  391.15
  950.17     388  978.76     374 1019.48  371.06 1026.31  371.66 1042.87  376.27
 1046.55     382 1077.88     392 1092.67     401  1163.6     402 1257.94  397.66
 1279.32     395 1412.44     395 1429.89     398 1469.53     400 1641.83     401
  1716.4     399 1786.84     400    1813     405 1912.86  429.94 1931.37  429.86
#Mann= 3 ,0,0
       0    .055       0  871.35    .035       0 1092.67    .055       0
Levee=-1,0,428.76,-1,1912,428.76,,
#XS Ineff= 2 , 0
       0  871.35     403 1092.67       0     401
Permanent Ineff=
       F       F
Bank Sta=871.35,1092.67
XS Rating Curve= 0 ,0
Exp/Cntr=0.3,0.1

Type RM Length L Ch R = 1 ,118766  ,67,67,67
BEGIN DESCRIPTION:
This cross section corresponds to cross section 118782 of the non-georeferenced CDC model which was the source of this model.
END DESCRIPTION:
XS GIS Cut Line= 2
2486486.841691086967620.720682292484607.959293996967150.00082321
#Sta/Elev= 30
       0     429    7.97  428.33   92.96     401  137.99     397   289.8     395
  314.63  396.97     369  397.82  571.56  397.95  610.94  399.92  849.71     403
  855.15     402  868.09     396  896.21  394.34  905.64     390  943.18  384.11
  966.46     370  984.23     369  997.24  369.68  1011.3  373.21 1026.03  372.87
 1027.09  379.76 1028.26     381 1083.27     392 1098.15     401 1105.76     402
 1789.86  398.87 1803.59     400 1822.12     404 1925.09     430 1936.95     430
#Mann= 3 ,0,0
       0    .055       0  849.71    .035       0 1105.76    .055       0
Levee=-1,0,428.7,-1,1923,428.7,,
#XS Ineff= 2 , 0
       0  849.71     403 1105.76       0     402
Permanent Ineff=
       F       F
Bank Sta=849.71,1105.76
XS Rating Curve= 0 ,0
Exp/Cntr=0.3,0.1

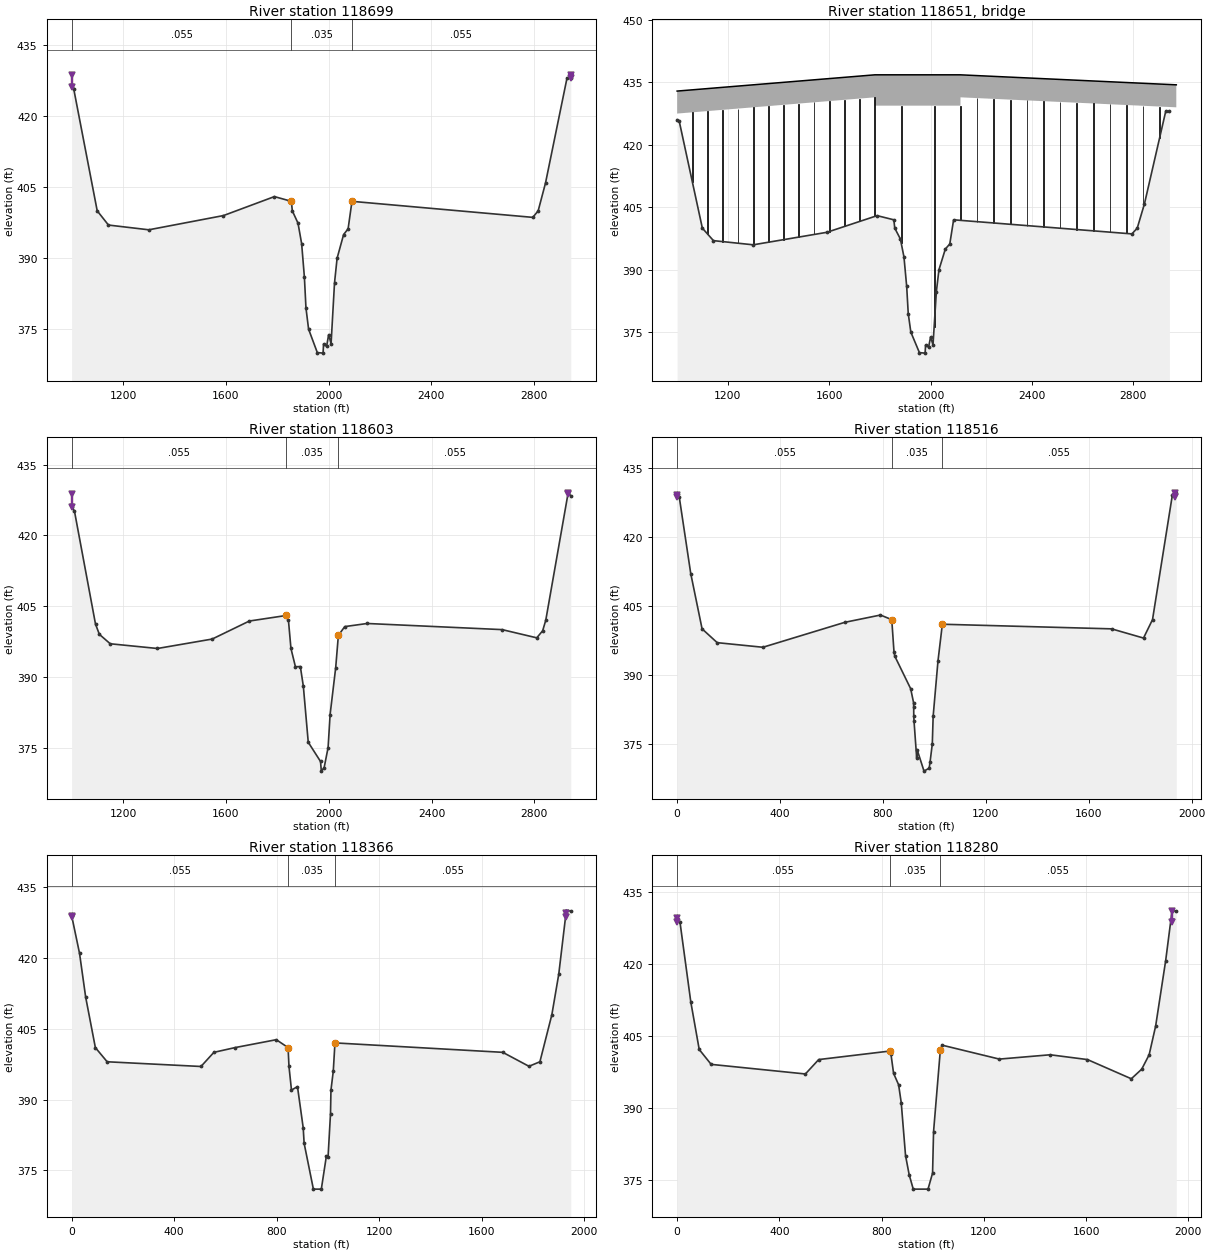
Type RM Length L Ch R = 1 ,118699  ,96,96,96
BEGIN DESCRIPTION:
This cross section corresponds to cross section 118703 of the non-georeferenced CDC model which was the source of this model.
END DESCRIPTION:
XS GIS Cut Line= 3
2486505.268163416967556.82415655 2485541.73728216967316.33808896
2484619.903495856967089.75816154
#Sta/Elev= 30
    1000     426 1008.54   425.6 1099.55     400 1143.31     397 1300.31     396
  1590.9     399 1789.14     403 1855.04     402 1858.71     400 1880.92  397.39
 1895.01  393.08 1905.76     386 1911.86  379.51 1922.09  375.05 1955.96  370.12
  1978.4     370  1980.3  371.91 1992.21  371.44 2000.14   373.9 2009.57     372
 2022.88  384.76 2032.98     390 2058.33     395 2075.81   396.2 2090.86     402
 2794.45  398.62 2815.41     400 2843.94  405.86 2927.65     428 2942.36     428
#Mann= 3 ,0,0
    1000    .055       0 1855.04    .035       0 2090.86    .055       0
Levee=-1,1000,428.67,-1,2942,428.67,,
#XS Ineff= 2 , 0
       0 1855.04     402 2090.86       0     402
Permanent Ineff=
       F       F
Bank Sta=1855.04,2090.86
XS Rating Curve= 0 ,0
Exp/Cntr=0.3,0.1

Type RM Length L Ch R = 3 ,118651  ,,,
BEGIN DESCRIPTION:
118657  IH 30
END DESCRIPTION:
Node Name=IH 30
Bridge Culvert--1,0,-1,-1, 0
Deck Dist Width WeirC Skew NumUp NumDn MinLoCord MaxHiCord MaxSubmerge Is_Ogee
4,88,2.6,0, 6, 6, , , 0.95, 0, ,,,
    1000    1780    1780    2118    2118  2969.5
   432.9   436.8   436.8   436.8   436.8   434.4
   427.5   431.4   429.4   429.4   431.4     429
    1000    1780    1780    2118    2118  2969.5
   432.9   436.8   436.8   436.8   436.8   434.4
   427.5   431.4   429.4   429.4   431.4     429
Pier Skew, UpSta & Num, DnSta & Num=  ,1060, 2 ,1060, 2 , 0 , 0 , 0 ,,
       3       3
     380   431.5
       3       3
     380   431.5
Pier Skew, UpSta & Num, DnSta & Num=  ,1120, 2 ,1120, 2 , 0 , 0 , 0 ,,
       3       3
       0     432
       3       3
       0     432
Pier Skew, UpSta & Num, DnSta & Num=  ,1180, 2 ,1180, 2 , 0 , 0 , 0 ,,
       3       3
       0   431.5
       3       3
       0   431.5
Pier Skew, UpSta & Num, DnSta & Num=  ,1240, 2 ,1240, 2 , 0 , 0 , 0 ,,
       3       3
       0   431.5
       3       3
       0   431.5
Pier Skew, UpSta & Num, DnSta & Num=  ,1300, 2 ,1300, 2 , 0 , 0 , 0 ,,
       3       3
       0   431.5
       3       3
       0   431.5
Pier Skew, UpSta & Num, DnSta & Num=  ,1360, 2 ,1360, 2 , 0 , 0 , 0 ,,
       3       3
       0   431.5
       3       3
       0   431.5
Pier Skew, UpSta & Num, DnSta & Num=  ,1420, 2 ,1420, 2 , 0 , 0 , 0 ,,
       3       3
       0   431.5
       3       3
       0   431.5
Pier Skew, UpSta & Num, DnSta & Num=  ,1480, 2 ,1480, 2 , 0 , 0 , 0 ,,
       3       3
       0   431.5
       3       3
       0   431.5
Pier Skew, UpSta & Num, DnSta & Num=  ,1540, 2 ,1540, 2 , 0 , 0 , 0 ,,
       3       3
       0   431.5
       3       3
       0   431.5
Pier Skew, UpSta & Num, DnSta & Num=  ,1600, 2 ,1600, 2 , 0 , 0 , 0 ,,
       3       3
       0   431.5
       3       3
       0   431.5
Pier Skew, UpSta & Num, DnSta & Num=  ,1660, 2 ,1660, 2 , 0 , 0 , 0 ,,
       3       3
       0   431.5
       3       3
       0   431.5
Pier Skew, UpSta & Num, DnSta & Num=  ,1720, 2 ,1720, 2 , 0 , 0 , 0 ,,
       3       3
       0   431.5
       3       3
       0   431.5
Pier Skew, UpSta & Num, DnSta & Num=  ,1780, 2 ,1780, 2 , 0 , 0 , 0 ,,
       3       3
       0   431.5
       3       3
       0   431.5
Pier Skew, UpSta & Num, DnSta & Num=  ,1884, 2 ,1884, 2 , 0 , 0 , 0 ,,
       4       4
       0   431.5
       4       4
       0   431.5
Pier Skew, UpSta & Num, DnSta & Num=  ,2014, 2 ,2014, 2 , 0 , 0 , 0 ,,
       4       4
       0   431.5
       4       4
       0   431.5
Pier Skew, UpSta & Num, DnSta & Num=  ,2118, 2 ,2118, 2 , 0 , 0 , 0 ,,
       3       3
       0   431.5
       3       3
       0   431.5
Pier Skew, UpSta & Num, DnSta & Num=  ,2183.5, 2 ,2183.5, 2 , 0 , 0 , 0 ,,
       3       3
       0   431.5
       3       3
       0   431.5
Pier Skew, UpSta & Num, DnSta & Num=  ,2249, 2 ,2249, 2 , 0 , 0 , 0 ,,
       3       3
       0   431.5
       3       3
       0   431.5
Pier Skew, UpSta & Num, DnSta & Num=  ,2314.5, 2 ,2314.5, 2 , 0 , 0 , 0 ,,
       3       3
       0   431.5
       3       3
       0   431.5
Pier Skew, UpSta & Num, DnSta & Num=  ,2380, 2 ,2380, 2 , 0 , 0 , 0 ,,
       3       3
       0   431.5
       3       3
       0   431.5
Pier Skew, UpSta & Num, DnSta & Num=  ,2445.5, 2 ,2445.5, 2 , 0 , 0 , 0 ,,
       3       3
       0   431.5
       3       3
       0   431.5
Pier Skew, UpSta & Num, DnSta & Num=  ,2511, 2 ,2511, 2 , 0 , 0 , 0 ,,
       3       3
       0   431.5
       3       3
       0   431.5
Pier Skew, UpSta & Num, DnSta & Num=  ,2576.5, 2 ,2576.5, 2 , 0 , 0 , 0 ,,
       3       3
       0   431.5
       3       3
       0   431.5
Pier Skew, UpSta & Num, DnSta & Num=  ,2642, 2 ,2642, 2 , 0 , 0 , 0 ,,
       3       3
       0   431.5
       3       3
       0   431.5
Pier Skew, UpSta & Num, DnSta & Num=  ,2707.5, 2 ,2707.5, 2 , 0 , 0 , 0 ,,
       3       3
       0   431.5
       3       3
       0   431.5
Pier Skew, UpSta & Num, DnSta & Num=  ,2773, 2 ,2773, 2 , 0 , 0 , 0 ,,
       3       3
       0   431.5
       3       3
       0   431.5
Pier Skew, UpSta & Num, DnSta & Num=  ,2838.5, 2 ,2838.5, 2 , 0 , 0 , 0 ,,
       3       3
       0   431.5
       3       3
       0   431.5
Pier Skew, UpSta & Num, DnSta & Num=  ,2904, 2 ,2904, 2 , 0 , 0 , 0 ,,
       3       3
       0   431.5
       3       3
       0   431.5
BR Coef= 1 , 1 , 1 ,1.05, 0 ,,,0.8,-1,1.2,1,
WSPro=,,,, 1 ,,,, 0 ,,,, 0 ,,,,-1 ,-1 ,-1 , 0 , 0 , 0 , 0 , 0
BC Design=,, 0 ,, 0 ,,,,,,
BC HTab HWMax=431
BC Use User HTab Curves=0
BC User HTab FreeFlow(D)= 0

Type RM Length L Ch R = 1 ,118603  ,87,87,87
BEGIN DESCRIPTION:
This cross section corresponds to cross section 118611 of the non-georeferenced CDC model which was the source of this model.
END DESCRIPTION:
XS GIS Cut Line= 3
2486524.275999436967467.967706962485581.777228276967229.20867005
2484640.08422977 6966999.3538148
#Sta/Elev= 30
    1000     426 1010.89  425.16  1092.9  401.17  1107.9     399 1150.16     397
 1333.92     396 1546.73     398 1691.27  401.82 1835.14     403 1843.32     402
 1853.07  396.01  1870.5  392.13 1889.64  392.17 1901.31     388 1920.37  376.12
  1968.1  372.05 1971.25     370 1982.26  370.76 1997.59     375 2005.39     382
  2027.2  391.96 2037.53  398.79 2062.46  400.64 2149.59   401.3 2674.44     400
 2809.19  398.26 2832.16  399.76 2844.29     402 2931.32     429 2941.61  428.37
#Mann= 3 ,0,0
    1000    .055       0 1835.14    .035       0 2037.53    .055       0
Levee=-1,1000,428.65,-1,2931,428.65,,
#XS Ineff= 2 , 0
       0 1835.14     403 2037.53       0  398.79
Permanent Ineff=
       F       F
Bank Sta=1835.14,2037.53
XS Rating Curve= 0 ,0
Exp/Cntr=0.3,0.1

Type RM Length L Ch R = 1 ,118516  ,136,150,196
BEGIN DESCRIPTION:
This cross section corresponds to cross section 118533 of the non-georeferenced CDC model which was the source of this model.
END DESCRIPTION:
XS GIS Cut Line= 2
2486542.889479256967380.72378697 2484660.11076456966912.27656113
#Sta/Elev= 30
       0     429    8.37  428.61   52.96     412   96.99     400  155.78     397
  333.45     396  651.98  401.42  790.28     403  834.24     402  842.91     395
  845.99  394.07  907.74     387  918.92     384  919.54   383.1  919.74     381
  920.74     380  931.08     372  932.79  373.77  959.61   369.1  979.62  369.75
  982.94     371  991.83     375  995.11     381 1013.87     393 1030.88     401
 1688.51     400 1812.74     398 1847.73     402  1924.7     429 1940.18  429.54
#Mann= 3 ,0,0
       0    .055       0  834.24    .035       0 1030.88    .055       0
Levee=-1,0,428.63,-1,1936,428.63,,
#XS Ineff= 2 , 0
       0  834.24     402 1030.88       0     401
Permanent Ineff=
       F       F
Bank Sta=834.24,1030.88
XS Rating Curve= 0 ,0
Exp/Cntr=0.3,0.1

Type RM Length L Ch R = 1 ,118366  ,64,86,116
BEGIN DESCRIPTION:
This cross section corresponds to cross section 118381 of the non-georeferenced CDC model which was the source of this model.
END DESCRIPTION:
XS GIS Cut Line= 2
2486580.577067916967318.21406947 2484735.38259566966695.15297963
#Sta/Elev= 30
       0     429   30.83     421   54.73  411.72   92.64     401  138.64     398
  504.62     397  555.07     400  637.14     401  798.45  402.68  844.47  401.01
  848.04     397  857.72     392  881.19  392.73  903.53     384  907.09  380.73
  943.24     371  974.22     371  993.91     378 1000.45  377.77 1010.02  386.98
  1011.8     392 1020.85     396 1027.41     402  1682.2     400 1784.33  397.04
 1827.01     398 1873.69  407.99 1900.52  416.55 1929.91     430 1947.55     430
#Mann= 3 ,0,0
       0    .055       0  844.47    .035       0 1027.41    .055       0
Levee=-1,0,428.6,-1,1929,428.6,,
#XS Ineff= 2 , 0
       0  844.47  401.01 1027.41       0     402
Permanent Ineff=
       F       F
Bank Sta=844.47,1027.41
XS Rating Curve= 0 ,0
Exp/Cntr=0.3,0.1

Type RM Length L Ch R = 1 ,118280  ,167,217,255
BEGIN DESCRIPTION:
This cross section corresponds to cross section 118283 of the non-georeferenced CDC model which was the source of this model.
END DESCRIPTION:
XS GIS Cut Line= 2
2486604.002546016967289.436567962484790.028811756966566.40750222
#Sta/Elev= 30
       0  429.52   11.08  428.69   53.53     412   86.46   402.1  133.16     399
  501.81     397  553.82     400  831.22  401.77  836.32  401.21  846.82  397.13
  866.44  394.75  876.75     391  893.55     380   907.8     376  923.74     373
  981.52     373   999.3  376.34 1003.21     385 1029.59  401.91 1036.86     403
 1260.55   400.1 1459.32     401 1605.26     400 1776.79     396 1817.49     398
 1846.55     401    1872     407 1911.08  420.58 1936.22     431 1952.76     431
#Mann= 3 ,0,0
       0    .055       0  831.22    .035       0 1029.59    .055       0
Levee=-1,0,428.58,-1,1936,428.58,,
#XS Ineff= 2 , 0
       0  831.22  401.77 1029.59       0  401.91
Permanent Ineff=
       F       F
Bank Sta=831.22,1029.59
XS Rating Curve= 0 ,0
Exp/Cntr=0.3,0.1