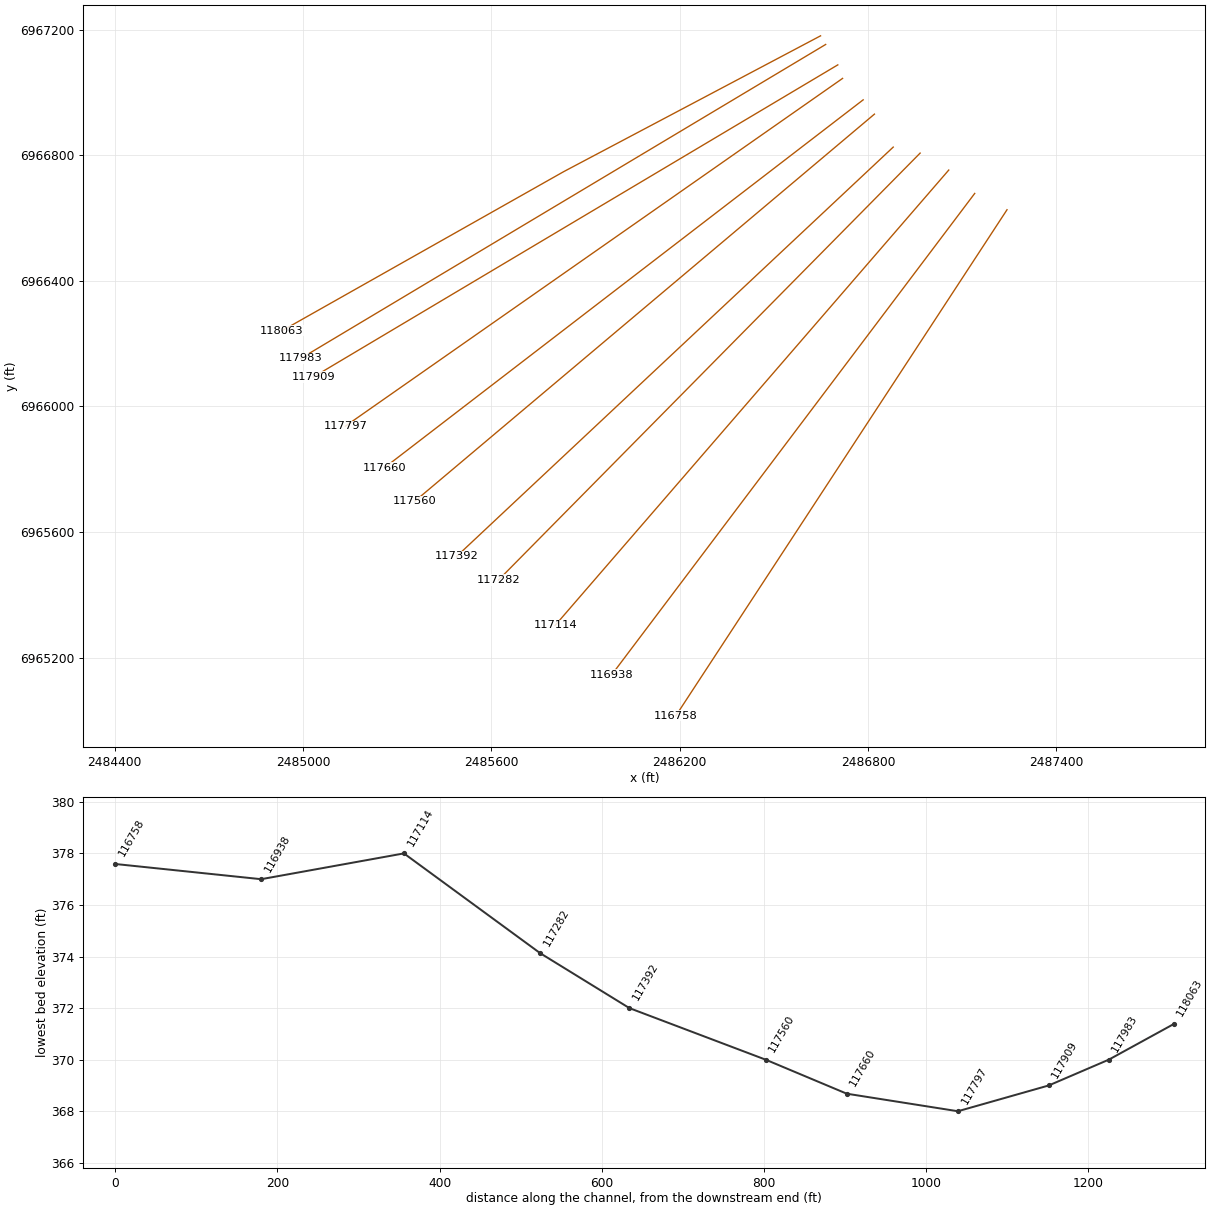
HEC-RAS study CDC_Consolidated_Model.prj: Upper Trinity CDC Consolidated Model

--- CDC_Consolidated_Model.g04 (geometry) --- (continued)

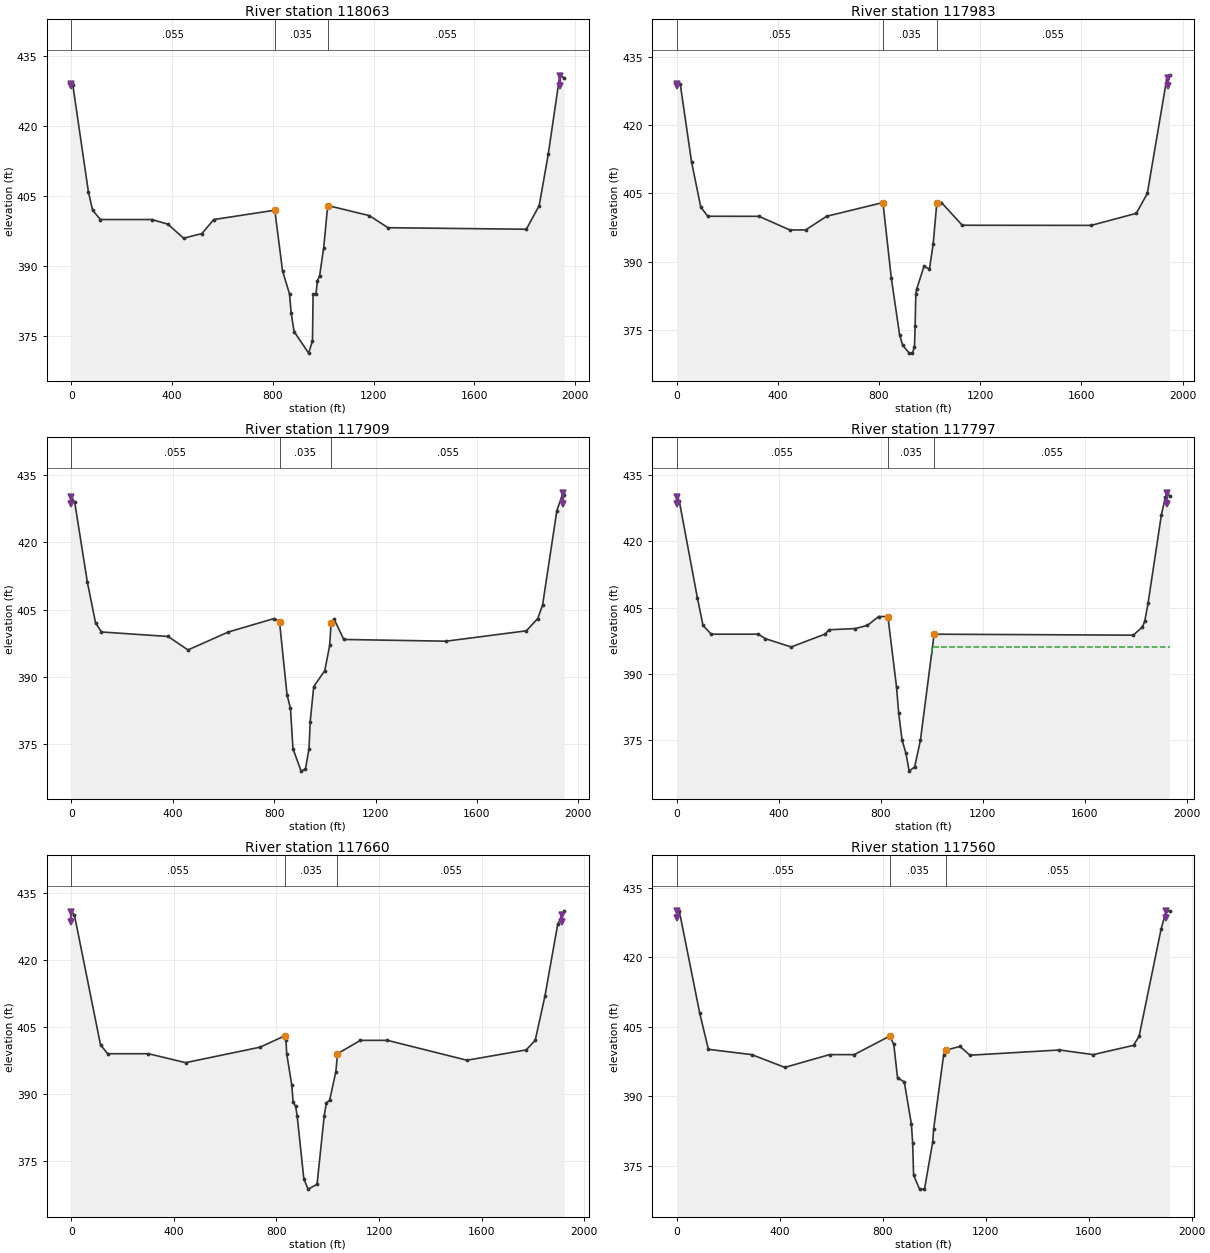
Type RM Length L Ch R = 1 ,118063  ,56,80,99
BEGIN DESCRIPTION:
This cross section corresponds to cross section 118075 of the non-georeferenced CDC model which was the source of this model.
END DESCRIPTION:
XS GIS Cut Line= 3
2486648.866629516967180.767165882485830.942740416966748.30083922
2484932.639746996966240.97376989
#Sta/Elev= 30
       0     429    6.11   428.8   67.63     406   84.43     402  115.66     400
  319.64     400  383.65     399  445.79     396  518.56     397  565.67     400
  807.94     402  838.63     389  866.28  384.06  872.83     380  884.43     376
  942.28  371.38  957.48     374  959.88     384  971.04     384  977.19  386.89
  985.95     388 1002.06     394 1017.97     403 1182.54  400.85 1257.47  398.25
 1806.53  397.92 1857.58     403 1893.57     414 1939.64     431 1956.88  430.29
#Mann= 3 ,0,0
       0    .055       0  807.94    .035       0 1017.97    .055       0
Levee=-1,0,428.53,-1,1939,428.53,,
#XS Ineff= 2 , 0
       0  807.94     402 1017.97       0     403
Permanent Ineff=
       F       F
Bank Sta=807.94,1017.97
XS Rating Curve= 0 ,0
Exp/Cntr=0.3,0.1

Type RM Length L Ch R = 1 ,117983  ,62,74,83
BEGIN DESCRIPTION:
This cross section corresponds to cross section 118000 of the non-georeferenced CDC model which was the source of this model.
END DESCRIPTION:
XS GIS Cut Line= 2
2486665.166465676967153.278047642484992.99658167 6966152.9893658
#Sta/Elev= 30
       0     429    14.4     429   58.92     412   95.61     402  123.35     400
  325.76  399.99  447.34     397  509.99     397  593.24     400  815.63     403
  849.05  386.36  881.68     374   893.5  371.74  919.47     370  932.09     370
   940.4  371.36  942.94     376  945.71     383  948.89     384  977.83     389
  999.74  388.46 1014.39     394 1028.83     403 1047.19     403 1129.27  398.03
 1638.91     398  1817.2  400.64 1860.83     405 1937.31     430 1948.52     431
#Mann= 3 ,0,0
       0    .055       0  815.63    .035       0 1028.83    .055       0
Levee=-1,0,428.51,-1,1941,428.51,,
#XS Ineff= 2 , 0
       0  815.63     403 1028.83       0     403
Permanent Ineff=
       F       F
Bank Sta=815.63,1028.83
XS Rating Curve= 0 ,0
Exp/Cntr=0.3,0.1

Type RM Length L Ch R = 1 ,117909  ,81,112,129
BEGIN DESCRIPTION:
This cross section corresponds to cross section 117920 of the non-georeferenced CDC model which was the source of this model.
END DESCRIPTION:
XS GIS Cut Line= 2
2486703.848474926967088.27784956 2485033.33278716966093.95962821
#Sta/Elev= 30
       0     430   13.18     429   63.01   411.2   95.76     402  119.05     400
  381.52     399  460.04     396  619.57     400  800.31     403  821.16  402.29
  850.84     386  864.33     383  874.18     374  906.37     369  923.59   369.5
  937.48     374  942.07     380  956.17  387.85  999.58  391.38 1018.98     397
 1024.64     402 1036.52  402.87 1074.48  398.33 1478.29  397.95 1794.64  400.26
 1839.73     403 1858.65     406 1914.93     427 1939.03     431 1944.04  430.43
#Mann= 3 ,0,0
       0    .055       0  821.16    .035       0 1024.64    .055       0
Levee=-1,0,428.5,-1,1939,428.5,,
#XS Ineff= 2 , 0
       0  821.16  402.29 1024.64       0     402
Permanent Ineff=
       F       F
Bank Sta=821.16,1024.64
XS Rating Curve= 0 ,0
Exp/Cntr=0.3,0.1

Type RM Length L Ch R = 1 ,117797  ,106,137,156
BEGIN DESCRIPTION:
This cross section corresponds to cross section 117801 of the non-georeferenced CDC model which was the source of this model.
END DESCRIPTION:
XS GIS Cut Line= 2
2486719.061042936967045.14834264  2485134.8991856965937.22240888
#Sta/Elev= 30
       0     430    10.8  429.08   81.49  407.23  103.56     401  135.78     399
   320.4     399  347.51     398   449.3  396.11  581.44     399  598.43     400
  700.42  400.27  748.71     401  792.56     403  828.71     403  862.66     387
  871.18  381.09  884.23  375.03  899.67     372  912.09     368  933.63  368.95
  956.31     375    1010     399 1791.01  398.78 1827.19  400.64 1836.24     402
 1849.02  405.99 1901.31     426 1916.82     430 1924.13     431 1933.15  430.25
#Mann= 3 ,0,0
       0    .055       0  828.71    .035       0    1010    .055       0
Levee=-1,0,428.47,-1,1924,428.47,,
#XS Ineff= 2 , 0
       0  828.71     403  999.76       0     396
Permanent Ineff=
       F       F
Bank Sta=828.71,1010
XS Rating Curve= 0 ,0
Exp/Cntr=0.3,0.1

Type RM Length L Ch R = 1 ,117660  ,78,100,114
BEGIN DESCRIPTION:
This cross section corresponds to cross section 117672 of the non-georeferenced CDC model which was the source of this model.
END DESCRIPTION:
XS GIS Cut Line= 2
2486784.62423199 6966976.85582832485260.233579996965805.33159655
#Sta/Elev= 30
       0   430.8   12.31     430  113.85     401  141.97     399  301.06     399
  445.86     397  735.73  400.46  832.15     403  837.38     402  840.15     399
  859.79     392  865.19  388.18  874.89  387.23  881.11     385  906.92     371
   923.6  368.68  958.44  369.75  986.48  385.09  994.87     388 1007.67  388.61
 1031.91     395  1038.2     399 1127.77     402 1232.82     402 1543.02  397.54
 1774.19  399.86 1809.44     402 1847.64     412 1897.22     428 1922.56     431
#Mann= 3 ,0,0
       0    .055       0  832.15    .035       0  1038.2    .055       0
Levee=-1,0,428.44,-1,1915,428.44,,
#XS Ineff= 2 , 0
       0  832.15     403  1038.2       0     399
Permanent Ineff=
       F       F
Bank Sta=832.15,1038.2
XS Rating Curve= 0 ,0
Exp/Cntr=0.3,0.1

Type RM Length L Ch R = 1 ,117560  ,130,168,191
BEGIN DESCRIPTION:
This cross section corresponds to cross section 117572 of the non-georeferenced CDC model which was the source of this model.
END DESCRIPTION:
XS GIS Cut Line= 2
2486820.520157586966931.338858962485356.777350166965698.54473664
#Sta/Elev= 30
       0     430   10.35     430   89.56     408  123.46  400.14  291.66     399
  420.13  396.25     594     399  689.64     399  827.74     403  843.31  401.19
  857.85     394  883.97  393.12  911.68     384  916.47     380   920.2     373
  943.46     370  962.46     370  994.35  380.13  998.07     383 1036.95     399
 1047.23     400 1100.45  400.76 1138.83  398.87  1486.4     400 1617.53     399
 1774.21     401 1795.83     403  1880.9     426 1900.49     430 1913.72     430
#Mann= 3 ,0,0
       0    .055       0  827.74    .035       0 1047.23    .055       0
Levee=-1,0,428.42,-1,1900,428.42,,
#XS Ineff= 2 , 0
       0  827.74     403 1047.23       0     400
Permanent Ineff=
       F       F
Bank Sta=827.74,1047.23
XS Rating Curve= 0 ,0
Exp/Cntr=0.3,0.1

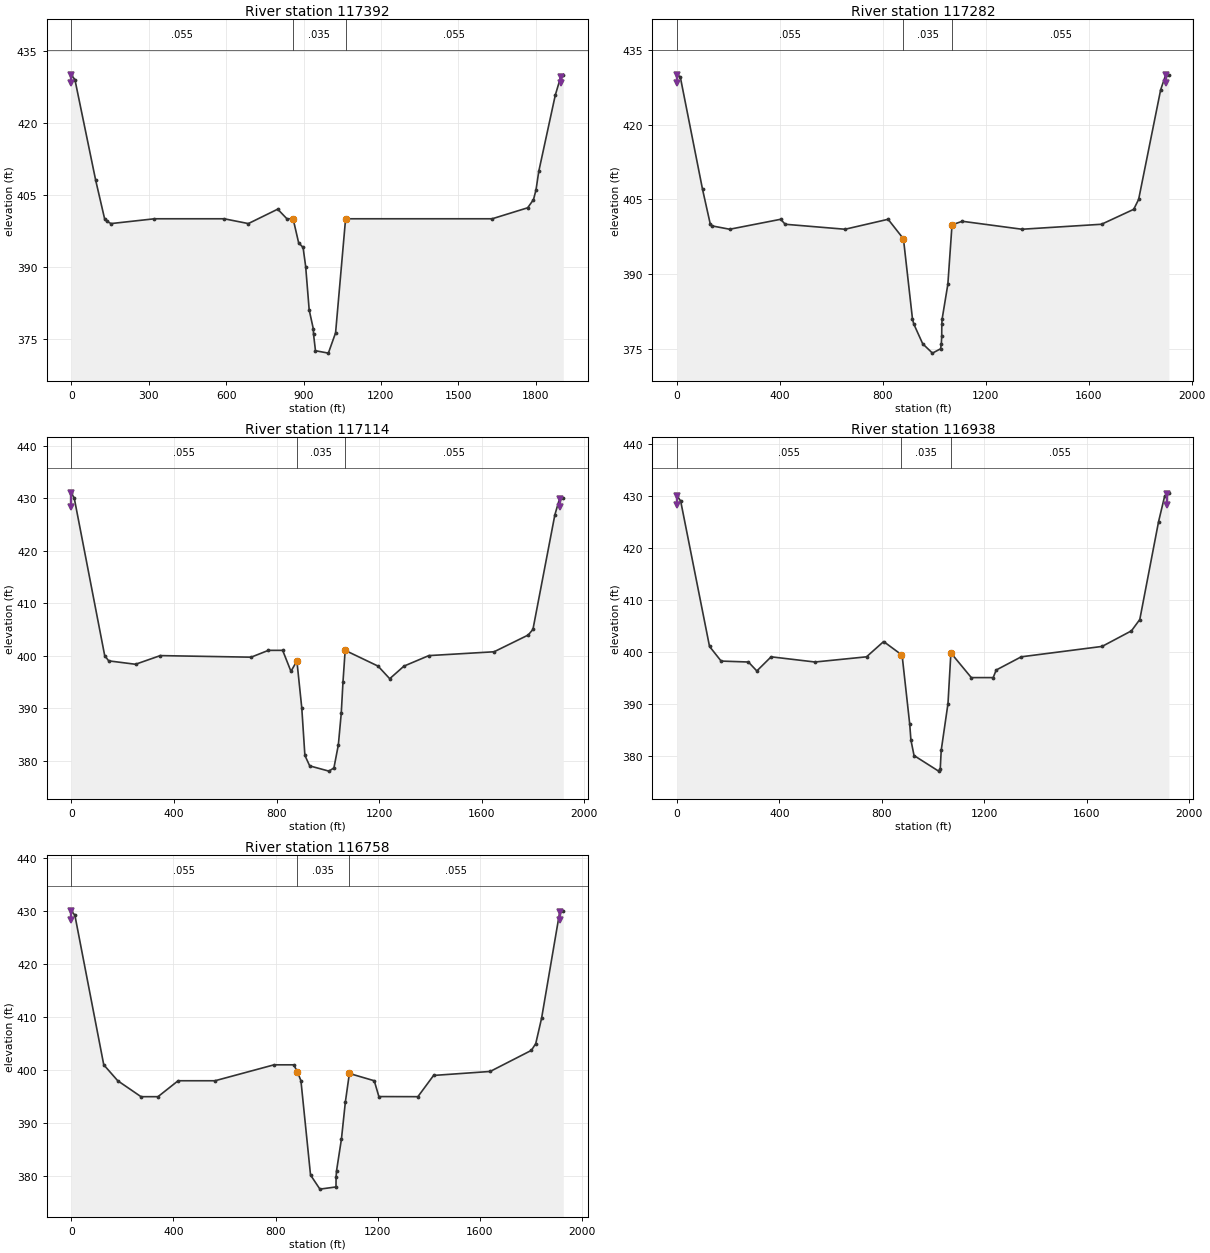
Type RM Length L Ch R = 1 ,117392  ,84,110,122
BEGIN DESCRIPTION:
This cross section corresponds to cross section 117403 of the non-georeferenced CDC model which was the source of this model.
END DESCRIPTION:
XS GIS Cut Line= 2
2486880.365510346966826.290840722485489.452609756965522.35250372
#Sta/Elev= 30
       0     430   14.15     429   94.72     408   129.2     400  138.21  399.46
  154.21     399  322.52     400  592.44     400  686.19     399  799.93     402
  835.68     400  859.57     400  881.04     395  898.27  394.02   908.3  390.05
  921.93     381  938.19     377  938.65     376  946.28   372.5  996.23     372
 1024.22  376.23    1063     400    1631     400  1768.6  402.29 1791.13     404
 1800.81     406 1811.52  409.87 1875.59  425.77 1897.69  429.75 1906.54     430
#Mann= 3 ,0,0
       0    .055       0  859.57    .035       0    1063    .055       0
Levee=-1,0,428.38,-1,1897,428.38,,
#XS Ineff= 2 , 0
       0  859.57     400    1063       0     400
Permanent Ineff=
       F       F
Bank Sta=859.57,1063
XS Rating Curve= 0 ,0
Exp/Cntr=0.3,0.1

Type RM Length L Ch R = 1 ,117282  ,139,168,199
BEGIN DESCRIPTION:
This cross section corresponds to cross section 117294 of the non-georeferenced CDC model which was the source of this model.
END DESCRIPTION:
XS GIS Cut Line= 2
2486966.092701086966807.221981212485623.040597176965447.35396604
#Sta/Elev= 30
       0     430   13.25  429.58   99.72     407   129.9     400  135.79  399.68
  205.17     399  403.32     401  420.75     400  653.33     399  820.57     401
  880.13  397.08  915.21     381  920.07     380  955.02     376  992.88  374.13
 1024.39     375 1027.34     376 1028.78  377.48 1029.19     380 1030.49     381
 1052.61  387.94 1068.83  399.88 1108.52   400.6 1340.49     399 1649.51     400
 1774.67     403  1793.8     405 1879.34     427 1898.94     430 1911.29     430
#Mann= 3 ,0,0
       0    .055       0  880.13    .035       0 1068.83    .055       0
Levee=-1,0,428.36,-1,1899,428.36,,
#XS Ineff= 2 , 0
       0  880.13  397.08 1068.83       0  399.88
Permanent Ineff=
       F       F
Bank Sta=880.13,1068.83
XS Rating Curve= 0 ,0
Exp/Cntr=0.3,0.1

Type RM Length L Ch R = 1 ,117114  ,146,176,209
BEGIN DESCRIPTION:
This cross section corresponds to cross section 117118 of the non-georeferenced CDC model which was the source of this model.
END DESCRIPTION:
XS GIS Cut Line= 2
2487057.26968408 6966753.1751733 2485803.18164116965302.39625071
#Sta/Elev= 30
       0     431   11.58     430   130.3     400  145.91     399  250.45  398.35
  346.85     400  700.98   399.7  768.33     401  823.95     401  856.26     397
  879.43  398.98   898.5     390  910.57     381   929.3     379 1004.15     378
 1023.73  378.61 1040.98     383 1052.28     389 1059.09  395.01 1067.52     401
 1195.76     398  1241.2   395.6  1296.8     398 1393.62     400 1647.98  400.73
 1780.94  403.92 1799.47     405 1884.78  426.79 1903.82     430 1917.68     430
#Mann= 3 ,0,0
       0    .055       0  879.43    .035       0 1067.52    .055       0
Levee=-1,0,428.32,-1,1903,428.32,,
#XS Ineff= 2 , 0
       0  879.43  398.98 1067.52       0     401
Permanent Ineff=
       F       F
Bank Sta=879.43,1067.52
XS Rating Curve= 0 ,0
Exp/Cntr=0.3,0.1

Type RM Length L Ch R = 1 ,116938  ,152,180,218
BEGIN DESCRIPTION:
This cross section corresponds to cross section 116942 of the non-georeferenced CDC model which was the source of this model.
END DESCRIPTION:
XS GIS Cut Line= 2
2487139.975883516966678.745204052485983.411595586965145.08915064
#Sta/Elev= 30
       0     430   14.73     429  127.45     401  172.76  398.18  279.26     398
  312.16  396.28   367.9     399  539.24     398  740.38     399  807.25  401.94
  876.71  399.41  879.98     399  909.13     386  913.66     383  925.93     380
 1021.78     377 1028.32  377.49 1031.99     381 1058.43     390 1069.75  399.75
 1149.51     395 1234.88     395 1246.73  396.46 1344.52     399 1660.03     401
  1774.7     404 1807.27  406.18 1880.51     425  1904.7     430 1920.87  430.56
#Mann= 3 ,0,0
       0    .055       0  876.71    .035       0 1069.75    .055       0
Levee=-1,0,428.28,-1,1912,428.28,,
#XS Ineff= 2 , 0
       0  876.71  399.41 1069.75       0  399.75
Permanent Ineff=
       F       F
Bank Sta=876.71,1069.75
XS Rating Curve= 0 ,0
Exp/Cntr=0.3,0.1

Type RM Length L Ch R = 1 ,116758  ,142,147,146
BEGIN DESCRIPTION:
This cross section corresponds to cross section 116766 of the non-georeferenced CDC model which was the source of this model.
END DESCRIPTION:
XS GIS Cut Line= 2
2487242.895625176966626.792880132486187.660530926965014.40076372
#Sta/Elev= 30
       0     430    14.1  429.18  127.27     401  182.05     398  273.18     395
  339.66     395  418.54     398  562.95     398  794.19     401  871.27     401
  885.84  399.68  899.52     398   937.1  380.25  973.81  377.59 1036.81     378
 1037.15  379.83 1038.84     381  1058.1     387  1073.5     394 1089.25  399.37
 1186.65     398 1204.78  395.02 1357.58     395    1419     399 1640.63  399.75
 1801.98  403.72 1819.21     405 1842.06  409.78 1913.63  429.94    1927     430
#Mann= 3 ,0,0
       0    .055       0  885.84    .035       0 1089.25    .055       0
Levee=-1,0,428.24,-1,1913,428.24,,
#XS Ineff= 2 , 0
       0  885.84  399.68 1089.25       0  399.37
Permanent Ineff=
       F       F
Bank Sta=885.84,1089.25
XS Rating Curve= 0 ,0
Exp/Cntr=0.3,0.1