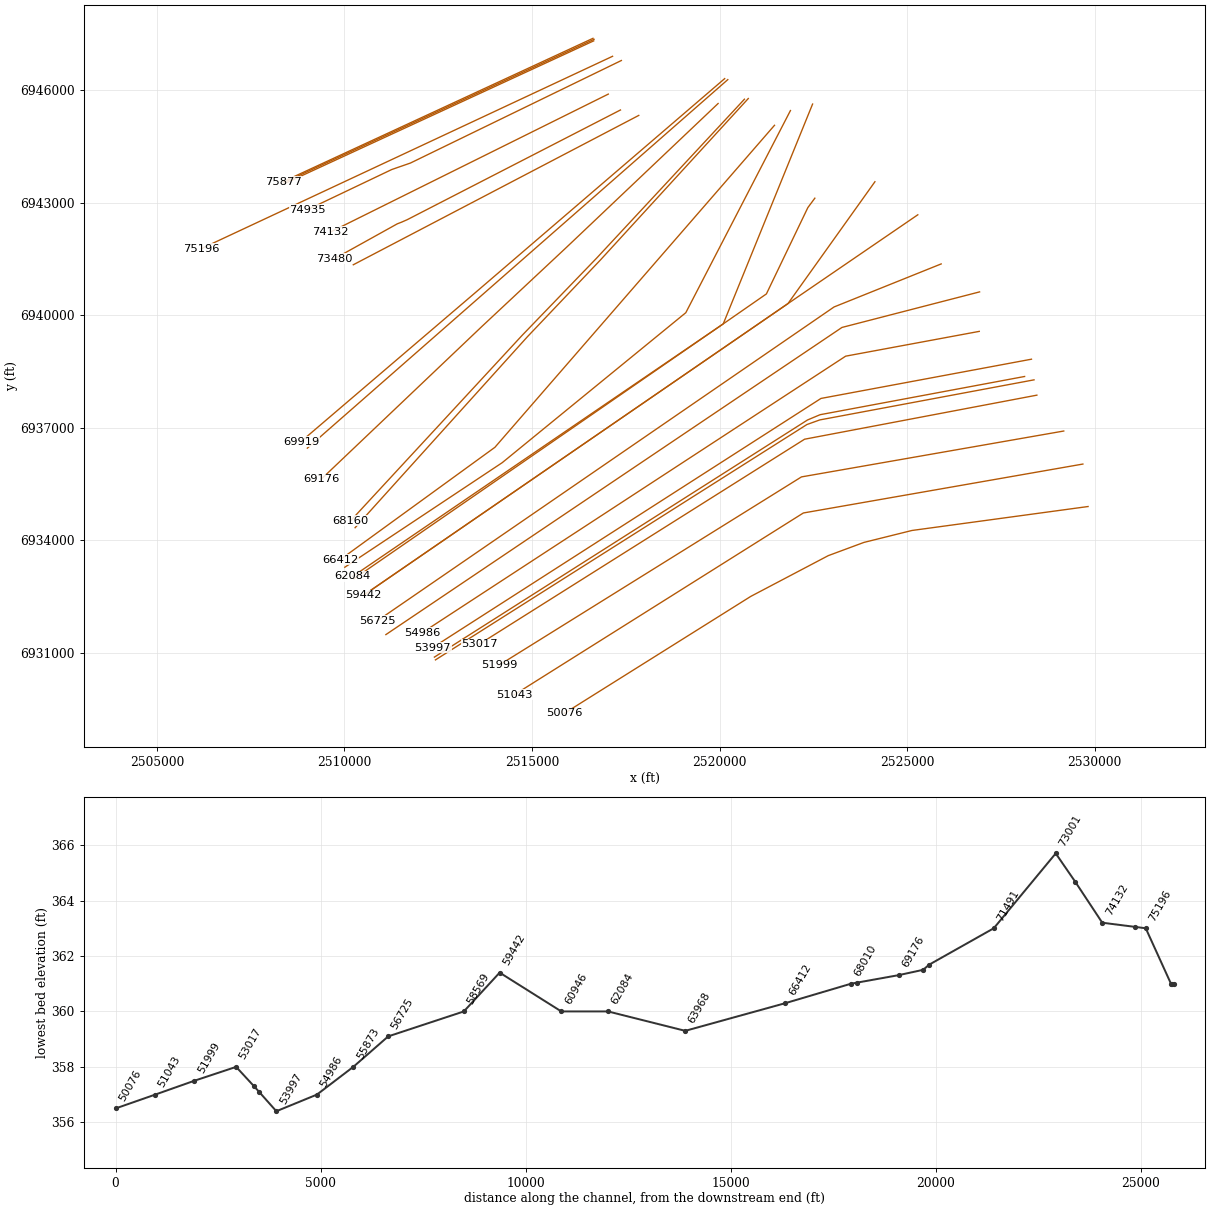
HEC-RAS study CDC_Consolidated_Model.prj: Upper Trinity CDC Consolidated Model

--- CDC_Consolidated_Model.g04 (geometry) --- (continued)

Type RM Length L Ch R = 3 ,75918   ,,,
BEGIN DESCRIPTION:
75926  SH 12
END DESCRIPTION:
Node Name=SH 12
Bridge Culvert--1,0,-1,-1, 0
Deck Dist Width WeirC Skew NumUp NumDn MinLoCord MaxHiCord MaxSubmerge Is_Ogee
1,80,2.6,0, 35, 35, , , 0.95, 0, ,,,
  3793.4    3864    3936  4006.6  4006.6    4025    4025    5174    5174  5192.4
  5192.4    5308    5542    5776    5893  6008.6  6008.6    6027    6027    6450
    6450  6468.4  6468.4    6565    6663    6763    6850    6850    7025    7200
    7200    7405    7592    7707  7820.6
   410.6   410.7   410.9   411.1   411.1   411.1   409.8   412.7     414     414
     414   414.3   414.9   415.4   415.7     416     416     416   414.6   416.2
   417.5   417.5   417.5   417.7   417.7   417.7   417.6   417.6   417.2   416.6
   416.6   415.5   414.2   413.2   412.1
   403.8   403.9   404.1   404.3   411.1   411.1   409.8   412.7     414     414
     406   406.3   406.9   407.4   407.7     408     416     416   414.6   416.2
   417.5   417.5   409.5   409.7   409.7   409.7   409.6   407.5   407.1   406.5
   408.6   407.5   406.2   405.2   404.1
  3793.4    3864    3936  4006.6  4006.6    4025    4025    5174    5174  5192.4
  5192.4    5308    5542    5776    5893  6008.6  6008.6    6027    6027    6450
    6450  6468.4  6468.4    6565    6663    6763    6850    6850    7025    7200
    7200    7405    7592    7707  7820.6
   410.6   410.7   410.9   411.1   411.1   411.1   409.8   412.7     414     414
     414   414.3   414.9   415.4   415.7     416     416     416   414.6   416.2
   417.5   417.5   417.5   417.7   417.7   417.7   417.6   417.6   417.2   416.6
   416.6   415.5   414.2   413.2   412.1
   403.8   403.9   404.1   404.3   411.1   411.1   409.8   412.7     414     414
     406   406.3   406.9   407.4   407.7     408     416     416   414.6   416.2
   417.5   417.5   409.5   409.7   409.7   409.7   409.6   407.5   407.1   406.5
   408.6   407.5   406.2   405.2   404.1
Pier Skew, UpSta & Num, DnSta & Num=  ,3864, 2 ,3864, 2 , 0 , 0 , 0 ,,
       3       3
       0     410
       3       3
       0     410
Pier Skew, UpSta & Num, DnSta & Num=  ,3936, 2 ,3936, 2 , 0 , 0 , 0 ,,
       3       3
       0     410
       3       3
       0     410
Pier Skew, UpSta & Num, DnSta & Num=  ,5308, 2 ,5308, 2 , 0 , 0 , 0 ,,
       3       3
       0     413
       3       3
       0     413
Pier Skew, UpSta & Num, DnSta & Num=  ,5425, 2 ,5425, 2 , 0 , 0 , 0 ,,
       3       3
       0     413
       3       3
       0     413
Pier Skew, UpSta & Num, DnSta & Num=  ,5542, 2 ,5542, 2 , 0 , 0 , 0 ,,
       3       3
       0     413
       3       3
       0     413
Pier Skew, UpSta & Num, DnSta & Num=  ,5659, 2 ,5659, 2 , 0 , 0 , 0 ,,
       3       3
       0     413
       3       3
       0     413
Pier Skew, UpSta & Num, DnSta & Num=  ,5776, 2 ,5776, 2 , 0 , 0 , 0 ,,
       3       3
       0     413
       3       3
       0     413
Pier Skew, UpSta & Num, DnSta & Num=  ,5893, 2 ,5893, 2 , 0 , 0 , 0 ,,
       3       3
       0     413
       3       3
       0     413
Pier Skew, UpSta & Num, DnSta & Num=  ,6565, 2 ,6565, 2 , 0 , 0 , 0 ,,
       3       3
       0     415
       3       3
       0     415
Pier Skew, UpSta & Num, DnSta & Num=  ,6663, 2 ,6663, 2 , 0 , 0 , 0 ,,
       3       3
       0     415
       3       3
       0     415
Pier Skew, UpSta & Num, DnSta & Num=  ,6763, 2 ,6763, 2 , 0 , 0 , 0 ,,
       3       3
       0     415
       3       3
       0     415
Pier Skew, UpSta & Num, DnSta & Num=  ,6850, 2 ,6850, 2 , 0 , 0 , 0 ,,
       3       3
       0     415
       3       3
       0     415
Pier Skew, UpSta & Num, DnSta & Num=  ,7025, 2 ,7025, 2 , 0 , 0 , 0 ,,
       4       4
       0     415
       4       4
       0     415
Pier Skew, UpSta & Num, DnSta & Num=  ,7200, 2 ,7200, 2 , 0 , 0 , 0 ,,
       3       3
       0     415
       3       3
       0     415
Pier Skew, UpSta & Num, DnSta & Num=  ,7305, 2 ,7305, 2 , 0 , 0 , 0 ,,
       3       3
       0     413
       3       3
       0     413
Pier Skew, UpSta & Num, DnSta & Num=  ,7405, 2 ,7405, 2 , 0 , 0 , 0 ,,
       3       3
       0     413
       3       3
       0     413
Pier Skew, UpSta & Num, DnSta & Num=  ,7505, 2 ,7505, 2 , 0 , 0 , 0 ,,
       3       3
       0     413
       3       3
       0     413
Pier Skew, UpSta & Num, DnSta & Num=  ,7592, 2 ,7592, 2 , 0 , 0 , 0 ,,
       3       3
       0     413
       3       3
       0     413
Pier Skew, UpSta & Num, DnSta & Num=  ,7707, 2 ,7707, 2 , 0 , 0 , 0 ,,
       3       3
       0     410
       3       3
       0     410
BR Coef= 1 , 0 , 0 ,1.05, 0 ,,,0.8,0,0.5,1,
WSPro=,,,, 1 ,,,, 0 ,,,, 0 ,,,,-1 ,-1 ,-1 , 0 , 0 , 0 , 0 , 0
BC Design=,, 0 ,, 0 ,,,,,,
BC HTab HWMax=419.8
BC Use User HTab Curves=0
BC User HTab FreeFlow(D)= 0

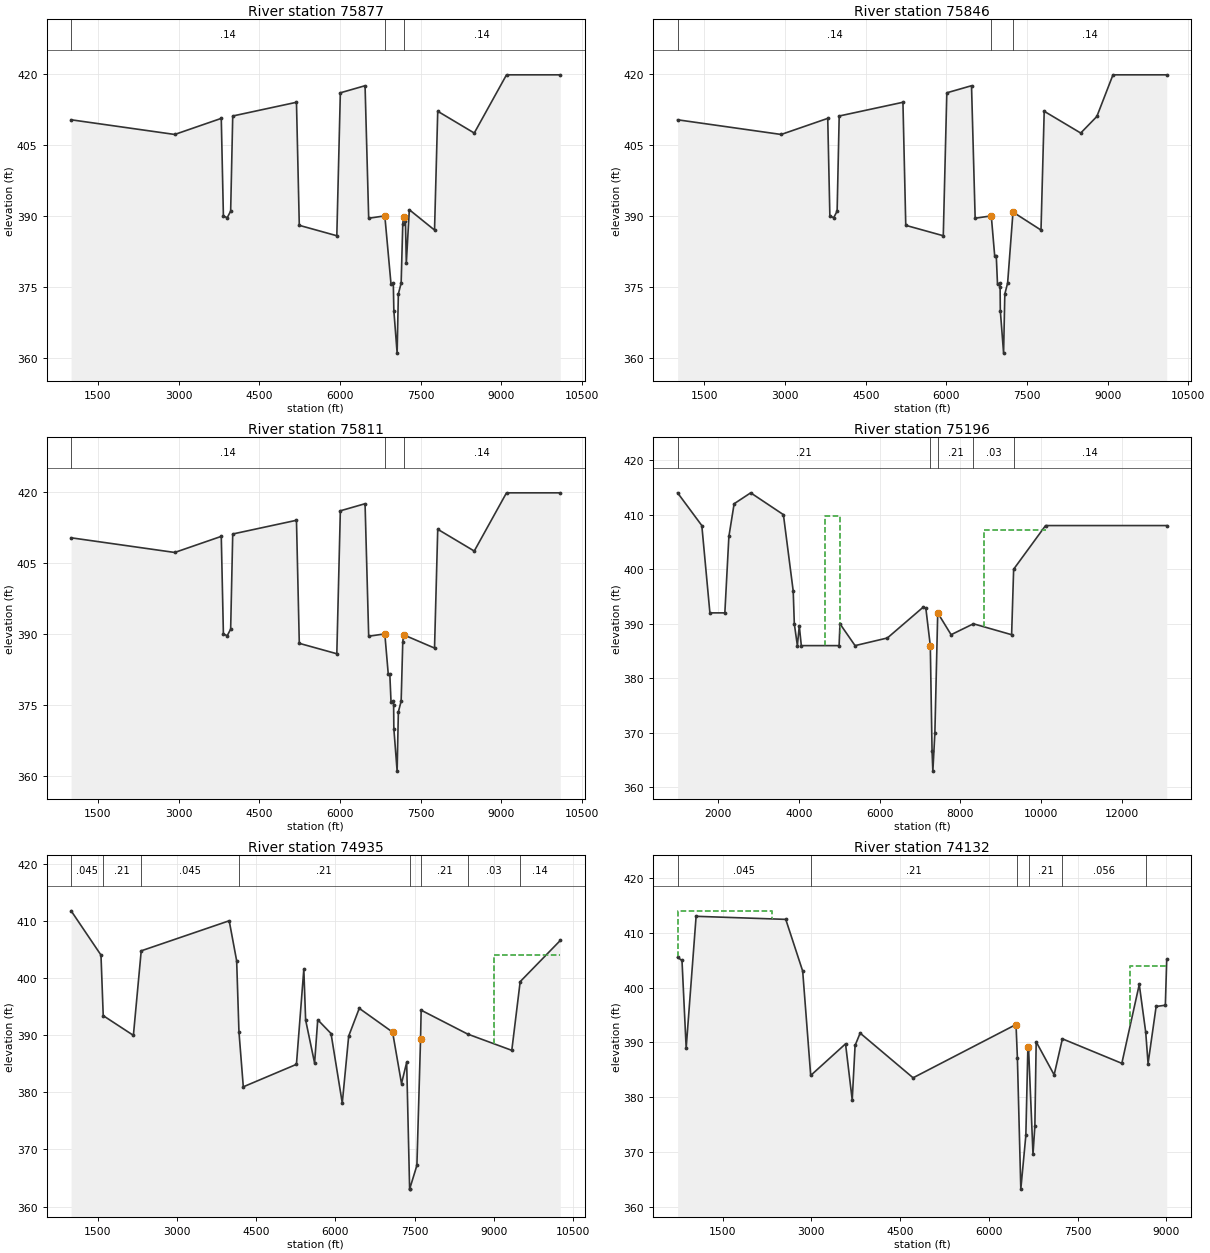
Type RM Length L Ch R = 1 ,75877   ,31,31,31
BEGIN DESCRIPTION:
This cross section corresponds to cross section 75882 of the non-georeferenced CDC model which was the source of this model.
END DESCRIPTION:
XS GIS Cut Line= 3
2516625.817502266947387.06495547  2509274.1816156943986.55764888
2508366.572247326943566.74193253
#Sta/Elev= 30
    1000   410.3    2927   407.2  3793.4   410.6    3833     390    3903   389.6
    3968     391  4006.6   411.1  5192.4     414    5245     388    5943   385.8
  6008.6     416  6468.4   417.5    6536   389.5    6836     390    6952   375.5
    6994   375.8    7004     370    7065     361    7088   373.5    7140   375.8
    7170   388.3    7186   389.8    7220     389    7236     380    7292   391.3
    7761     387  7820.6   412.1    8500   407.5    9100   419.8   10100   419.8
#Mann= 3 ,0,0
    1000     .14       0    6836    .055       0    7186     .14       0
Bank Sta=6836,7186
XS Rating Curve= 0 ,0
Exp/Cntr=0.3,0.1

Type RM Length L Ch R = 1 ,75846   ,35,35,35
BEGIN DESCRIPTION:
This cross section corresponds to cross section 75847 of the non-georeferenced CDC model which was the source of this model.
-----------------------------------------------------------------------
CDC DAL121500-1, Trinity River Boat Ramps at Sylvan Avenue and Loop 12.
-----------------------------------------------------------------------
Cross-section added.
END DESCRIPTION:
XS GIS Cut Line= 3
2516654.809242166947360.645388892509300.080185266943966.83360697
2508392.088929226943547.84449142
#Sta/Elev= 30
    1000   410.3    2927   407.2  3793.4   410.6    3833     390    3903   389.6
    3968     391  4006.6   411.1  5192.4     414    5245     388    5943   385.8
  6008.6     416  6468.4   417.5    6536   389.5    6836     390    6900   381.5
    6929   381.5    6952   375.5    6994   375.8    7000     375    7004     370
    7065     361    7088   373.5    7140   375.8    7240   390.8    7761     387
  7820.6   412.1    8500   407.5    8800     411    9100   419.8   10100   419.8
#Mann= 3 ,0,0
    1000     .14       0    6836    .055       0    7240     .14       0
Bank Sta=6836,7240
XS Rating Curve= 0 ,0
Exp/Cntr=0.3,0.1

Type RM Length L Ch R = 1 ,75811   ,615,615,615
BEGIN DESCRIPTION:
This cross section corresponds to cross section 75812 of the non-georeferenced CDC model which was the source of this model.
-----------------------------------------------------------------------
CDC DAL121500-1, Trinity River Boat Ramps at Sylvan Avenue and Loop 12.
-----------------------------------------------------------------------
Cross-section added.
END DESCRIPTION:
XS GIS Cut Line= 3
  2516645.241676 6947319.84789832509291.771802936943923.30875963
2508383.93599741 6943503.9829314
#Sta/Elev= 30
    1000   410.3    2927   407.2  3793.4   410.6    3833     390    3903   389.6
    3968     391  4006.6   411.1  5192.4     414    5245     388    5943   385.8
  6008.6     416  6468.4   417.5    6536   389.5    6836     390    6900   381.5
    6929   381.5    6952   375.5    6994   375.8    7000     375    7004     370
    7065     361    7088   373.5    7140   375.8    7170   388.3    7186   389.8
    7761     387  7820.6   412.1    8500   407.5    9100   419.8   10100   419.8
#Mann= 3 ,0,0
    1000     .14       0    6836    .055       0    7186     .14       0
Bank Sta=6836,7186
XS Rating Curve= 0 ,0
Exp/Cntr=0.3,0.1

Type RM Length L Ch R = 1 ,75196   ,272,261,342
BEGIN DESCRIPTION:
This cross section corresponds to cross section 75204 of the non-georeferenced CDC model which was the source of this model.
END DESCRIPTION:
XS GIS Cut Line= 3
2517148.195066426946908.364797382508896.231255416943048.67599447
2506178.789896716941777.64788226
#Sta/Elev= 30
    1000     414    1600     408    1800     392    2170     392    2270     406
    2400     412    2810     414    3620     410  3862.6     396  3889.9     390
  3965.6     386  4012.9   389.6  4063.2     386  4998.8     386    5020     390
  5393.9     386    6194   387.4  7073.4     393  7145.6   392.9  7256.6     386
    7300   366.7    7320     363    7370     370  7440.4     392  7771.5     388
  8324.1     390    9270     388    9320     400   10110     408   13110     408
#Mann= 5 ,-1,0
    1000     .21       0  7256.6    .055       0  7440.4     .21       0
  8324.1     .03       0    9320     .14       0
#XS Ineff= 3 ,-1
    1000    2800   407.4    4650    5010   409.8    8580   10110   407.2
Permanent Ineff=
       F       F       F
Bank Sta=7256.6,7440.4
XS Rating Curve= 0 ,0
Exp/Cntr=0.6,0.4

Type RM Length L Ch R = 1 ,74935   ,684,799,914
BEGIN DESCRIPTION:
Trinity Forest Golf Course in LOB.
LOMR 17-06-4026P.
Added Section based on 2009 LiDAR and proposed Simpkins Remediation Project.
END DESCRIPTION:
XS GIS Cut Line= 5
2517383.060977656946796.095405822511758.059042726944061.75214133
2511509.345788246943975.486964512511260.632533776943889.22178768
2509021.21804206  6942821.284529
#Sta/Elev= 30
    1000  411.74    1565     404 1607.42   393.4 2178.27  389.95 2326.28 404.741
    3991     410    4132     403 4175.46 390.594 4257.76  380.95  5263.2  384.88
 5402.84  401.52 5437.06  392.64 5606.79   385.1 5665.99  392.68 5917.84  390.27
 6130.37  378.11 6251.93  389.83  6451.7  394.68  7082.5  390.52 7251.03  381.52
 7348.73  385.22 7404.91  363.05 7406.95 363.112 7542.34   367.2 7611.25 389.238
 7622.91 394.356 8502.89 390.177 9337.83  387.33 9496.35 399.34810254.89  406.55
#Mann= 8 ,-1,0
    1000    .045       0 1607.42     .21       0 2326.28    .045       0
 4175.46     .21       0 7406.95    .055       0 7622.91     .21       0
 8502.89     .03       0 9496.35     .14       0
#XS Ineff= 2 , 0
            3991     410    8995             404
Permanent Ineff=
       F       F
Bank Sta=7082.5,7611.25
XS Rating Curve= 0 ,0
Exp/Cntr=0.3,0.1

Type RM Length L Ch R = 1 ,74132   ,492,656,585
BEGIN DESCRIPTION:
This cross section corresponds to cross section 71136 of the non-georeferenced CDC model which was the source of this model.
Trinity Forest Golf Course in LOB.
LOMR 17-06-4026P.
Effective Section updated with 2009 LiDAR data and proposed Simpkins Remediation Project.
END DESCRIPTION:
XS GIS Cut Line= 2
  2517034.303557 6945900.14689552509630.866754966942224.65231485
#Sta/Elev= 30
     740   405.5  814.46  404.94  885.07  388.95    1053     413 2567.86  412.44
    2854     403  2989.4  383.95 3578.17  389.72 3690.94  379.47 3739.51  389.43
 3824.95  391.68 4719.61  383.52  6458.9  393.25 6482.02387.1988    6540   363.2
    6625     373 6659.55  389.18 6671.23388.8001 6745.88  369.57 6777.54  374.72
 6799.61  390.09 7103.11  384.06 7242.56390.6369 8247.01  386.16  8541.5  400.56
 8650.85391.8318 8690.29  386.13 8826.66  396.54 8982.29  396.77  9005.6  405.12
#Mann= 6 ,-1,0
     740    .045       0  2989.4     .21       0 6482.02    .055       0
 6671.23     .21       0 7242.56    .056       0 8650.85    .154       0
#XS Ineff= 2 , 0
            2327     414    8390             404
Permanent Ineff=
       F       F
Bank Sta=6458.9,6659.55
XS Rating Curve= 0 ,0
Exp/Cntr=0.3,0.1

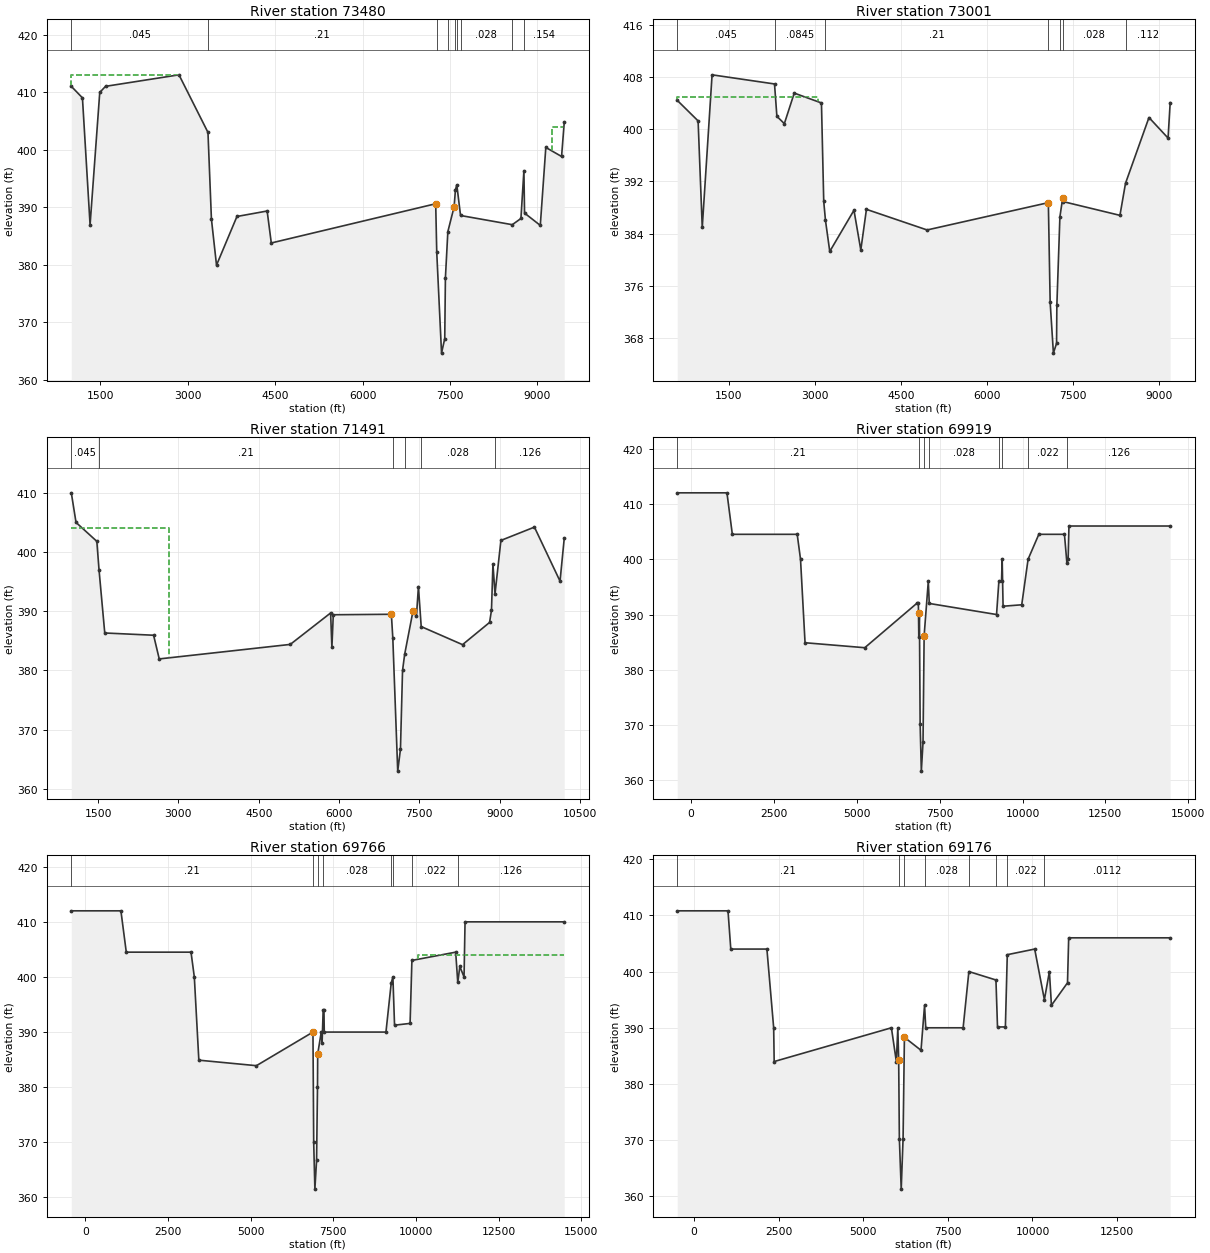
Type RM Length L Ch R = 1 ,73480   ,447,479,482
BEGIN DESCRIPTION:
Trinity Forest Golf Course in LOB.
LOMR 17-06-4026P.
Added Effective Section updated with 2009 LiDAR data and proposed Simpkins Remediation Project.
END DESCRIPTION:
XS GIS Cut Line= 5
2517358.77615518 6945476.9608634 2511670.91699046942550.56208079
2511520.751748756942484.981902312511408.952026386942441.74939912
2509734.682328996941511.65534684
#Sta/Elev= 30
    1000     411    1191     409 1322.08  386.95 1488.18  409.94    1587     411
    2848     413 3345.82     403 3405.02  387.95 3492.35  379.95 3843.13   388.4
 4361.57  389.35 4432.66   383.8 7254.76 390.611 7272.75382.1856    7355  364.67
    7410   367.2  7421.6  377.77 7463.35385.7648 7570.55  390.07 7593.87393.0508
 7617.06393.8905 7681.27388.5714 8569.08386.9745 8717.75  388.05 8768.93396.3603
 8779.94  388.99  9050.2  386.85 9144.92  400.39 9415.36  398.82 9461.34  404.75
#Mann= 9 ,-1,0
    1000    .045       0 3345.82     .21       0 7272.75    .055       0
 7463.35     .21       0 7593.87    .168       0 7617.06    .056       0
 7681.27    .028       0 8569.08    .056       0 8768.93    .154       0
#XS Ineff= 2 , 0
            2848     413 9248.93             404
Permanent Ineff=
       F       F
Bank Sta=7254.76,7570.55
XS Rating Curve= 0 ,0
Exp/Cntr=0.3,0.1

Type RM Length L Ch R = 1 ,73001   ,900,1510,1350
BEGIN DESCRIPTION:
This cross section corresponds to cross section 73020 of the non-georeferenced CDC model which was the source of this model.
Trinity Forest Golf Course in LOB.
LOMR 17-06-4026P.
Effective Section updated with 2009 LiDAR data and proposed Simpkins Remediation Project.
END DESCRIPTION:
XS GIS Cut Line= 3
  2517846.513146 6945332.1864865        2517483.        6945142.
2510235.310200666941350.08030732
#Sta/Elev= 30
     600  404.43  963.37  401.28 1035.66  384.95 1206.92  408.34 2295.02  406.94
 2336.39  401.98 2466.42  400.86 2638.81  405.54 3112.95  404.03 3152.63  388.95
 3183.02386.0308 3257.75  381.28 3679.54  387.59 3798.61   381.5 3896.81  387.73
 4953.62  384.57 7065.02388.7537 7066.73  388.77 7098.38  373.49    7155   365.7
    7210   367.2    7215     373 7268.22386.5758 7316.59  389.46 7320.62388.9244
 8314.48  386.81 8411.39391.7185 8820.27   401.8 9153.04  398.65 9189.97  404.07
#Mann= 7 ,-1,0
     600    .045       0 2295.02   .0845       0 3183.02     .21       0
 7065.02    .055       0 7268.22    .168       0 7320.62    .028       0
 8411.39    .112       0
#XS Ineff= 2 , 0
            3056     405
Permanent Ineff=
       F       F
Bank Sta=7066.73,7316.59
XS Rating Curve= 0 ,0
Exp/Cntr=0.3,0.1

Type RM Length L Ch R = 1 ,71491   ,833,1572,1145
#Sta/Elev= 30
    1000     410    1088     405  1476.6  401.81 1518.13 396.945 1624.68  386.33
 2536.96  385.95 2642.21  381.95 5090.01   384.4 5843.36  389.71 5867.43  383.91
 5893.33  389.41 6978.24  389.49 7005.38 385.443    7097     363    7148   366.7
    7187     380 7226.68 382.729  7384.1  390.12 7446.46  389.12 7483.62  394.17
 7535.48 387.411 8307.62  384.36  8812.6  388.11 8848.12  390.16 8875.56  397.98
 8914.38  392.94 9024.24  401.96 9650.37  404.2110128.74  395.0810207.45  402.33
#Mann= 6 ,-1,0
    1000    .045       0 1518.13     .21       0 7005.38    .055       0
 7226.68    .196       0 7535.48    .028       0 8914.38    .126       0
#XS Ineff= 2 , 0
       0    2825     404               0
Permanent Ineff=
       F       F
Bank Sta=6978.24,7384.1
XS Rating Curve= 0 ,0
Exp/Cntr=0.3,0.1

Type RM Length L Ch R = 1 ,69919   ,161,153,154
BEGIN DESCRIPTION:
This cross section corresponds to cross section 70000 of the non-georeferenced CDC model which was the source of this model.
END DESCRIPTION:
XS GIS Cut Line= 5
2520137.081811856946312.733870752518998.855735186945335.77870372
2513502.254851766940617.97022596 2511120.65462816938583.35716921
 2508839.68946446936634.71715064
#Sta/Elev= 30
    -420     412    1080     412  1242.3   404.5    3200   404.5    3300     400
  3436.7   384.9  5238.9     384  6805.2     392    6857     392  6869.5     386
  6887.9  390.19    6910  370.19    6946  361.69    6997  366.89  7030.8  386.19
    7156     396    7186     392    9216     390    9286     396    9366     396
    9386     400    9413   391.5    9976  391.76   10168     400   10492   404.5
   11265   404.5   11340  399.25   11376     400   11401     406   14456     406
#Mann= 8 ,-1,0
    -420     .21       0  6887.9    .055       0  7030.8    .182       0
    7186    .028       0    9286    .126       0    9386    .028       0
   10168    .022       0   11340    .126       0
Bank Sta=6887.9,7030.8
XS Rating Curve= 0 ,0
Exp/Cntr=0.3,0.1

Type RM Length L Ch R = 1 ,69766   ,407,590,692
BEGIN DESCRIPTION:
This cross section corresponds to cross section 69782 of the non-georeferenced CDC model which was the source of this model.
END DESCRIPTION:
XS GIS Cut Line= 4
2520220.527997456946286.33263317 2519092.50482616945297.61440997
  2511266.2799936938437.88731579 2509010.23365036936460.45086938
#Sta/Elev= 30
    -420     412    1080     412  1242.3   404.5    3200   404.5    3300     400
  3436.7   384.9  5177.5   383.9  6887.9     390    6910     370    6946   361.5
    6997   366.7    7025     380  7030.8     386  7138.5     390  7163.6     388
  7196.8     394  7219.9     394    7230     390  9095.4     390  9254.5   398.9
    9305     400    9355  391.25    9825  391.57    9880     403   11204   404.5
   11267     399 11329.2   401.9   11457     400   11487     410   14487     410
#Mann= 8 ,-1,0
    -420     .21       0  6887.9    .055       0  7030.8    .182       0
  7196.8    .028       0  9254.5    .126       0    9305    .028       0
    9880    .022       0   11267    .126       0
#XS Ineff= 2 , 0
       0    2480     40410060.15       0     404
Permanent Ineff=
       F       F
Bank Sta=6887.9,7030.8
XS Rating Curve= 0 ,0
Exp/Cntr=0.3,0.1

Type RM Length L Ch R = 1 ,69176   ,770,1016,674
BEGIN DESCRIPTION:
This cross section corresponds to cross section 69100 of the non-georeferenced CDC model which was the source of this model.
END DESCRIPTION:
XS GIS Cut Line= 6
2519962.221802626945649.507311022518874.006247346944617.13775255
 2515914.56826866941809.574798142513661.065557756939701.99075872
2511555.366685186937700.262478712509381.046201596935633.30083547
#Sta/Elev= 30
    -500   410.8    1000   410.8  1082.4     404    2150     404    2350     390
    2365     384    5830     390  5975.7     384    6020     390    6045  384.31
    6065  370.31    6120  361.31    6175  370.31  6214.5  388.31    6705     386
    6810     394    6845     390    7950     390    8120     400    8920   398.5
    8966  390.15    9199  390.15    9255     403   10065     404   10352     395
   10500     400   10560     394   11035     398   11070     406   14070     406
#Mann= 8 ,-1,0
    -500     .21       0    6045    .055       0  6214.5   .0845       0
    6810    .028       0    8120    .112       0    8920    .028       0
    9255    .022       0   10352   .0112       0
Bank Sta=6045,6214.5
XS Rating Curve= 0 ,0
Exp/Cntr=0.3,0.1

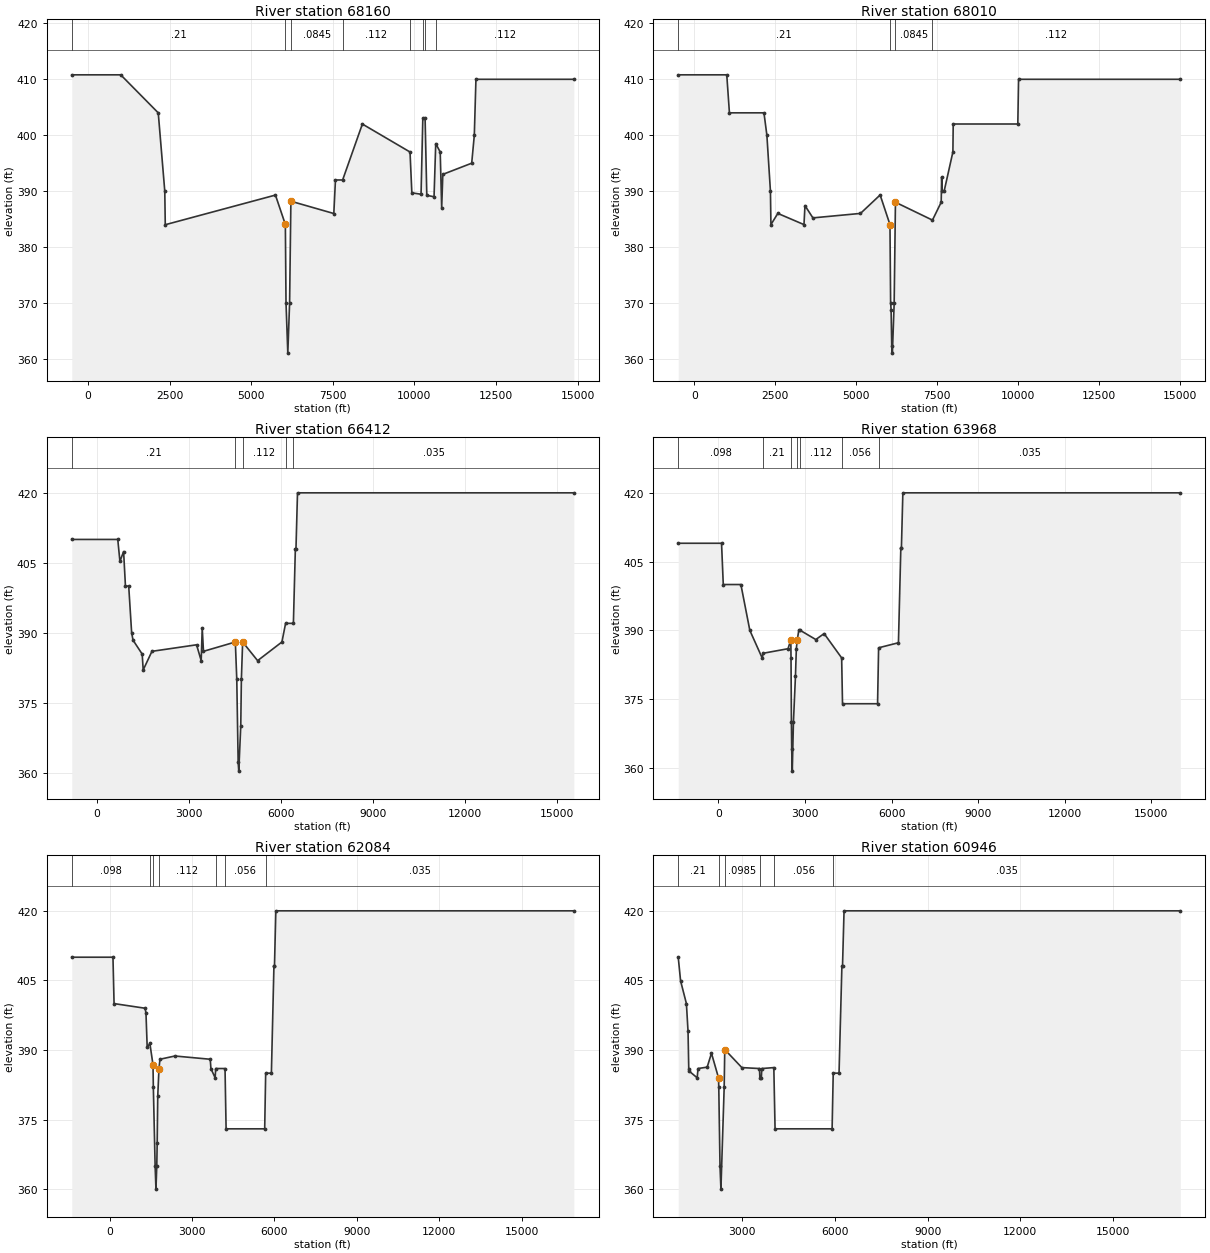
Type RM Length L Ch R = 1 ,68160   ,97,150,219
BEGIN DESCRIPTION:
This cross section corresponds to cross section 68150 of the non-georeferenced CDC model which was the source of this model.
END DESCRIPTION:
XS GIS Cut Line= 6
2520664.47891507  6945764.6722222519642.965011276944666.26002963
2516722.098805766941525.514670712514741.519105496939472.78419614
2512199.576354746936724.589233222510162.509831086934522.23595134
#Sta/Elev= 30
    -500   410.8    1000   410.8    2150     404    2350     390    2365     384
  5741.1   389.3    6045  384.04    6065  370.04    6120  361.04    6175  370.04
  6214.5   388.2    7530     386    7580     392    7800     392    8405     402
    9865     397    9921   389.7   10203  389.45   10257     403   10327     403
   10379  389.25   10601     389   10653   398.5   10790     397   10835     387
   10870     393   11755     395   11835     400   11885     410   14885     410
#Mann= 8 ,-1,0
    -500     .21       0    6045    .055       0  6214.5   .0845       0
    7800    .112       0    9865    .028       0   10257    .013       0
   10327    .028       0   10653    .112       0
Bank Sta=6045,6214.5
XS Rating Curve= 0 ,0
Exp/Cntr=0.3,0.1

Type RM Length L Ch R = 1 ,68010   ,1107,1598,1205
BEGIN DESCRIPTION:
This cross section corresponds to cross section 68027 of the non-georeferenced CDC model which was the source of this model.
----------------------------------------------------------------------------
CDC DAL072100-1 Simpson Stuart Road and Adjacent Industrial Park Development
Cross-section 68027 - 71510
Located in ROB.
----------------------------------------------------------------------------
END DESCRIPTION:
XS GIS Cut Line= 6
2520766.782297256945782.338193552519753.699369856944676.14518046
2516821.999852666941475.000007972514876.000135756939429.00016296
2513632.998684766938051.268666462510283.647207886934338.87796984
#Sta/Elev= 30
    -500   410.8    1000   410.8  1082.4     404    2150     404    2240     400
    2350     390    2365     384  2578.8     386    3387     384  3417.6   387.4
  3662.7   385.2  5133.9     386  5741.1   389.3    6045     384    6065     370
    6080   368.8    6100   362.2    6120     361    6175     370  6214.5     388
  7358.5   384.8  7628.4     388  7642.4   392.5  7659.2     390  7720.4     390
  7990.2     397    8000     402  9996.9     402   10020     410   15020     410
#Mann= 4 ,-1,0
    -500     .21       0    6045    .055       0  6214.5   .0845       0
  7358.5    .112       0
Bank Sta=6045,6214.5
XS Rating Curve= 0 ,0
Exp/Cntr=0.3,0.1

Type RM Length L Ch R = 1 ,66412   ,1008,2444,1815
BEGIN DESCRIPTION:
This cross section corresponds to cross section 66395 of the non-georeferenced CDC model which was the source of this model.
END DESCRIPTION:
XS GIS Cut Line= 4
 2521465.6429241 6945068.3603107 2520482.2156293 6943935.7214645
 2514011.2640044 6936482.9578267      2509883.64      6933485.74
#Sta/Elev= 30
    -810     410     690     410     760   405.3     880   407.4     940     400
  1046.6     400    1142     390  1186.9   388.4  1486.6   385.4  1518.3     382
    1804     386  3259.2   387.4  3409.7     384  3443.4     391  3484.1     386
    4523     388    4570     380    4615   362.2    4635   360.3    4700     370
    4720     380  4761.2     388  5249.3     384  6041.7     388  6161.7     392
    6416     392    6480     408    6500     408    6550     420   15560     420
#Mann= 5 ,-1,0
    -810     .21       0    4523    .055       0  4761.2    .112       0
  6161.7    .098       0    6416    .035       0
Bank Sta=4523,4761.2
XS Rating Curve= 0 ,0
Exp/Cntr=0.3,0.1

Type RM Length L Ch R = 1 ,63968   ,750,1884,950
BEGIN DESCRIPTION:
This cross section corresponds to cross section 63971 of the non-georeferenced CDC model which was the source of this model.
END DESCRIPTION:
XS GIS Cut Line= 5
 2521890.8117958 6945461.5249048 2521201.2627477 6944129.4130062
 2519100.9998878 6940072.0001893 2514205.5556105 6936072.9363371
       2510008.9      6933285.32
#Sta/Elev= 30
   -1390     409     110     409     170     400     780     400  1089.7     390
  1523.5   383.9  1543.5     385  2414.2     386  2509.2     388  2516.2     384
    2530     370    2540   364.1    2560   359.3    2600     370    2670     380
  2700.7     386  2733.8     388  2785.9     390  2836.8     390  3374.9     388
  3662.7   389.3    4270     384    4300     374    5514     374    5550   386.2
    6237   387.3    6320     408    6340     408    6390     420   16000     420
#Mann= 7 ,-1,0
   -1390    .098       0  1543.5     .21       0  2509.2    .055       0
  2733.8    .168       0  2836.8    .112       0    4270    .056       0
    5550    .035       0
Bank Sta=2509.2,2733.8
XS Rating Curve= 0 ,0
Exp/Cntr=0.3,0.1

Type RM Length L Ch R = 1 ,62084   ,904,1138,804
BEGIN DESCRIPTION:
This cross section corresponds to cross section 62087 of the non-georeferenced CDC model which was the source of this model.
END DESCRIPTION:
XS GIS Cut Line= 5
2522481.226697496945634.409384892521916.358758426944244.83239479
2520098.971973276939774.054919052514352.916208186935857.38755555
2510221.412093846933041.24236164
#Sta/Elev= 30
   -1380     410     120     410     160     400  1287.8     399  1321.5     398
  1365.8   390.6  1464.1   391.4  1577.6   386.8  1589.9     382    1655     365
    1685     360    1715     365    1730     370    1750     380    1795     386
  1831.3     388  2374.7   388.7  3661.7     388  3686.1     386  3839.6     384
  3860.1     386    4200     386    4239     373    5644     373    5680     385
    5888     385    5980     408    6000     408    6050     420   16900     420
#Mann= 7 ,-1,0
   -1380    .098       0  1464.1    .196       0  1577.6    .055       0
    1795    .112       0  3860.1    .098       0    4200    .056       0
    5680    .035       0
Bank Sta=1577.6,1795
XS Rating Curve= 0 ,0
Exp/Cntr=0.3,0.1

Type RM Length L Ch R = 1 ,60946   ,1151,1504,851
BEGIN DESCRIPTION:
This cross section corresponds to cross section 60954 of the non-georeferenced CDC model which was the source of this model.
END DESCRIPTION:
XS GIS Cut Line= 6
2522541.265973186943125.02459505 2522354.99994156942874.00016272
2521249.999854926940573.000171562520098.999860356939774.00012913
2514368.388290086935817.584813642510253.757578786932976.84298981
#Sta/Elev= 30
     940     410    1016   404.9  1204.1     400    1257     394    1280     386
  1301.3   385.4  1552.5     384  1579.9     386  1875.5   386.3  2014.4   389.3
  2241.9     384  2250.5     382    2290     365    2320     360  2425.2     382
  2443.7   390.1  2996.8   386.2  3566.5     386  3578.7     384  3626.5     384
  3641.5     386    4030   386.2    4070     373    5914     373    5950     385
    6138     385    6230     408    6250     408    6300     420   17170     420
#Mann= 6 ,-1,0
     940     .21       0  2241.9    .063       0  2443.7   .0985       0
  3578.7    .098       0    4030    .056       0    5950    .035       0
Bank Sta=2241.9,2443.7
XS Rating Curve= 0 ,0
Exp/Cntr=0.3,0.1

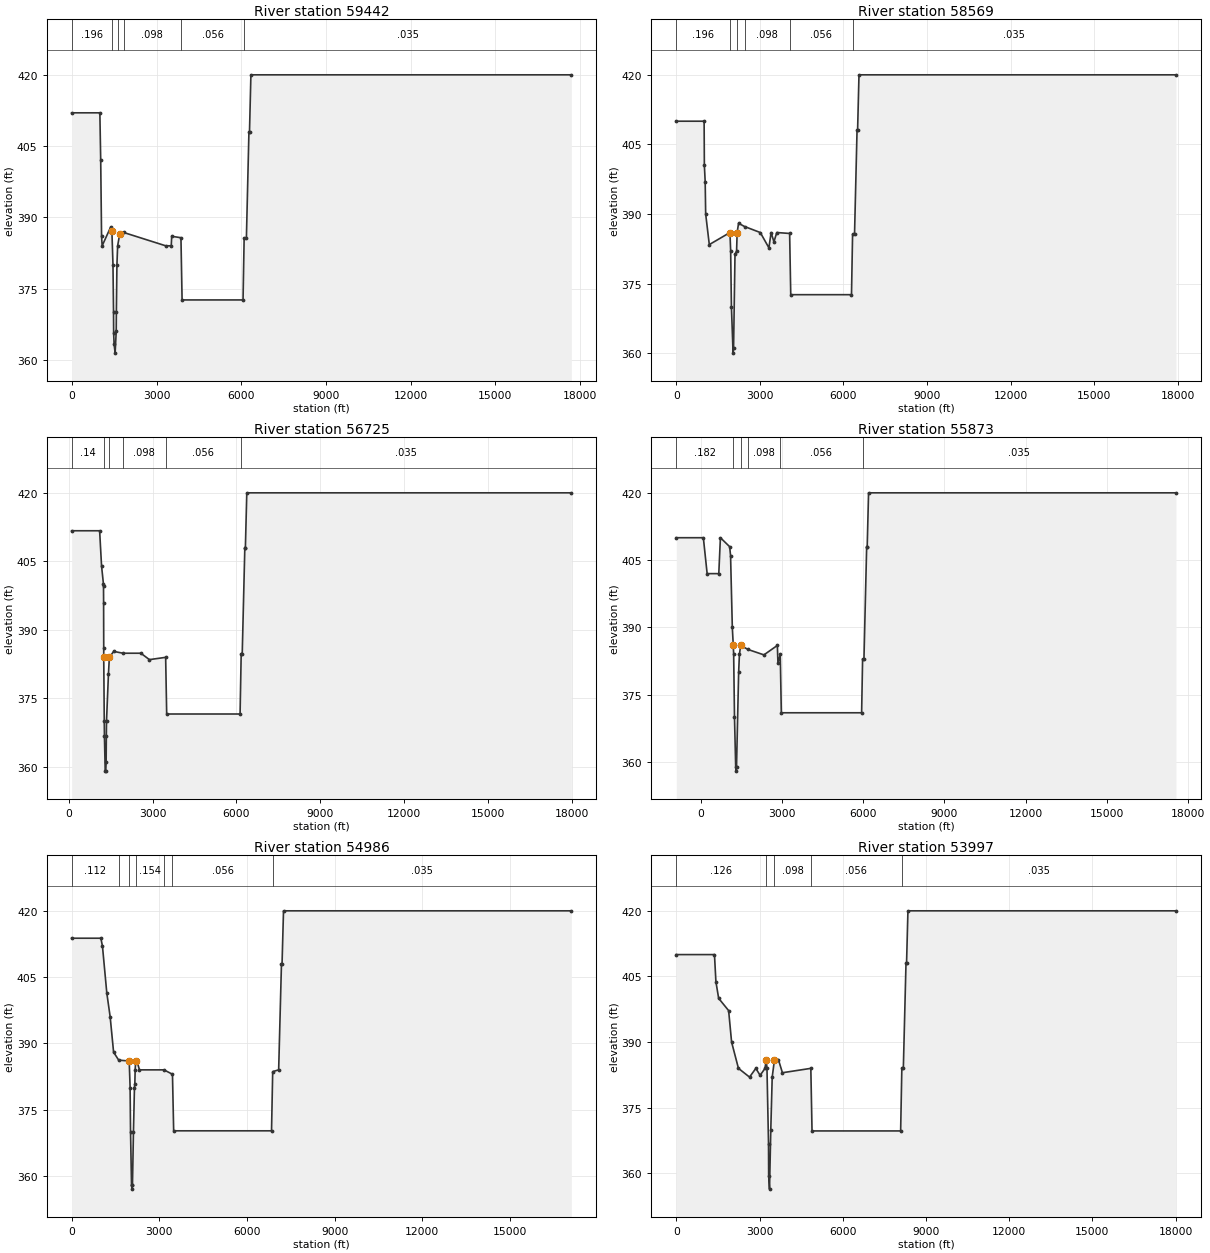
Type RM Length L Ch R = 1 ,59442   ,957,873,604
BEGIN DESCRIPTION:
This cross section corresponds to cross section 59451 of the non-georeferenced CDC model which was the source of this model.
END DESCRIPTION:
XS GIS Cut Line= 5
2524143.339898956943563.733072482523562.464062016942749.74089681
2521825.000017266940315.000031382514635.463543336935373.66641013
2510514.859916226932541.59548089
#Sta/Elev= 30
     -15     412     985     412  1014.9     402  1045.5     386  1066.1     384
  1372.6     388  1412.2   387.1    1450     380    1470     370    1474   365.6
    1490   363.3    1526   361.4    1565     366    1570     370    1590     380
  1615.5     384  1689.8   386.5  1831.5   386.8  3318.8     384  3515.3     384
  3532.4     386    3860   385.7    3900   372.6    6061   372.6    6100   385.6
    6180   385.6    6270     408    6290     408    6340     420   17700     420
#Mann= 6 ,-1,0
     -15    .196       0  1412.2    .055       0  1615.5    .168       0
  1831.5    .098       0    3860    .056       0    6100    .035       0
Bank Sta=1412.2,1689.8
XS Rating Curve= 0 ,0
Exp/Cntr=0.3,0.1

Type RM Length L Ch R = 1 ,58569   ,1408,1844,1006
BEGIN DESCRIPTION:
This cross section corresponds to cross section 58584 of the non-georeferenced CDC model which was the source of this model.
END DESCRIPTION:
XS GIS Cut Line= 5
2525286.518457996942682.383982192524461.126962846942117.82319738
2521825.08236617 6940314.7910423 2514617.24212316935360.50206639
2510496.738638086932528.28543803
#Sta/Elev= 30
       0     410    1000     410  1008.7   400.5    1038     397  1055.8     390
    1186   383.4  1927.6     386  1952.7     382    1980     370    2040     360
    2057     361  2108.8   381.3  2165.4     382  2185.8     386  2236.5     388
    2450   387.3  3016.9     386    3326   382.7  3404.5     386  3506.4     384
  3609.5     386    4070   385.8    4110   372.6    6291   372.6    6330   385.6
    6400   385.6    6490     408    6510     408    6560     420   17940     420
#Mann= 6 ,-1,0
       0    .196       0  1927.6    .055       0  2185.8    .126       0
    2450    .098       0    4070    .056       0    6330    .035       0
Bank Sta=1927.6,2185.8
XS Rating Curve= 0 ,0
Exp/Cntr=0.3,0.1

Type RM Length L Ch R = 1 ,56725   ,865,852,696
BEGIN DESCRIPTION:
This cross section corresponds to cross section 56750 of the non-georeferenced CDC model which was the source of this model.
END DESCRIPTION:
XS GIS Cut Line= 5
2525909.816090616941372.512288442524981.92152491 6940999.6695938
2523053.999855856940225.000211392514991.958893336934685.29606771
2510871.04568382 6931853.6756271
#Sta/Elev= 30
   110.4   411.7  1110.4   411.7  1179.1     404  1247.4     400    1249   399.6
  1252.5     396  1256.9   386.1  1257.4     384    1276     370    1282   366.7
    1310   359.1    1329   359.1    1343   361.1    1350   366.7    1356     370
    1426   380.4  1458.2     384  1613.3   385.3    1946   384.9  2584.7   384.9
  2888.8   383.5    3470     384    3507   371.6    6130   371.6    6170   384.8
    6207   384.8    6300     408    6320     408    6370     420   17970     420
#Mann= 6 ,-1,0
   110.4     .14       0  1257.4    .055       0  1458.2    .154       0
    1946    .098       0    3470    .056       0    6170    .035       0
Bank Sta=1257.4,1458.2
XS Rating Curve= 0 ,0
Exp/Cntr=0.3,0.1

Type RM Length L Ch R = 1 ,55873   ,887,887,798
BEGIN DESCRIPTION:
This cross section corresponds to cross section 55893 of the non-georeferenced CDC model which was the source of this model.
END DESCRIPTION:
XS GIS Cut Line= 5
2526933.522219856940626.692987152525965.307353446940376.57307097
   2523265.000096939678.99999104  2515251.764148 6934282.3483828
2511104.575317236931489.35271472
#Sta/Elev= 30
    -900     410     100     410     240     402     670     402     730     410
  1071.6     408  1104.9     406  1169.7     390  1204.8     386  1219.2     384
    1250     370    1294     359    1310     358    1325     359  1403.2     380
  1431.7     384  1478.6     386    1750   385.1  2336.3   383.9  2832.7     386
  2854.6     382    2940     384    2979     371    5944     371    5980     383
    6030     383    6130     408    6150     408    6200     420   17550     420
#Mann= 6 ,-1,0
    -900    .182       0  1204.8    .055       0  1478.6    .182       0
    1750    .098       0    2940    .056       0    5980    .035       0
Bank Sta=1204.8,1478.6
XS Rating Curve= 0 ,0
Exp/Cntr=0.3,0.1

Type RM Length L Ch R = 1 ,54986   ,1000,989,1000
BEGIN DESCRIPTION:
This cross section corresponds to cross section 55003 of the non-georeferenced CDC model which was the source of this model.
END DESCRIPTION:
XS GIS Cut Line= 5
2526924.71181251 6939573.92203452525941.496377416939391.47366321
2523362.999893996938913.000210722516264.936334256934277.78080663
2512078.516126436931543.93994741
#Sta/Elev= 30
       0   413.8    1000   413.8  1054.5     412  1202.9   401.4    1318     396
  1435.2     388    1610   386.2    1970     386    2000     380    2015     370
    2049     358    2065     357    2081     358    2115     370  2149.5     380
  2162.5   380.9  2173.3     384  2191.2     386    2230   386.1  2320.4     384
    3160     384    3450     383    3491   370.2    6840   370.2    6880   383.6
    7084     384    7180     408    7200     408    7250     420   17100     420
#Mann= 7 ,-1,0
       0    .112       0    1610    .182       0    1970    .055       0
  2191.2    .154       0    3160    .098       0    3450    .056       0
    6880    .035       0
Bank Sta=1970,2191.2
XS Rating Curve= 0 ,0
Exp/Cntr=0.3,0.1

Type RM Length L Ch R = 1 ,53997   ,427,421,427
BEGIN DESCRIPTION:
This cross section corresponds to cross section 54014 of the non-georeferenced CDC model which was the source of this model.
END DESCRIPTION:
XS GIS Cut Line= 5
2528316.979376556938832.17794604 2527333.91518056938648.91642129
2522704.999897666937786.000168132516559.752017596933843.22327679
 2512351.45042546931143.18666423
#Sta/Elev= 30
       0     410    1377     410  1428.8   403.8  1528.1     400  1887.2   397.2
  1994.3     390  2241.2     384    2641     382  2867.9     384  3022.4   382.4
  3198.4     384  3242.4     386  3269.2     384    3325   366.8    3330   359.5
    3361   356.4    3407     370  3457.8     382  3540.3     386  3681.3     386
    3826     383    4850     384    4893   369.7    8087   369.7    8130     384
    8184     384    8280     408    8300     408    8350     420   18010     420
#Mann= 5 ,-1,0
       0    .126       0  3242.4    .055       0  3540.3    .098       0
    4850    .056       0    8130    .035       0
Bank Sta=3242.4,3540.3
XS Rating Curve= 0 ,0
Exp/Cntr=0.3,0.1

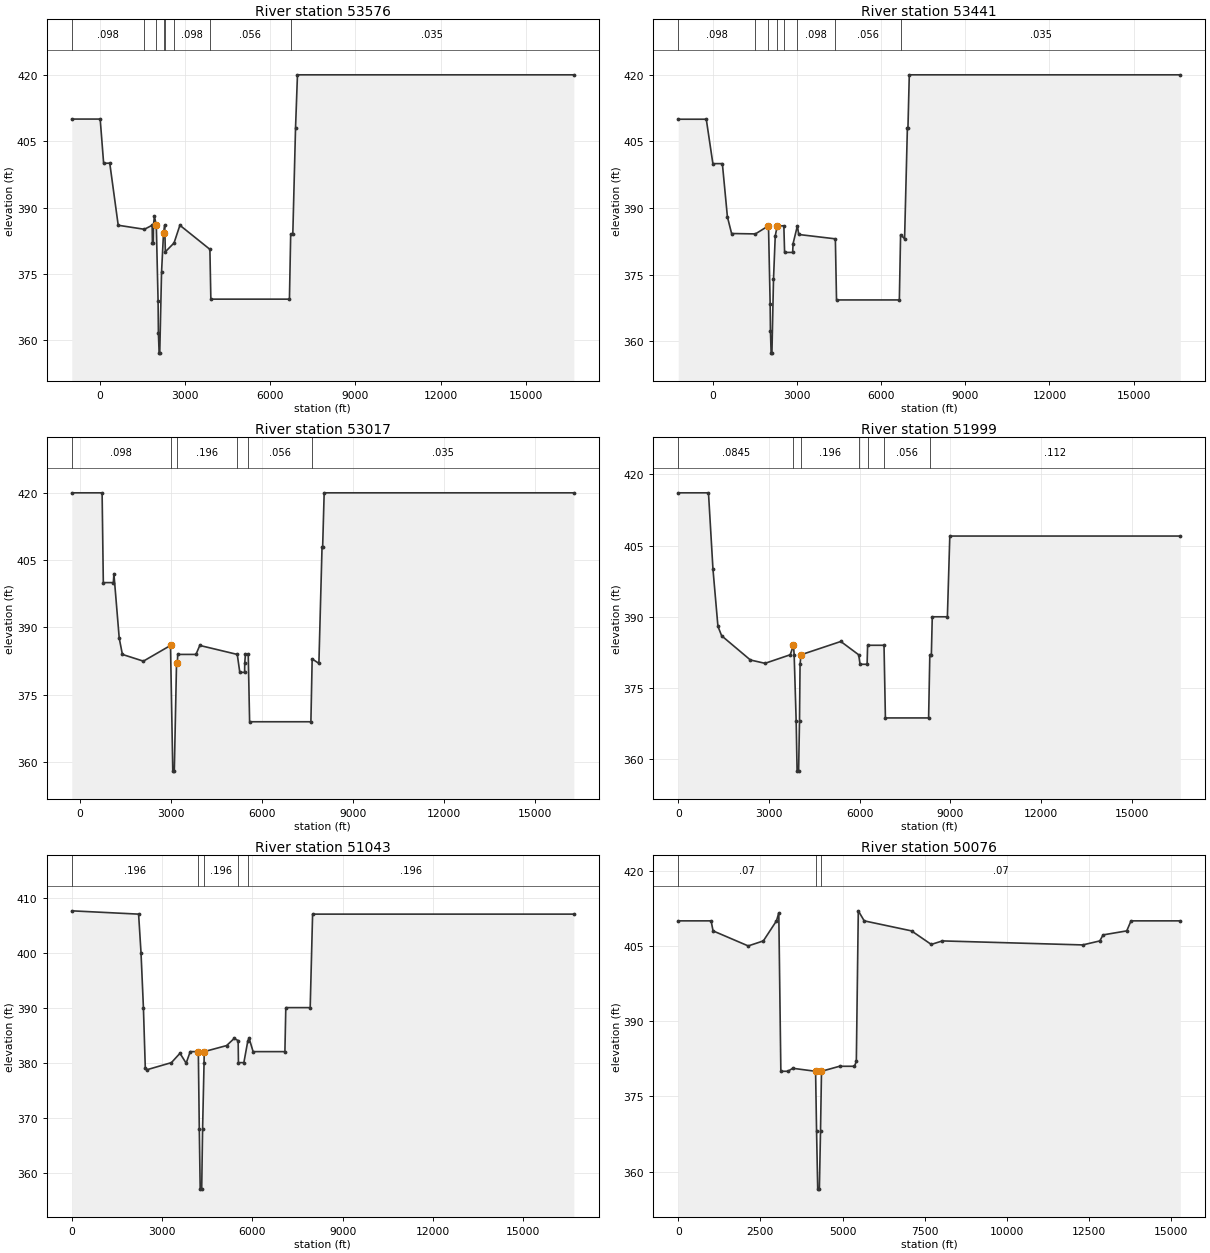
Type RM Length L Ch R = 1 ,53576   ,137,135,137
BEGIN DESCRIPTION:
This cross section corresponds to cross section 53580 of the non-georeferenced CDC model which was the source of this model.
END DESCRIPTION:
XS GIS Cut Line= 6
2528134.545594136938371.381576282527151.562526856938187.68538839
 2522681.91497016937352.41442113 2522346.33690116937211.70636922
2514507.659337016932230.012920542512397.706701066930889.08045615
#Sta/Elev= 30
   -1000     410    1.66     410  123.42     400  339.04  400.04   637.2     386
 1560.69  385.09 1833.54     386 1842.56     382 1872.12     382 1879.06     386
 1912.85     388 1980.13     386 2042.72  368.81 2053.62  361.72 2079.63   357.1
 2101.64   357.1  2164.4  375.36 2234.19  384.24 2276.09     386 2298.65     380
 2605.45     382 2811.49     386 3868.96  380.56 3902.74   369.3 6673.04   369.3
 6717.14     384 6791.98     384 6887.98     408 6955.98     42016698.65     420
#Mann= 8 ,-1,0
   -1000    .098       0 1560.69    .126       0 1980.13    .055       0
 2234.19    .126       0 2276.09    .065       0 2605.45    .098       0
 3868.96    .056       0 6717.14    .035       0
Bank Sta=1980.13,2234.19
XS Rating Curve= 0 ,0
Exp/Cntr=0.3,0.1

Type RM Length L Ch R = 1 ,53441   ,430,424,430
BEGIN DESCRIPTION:
This cross section corresponds to cross section 53445 of the non-georeferenced CDC model which was the source of this model.
END DESCRIPTION:
XS GIS Cut Line= 6
2528385.19297907 6938281.52359962527402.239190856938097.67080463
2522672.603965076937213.034450552522329.419284026937089.92019546
2514537.64845026 6932152.9057913  2512425.8735386930814.84498553
#Sta/Elev= 30
   -1235     410    -235     410       0     400  338.25     400  518.31     388
  667.45  384.26 1517.26  384.17 1983.06     386  2041.9  368.44 2052.16  362.41
 2076.61  357.32 2105.46  357.32 2161.35  373.92 2223.48  383.69 2294.57     386
 2530.53     386 2557.02     380 2843.71     380 2860.12     382 3013.26     386
 3060.59  384.04 4366.94  383.06 4408.22   369.3 6648.46   369.3 6692.56     384
 6835.04  383.07 6934.76     408 6954.76     408 7002.76     42016665.47     420
#Mann= 8 ,-1,0
   -1235    .098       0 1517.26    .126       0 1983.06    .055       0
 2294.57    .196       0 2530.53    .065       0 3013.26    .098       0
 4366.94    .056       0 6692.56    .035       0
Bank Sta=1983.06,2294.57
XS Rating Curve= 0 ,0
Exp/Cntr=0.3,0.1

Type RM Length L Ch R = 1 ,53017   ,1016,1018,1016
BEGIN DESCRIPTION:
This cross section corresponds to cross section 53028 of the non-georeferenced CDC model which was the source of this model.
END DESCRIPTION:
XS GIS Cut Line= 5
2528461.542538256937873.60187001 2527479.05498216937687.27365956
2522268.000115516936699.000045552516137.488098356932836.07240397
2513599.345204786931236.75046896
#Sta/Elev= 30
    -270     420     730     420     770     400  1100.8     400  1118.6     402
  1294.5   387.6  1399.2     384  2090.8   382.5  2984.8     386    3060     358
    3110     358  3183.1     382  3211.7     382  3221.9     384  3823.4     384
  3949.6     386  5185.3     384  5268.9     380  5427.6     380  5431.3     382
  5453.2     384  5547.2     384  5592.2     369  7612.4     369  7654.4     383
    7876     382    7980     408    8000     408    8050     420   16280     420
#Mann= 6 ,-1,0
    -270    .098       0  2984.8    .055       0  3183.1    .196       0
  5185.3    .065       0  5547.2    .056       0  7654.4    .035       0
Bank Sta=2984.8,3183.1
XS Rating Curve= 0 ,0
Exp/Cntr=0.3,0.1

Type RM Length L Ch R = 1 ,51999   ,990,956,990
BEGIN DESCRIPTION:
This cross section corresponds to cross section 52016 of the non-georeferenced CDC model which was the source of this model.
END DESCRIPTION:
XS GIS Cut Line= 5
2529177.651470326936917.10245814 2528192.60637656936744.80572821
2522184.999953426935694.00008705 2514966.51898366931199.81386547
2514117.60415186 6930671.2841989
#Sta/Elev= 30
       0   416.1    1000   416.1  1148.6     400  1312.4     388  1435.2     386
  2386.1   380.9  2870.2   380.2  3702.7     382  3810.1     384  3833.2     382
    3900     368    3930   357.5    3980   357.5    4010     368  4028.3     380
  4059.7     382  5376.1   384.8  5966.6     382 6011.91     380  6245.5     380
  6262.2     384 6804.53     384 6850.43   368.7  8279.3   368.7  8319.2     382
    8370     382    8400     390    8900     390    8980     407   16602     407
#Mann= 7 ,-1,0
       0   .0845       0  3810.1    .055       0  4059.7    .196       0
  5966.6    .065       0  6262.2    .196       0 6804.53    .056       0
  8319.2    .112       0
Bank Sta=3810.1,4059.7
XS Rating Curve= 0 ,0
Exp/Cntr=0.3,0.1

Type RM Length L Ch R = 1 ,51043   ,1000,967,1000
BEGIN DESCRIPTION:
51060  Five Mile Creek
END DESCRIPTION:
XS GIS Cut Line= 5
2529688.141456386936036.458120822528703.114541836935864.05748972
2522234.999853436934732.000042542515368.60938674 6930413.4151758
2514522.115507296929881.01672347
#Sta/Elev= 30
       0   407.6    2220     407    2300     400    2380     390  2441.9   379.1
  2491.6   378.7  3310.2     380  3594.8   381.7  3799.3   379.9  3934.6     382
  4204.1     382    4236     368    4266     357    4316     357    4346     368
  4394.4     380  4399.1     382  5143.1   383.1  5395.5   384.4 5526.93     384
 5536.56     380 5716.67     380 5849.82     384  5892.2   384.4  6023.8     382
    7080     382    7110     390    7920     390    8000     407   16678     407
#Mann= 5 ,-1,0
       0    .196       0  4204.1    .055       0  4399.1    .196       0
 5526.93    .065       0 5849.82    .196       0
Bank Sta=4204.1,4399.1
XS Rating Curve= 0 ,0
Exp/Cntr=0.3,0.1

Type RM Length L Ch R = 1 ,50076   ,180,180,180
BEGIN DESCRIPTION:
This cross section corresponds to cross section 50093 of the non-georeferenced CDC model which was the source of this model.
END DESCRIPTION:
XS GIS Cut Line= 6
2529826.035533716934904.095777922525130.481595256934265.45405963
  2523848.2627036933946.670248392522898.995572696933594.49017847
2520832.467881596932507.589793222515860.561979476929388.99380003
#Sta/Elev= 30
       0     410    1000     410    1060     408    2130     405    2590     406
    2990     410    3060   411.6    3123     380    3339     380    3483   380.6
    4180     380    4210     368    4245   356.5    4295   356.5    4330     368
    4360     380    4908     381    5364     381    5420     382    5480     412
    5660     410    7100     408    7700   405.3    8040     406   12310   405.2
   12830     406   12930   407.2   13650     408   13780     410   15280     410
#Mann= 3 ,0,0
       0     .07       0    4180    .056       0    4360     .07       0
Bank Sta=4180,4360
XS Rating Curve= 0 ,0
Exp/Cntr=0.5,0.3