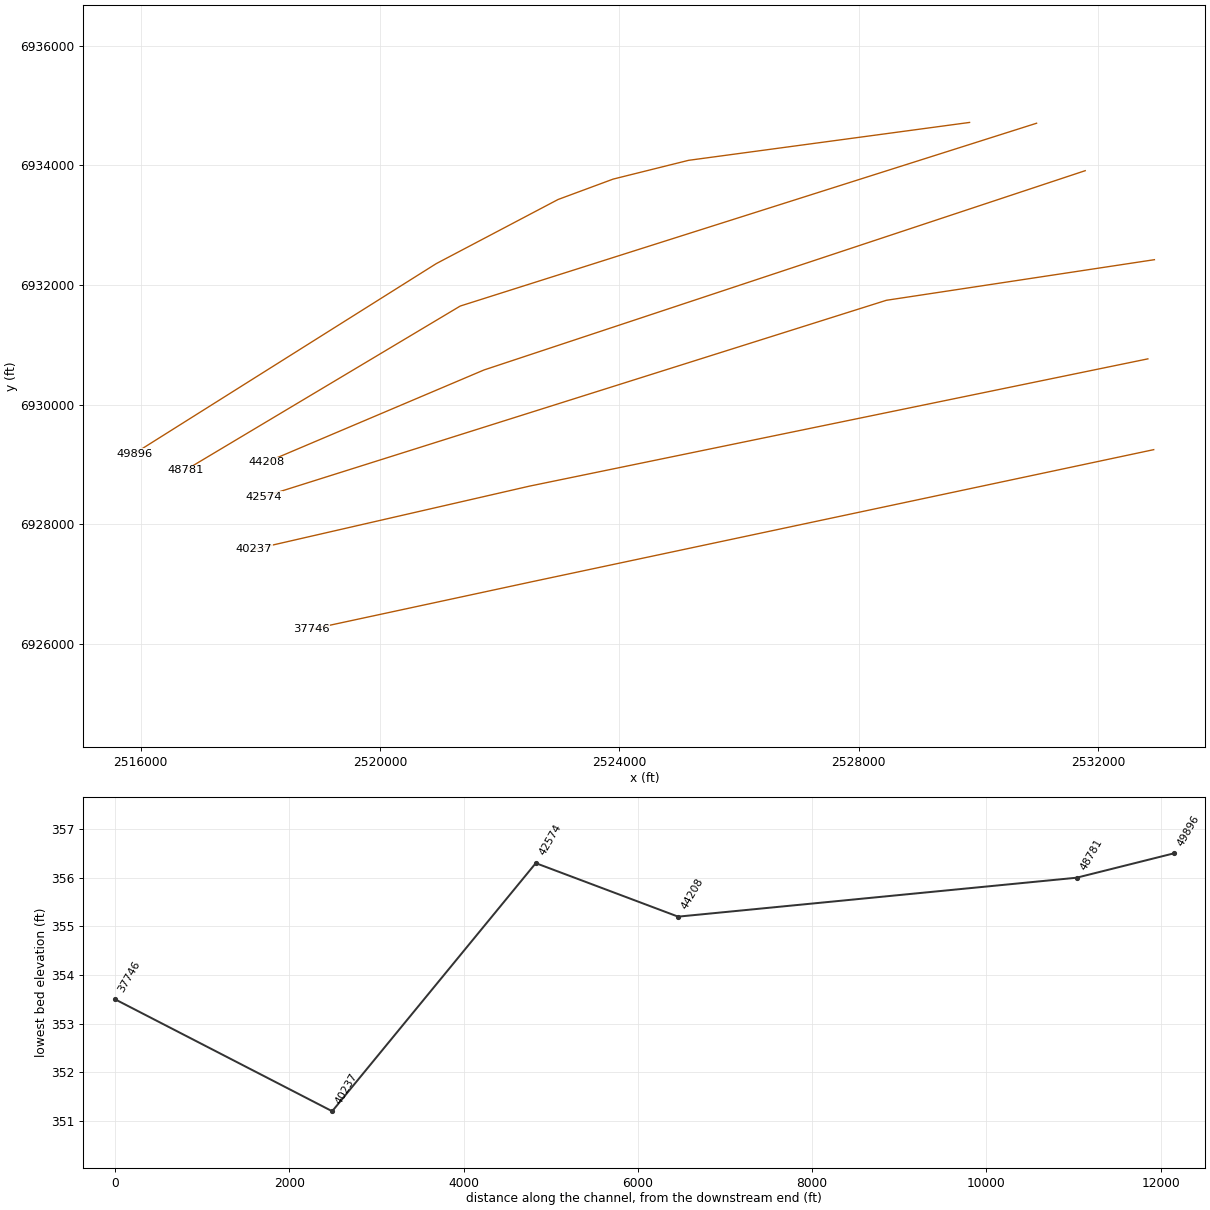
HEC-RAS study CDC_Consolidated_Model.prj: Upper Trinity CDC Consolidated Model

--- CDC_Consolidated_Model.g04 (geometry) --- (continued)

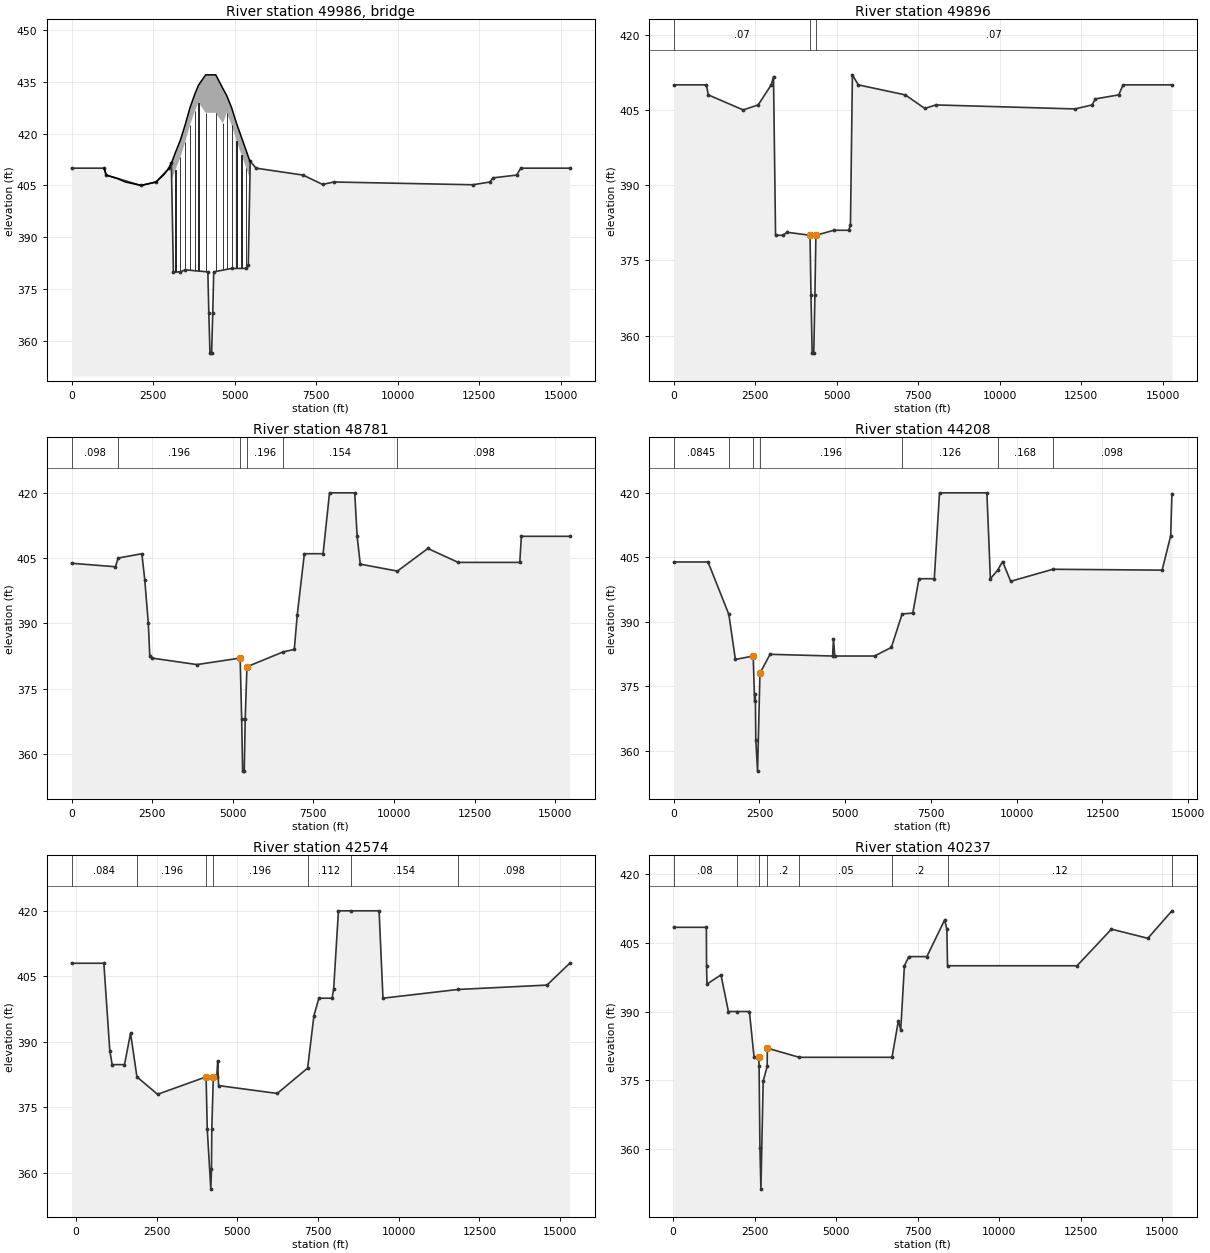
Type RM Length L Ch R = 3 ,49986   ,,,
BEGIN DESCRIPTION:
50003  IH 20/IH 635
END DESCRIPTION:
Node Name=IH20/IH 635
Bridge Culvert--1,0,-1,-1, 0
Deck Dist Width WeirC Skew NumUp NumDn MinLoCord MaxHiCord MaxSubmerge Is_Ogee
1,178,2.6,0, 26, 26, , , 0.95, 0, ,,,
    1000    1060    1410    1650    2130    2590    2820    2990    3060    3070
    3183    3333    3483    3633    3783    3893    4113    4423    4643    4758
    4908    5058    5208    5358    5470    5480
     410     408     407     406     405     406     408     410   411.6   411.6
   414.5     418   422.5   427.5   431.5     434     437     437     433     431
   427.5     423     419     415     412     412
     410     408     407     406     405     406     408     410   411.6   406.6
   409.5     413   417.5   422.5   426.5     429     426     426     423     426
   422.5     418     414     410     407     412
    1000    1060    1410    1650    2130    2590    2820    2990    3060    3070
    3183    3333    3483    3633    3783    3893    4113    4423    4643    4758
    4908    5058    5208    5358    5470    5480
     410     408     407     406     405     406     408     410   411.6   411.6
   414.5     418   422.5   427.5   431.5     434     437     437     433     431
   427.5     423     419     415     412     412
     410     408     407     406     405     406     408     410   411.6   406.6
   409.5     413   417.5   422.5   426.5     429     426     426     423     426
   422.5     418     414     410     407     412
Pier Skew, UpSta & Num, DnSta & Num=  ,3186, 2 ,3186, 2 , 0 , 0 , 0 ,,
       6       6
       0     410
       6       6
       0     410
Pier Skew, UpSta & Num, DnSta & Num=  ,3336, 2 ,3336, 2 , 0 , 0 , 0 ,,
       6       6
       0   413.5
       6       6
       0   413.5
Pier Skew, UpSta & Num, DnSta & Num=  ,3486, 2 ,3486, 2 , 0 , 0 , 0 ,,
       6       6
       0     418
       6       6
       0     418
Pier Skew, UpSta & Num, DnSta & Num=  ,3636, 2 ,3636, 2 , 0 , 0 , 0 ,,
       6       6
       0     423
       6       6
       0     423
Pier Skew, UpSta & Num, DnSta & Num=  ,3786, 2 ,3786, 2 , 0 , 0 , 0 ,,
       6       6
       0     427
       6       6
       0     427
Pier Skew, UpSta & Num, DnSta & Num=  ,3895, 2 ,3895, 2 , 0 , 0 , 0 ,,
       4       4
       0   429.5
       4       4
       0   429.5
Pier Skew, UpSta & Num, DnSta & Num=  ,4115, 2 ,4115, 2 , 0 , 0 , 0 ,,
       4       4
       0   426.5
       4       4
       0   426.5
Pier Skew, UpSta & Num, DnSta & Num=  ,4425, 2 ,4425, 2 , 0 , 0 , 0 ,,
       4       4
       0   426.5
       4       4
       0   426.5
Pier Skew, UpSta & Num, DnSta & Num=  ,4645, 2 ,4645, 2 , 0 , 0 , 0 ,,
       4       4
       0   423.5
       4       4
       0   423.5
Pier Skew, UpSta & Num, DnSta & Num=  ,4761, 2 ,4761, 2 , 0 , 0 , 0 ,,
       6       6
       0   426.5
       6       6
       0   426.5
Pier Skew, UpSta & Num, DnSta & Num=  ,4911, 2 ,4911, 2 , 0 , 0 , 0 ,,
       6       6
       0     423
       6       6
       0     423
Pier Skew, UpSta & Num, DnSta & Num=  ,5061, 2 ,5061, 2 , 0 , 0 , 0 ,,
       6       6
       0   418.5
       6       6
       0   418.5
Pier Skew, UpSta & Num, DnSta & Num=  ,5211, 2 ,5211, 2 , 0 , 0 , 0 ,,
       6       6
       0   414.5
       6       6
       0   414.5
Pier Skew, UpSta & Num, DnSta & Num=  ,5361, 2 ,5361, 2 , 0 , 0 , 0 ,,
       6       6
       0   410.5
       6       6
       0   410.5
BR Coef= 1 , 0 , 0 ,1.05, 0 ,,,0.8,-1,0.5,1,
WSPro=,,,, 1 ,,,, 0 ,,,, 0 ,,,,-1 ,-1 ,-1 , 0 , 0 , 0 , 0 , 0
BC Design=,, 0 ,, 0 ,,,,,,
BC HTab HWMax=412
BC Use User HTab Curves=0
BC User HTab FreeFlow(D)= 0

Type RM Length L Ch R = 1 ,49896   ,1000,1115,1219
BEGIN DESCRIPTION:
This cross section corresponds to cross section 49913 of the non-georeferenced CDC model which was the source of this model.
END DESCRIPTION:
XS GIS Cut Line= 6
2529849.946138666934718.402242042525155.999916916934085.00002421
2523895.000142346933770.999996052522975.000013836933430.00002189
2520940.000146846932358.000197382515897.349771236929183.30549171
#Sta/Elev= 30
       0     410    1000     410    1060     408    2130     405    2590     406
    2990     410    3060   411.6    3123     380    3339     380    3483   380.6
    4180     380    4210     368    4245   356.5    4295   356.5    4330     368
    4360     380    4908     381    5364     381    5420     382    5480     412
    5660     410    7100     408    7700   405.3    8040     406   12310   405.2
   12830     406   12930   407.2   13650     408   13780     410   15280     410
#Mann= 3 ,0,0
       0     .07       0    4180    .056       0    4360     .07       0
Bank Sta=4180,4360
XS Rating Curve= 0 ,0
Exp/Cntr=0.5,0.3

Type RM Length L Ch R = 1 ,48781   ,1200,4573,1100
BEGIN DESCRIPTION:
This cross section corresponds to cross section 48797 of the non-georeferenced CDC model which was the source of this model.
END DESCRIPTION:
XS GIS Cut Line= 5
2530969.438167746934705.064884832530016.297282936934402.53810304
2521341.000001016931648.999974972518037.58600417 6929675.1449988
2516749.939758586928905.75098647
#Sta/Elev= 30
       0   403.8    1360     403    1445     405    2180     406    2270     400
    2380     390  2425.4   382.5  2493.7     382  3887.9   380.5  5228.2     382
    5275     368    5305     356    5355     356    5385     368  5439.2     380
    6555   383.4  6907.2     384    7000     392    7220     406    7800     406
    8000     420  8781.5     420  8856.6     410  8953.2   403.6   10105     402
   11050   407.2   11990     404   13900     404   13950     410   15450     410
#Mann= 6 ,-1,0
       0    .098       0    1445    .196       0  5228.2    .055       0
  5439.2    .196       0    6555    .154       0   10105    .098       0
Bank Sta=5228.2,5439.2
XS Rating Curve= 0 ,0
Exp/Cntr=0.5,0.3

Type RM Length L Ch R = 1 ,44208   ,1350,1634,1000
BEGIN DESCRIPTION:
This cross section corresponds to cross section 44224 of the non-georeferenced CDC model which was the source of this model.
END DESCRIPTION:
XS GIS Cut Line= 4
2531782.151871076933911.818714052530833.000045846933597.00001596
2521736.999865176930580.000144472518108.732843526929040.40053338
#Sta/Elev= 30
       0   403.9    1000   403.9    1606   391.7  1797.3   381.2  2316.4     382
    2358   371.5    2379   373.1    2392   362.5    2444   355.2  2513.7     378
  2808.1   382.4  4631.8     382    4657     386    4694     382    5854     382
    6344     384  6659.4   391.8    6970     392    7150     400  7596.6     400
    7749     420  9130.4     420  9232.1     400  9445.8     402  9587.5     404
  9824.8   399.4 11053.8   402.2 14238.8     402 14488.9     410 14524.7   419.8
#Mann= 7 ,-1,0
       0   .0845       0    1606    .196       0  2316.4    .055       0
  2513.7    .196       0  6659.4    .126       0  9445.8    .168       0
 11053.8    .098       0
Bank Sta=2316.4,2513.7
XS Rating Curve= 0 ,0
Exp/Cntr=0.3,0.1

Type RM Length L Ch R = 1 ,42574   ,1798,2337,1498
BEGIN DESCRIPTION:
This cross section corresponds to cross section 42590 of the non-georeferenced CDC model which was the source of this model.
END DESCRIPTION:
XS GIS Cut Line= 4
2532938.199104266932423.879449442531949.495516246932273.99544413
 2528459.99987066931745.000111042518057.000007336928462.00011538
#Sta/Elev= 30
    -140     408     860     408  1044.6     388    1118   384.8  1499.5   384.8
  1688.6     392  1884.9     382  2524.7     378  4028.7     382    4065     370
    4175   356.3    4196     361    4205     370  4252.6     382  4358.9     382
  4388.9   385.7  4415.5     380  6233.5   378.2    7175     384  7370.4     396
  7523.4     400  7932.2     400  7982.1   402.1    8130     420    8515     420
    9390     420    9510     400   11835     402 14590.5     403 15298.1     408
#Mann= 7 ,-1,0
    -140    .084       0  1884.9    .196       0  4028.7    .055       0
  4252.6    .196       0    7175    .112       0    8515    .154       0
   11835    .098       0
Bank Sta=4028.7,4252.6
XS Rating Curve= 0 ,0
Exp/Cntr=0.3,0.1

Type RM Length L Ch R = 1 ,40237   ,1551,2491,1601
BEGIN DESCRIPTION:
This cross section corresponds to cross section 40250 of the non-georeferenced CDC model which was the source of this model.
END DESCRIPTION:
XS GIS Cut Line= 4
 2532829.1475768 6930766.04705362531849.702408766930564.33646189
 2522495.99998766928638.000091462517894.671263756927581.77746639
#Sta/Elev= 30
      23   408.4    1023   408.4  1028.9     400  1041.5     396  1470.5     398
    1699     390  1947.9     390  2342.5     390  2485.7     380  2628.7     380
  2639.4     378    2665   360.2    2695   351.2    2765   374.8  2886.2     378
  2891.9     382  3869.4     380    6714     380  6909.4     388  6981.3     386
  7093.8     400  7227.9     402  7782.2     402  8326.5     410  8396.1     408
  8415.1     400   12386     400   13440     408   14557     406   15294     412
#Mann= 8 ,-1,0
      23     .08       0  1947.9     .12       0  2628.7    .055       0
  2891.9      .2       0  3869.4     .05       0    6714      .2       0
  8415.1     .12       0   15294      .7       0
#XS Ineff= 2 , 0
          2628.7     380  2891.9             382
Permanent Ineff=
       F       F
Bank Sta=2628.7,2891.9
XS Rating Curve= 0 ,0
Exp/Cntr=0.3,0.1

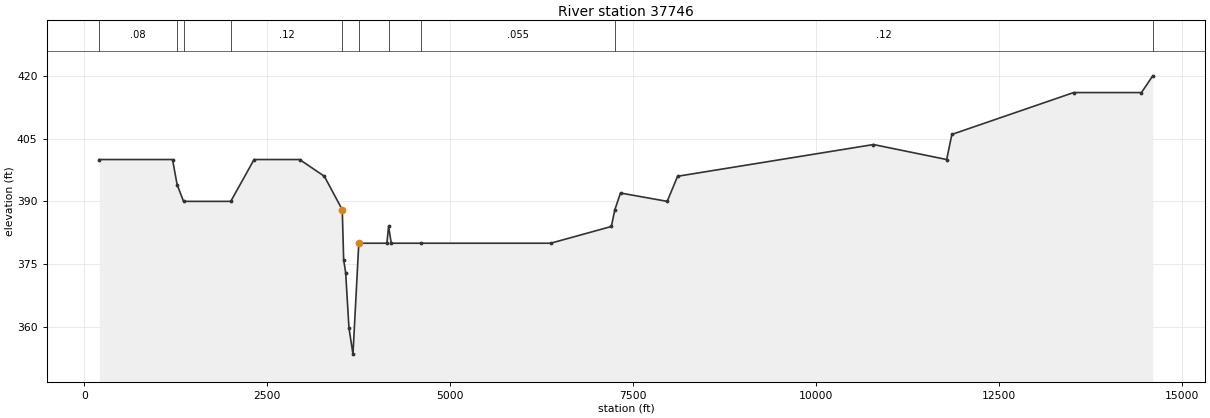
Type RM Length L Ch R = 1 ,37746   ,960,1241,1260
BEGIN DESCRIPTION:
This cross section corresponds to cross section 37760 of the non-georeferenced CDC model which was the source of this model.
END DESCRIPTION:
XS GIS Cut Line= 4
2532926.589845656929248.149480832531948.441056436929040.24338147
2522565.999847596927045.999994642518848.287794836926245.29293463
#Sta/Elev= 30
     204     400    1204     400  1266.9     394  1354.7     390  1999.9     390
  2318.6     400  2940.7     400    3279     396  3523.6     388  3542.8     376
    3570     373    3615   359.8    3670   353.5  3749.5     380  4133.3     380
  4156.8     384  4193.4     380  4599.5     380  6371.5     380    7201     384
  7248.3     388  7325.8     392  7963.8     390  8106.1     396   10783  403.58
   11783     400   11854     406   13518     416   14445     416   14599     420
#Mann= 10 ,-1,0
     204     .08       0  1266.9     .08       0  1354.7     .05       0
  1999.9     .12       0  3523.6    .055       0  3749.5      .2       0
  4156.8     .05       0  4599.5    .055       0  7248.3     .12       0
   14599       2       0
#XS Ineff= 2 , 0
          3523.6     388  3749.5             380
Permanent Ineff=
       F       F
Bank Sta=3523.6,3749.5
XS Rating Curve= 0 ,0
Exp/Cntr=0.3,0.1