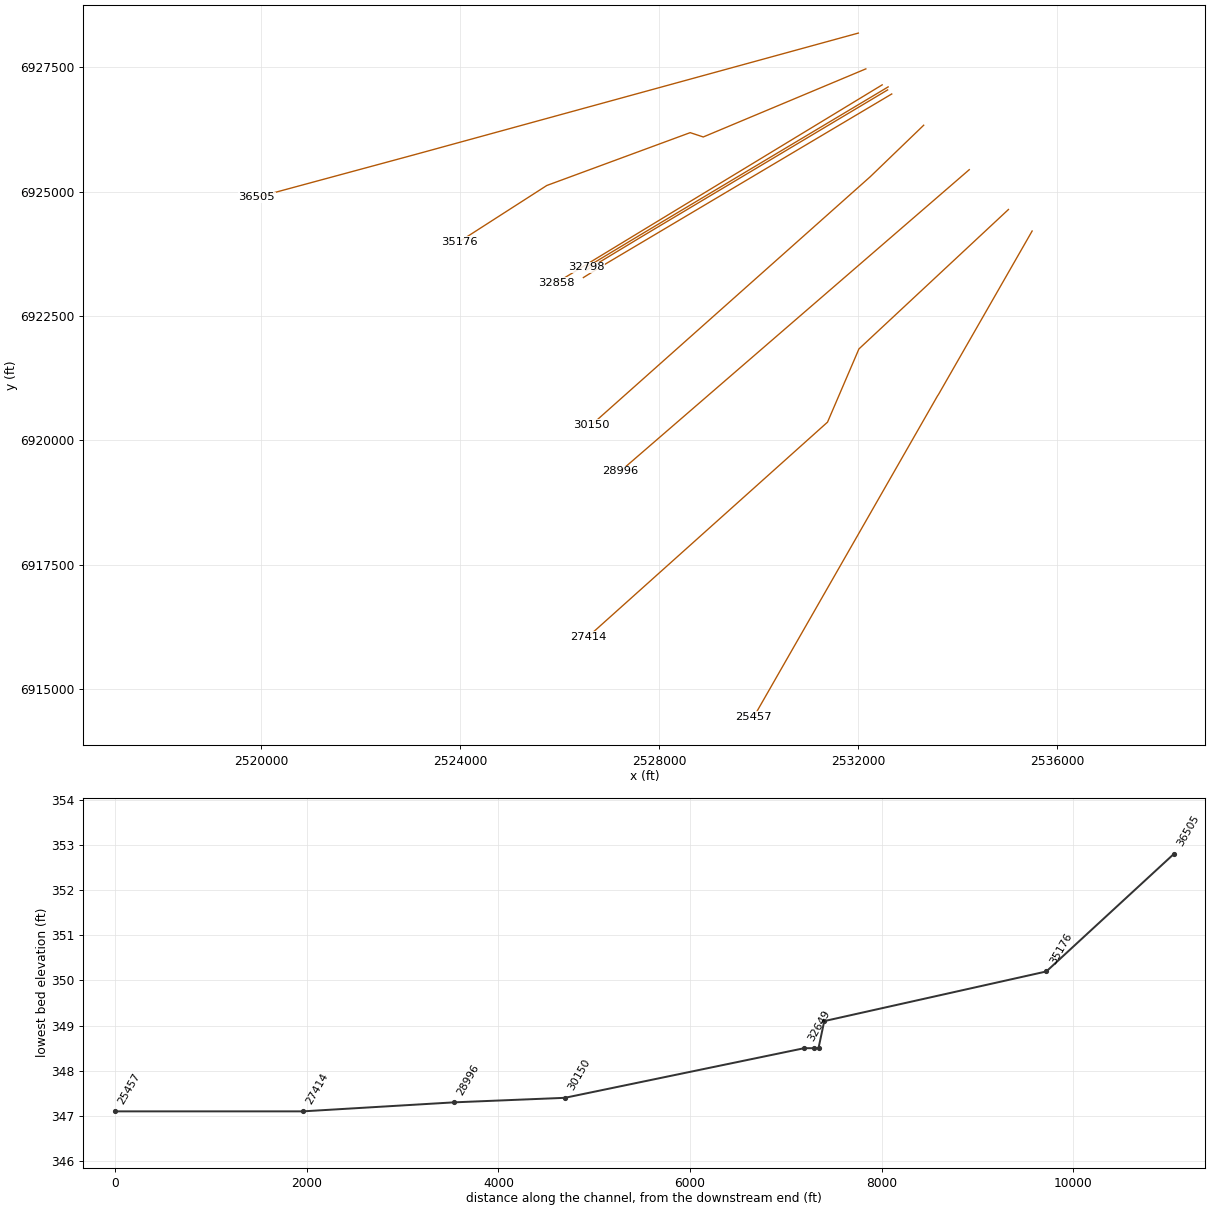
HEC-RAS study CDC_Consolidated_Model.prj: Upper Trinity CDC Consolidated Model

--- CDC_Consolidated_Model.g04 (geometry) --- (continued)

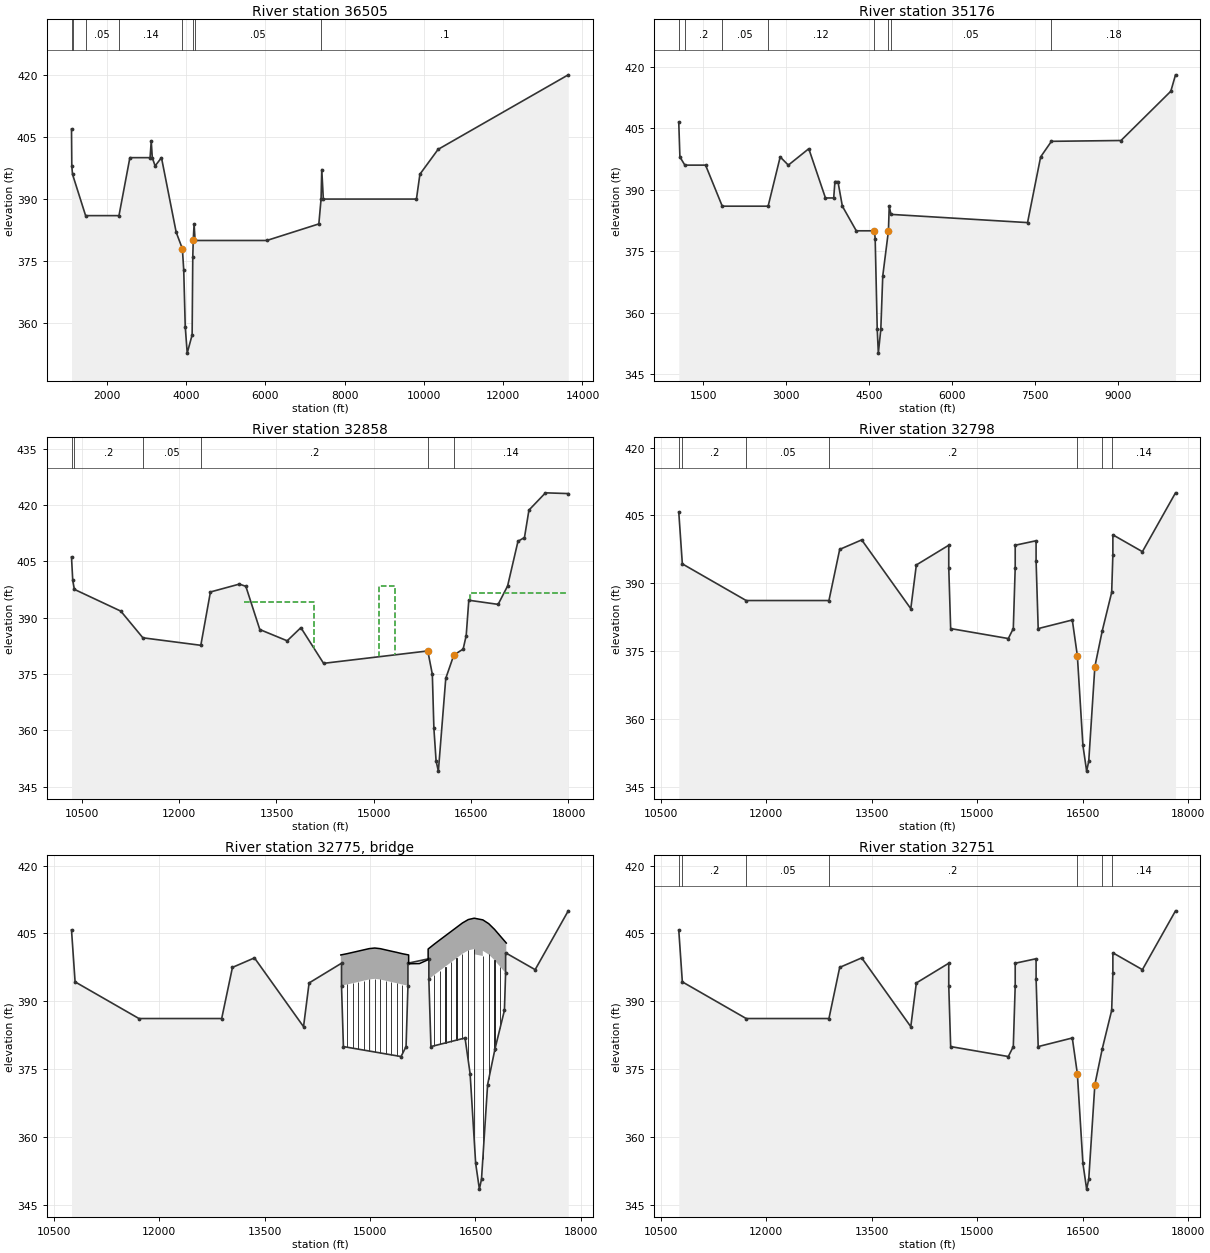
Type RM Length L Ch R = 1 ,36505   ,951,1329,1302
BEGIN DESCRIPTION:
This cross section corresponds to cross section 36519 of the non-georeferenced CDC model which was the source of this model.
END DESCRIPTION:
XS GIS Cut Line= 3
 2532005.15419766928185.576127542523073.000145916925737.99998596
 2519915.63113266924884.57649596
#Sta/Elev= 30
  1108.9   406.9  1116.4     398  1134.2     396  1464.7     386  2306.4     386
  2581.6     400  3091.6     400  3120.2     404  3147.1     400    3218     398
  3378.7     400  3749.4     382  3905.9     378    3940   372.9    3978   359.2
    4028   352.8    4152   357.2  4168.3     376  4179.8     380  4201.7     384
  4226.5     380  6035.5     380  7348.6     384  7404.8     390  7422.4  397.13
  7461.8     390  9810.8     390  9898.4     396   10357     402   13641     420
#Mann= 8 ,-1,0
  1108.9     .03       0  1134.2      .1       0  1464.7     .05       0
  2306.4     .14       0  3905.9    .055       0  4179.8      .2       0
  4226.5     .05       0  7404.8      .1       0
#XS Ineff= 2 , 0
          3905.9     378  4179.8             380
Permanent Ineff=
       F       F
Bank Sta=3905.9,4179.8
XS Rating Curve= 0 ,0
Exp/Cntr=0.3,0.1

Type RM Length L Ch R = 1 ,35176   ,849,2318,1797
BEGIN DESCRIPTION:
This cross section corresponds to cross section 35192 of the non-georeferenced CDC model which was the source of this model.
END DESCRIPTION:
XS GIS Cut Line= 5
2532155.647334936927466.298694712528888.999996846926097.99992213
2528625.999866666926185.000076222525745.000051266925123.00023171
2523980.464538346923989.68852197
#Sta/Elev= 30
  1059.7   406.5  1080.5     398  1170.1     396  1544.8     396  1846.7     386
  2676.3     386  2894.7     398  3041.7     396    3412     400  3713.4     388
  3862.6     388  3885.2     392  3939.2     392  4019.4     386  4271.3     380
  4599.5     380    4613     378    4650   356.1    4670   350.2    4715     356
    4750     369    4853     380    4867     386  4898.5     384  7369.4     382
  7605.9     398  7801.3   401.8  9060.1     402    9961     414   10046     418
#Mann= 8 ,-1,0
  1059.7     .03       0  1170.1      .2       0  1846.7     .05       0
  2676.3     .12       0  4599.5    .055       0    4853      .2       0
  4898.5     .05       0  7801.3     .18       0
#XS Ineff= 2 , 0
          4599.5     380    4853             380
Permanent Ineff=
       F       F
Bank Sta=4599.5,4853
XS Rating Curve= 0 ,0
Exp/Cntr=0.3,0.1

Type RM Length L Ch R = 1 ,32858   ,60,60,60
BEGIN DESCRIPTION:
This cross section corresponds to cross section 32870 of the non-georeferenced CDC model which was the source of this model.
END DESCRIPTION:
XS GIS Cut Line= 2
 2532484.41898716927145.076568132525940.685355426923170.92441146
#Sta/Elev= 30
   10341   406.1   10360   399.9   10385   397.5   11101   391.7   11441   384.6
   12334   382.6   12482   396.8   12928   398.9   13028   398.3   13243   386.8
   13665   383.8   13876   387.3   14226   377.8   15832   381.1   15902   374.9
   15926   360.5   15960   351.8   15995   349.1   16109   373.8   16233     380
   16377   381.6   16424   385.2   16464   394.6   16916   393.5   17062   398.4
   17222   410.3   17322   411.3   17391   418.6   17646   423.2   17997     423
#Mann= 6 ,-1,0
   10341     .03       0   10385      .2       0   11441     .05       0
   12334      .2       0   15832    .055       0   16233     .14       0
#XS Ineff= 3 ,-1
   13000   14085     394   15085   15320   398.3   16480   17997   396.6
Permanent Ineff=
       F       F       F
Bank Sta=15832,16233
XS Rating Curve= 0 ,0
Exp/Cntr=0.3,0.1

Type RM Length L Ch R = 1 ,32798   ,47,47,47
BEGIN DESCRIPTION:
This cross section corresponds to cross section 32796 of the non-georeferenced CDC model which was the source of this model.
END DESCRIPTION:
XS GIS Cut Line= 3
2532603.880034276927103.952306552527617.459232846924126.36967905
2526539.912503426923478.69938646
#Sta/Elev= 30
   10755   405.8   10806   394.3   11714   386.2   12891   386.2   13044   397.5
   13357   399.6   14055   384.4   14134  394.06   14595  398.42   14595  393.44
   14622     380   15442   377.8   15513     380   15540  393.44   15540  398.42
   15837  399.41   15837  394.95   15867     380   16352   381.9   16424     374
   16503   354.2   16556   348.5   16586   350.7   16673   371.6   16778   379.5
   16912     388   16929  396.27   16929  400.72   17349     397   17820     410
#Mann= 7 ,-1,0
   10755     .03       0   10806      .2       0   11714     .05       0
   12891      .2       0   16424    .055       0   16778      .2       0
   16912     .14       0
#XS Ineff= 1 ,-1
   13500   14134     394
Permanent Ineff=
       F
Bank Sta=16424,16673
XS Rating Curve= 0 ,0
Exp/Cntr=0.3,0.1

Type RM Length L Ch R = 3 ,32775   ,,,
BEGIN DESCRIPTION:
32772  Dowdy-Ferry Road
Bridge data revised May 2002 from bridge plans dated 12-98 supplied by TXDOT.  Bridge plans supplied in metric, therefore stationing and elevations were converted to english prior to input.  Main bridge length is 1092.2 ft. (333.0 m) and relief bridge length is 944.6 ft (288.0m).
END DESCRIPTION:
Node Name=Dowdy-Ferry Road
Bridge Culvert--1,0,-1,-1, 0
Deck Dist Width WeirC Skew NumUp NumDn MinLoCord MaxHiCord MaxSubmerge Is_Ogee
1.5,44,2.6,0, 33, 33, , , 0.95, 0, ,,,
   14585   14674   14753   14832   14910   14989   15068   15146   15225   15304
   15383   15461   15550   15550   15571   15703   15827   15827   15916   15994
   16073   16152   16231   16314   16398   16482   16482   16605   16605   16688
   16772   16851   16939
  400.25  400.53  400.81  401.09  401.37  401.65  401.78  401.64  401.36  401.08
  400.81  400.52  400.25  398.42  398.31  398.34   399.2  401.56  402.66  403.58
   404.5  405.42  406.34  407.31  408.07  408.37  408.37     408     408  407.17
  405.89  404.46  402.88
  393.44  393.72     394  394.28  394.56  394.84  394.97  394.83  394.55  394.27
     394  393.71  393.44  398.42  398.31  398.34   399.2  394.75  395.85  396.77
  397.69  398.61  399.53   400.5  401.26  401.56   400.4  400.02  401.17  400.36
  399.08  397.65  396.07
   14585   14674   14753   14832   14910   14989   15068   15146   15225   15304
   15383   15461   15550   15550   15571   15703   15827   15827   15916   15994
   16073   16152   16231   16314   16398   16482   16482   16605   16605   16688
   16772   16851   16939
  400.25  400.53  400.81  401.09  401.37  401.65  401.78  401.64  401.36  401.08
  400.81  400.52  400.25  398.42  398.31  398.34   399.2  401.56  402.66  403.58
   404.5  405.42  406.34  407.31  408.07  408.37  408.37     408     408  407.17
  405.89  404.46  402.88
  393.44  393.72     394  394.28  394.56  394.84  394.97  394.83  394.55  394.27
     394  393.71  393.44  398.42  398.31  398.34   399.2  394.75  395.85  396.77
  397.69  398.61  399.53   400.5  401.26  401.56   400.4  400.02  401.17  400.36
  399.08  397.65  396.07
Pier Skew, UpSta & Num, DnSta & Num=  ,14674, 2 ,14674, 2 , 0 , 0 , 0 ,,
     2.5     2.5
       0     396
     2.5     2.5
       0     396
Pier Skew, UpSta & Num, DnSta & Num=  ,14753, 2 ,14753, 2 , 0 , 0 , 0 ,,
     2.5     2.5
       0     396
     2.5     2.5
       0     396
Pier Skew, UpSta & Num, DnSta & Num=  ,14832, 2 ,14832, 2 , 0 , 0 , 0 ,,
     2.5     2.5
       0     396
     2.5     2.5
       0     396
Pier Skew, UpSta & Num, DnSta & Num=  ,14910, 2 ,14910, 2 , 0 , 0 , 0 ,,
     2.5     2.5
       0     396
     2.5     2.5
       0     396
Pier Skew, UpSta & Num, DnSta & Num=  ,14989, 2 ,14989, 2 , 0 , 0 , 0 ,,
     2.5     2.5
       0     396
     2.5     2.5
       0     396
Pier Skew, UpSta & Num, DnSta & Num=  ,15068, 2 ,15068, 2 , 0 , 0 , 0 ,,
     2.5     2.5
       0     396
     2.5     2.5
       0     396
Pier Skew, UpSta & Num, DnSta & Num=  ,15146, 2 ,15146, 2 , 0 , 0 , 0 ,,
     2.5     2.5
       0     396
     2.5     2.5
       0     396
Pier Skew, UpSta & Num, DnSta & Num=  ,15225, 2 ,15225, 2 , 0 , 0 , 0 ,,
     2.5     2.5
       0     396
     2.5     2.5
       0     396
Pier Skew, UpSta & Num, DnSta & Num=  ,15304, 2 ,15304, 2 , 0 , 0 , 0 ,,
     2.5     2.5
       0     396
     2.5     2.5
       0     396
Pier Skew, UpSta & Num, DnSta & Num=  ,15383, 2 ,15383, 2 , 0 , 0 , 0 ,,
     2.5     2.5
       0     396
     2.5     2.5
       0     396
Pier Skew, UpSta & Num, DnSta & Num=  ,15461, 2 ,15461, 2 , 0 , 0 , 0 ,,
     2.5     2.5
       0     396
     2.5     2.5
       0     396
Pier Skew, UpSta & Num, DnSta & Num=  ,15916, 2 ,15916, 2 , 0 , 0 , 0 ,,
     2.5     2.5
       0     400
     2.5     2.5
       0     400
Pier Skew, UpSta & Num, DnSta & Num=  ,15994, 2 ,15994, 2 , 0 , 0 , 0 ,,
     2.5     2.5
       0     400
     2.5     2.5
       0     400
Pier Skew, UpSta & Num, DnSta & Num=  ,16073, 2 ,16073, 2 , 0 , 0 , 0 ,,
     2.5     2.5
       0     400
     2.5     2.5
       0     400
Pier Skew, UpSta & Num, DnSta & Num=  ,16152, 2 ,16152, 2 , 0 , 0 , 0 ,,
     2.5     2.5
       0     401
     2.5     2.5
       0     401
Pier Skew, UpSta & Num, DnSta & Num=  ,16231, 2 ,16231, 2 , 0 , 0 , 0 ,,
     2.5     2.5
       0     401
     2.5     2.5
       0     401
Pier Skew, UpSta & Num, DnSta & Num=  ,16314, 2 ,16314, 2 , 0 , 0 , 0 ,,
     2.5     2.5
       0     402
     2.5     2.5
       0     402
Pier Skew, UpSta & Num, DnSta & Num=  ,16398, 2 ,16398, 2 , 0 , 0 , 0 ,,
     2.5     2.5
       0     403
     2.5     2.5
       0     403
Pier Skew, UpSta & Num, DnSta & Num=  ,16482, 2 ,16482, 2 , 0 , 0 , 0 ,,
     3.5     3.5
       0     403
     3.5     3.5
       0     403
Pier Skew, UpSta & Num, DnSta & Num=  ,16605, 2 ,16605, 2 , 0 , 0 , 0 ,,
     3.5     3.5
       0     403
     3.5     3.5
       0     403
Pier Skew, UpSta & Num, DnSta & Num=  ,16688, 2 ,16688, 2 , 0 , 0 , 0 ,,
     2.5     2.5
       0     403
     2.5     2.5
       0     403
Pier Skew, UpSta & Num, DnSta & Num=  ,16772, 2 ,16772, 2 , 0 , 0 , 0 ,,
     2.5     2.5
       0     403
     2.5     2.5
       0     403
Pier Skew, UpSta & Num, DnSta & Num=  ,16851, 2 ,16851, 2 , 0 , 0 , 0 ,,
     2.5     2.5
       0     403
     2.5     2.5
       0     403
BR Coef= 1 , 0 , 0 ,1.05, 0 ,,,0.8,-1,0.5,1,
WSPro=,,,, 1 ,,,, 0 ,,,, 0 ,,,,-1 ,-1 ,-1 , 0 , 0 , 0 , 0 , 0
BC Design=,, 0 ,, 0 ,,,,,,
BC HTab HWMax=410
BC Use User HTab Curves=0
BC User HTab FreeFlow(D)= 0

Type RM Length L Ch R = 1 ,32751   ,102,102,102
BEGIN DESCRIPTION:
This cross section corresponds to cross section 32748 of the non-georeferenced CDC model which was the source of this model.
END DESCRIPTION:
XS GIS Cut Line= 3
  2532593.520803 6927043.47112832527625.427064666924079.38912997
2526530.35117084 6923416.9134208
#Sta/Elev= 30
   10755   405.8   10806   394.3   11714   386.2   12891   386.2   13044   397.5
   13357   399.6   14055   384.4   14134  394.06   14595  398.42   14595  393.44
   14622     380   15442   377.8   15513     380   15540  393.44   15540  398.42
   15837  399.41   15837  394.95   15867     380   16352   381.9   16424     374
   16503   354.2   16556   348.5   16586   350.7   16673   371.6   16778   379.5
   16912     388   16929  396.27   16929  400.72   17349     397   17820     410
#Mann= 7 ,-1,0
   10755     .03       0   10806      .2       0   11714     .05       0
   12891      .2       0   16424    .055       0   16778      .2       0
   16912     .14       0
#XS Ineff= 1 ,-1
   13500   14134     394
Permanent Ineff=
       F
Bank Sta=16424,16673
XS Rating Curve= 0 ,0
Exp/Cntr=0.3,0.1

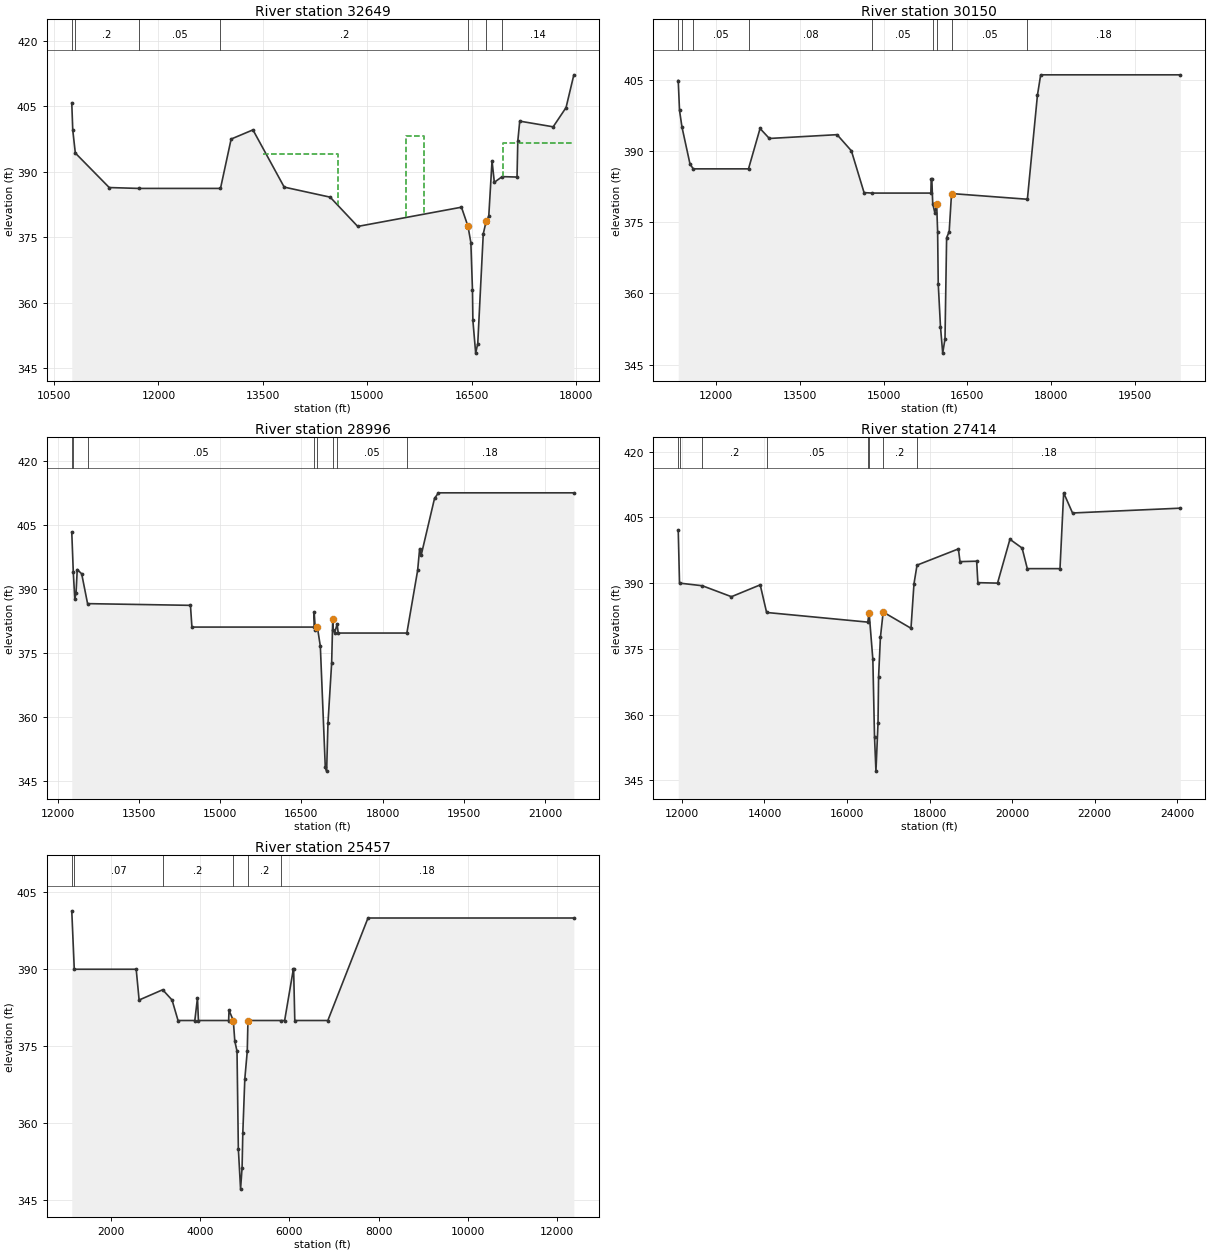
Type RM Length L Ch R = 1 ,32649   ,1449,2499,2298
BEGIN DESCRIPTION:
This cross section corresponds to cross section 32658 of the non-georeferenced CDC model which was the source of this model.
END DESCRIPTION:
XS GIS Cut Line= 3
2532676.001937276926961.907643142526802.99990377 6923473.9999208
2526480.132767356923272.92781638
#Sta/Elev= 30
   10755   405.8   10769   399.6   10806   394.3   11293   386.4   11714   386.2
   12891   386.2   13044   397.5   13357   399.6   13806   386.5   14466   384.2
   14862   377.5   16352   381.9   16446   377.5   16487   373.8   16510     363
   16516     356   16556   348.5   16586   350.7   16665   375.8   16707   378.7
   16744   379.8   16791   392.5   16824   387.6   16937   388.9   17150   388.8
   17161     397   17189   401.6   17669   400.3   17854   404.7   17966   412.2
#Mann= 7 ,-1,0
   10755     .03       0   10806      .2       0   11714     .05       0
   12891      .2       0   16446    .055       0   16707      .2       0
   16937     .14       0
#XS Ineff= 3 ,-1
   13500   14575     394   15560   15817   398.3   16950   17966   396.5
Permanent Ineff=
       F       F       F
Bank Sta=16446,16707
XS Rating Curve= 0 ,0
Exp/Cntr=0.3,0.1

Type RM Length L Ch R = 1 ,30150   ,1200,1154,1130
BEGIN DESCRIPTION:
This cross section corresponds to cross section 30157 of the non-georeferenced CDC model which was the source of this model.
END DESCRIPTION:
XS GIS Cut Line= 4
2533318.201440246926333.938426632532243.99984851 6925299.0002078
2528511.396421346921976.166630392526644.106699696920313.87029838
#Sta/Elev= 30
   11325   404.8   11348   398.5   11392     395   11536   387.2   11594   386.2
   12583   386.2   12790   394.7   12956   392.6   14169   393.4   14425     390
   14652   381.2   14798   381.1   15848   381.1   15854   384.1   15865   384.1
   15881   378.9   15918     377   15952   378.7   15969     373   15980     362
   16020     353   16060   347.4   16101   350.4   16130   371.7   16176     373
   16218     381   17576   379.8   17756   401.7   17814     406   20314     406
#Mann= 9 ,-1,0
   11325     .03       0   11392      .2       0   11594     .05       0
   12583     .08       0   14798     .05       0   15881      .2       0
   15952    .055       0   16218     .05       0   17576     .18       0
#XS Ineff= 2 , 0
           15952   378.7   16218             381
Permanent Ineff=
       F       F
Bank Sta=15952,16218
XS Rating Curve= 0 ,0
Exp/Cntr=0.3,0.1

Type RM Length L Ch R = 1 ,28996   ,1245,1582,1992
BEGIN DESCRIPTION:
This cross section corresponds to cross section 29003 of the non-georeferenced CDC model which was the source of this model.
END DESCRIPTION:
XS GIS Cut Line= 3
 2534234.07690516925440.849333552529110.048767336921011.64362505
2527218.705116846919376.76772892
#Sta/Elev= 30
   12258   403.4   12286     394   12314   387.7   12337   389.1   12359   394.6
   12441   393.6   12550   386.6   14450   386.2   14477   381.1   16733   381.1
   16735   384.6   16756   380.5   16794   381.1   16849   376.6   16940   348.3
   16965   347.3   16990   358.6   17058   372.7   17078     383   17082   380.5
   17115   379.8   17159   381.8   17179   379.7   18447   379.7   18646   394.4
   18683   399.5   18712     398   18958   411.3   19031   412.6   21531   412.6
#Mann= 8 ,-1,0
   12258     .03       0   12286     .16       0   12550     .05       0
   16733      .2       0   16794    .055       0   17078      .2       0
   17159     .05       0   18447     .18       0
#XS Ineff= 2 , 0
           16794   381.1   17078             383
Permanent Ineff=
       F       F
Bank Sta=16794,17078
XS Rating Curve= 0 ,0
Exp/Cntr=0.3,0.1

Type RM Length L Ch R = 1 ,27414   ,1300,1957,1999
BEGIN DESCRIPTION:
This cross section corresponds to cross section 27415 of the non-georeferenced CDC model which was the source of this model.
END DESCRIPTION:
XS GIS Cut Line= 5
2535021.79120892 6924641.00742932532016.999974436921839.00023805
2531385.99992409 6920368.00022732528440.778124246917728.59376071
2526578.997260126916060.12979226
#Sta/Elev= 30
   11911   402.1   11942     390   12494   389.4   13200   386.9   13897   389.6
   14052   383.3   16503   381.1   16536   383.2   16626   372.6   16666     355
   16701   347.1   16751     358   16765   368.6   16809   377.6   16876   383.4
   17550   379.7   17622   389.8   17696   394.1   18698   397.8   18738   394.9
   19141     395   19170   390.1   19647     390   19947     400   20242     398
   20368   393.3   21160   393.3   21249   410.6   21464     406   24075   407.1
#Mann= 8 ,-1,0
   11911     .03       0   11942     .08       0   12494      .2       0
   14052     .05       0   16503      .2       0   16536    .055       0
   16876      .2       0   17696     .18       0
#XS Ineff= 2 , 0
           16536   383.2   16876           383.4
Permanent Ineff=
       F       F
Bank Sta=16536,16876
XS Rating Curve= 0 ,0
Exp/Cntr=0.3,0.1

Type RM Length L Ch R = 1 ,25457   ,0,0,0
BEGIN DESCRIPTION:
This cross section corresponds to cross section 25457 of the non-georeferenced CDC model which was the source of this model.
END DESCRIPTION:
XS GIS Cut Line= 5
2535497.477593516924208.306194962533614.000061246920921.00010554
2533600.635914746920903.282293222531145.627045246916614.24133064
2529903.705690966914444.53366605
#Sta/Elev= 30
  1121.7   401.4  1177.8     390  2565.6     390  2631.2     384  3159.1     386
  3369.4     384  3503.5     380  3879.8     380  3938.8  384.42  3960.6     380
  4637.8     380  4645.8     382  4742.3     380  4775.5     376  4825.3     374
    4855     355    4905   347.1    4939  351.31    4955     358    5000   368.6
  5054.8     374  5070.4     380    5800     380  5892.7     380  6087.4     390
  6094.1     390  6120.1     380    6861     380  7760.7     400 12374.5     400
#Mann= 6 ,-1,0
  1121.7     .03       0  1177.8     .07       0  3159.1      .2       0
  4742.3    .055       0  5070.4      .2       0    5800     .18       0
#XS Ineff= 2 , 0
          4742.3     380  5070.4             380
Permanent Ineff=
       F       F
Bank Sta=4742.3,5070.4
XS Rating Curve= 0 ,0
Exp/Cntr=0.3,0.1
Stream Node=Elm Fork        ,ef6             , 0 , 0 ,Upstream end
Stream Node=Elm Fork        ,ef6             , 0 , 1 ,Downstream end
Stream Node=Elm Fork        ,ef5             , 0 , 0 ,Upstream end
Stream Node=Elm Fork        ,ef5             , 0 , 1 ,Downstream end
Stream Node=Elm Fork        ,ef4             , 0 , 0 ,Upstream end
Stream Node=Elm Fork        ,ef4             , 0 , 1 ,Downstream end
Stream Node=Elm Fork        ,ef3             , 0 , 0 ,Upstream end
Stream Node=Elm Fork        ,ef3             , 0 , 1 ,Downstream end
Stream Node=Elm Fork        ,PGBT split west , 0 , 0 ,Upstream end
Stream Node=Elm Fork        ,PGBT split west , 0 , 1 ,Downstream end
Stream Node=Elm Fork        ,PGBT split east , 0 , 0 ,Upstream end
Stream Node=Elm Fork        ,PGBT split east , 0 , 1 ,Downstream end
Stream Node=Elm Fork        ,ef3 ds          , 0 , 0 ,Upstream end
Stream Node=Elm Fork        ,ef3 ds          , 0 , 1 ,Downstream end
Stream Node=Elm Fork        ,ef2             , 0 , 0 ,Upstream end
Stream Node=Elm Fork        ,ef2             , 0 , 1 ,Downstream end
Stream Node=Elm Fork        ,ef1             , 0 , 0 ,Upstream end
Stream Node=Elm Fork        ,ef1             , 0 , 1 ,Downstream end
Stream Node=Elm Fork L-Spill,efl             , 0 , 0 ,Upstream end
Stream Node=Elm Fork L-Spill,efl             , 0 , 1 ,Downstream end
Stream Node=Elm Fork Split1 ,efs1b           , 0 , 0 ,Upstream end
Stream Node=Elm Fork Split1 ,efs1b           , 0 , 1 ,Downstream end
Stream Node=Elm Fork Split1 ,efs1a           , 0 , 0 ,Upstream end
Stream Node=Elm Fork Split1 ,efs1a           , 0 , 1 ,Downstream end
Stream Node=Elm Fork Split2 ,efs2            , 0 , 0 ,Upstream end
Stream Node=Elm Fork Split2 ,efs2            , 0 , 1 ,Downstream end
Stream Node=Main Stem       ,ms              , 0 , 0 ,Upstream end
Stream Node=Main Stem       ,ms              , 0 , 1 ,Downstream end
Stream Node=West Fork       ,wf              , 0 , 0 ,Upstream end
Stream Node=West Fork       ,wf              , 0 , 1 ,Downstream end
LCMann Table=0

Chan Stop Cuts=-1
Use User Specified Reach Order=0
User Specified Reach Order=Main Stem       ,ms
User Specified Reach Order=West Fork       ,wf1
User Specified Reach Order=West Fork       ,wf2
User Specified Reach Order=West Fork       ,wf
User Specified Reach Order=West Fork       ,wf4
User Specified Reach Order=West Fork Split1,wfs1a
User Specified Reach Order=West Fork Split1,wfs1b
User Specified Reach Order=Clear Fork      ,cf
User Specified Reach Order=Elm Fork Split1 ,efs1a
User Specified Reach Order=Elm Fork Split1 ,efs1b
User Specified Reach Order=Elm Fork Split2 ,efs2
User Specified Reach Order=Elm Fork        ,ef1
User Specified Reach Order=Elm Fork        ,ef2
User Specified Reach Order=Elm Fork        ,ef3
User Specified Reach Order=Elm Fork        ,ef4
User Specified Reach Order=Elm Fork        ,ef5
User Specified Reach Order=Elm Fork        ,ef6
User Specified Reach Order=Elm Fork L-Spill,efl
Composite Channel Slope=5

--- CDC_Consolidated_Model.g12 (geometry) ---

Geom Title=CDC: 50% to 1% AEP [WF/EF/TRMS]
Program Version=6.10
BEGIN GEOM DESCRIPTION:
CDC: Geometry file for use with 50%, 20%, 10%, 4%, 2%, 1% AEP peak flows for the WF/EF/TRMS
END GEOM DESCRIPTION:

Junct Name=ef-wf
Junct Desc=, 0 , 0 , 0 ,0
Up River,Reach=Elm Fork        ,ef1
Up River,Reach=West Fork       ,wf1
Dn River,Reach=Main Stem       ,ms
Junc L&A=3087.05,20
Junc L&A=1493.66,0

Junct Name=ef3-ef2-efs1
Junct Desc=, 0 , 0 ,-1 ,0
Up River,Reach=Elm Fork        ,ef3
Dn River,Reach=Elm Fork        ,ef2
Dn River,Reach=Elm Fork Split1 ,efs1
Junc L&A=1005.41,
Junc L&A=4530.96,

Junct Name=ef2-efs1-ef1
Junct Desc=, 0 , 0 ,-1 ,0
Up River,Reach=Elm Fork        ,ef2
Up River,Reach=Elm Fork Split1 ,efs1
Dn River,Reach=Elm Fork        ,ef1
Junc L&A=275.06,
Junc L&A=3070.88,

Junct Name=wf3gwf3ewf3f
Junct Desc=, 0 , 0 ,-1 ,0
Up River,Reach=West Fork       ,wf3
Dn River,Reach=West Fork       ,wf3f
Dn River,Reach=West Fork       ,wf3e
Junc L&A=2092.96,0
Junc L&A=105.33,0

Junct Name=wf3ewf3fwf3d
Junct Desc=, 0 , 0 ,-1 ,0
Up River,Reach=West Fork       ,wf3f
Up River,Reach=West Fork       ,wf3e
Dn River,Reach=West Fork       ,wf3d
Junc L&A=1330.22,0
Junc L&A=268.91,0

Junct Name=wf3dwf3bwf3c
Junct Desc=, 0 , 0 ,-1 ,0
Up River,Reach=West Fork       ,wf3d
Dn River,Reach=West Fork       ,wf3b
Dn River,Reach=West Fork       ,wf3c
Junc L&A=1252.4,0
Junc L&A=1233.08,0

Junct Name=wf3bwf3cwf3a
Junct Desc=, 0 , 0 ,-1 ,0
Up River,Reach=West Fork       ,wf3b
Up River,Reach=West Fork       ,wf3c
Dn River,Reach=West Fork       ,wf3a
Junc L&A=3233.81,0
Junc L&A=2784.71,0

Junct Name=wf3a-wf2-wfs
Junct Desc=, 0 , 0 ,-1 ,0
Up River,Reach=West Fork       ,wf3a
Dn River,Reach=West Fork       ,wf2
Dn River,Reach=West Fork Split ,wfs
Junc L&A=734.46,0
Junc L&A=1237.76,0

Junct Name=wfs-wf2-wf1
Junct Desc=, 0 , 0 ,-1 ,0
Up River,Reach=West Fork       ,wf2
Up River,Reach=West Fork Split ,wfs
Dn River,Reach=West Fork       ,wf1
Junc L&A=521.04,0
Junc L&A=4005.92,0

Junct Name=Junction3
Junct Desc=, 0 , 0 ,-1 ,0
Up River,Reach=Elm Fork L-Spill,efl1
Up River,Reach=Elm Fork        ,ef6
Dn River,Reach=Elm Fork        ,ef5
Junc L&A=134.62,0
Junc L&A=622.82,0

Junct Name=Junction 1
Junct Desc=, 0 , 0 ,-1 ,0
Up River,Reach=L-Overflow      ,efs3
Up River,Reach=Elm Fork        ,ef5
Dn River,Reach=Elm Fork        ,ef4
Junc L&A=642.67,0
Junc L&A=1132.05,0

Junct Name=Junction 4
Junct Desc=, 0 , 0 ,-1 ,0
Up River,Reach=Elm Fork L-Spill,efl2
Dn River,Reach=Elm Fork L-Spill,efl1
Dn River,Reach=L-Overflow      ,efs3
Junc L&A=1205.71,0
Junc L&A=1079.88,0

Junct Name=ef4-efs2-ef3
Junct Desc=, 0 , 0 ,-1 ,0
Up River,Reach=Elm Fork Split2 ,efs2
Up River,Reach=Elm Fork        ,ef4
Dn River,Reach=Elm Fork        ,ef3
Junc L&A=971.19,
Junc L&A=264.08,

River Reach=Elm Fork L-Spill,efl2
Reach XY= 30
2451740.398205247074594.431797062451498.275683157072448.15927072
 2451151.7607956 7070662.9803957 2450845.2256476 7070288.5024702
 2449714.2508754 7069831.4843553 2449387.4975919 7069340.5207703
 2448346.9914708 7068965.4788695 2447272.2747882 7069420.9736934
 2446497.7655105 7069465.5159272 2446113.5116858 7069771.9893956
 2445393.7447526 7069849.5164715 2444567.2352508 7069785.0051176
 2443355.4788161 7069500.9777985 2442726.4810583 7069038.0151417
 2442454.7699876 7069151.4909647 2442326.5251653 7069042.0052912
 2441886.4810979 7069033.5171192 2441561.2609478 7069254.4809161
 2441534.7278644 7069148.0188587 2440898.2570245  7068922.500609
 2440879.5152641 7068708.4961157 2440653.7394689 7068824.9784943
 2440507.4838559 7068577.0196727 2440550.7505016 7068495.4932609
 2440889.7593381 7068556.5220102 2440984.7332295 7068354.0066672
 2441218.2471981 7068389.5200477 2441162.5150261 7068102.5084826
  2440921.991229 7067994.9791701  2441132.601191 7067821.9862019

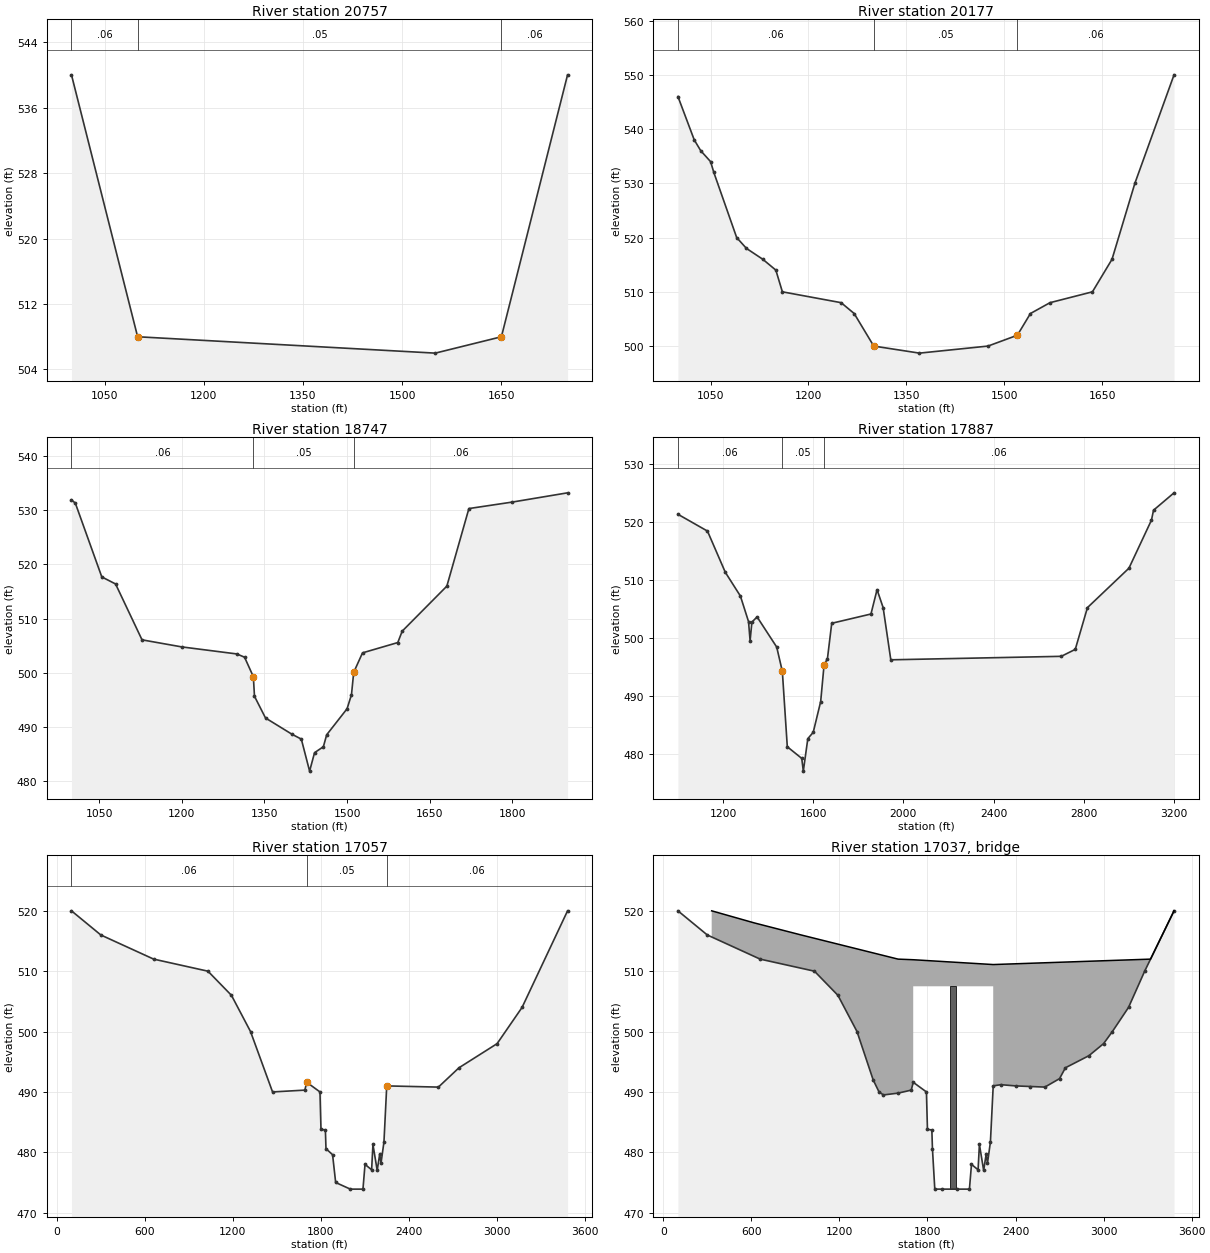
Type RM Length L Ch R = 1 ,20757   ,580,580,580
BEGIN DESCRIPTION:
15590
Cross-section surveyed December 1990.
END DESCRIPTION:
XS GIS Cut Line= 2
2452120.868883627074470.158571182451373.760863037074518.00828429
#Sta/Elev= 5
    1000     540    1100     508    1550     506    1650     508    1750     540
#Mann= 3 ,-1,0
    1000     .06       0    1100     .05       0    1650     .06       0
Bank Sta=1100,1650
XS Rating Curve= 0 ,0
Exp/Cntr=0.3,0.1

Type RM Length L Ch R = 1 ,20177   ,1430,1430,1430
BEGIN DESCRIPTION:
15010
Cross-section surveyed December 1990.
END DESCRIPTION:
XS GIS Cut Line= 2
2452072.513160077073925.240004622451317.245406937073990.14582716
#Sta/Elev= 22
    1000     546    1025     538    1035     536    1050     534    1055     532
    1090     520    1105     518    1130     516    1150     514    1160     510
    1250     508    1270     506    1300     500    1370   498.7    1475     500
    1520     502    1540     506    1570     508    1635     510    1665     516
    1700     530    1760     550
#Mann= 3 ,0,0
    1000     .06       0    1300     .05       0    1520     .06       0
Bank Sta=1300,1520
XS Rating Curve= 0 ,0
Exp/Cntr=0.3,0.1

Type RM Length L Ch R = 1 ,18747   ,850,860,870
BEGIN DESCRIPTION:
13580
Cross-section surveyed December 1990.
END DESCRIPTION:
XS GIS Cut Line= 2
2451926.207545137072464.820604362451032.287904787072596.40731541
#Sta/Elev= 27
    1000   531.9    1007   531.3    1055   517.7    1080   516.4    1128   506.1
    1200   504.8    1300   503.5    1314   502.9    1330   499.3    1332   495.7
    1352   491.7    1400   488.7    1417   487.8    1432   481.9    1441   485.3
    1457   486.4    1463   488.6    1500   493.4    1508     496    1512   500.1
    1528   503.7    1592   505.6    1600   507.7    1681     516    1721   530.3
    1800   531.5    1900   533.2
#Mann= 3 ,-1,0
    1000     .06       0    1330     .05       0    1512     .06       0
Bank Sta=1330,1512
XS Rating Curve= 0 ,0
Exp/Cntr=0.3,0.1

Type RM Length L Ch R = 1 ,17887   ,820,830,840
BEGIN DESCRIPTION:
12720
Cross-section surveyed December 1990.
END DESCRIPTION:
XS GIS Cut Line= 2
2451898.447547427071579.779564592449727.052757157071951.51291184
#Sta/Elev= 30
    1000   521.3    1131   518.4    1210   511.3    1277   507.2    1313   502.8
    1320   499.5    1328   502.7    1351   503.6    1438   498.4    1463   494.2
    1485   481.2    1549   479.2    1556     477    1576   482.6    1600   483.7
    1633     489    1648   495.3    1663   496.4    1682   502.5    1856   504.1
    1883   508.3    1910   505.2    1944   496.2    2700   496.8    2762     498
    2816   505.2    3000     512    3100   520.3    3109     522    3200     525
#Mann= 3 ,-1,0
    1000     .06       0    1463     .05       0    1648     .06       0
Bank Sta=1463,1648
XS Rating Curve= 0 ,0
Exp/Cntr=0.5,0.3

Type RM Length L Ch R = 1 ,17057   ,20,20,20
BEGIN DESCRIPTION:
11890
Cross-section surveyed December 1990.
END DESCRIPTION:
XS GIS Cut Line= 2
2453005.220931317070476.516030742449684.912676077071167.76417064
#Sta/Elev= 30
     100     520     300     516     660     512    1030     510    1190     506
    1320     500    1470     490    1690   490.3    1703   491.6    1793     490
    1800   483.8    1830   483.7    1834   480.6    1879   479.6    1900     475
    2000   473.9    2086   473.9    2100     478    2145   477.1    2154   481.3
    2183     477    2200   479.7    2209   478.2    2229   481.7    2248     491
    2600   490.8    2740     494    3000     498    3170     504    3480     520
#Mann= 3 ,-1,0
     100     .06       0    1703     .05       0    2248     .06       0
#XS Ineff= 2 , 0
            1703            2248
Permanent Ineff=
       F       F
Bank Sta=1703,2248
XS Rating Curve= 0 ,0
Exp/Cntr=0.5,0.3

Type RM Length L Ch R = 3 ,17037   ,,,
BEGIN DESCRIPTION:
Atchinson, Topeka, and Sante Fe Railroad
END DESCRIPTION:
Node Name=ATSF Railroad
Bridge Culvert--1,0,-1,-1, 0
Deck Dist Width WeirC Skew NumUp NumDn MinLoCord MaxHiCord MaxSubmerge Is_Ogee
1,18,2.7,0, 10, 10, 511.1, , 0.95, 0, 0,0,,
     330     620     940    1600    1703    1703    2248    2248    3320    3480
     520     518     516     512   511.9   511.9   511.1   511.1     512     520
   473.9   473.9   473.9   473.9   473.9   507.5   507.5   473.9   473.9   473.9
     330     620     940    1600    1703    1703    2248    2248    3320    3480
     520     518     516     512   511.9   511.9   511.1   511.1     512     520
   473.9   473.9   473.9   473.9   473.9   507.5   507.5   473.9   473.9   473.9
Pier Skew, UpSta & Num, DnSta & Num=  ,1975.5, 2 ,1975.5, 2 , 0 , 0 , 0 ,,
      38      38
   473.9   507.5
      38      38
   473.9   507.5
Abutment Skew #Up #Dn= , 2 , 2
    1703    1898
   507.5   473.9
    1703    1898
   507.5   473.9
Abutment Skew #Up #Dn= , 2 , 2
    2053    2248
   473.9   507.5
    2053    2248
   473.9   507.5
BR Coef= 0 , 0 ,-1 ,1.05, 0 ,,,0.7905694,0,2,2,507.5
WSPro=,,,, 1 ,,,, 0 ,,,, 0 ,,,,-1 ,-1 ,-1 , 0 , 0 , 0 , 0 , 0
BR U #Sta/Elev= 40
     100     520     300     516     660     512    1030     510    1190     506
    1320     500    1430     492    1470     490    1500   489.5    1600   489.8
    1690   490.3    1703   491.6    1793     490    1800   483.8    1830   483.7
    1834   480.6    1850   473.9    1900   473.9    2000   473.9    2086   473.9
    2100     478    2145   477.1    2154   481.3    2183     477    2200   479.7
    2209   478.2    2229   481.7    2248     491    2300   491.2    2400     491
    2500   490.9    2600   490.8    2700   492.2    2740     494    2900     496
    3000     498    3060     500    3170     504    3280     510    3480     520
BR U #Mann= 3
     100     .06    1703     .05    2248     .06
BR D #Sta/Elev= 40
     100     520     300     516     660     512    1030     510    1190     506
    1320     500    1430     492    1470     490    1500   489.5    1600   489.8
    1690   490.3    1703   491.6    1793     490    1800   483.8    1830   483.7
    1834   480.6    1850   473.9    1900   473.9    2000   473.9    2086   473.9
    2100     478    2145   477.1    2154   481.3    2183     477    2200   479.7
    2209   478.2    2229   481.7    2248     491    2300   491.2    2400     491
    2500   490.9    2600   490.8    2700   492.2    2740     494    2900     496
    3000     498    3060     500    3170     504    3280     510    3480     520
BR D #Mann= 3
     100     .06    1703     .05    2248     .06
BC Design=,, 0 ,, 0 ,,,,,,
BC HTab HWMax=520
BC Use User HTab Curves=0
BC User HTab FreeFlow(D)= 0

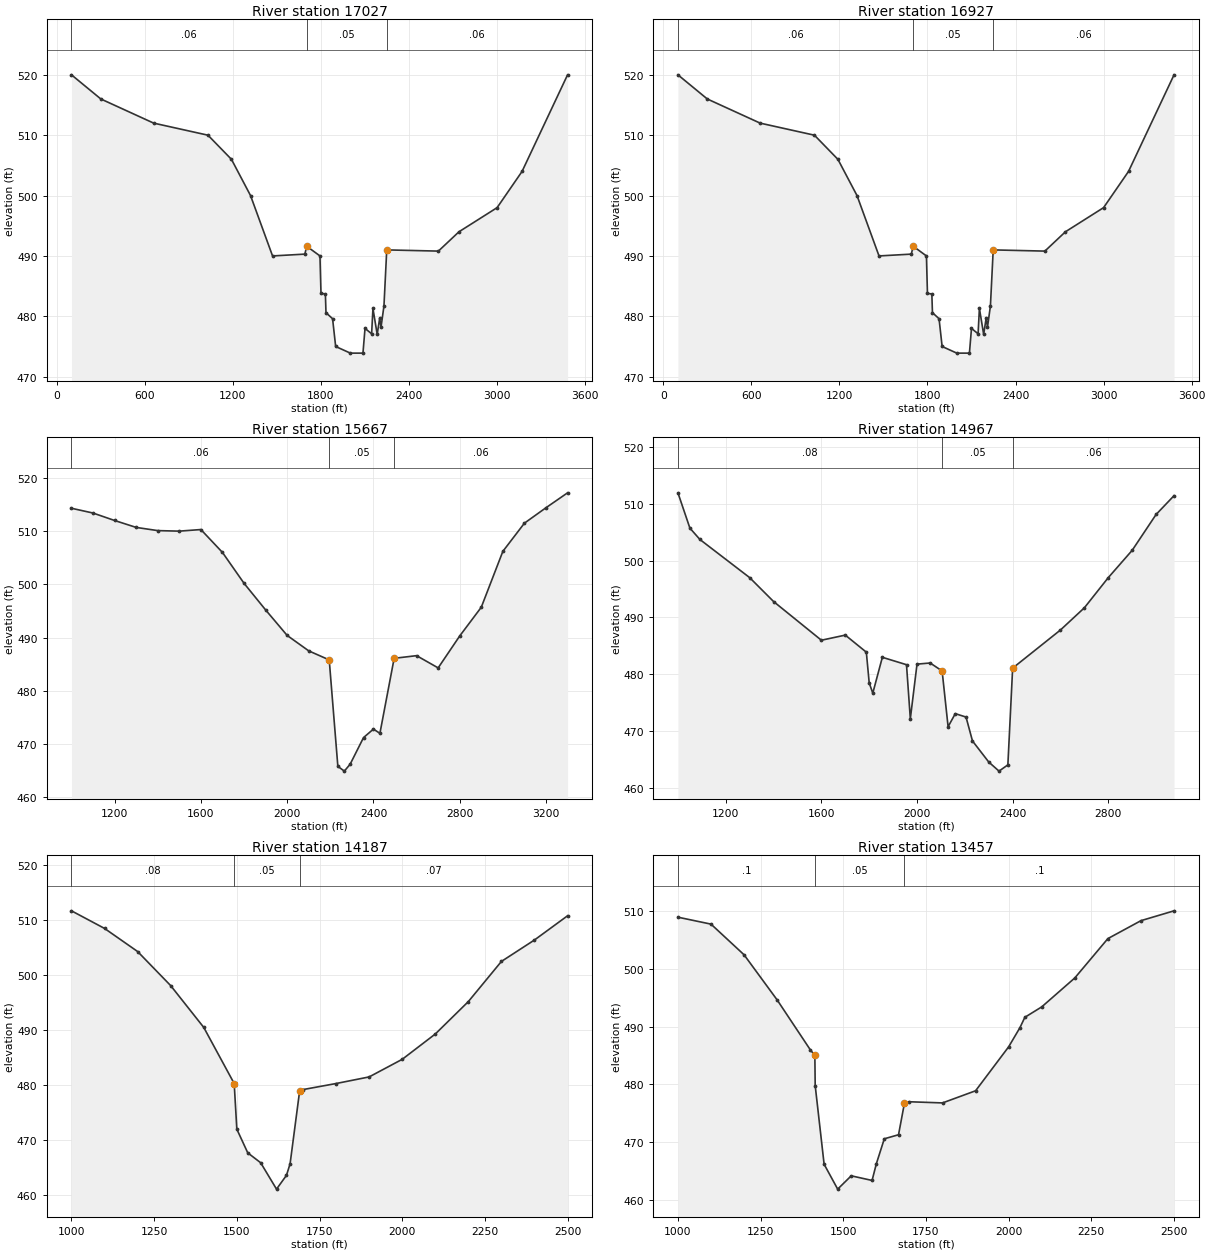
Type RM Length L Ch R = 1 ,17027   ,100,100,100
BEGIN DESCRIPTION:
11870
Cross-section surveyed December 1990.
END DESCRIPTION:
XS GIS Cut Line= 2
2453002.391998887070466.669530612449681.868435297071151.76130327
#Sta/Elev= 30
     100     520     300     516     660     512    1030     510    1190     506
    1320     500    1470     490    1690   490.3    1703   491.6    1793     490
    1800   483.8    1830   483.7    1834   480.6    1879   479.6    1900     475
    2000   473.9    2086   473.9    2100     478    2145   477.1    2154   481.3
    2183     477    2200   479.7    2209   478.2    2229   481.7    2248     491
    2600   490.8    2740     494    3000     498    3170     504    3480     520
#Mann= 3 ,0,0
     100     .06       0    1703     .05       0    2248     .06       0
#XS Ineff= 2 , 0
            1703            2248
Permanent Ineff=
       F       F
Bank Sta=1703,2248
XS Rating Curve= 0 ,0
Exp/Cntr=0.5,0.3

Type RM Length L Ch R = 1 ,16927   ,1300,1260,1200
BEGIN DESCRIPTION:
11770
Cross-section surveyed December 1990.
END DESCRIPTION:
XS GIS Cut Line= 3
2453034.299441227070134.149864012450996.779024987070782.72190619
2449803.759637757071063.48323213
#Sta/Elev= 30
     100     520     300     516     660     512    1030     510    1190     506
    1320     500    1470     490    1690   490.3    1703   491.6    1793     490
    1800   483.8    1830   483.7    1834   480.6    1879   479.6    1900     475
    2000   473.9    2086   473.9    2100     478    2145   477.1    2154   481.3
    2183     477    2200   479.7    2209   478.2    2229   481.7    2248     491
    2600   490.8    2740     494    3000     498    3170     504    3480     520
#Mann= 3 ,0,0
     100     .06       0    1703     .05       0    2248     .06       0
Bank Sta=1703,2248
XS Rating Curve= 0 ,0
Exp/Cntr=0.5,0.3

Type RM Length L Ch R = 1 ,15667   ,850,700,720
BEGIN DESCRIPTION:
10510
Cross-section surveyed December 1990.
END DESCRIPTION:
XS GIS Cut Line= 3
2450467.569171527068821.282054892450178.183611567070348.32479818
 2449800.80935827070998.57737448
#Sta/Elev= 28
    1000   514.3    1100   513.4    1200     512    1300   510.7    1400   510.1
    1500     510    1600   510.3    1700     506    1800   500.2    1900   495.2
    2000   490.4    2100   487.5    2195   485.8    2235   465.8    2265   464.9
    2292   466.2    2354   471.2    2400   472.8    2430     472    2496   486.1
    2600   486.6    2700   484.3    2800   490.3    2900   495.7    3000   506.2
    3100   511.5    3200   514.4    3300   517.2
#Mann= 3 ,0,0
    1000     .06       0    2195     .05       0    2496     .06       0
Bank Sta=2195,2496
XS Rating Curve= 0 ,0
Exp/Cntr=0.3,0.1

Type RM Length L Ch R = 1 ,14967   ,900,780,500
BEGIN DESCRIPTION:
9810
Cross-section surveyed December 1990.
END DESCRIPTION:
XS GIS Cut Line= 5
2450258.700186657068643.290745942449750.048614747069611.26457518
 2449619.93817767069699.869565582449489.827740477069788.47455597
2449091.737719527070315.60450099
#Sta/Elev= 30
    1000   511.9    1050   505.7    1092   503.7    1300     497    1400   492.8
    1600     486    1700   486.9    1788   483.9    1800   478.5    1815   476.7
    1855     483    1956   481.7    1972   472.2    2000   481.8    2055     482
    2105   480.6    2130   470.8    2160   473.1    2205   472.5    2232   468.3
    2300   464.6    2343     463    2380   464.1    2400   481.1    2600   487.8
    2700   491.7    2800     497    2900   501.8    3000   508.1    3075   511.4
#Mann= 3 ,0,0
    1000     .08       0    2105     .05       0    2400     .06       0
Bank Sta=2105,2400
XS Rating Curve= 0 ,0
Exp/Cntr=0.3,0.1

Type RM Length L Ch R = 1 ,14187   ,800,730,550
BEGIN DESCRIPTION:
9030
Cross-section surveyed December 1990.
END DESCRIPTION:
XS GIS Cut Line= 2
2449192.25447184 7068616.56966822448790.615445067070066.38859415
#Sta/Elev= 22
    1000   511.6    1100   508.4    1200   504.2    1300     498    1400   490.4
    1492   480.2    1500   471.9    1533   467.6    1572   465.8    1620     461
    1650   463.5    1661   465.6    1690   478.9    1700   479.1    1800   480.2
    1900   481.4    2000   484.6    2100   489.2    2200   495.1    2300   502.4
    2400   506.3    2500   510.7
#Mann= 3 ,0,0
    1000     .08       0    1492     .05       0    1690     .07       0
Bank Sta=1492,1690
XS Rating Curve= 0 ,0
Exp/Cntr=0.3,0.1

Type RM Length L Ch R = 1 ,13457   ,910,920,980
BEGIN DESCRIPTION:
8300
Cross-section surveyed December 1990.
END DESCRIPTION:
XS GIS Cut Line= 2
2448104.407189687068523.305319532448650.20615191 7069921.7307687
#Sta/Elev= 26
    1000   508.9    1100   507.7    1200   502.4    1300   494.6    1400     486
    1414     485    1415   479.8    1442   466.2    1483   461.9    1524   464.2
    1587   463.4    1600   466.3    1624   470.6    1667   471.3    1685   476.8
    1700     477    1800   476.8    1900   478.9    2000   486.5    2034   489.8
    2049   491.6    2100   493.4    2200   498.4    2300   505.2    2400   508.3
    2500     510
#Mann= 3 ,0,0
    1000      .1       0    1414     .05       0    1685      .1       0
Bank Sta=1414,1685
XS Rating Curve= 0 ,0
Exp/Cntr=0.3,0.1