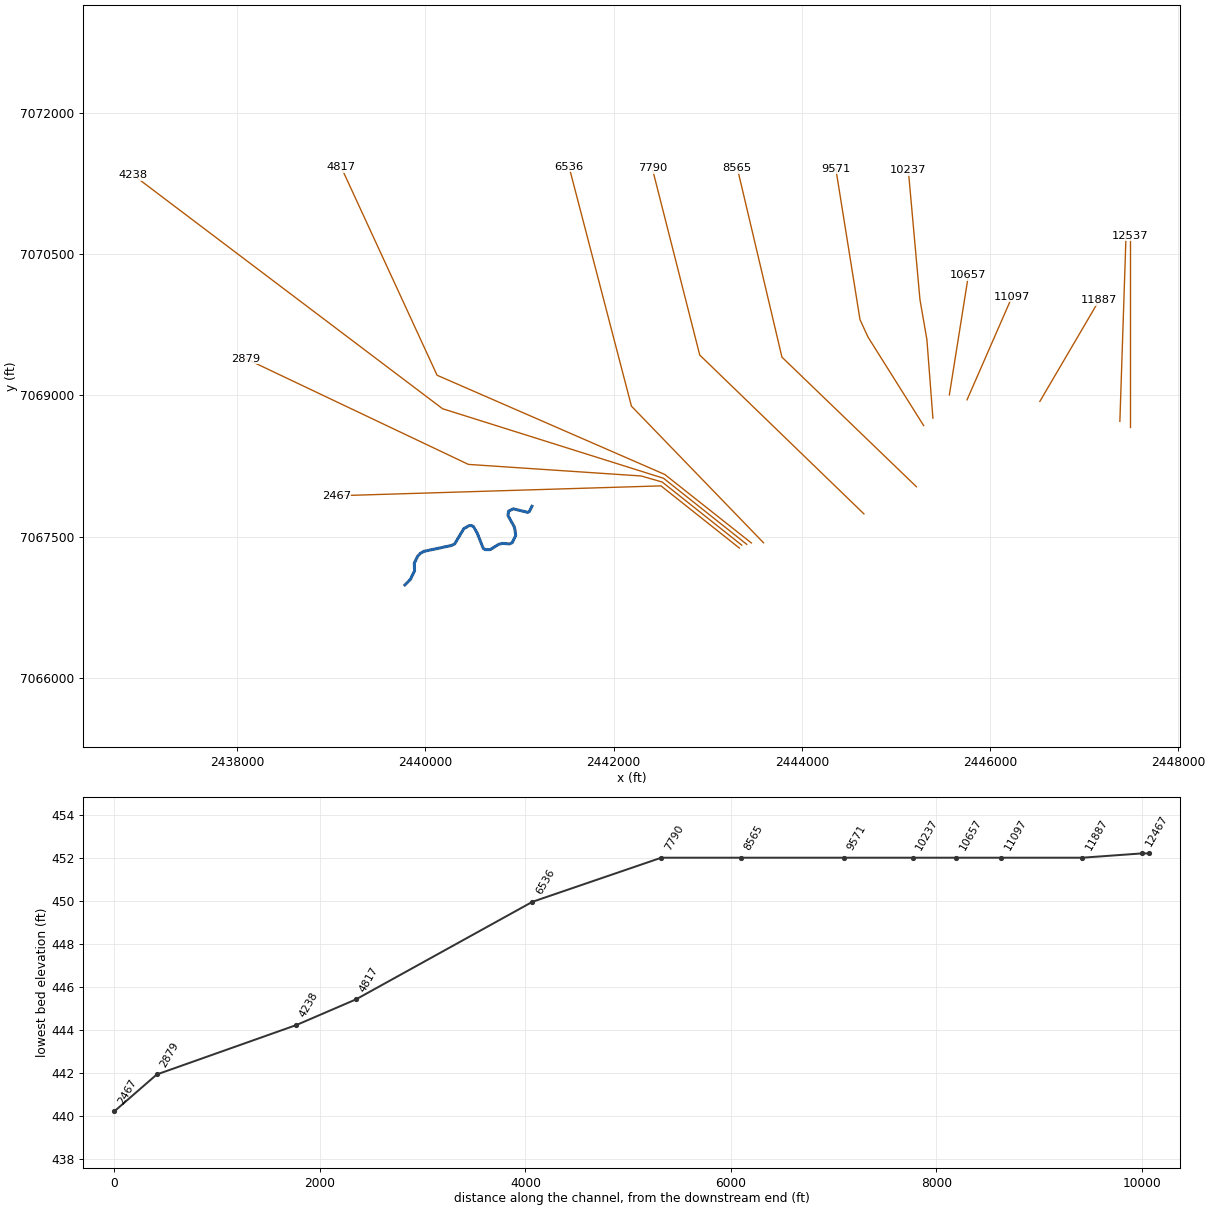
HEC-RAS study CDC_Consolidated_Model.prj: Upper Trinity CDC Consolidated Model

--- CDC_Consolidated_Model.g12 (geometry) --- (continued)

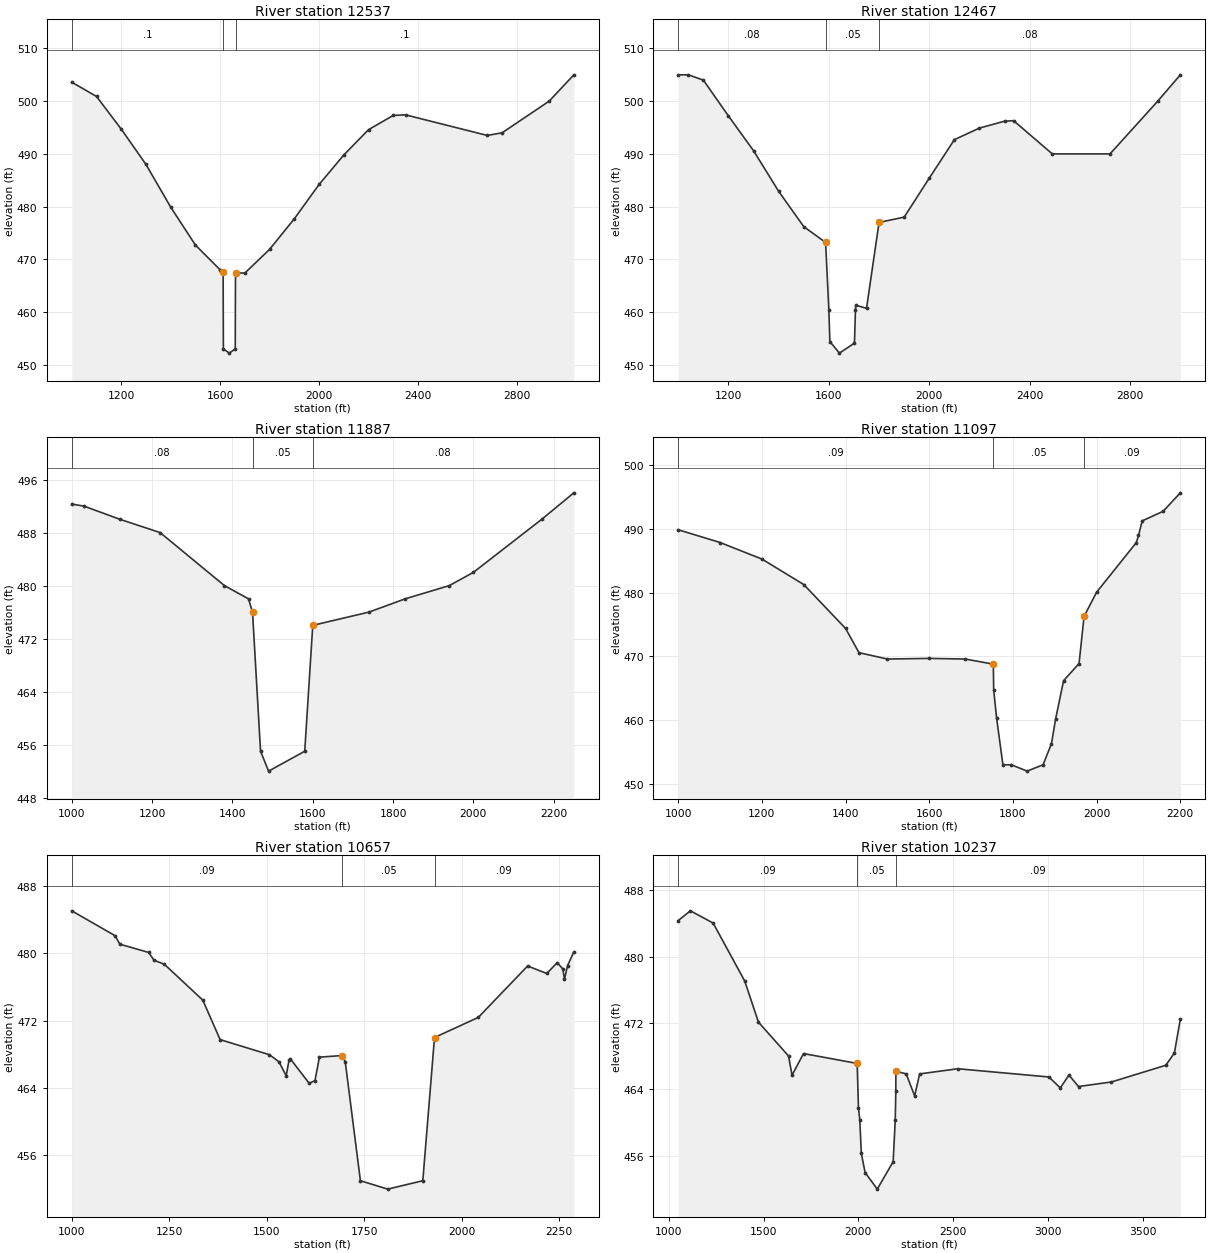
Type RM Length L Ch R = 1 ,12537   ,70,70,70
BEGIN DESCRIPTION:
7380 DS of Hatchery Road
Cross-section surveyed December 1990.
END DESCRIPTION:
XS GIS Cut Line= 2
2447490.752159517068664.918032652447490.752159517070697.65038387
#Sta/Elev= 24
    1000   503.6    1100   500.9    1200   494.7    1300     488    1400   479.9
    1500   472.7    1600     468    1612   467.5    1613     453    1637   452.2
    1661     453    1662   467.4    1700   467.4    1800   471.9    1900   477.7
    2000   484.2    2100   489.8    2200   494.6    2300   497.3    2350   497.4
    2680   493.5    2740     494    2930     500    3030     505
#Mann= 3 ,0,0
    1000      .1       0    1612     .05       0    1662      .1       0
Bank Sta=1612,1662
XS Rating Curve= 0 ,0
Exp/Cntr=0.3,0.1

Type RM Length L Ch R = 1 ,12467   ,580,580,580
BEGIN DESCRIPTION:
7310
Cross-section surveyed December 1990.
END DESCRIPTION:
XS GIS Cut Line= 2
2447379.862883547068724.975605792447446.214549237070729.65223046
#Sta/Elev= 26
    1000     505    1040     505    1100     504    1200   497.2    1300   490.6
    1400   482.9    1500   476.2    1587   473.2    1600   460.4    1604   454.4
    1642   452.2    1702   454.1    1706   460.4    1707   461.3    1750   460.7
    1800     477    1900     478    2000   485.4    2100   492.7    2200   494.9
    2300   496.2    2336   496.3    2490     490    2720     490    2910     500
    3000     505
#Mann= 3 ,0,0
    1000     .08       0    1587     .05       0    1800     .08       0
Bank Sta=1587,1800
XS Rating Curve= 0 ,0
Exp/Cntr=0.3,0.1

Type RM Length L Ch R = 1 ,11887   ,650,790,670
BEGIN DESCRIPTION:
6730
Cross-section surveyed December 1990.
END DESCRIPTION:
XS GIS Cut Line= 2
2446529.696861847068937.086467862447160.54669862 7070013.1020385
#Sta/Elev= 17
    1000   492.3    1030     492    1120     490    1220     488    1380     480
    1440     478    1450     476    1470     455    1490     452    1580     455
    1600     474    1740     476    1830     478    1940     480    2000     482
    2170     490    2250     494
#Mann= 3 ,0,0
    1000     .08       0    1450     .05       0    1600     .08       0
Bank Sta=1450,1600
XS Rating Curve= 0 ,0
Exp/Cntr=0.3,0.1

Type RM Length L Ch R = 1 ,11097   ,420,440,360
BEGIN DESCRIPTION:
5940
Cross-section surveyed December 1990.
END DESCRIPTION:
Node Name=End of Effective
XS GIS Cut Line= 2
2445755.996541657068954.043972422446233.939416687070048.59216154
#Sta/Elev= 27
    1000   489.9    1100   487.9    1200   485.3    1300   481.3    1400   474.4
    1432   470.6    1500   469.6    1600   469.7    1686   469.6    1753   468.8
    1754   464.7    1761   460.3    1776     453    1796     453    1834     452
    1872     453    1892   456.3    1902   460.2    1921   466.2    1958   468.9
    1970   476.3    2000   480.1    2095   487.9    2100     489    2109   491.3
    2159   492.8    2200   495.7
#Mann= 3 ,0,0
    1000     .09       0    1753     .05       0    1970     .09       0
Bank Sta=1753,1970
XS Rating Curve= 0 ,0
Exp/Cntr=0.3,0.1

Type RM Length L Ch R = 1 ,10657   ,304.15,420,1021.26
BEGIN DESCRIPTION:
5500
Cross-section surveyed December 1990.
END DESCRIPTION:
XS GIS Cut Line= 2
2445567.948472477069006.122817052445770.296492967070277.34468406
#Sta/Elev= 30
    1000  485.04  1110.9  482.09 1123.25  481.08 1197.06   480.1 1210.69  479.18
 1237.26   478.7 1335.88  474.44 1380.34  469.75 1506.61  467.96 1531.17  467.12
 1549.72  465.46 1557.26  467.36 1560.72  467.45 1608.54  464.57 1623.55  464.88
 1634.95  467.67    1694  467.86 1701.06  467.14    1740     453    1810     452
    1900     453    1930     470  2042.3  472.39 2168.72  478.49 2217.84   477.6
 2244.74  478.89 2259.01  478.13 2263.26  476.92 2271.12  478.54 2287.23  480.16
#Mann= 3 ,-1,0
    1000     .09       0    1694     .05       0    1930     .09       0
Bank Sta=1694,1930
XS Rating Curve= 0 ,0
Exp/Cntr=0.3,0.1

Type RM Length L Ch R = 1 ,10237   ,396.53,666.47,997.49
BEGIN DESCRIPTION:
5080
Cross-section surveyed December 1990.
END DESCRIPTION:
XS GIS Cut Line= 5
2445393.113848397068759.326394652445329.388582147069593.05471405
2445292.348629977069806.780008392445255.308677817070020.50530273
 2445131.87191687071394.02814622
#Sta/Elev= 30
    1050  484.33    1114   485.5 1234.07  484.03 1400.75  477.05 1473.19   472.1
 1631.88  468.03  1650.5  465.71 1710.99  468.32 1993.94  467.13    2001   461.8
    2008   460.3    2016   456.3    2036     454    2100     452    2184   455.3
    2195   460.3    2198   463.8 2198.29   466.2  2252.6  465.87 2297.46  463.22
 2323.69  465.87 2525.27  466.49 3005.77   465.5 3065.89  464.18 3111.47  465.73
 3161.88  464.35 3335.95   464.9 3622.59  466.91 3667.76  468.39 3699.04  472.45
#Mann= 3 ,-1,0
    1050     .09       0 1993.94     .05       0 2198.29     .09       0
Bank Sta=1993.94,2198.29
XS Rating Curve= 0 ,0
Exp/Cntr=0.3,0.1

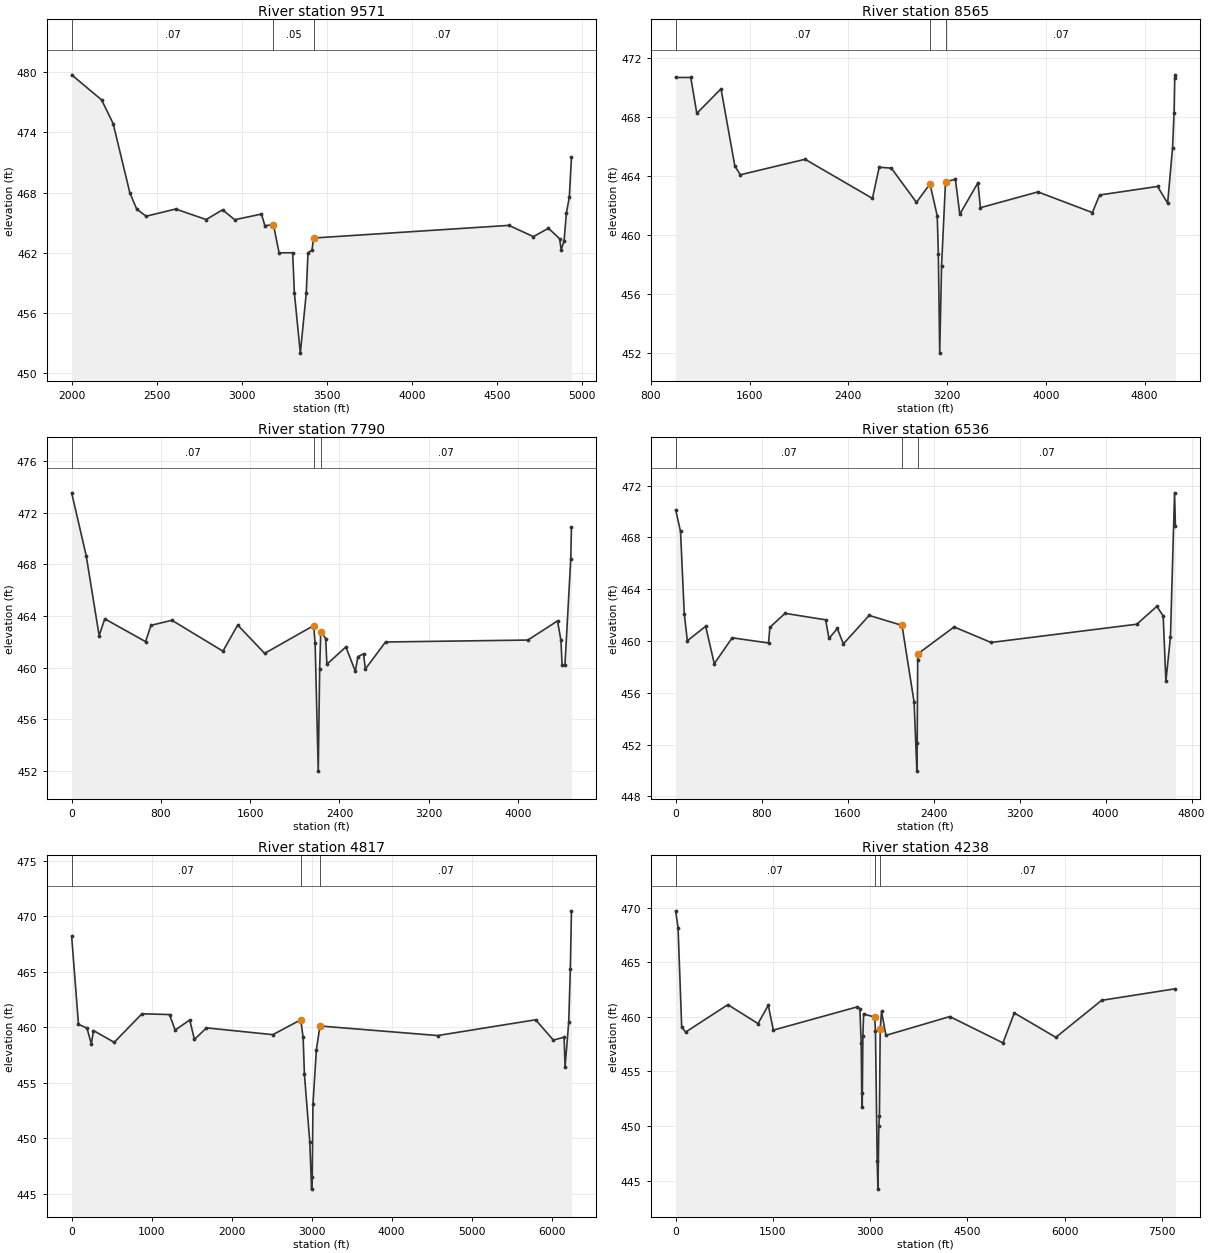
Type RM Length L Ch R = 1 ,9571    ,615.14,1005.99,1028.41
BEGIN DESCRIPTION:
4420
Cross-section surveyed December 1990.
END DESCRIPTION:
XS GIS Cut Line= 5
2445294.949018467068679.712380652444703.886880387069620.22362298
2444661.151401557069713.059067232444618.415922727069805.89451148
2444361.382972237071409.92936115
#Sta/Elev= 30
    2000  479.73 2176.25  477.23  2243.9  474.88 2342.26  467.98 2382.53  466.35
 2437.79  465.64  2611.7  466.36  2791.1  465.31 2887.48  466.28 2959.12  465.29
 3116.39  465.86 3136.34   464.7 3186.79   464.8    3220     462    3300     462
    3310     458    3345     452    3380     458    3390     462 3413.26  462.24
 3423.24  463.47 4571.71  464.73  4715.7  463.61  4804.5  464.44 4869.99   463.4
  4879.3   462.3 4896.35   463.2 4910.13     466 4927.06  467.51 4939.71  471.51
#Mann= 3 ,-1,0
    2000     .07       0 3186.79     .05       0 3423.24     .07       0
Bank Sta=3186.79,3423.24
XS Rating Curve= 0 ,0
Exp/Cntr=0.3,0.1

Type RM Length L Ch R = 1 ,8565    ,594.36,775.32,900.2
BEGIN DESCRIPTION:
3500
Lewisville Lake Spillway Reach
This reach represents discharge from Lewisville Lake uncontrolled spillway for rare flood events: 50 year, 100 year, 500 year. During these rare events the Lewisville Lake outlet works are closed per normal lake regulation plan for flood control.  10-year flood event not considered since no flow occurs.  Cross-section river stations from this point upstream represent distance from McWhorter Creek/Stewart Creek confluence. Cross-section surveyed December 1990.
END DESCRIPTION:
XS GIS Cut Line= 3
2445217.867807817068030.068338722443789.137069467069407.23061064
2443314.35685106 7071417.6170098
#Sta/Elev= 30
    1000  470.67 1122.58  470.67 1171.74  468.24 1367.93   469.9 1479.73  464.68
  1524.2  464.08 2048.93  465.13 2594.89  462.48 2649.75  464.59  2748.1  464.53
 2951.41  462.21 3061.04  463.46    3120   461.3    3129   458.7    3140     452
    3155   457.9    3187   463.6 3266.97  463.78 3302.74  461.41 3449.91  463.54
 3469.82  461.85 3936.25  462.92 4377.23  461.52 4435.57  462.71 4905.29  463.29
 4986.95  462.16 5026.87  465.91 5039.26  468.29 5044.34  470.63 5050.09  470.85
#Mann= 3 ,-1,0
    1000     .07       0 3061.04     .05       0    3187     .07       0
Bank Sta=3061.04,3187
XS Rating Curve= 0 ,0
Exp/Cntr=0.3,0.1

Type RM Length L Ch R = 1 ,7790    ,1034.7,1253.62,878.94
BEGIN DESCRIPTION:
Lidar XS
END DESCRIPTION:
XS GIS Cut Line= 3
2444660.142217227067741.439650892442915.350431227069429.80799331
2442410.142124067071418.08912173
#Sta/Elev= 30
       0  473.53  130.56  468.66  246.32  462.49  296.65  463.78   662.3  462.02
  711.41  463.28  898.62  463.67 1355.66  461.28 1488.12   463.3 1729.71  461.11
 2168.85  463.26  2182.2  461.88 2210.06     452 2222.84  459.93 2232.48   462.8
  2277.1  462.26 2287.27  460.27 2457.89  461.61 2542.28  459.72 2565.21  460.85
 2616.14  461.08 2632.12   459.9 2812.94  461.99 4088.64  462.14  4354.5  463.62
    4385  462.12 4395.54  460.19 4420.92  460.18 4473.06  468.38  4479.4  470.89
#Mann= 3 ,-1,0
       0     .07       0 2168.85     .05       0 2232.48     .07       0
Bank Sta=2168.85,2232.48
XS Rating Curve= 0 ,0
Exp/Cntr=0.3,0.1

Type RM Length L Ch R = 1 ,6536    ,147.91,1718.61,2375.96
BEGIN DESCRIPTION:
Lidar XS
END DESCRIPTION:
XS GIS Cut Line= 3
2443592.838905637067434.640067642442189.627145147068886.46295139
2441526.432605397071431.60188998
#Sta/Elev= 30
       0  470.14   45.58  468.47   80.49  462.11  108.89  460.02  279.28  461.14
  359.53  458.25  526.02  460.25  864.26  459.85  876.69  461.06 1018.01  462.14
 1395.15  461.64 1426.83   460.2 1504.03  460.97 1560.38  459.78 1800.29  461.98
 2105.94  461.21 2218.43  455.28  2244.2  449.95 2247.11  452.14 2251.81  458.57
  2256.5  459.03 2590.65  461.09 2934.37  459.89 4290.04   461.3 4476.59  462.68
  4535.4  461.94 4560.63  456.89 4602.96  460.33 4641.22  471.45 4649.23   468.9
#Mann= 3 ,-1,0
       0     .07       0 2105.94     .05       0  2256.5     .07       0
Bank Sta=2105.94,2256.5
XS Rating Curve= 0 ,0
Exp/Cntr=0.3,0.1

Type RM Length L Ch R = 1 ,4817    ,47.76,578.54,1233.78
BEGIN DESCRIPTION:
Lidar XS
END DESCRIPTION:
XS GIS Cut Line= 4
2443463.529781067067432.594468062442543.960425977068160.43520398
2440124.493152057069214.871415322439104.701556477071427.71869564
#Sta/Elev= 30
       0  468.18    85.3  460.25  191.33  459.91  246.22  458.49  272.81  459.69
  531.95  458.63  878.82   461.2  1223.3  461.13 1293.81  459.73 1476.17  460.64
 1534.72  458.89 1685.65  459.93 2515.91  459.32 2864.28  460.66 2893.81  459.07
 2910.13  455.75 2977.01  449.67 2999.92  445.41 3007.93  446.51  3016.8  453.06
 3059.57  457.97 3104.25   460.1 4575.75  459.24 5800.69  460.66 6022.21  458.83
 6156.35  459.09 6168.58  456.43 6214.27  460.43  6234.5  465.23 6248.54  470.47
#Mann= 3 ,0,0
       0     .07       0 2864.28     .05       0 3104.25     .07       0
Bank Sta=2864.28,3104.25
XS Rating Curve= 0 ,0
Exp/Cntr=0.3,0.1

Type RM Length L Ch R = 1 ,4238    ,46.19,1359.12,642.17
BEGIN DESCRIPTION:
Lidar XS
END DESCRIPTION:
XS GIS Cut Line= 4
2443414.976400467067417.849090732442530.553956727068120.00746331
2440182.504847057068859.156903642436895.845409897071343.32352322
#Sta/Elev= 30
       0  469.72    37.6  468.18   93.74  459.08  154.41  458.61  805.93  461.12
  1271.1  459.39  1429.4  461.07 1507.23  458.79 2802.53  460.92 2842.51  460.76
 2863.11  457.59 2871.14  453.03  2878.8  451.78 2888.93  458.23 2900.54  460.27
 3072.41  459.98 3083.17  458.69 3109.89  446.76 3121.25  444.22 3135.25     450
 3144.23  450.94 3156.09  458.88 3176.75  460.51 3243.97  458.31 4229.76  460.03
  5050.2  457.62 5224.88  460.36 5865.72  458.13 6572.79  461.52 7710.76  462.58
#Mann= 3 ,0,0
       0     .07       0 3072.41     .05       0 3156.09     .07       0
Bank Sta=3072.41,3156.09
XS Rating Curve= 0 ,0
Exp/Cntr=0.3,0.1

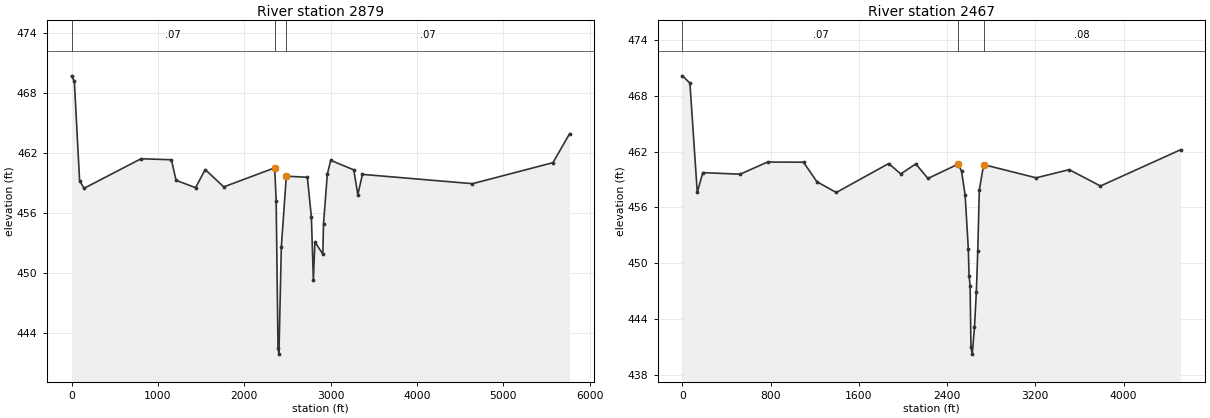
Type RM Length L Ch R = 1 ,2879    ,46.29,412.15,979.16
BEGIN DESCRIPTION:
Lidar XS
END DESCRIPTION:
XS GIS Cut Line= 5
2443361.644158057067409.265774562442517.147815567068079.57939456
2442293.931070397068144.325984222440457.132906727068267.35854656
2438094.072016067069389.88845372
#Sta/Elev= 30
       0  469.71   32.21  469.16   93.01  459.23  145.11  458.48  804.36  461.43
 1156.65  461.33 1209.66  459.28 1435.92  458.54 1547.87  460.35 1762.42  458.62
 2352.42  460.52 2369.32  457.26 2390.87  442.55  2401.5  441.92 2429.24  452.63
 2487.05  459.69 2730.98  459.58 2777.36  455.59 2800.18  449.34 2818.28  453.12
 2909.73  451.91 2917.75  454.93 2961.77  459.87 3000.96  461.27 3268.26  460.32
 3315.25  457.84 3368.24  459.87 4643.13  458.94 5575.12  461.04 5767.65  463.93
#Mann= 3 ,0,0
       0     .07       0 2352.42     .05       0 2487.05     .07       0
Bank Sta=2352.42,2487.05
XS Rating Curve= 0 ,0
Exp/Cntr=0.3,0.1

Type RM Length L Ch R = 1 ,2467    ,1500,1200,295
BEGIN DESCRIPTION:
Lidar XS
END DESCRIPTION:
XS GIS Cut Line= 3
2443336.776097557067377.93578473 2442503.7413463 7068039.1516539
2439052.336831817067933.80081473
#Sta/Elev= 30
       0  470.17    67.4  469.38  134.06  457.61  184.01  459.75  523.57  459.58
  771.28  460.89 1097.46  460.87 1219.06  458.77 1394.76  457.61  1870.1  460.73
 1979.35  459.61  2115.9  460.69 2225.87  459.12 2500.28  460.67 2530.53  459.91
 2563.33  457.32 2592.39   451.5 2598.83  448.65 2608.48  447.59 2616.02     441
 2627.58  440.21 2648.01  443.08 2664.82  446.89 2677.98   451.3 2691.82  457.88
 2731.35  460.61 3207.07  459.19 3507.01  460.07 3790.43  458.31 4516.57  462.21
#Mann= 3 ,0,0
       0     .07       0 2500.28     .05       0 2731.35     .08       0
Bank Sta=2500.28,2731.35
XS Rating Curve= 0 ,0
Exp/Cntr=0.3,0.1

River Reach=Elm Fork L-Spill,efl1
Reach XY= 30
  2441132.601191 7067821.9862019 2441105.4757701 7067768.0235872
 2441089.5004084 7067757.4806293 2440932.9839891 7067795.5008945
  2440883.522802  7067770.498976 2440878.0116581 7067722.4747938
 2440941.7251134 7067609.4694424 2440952.2700398 7067573.5147899
 2440959.2418106 7067511.5241002 2440922.2487744 7067434.9802901
 2440894.4866908 7067422.4947507 2440814.4816015 7067427.4806331
 2440776.7756401 7067416.9859035 2440689.4900536 7067361.4794528
 2440639.5141036 7067360.9906087 2440615.2749789 7067374.4810672
 2440548.7669098 7067541.4879511 2440511.9792537 7067604.9940576
 2440491.7253572 7067616.5301238 2440463.7286941 7067616.4861607
 2440408.2704716 7067583.5275652 2440310.5190267 7067421.9803161
 2440276.7530181 7067405.5042992 2439983.7286698 7067343.0205002
 2439948.0190956 7067322.4910137  2439918.516858 7067291.9871377
 2439881.7479026 7067217.5210793 2439885.0028174 7067135.5307577
 2439840.7634046 7067044.97450842439781.733275337066985.49287523