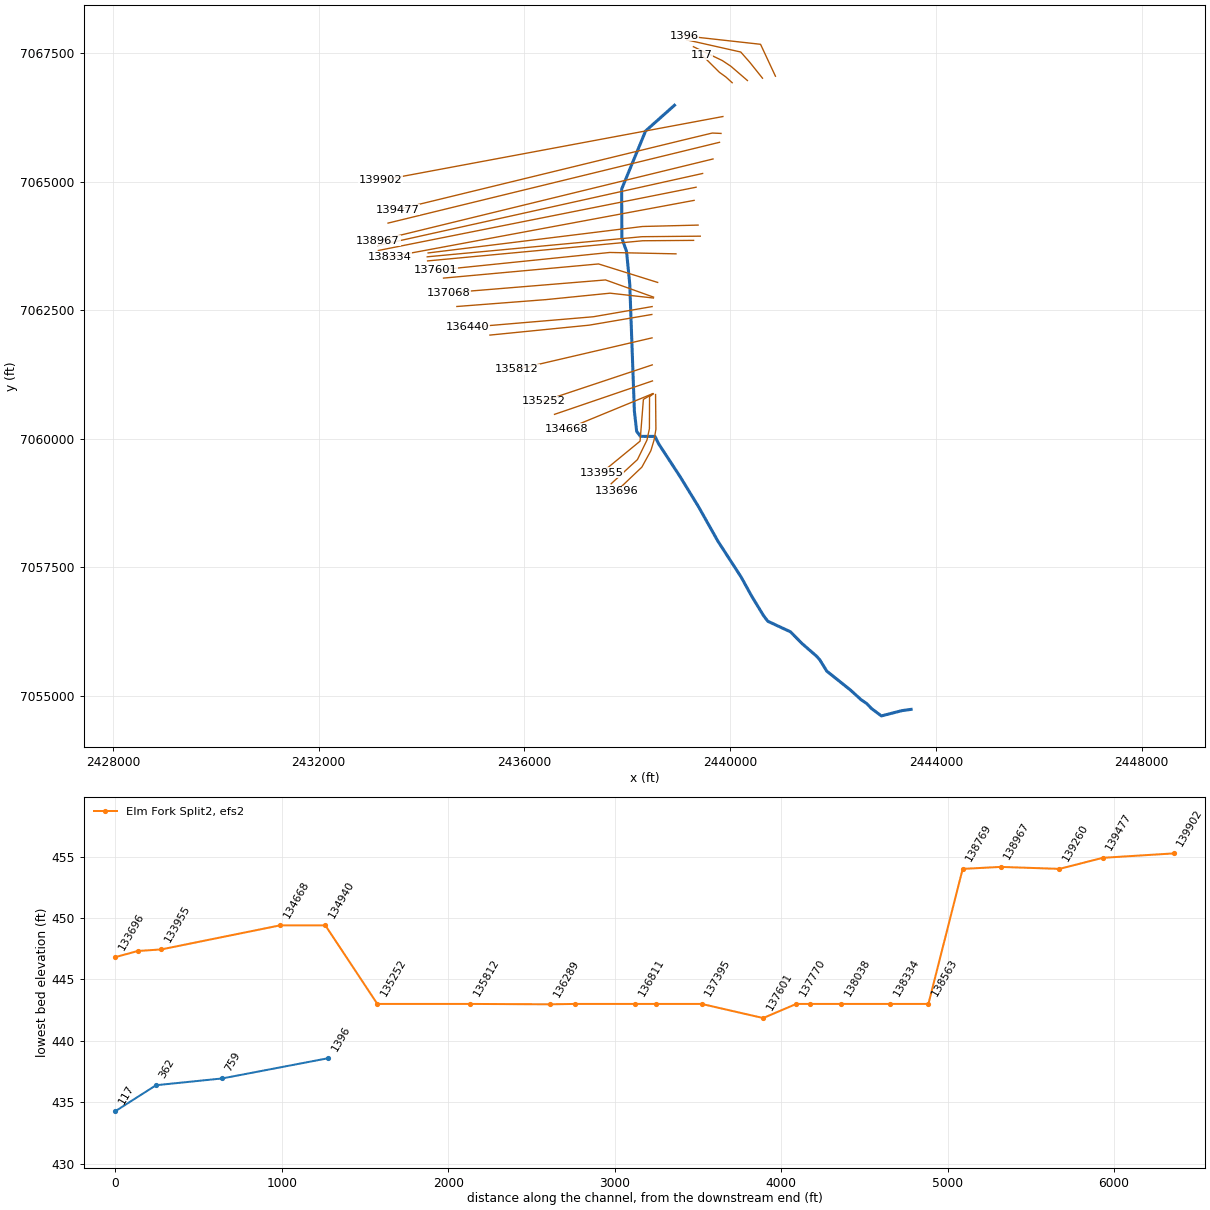
HEC-RAS study CDC_Consolidated_Model.prj: Upper Trinity CDC Consolidated Model

--- CDC_Consolidated_Model.g12 (geometry) --- (continued)

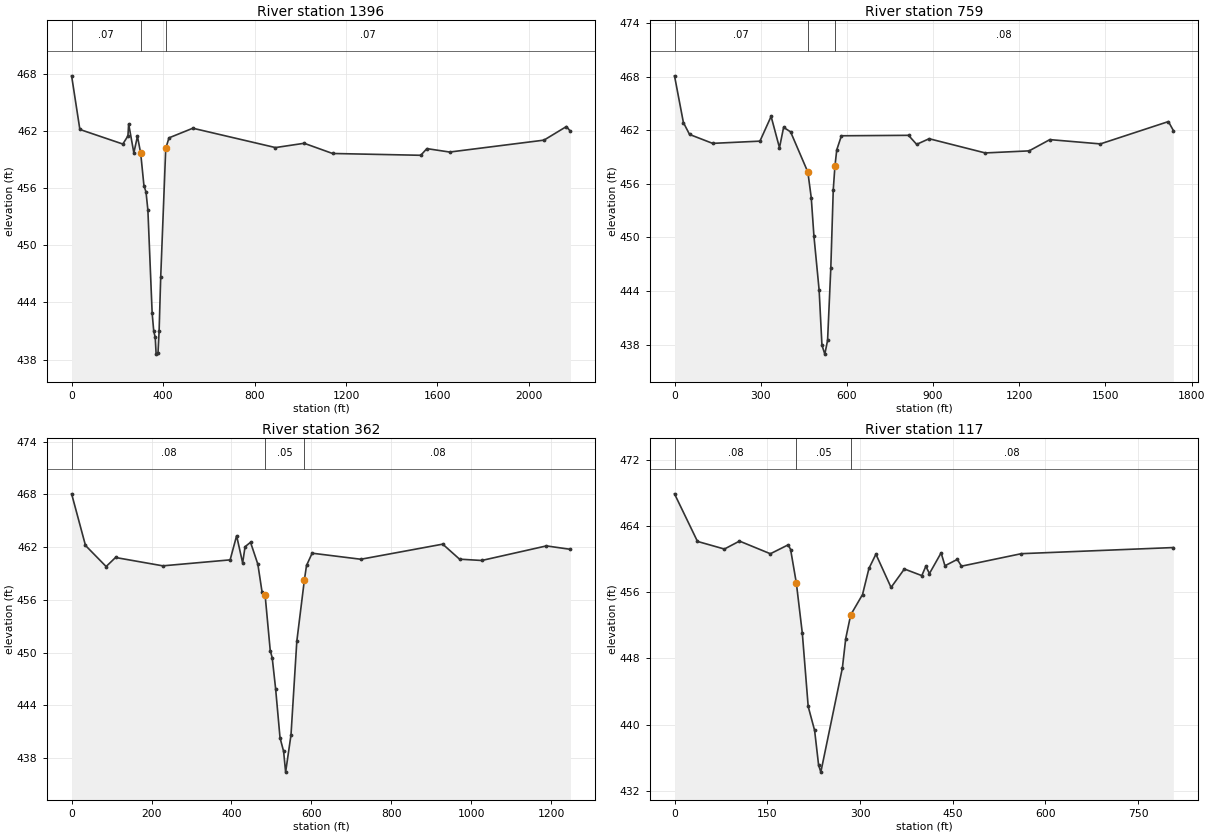
Type RM Length L Ch R = 1 ,1396    ,292.31,637.85,136.8
BEGIN DESCRIPTION:
1396-- From 2009 Lidar
END DESCRIPTION:
XS GIS Cut Line= 3
  2440879.699975 7067049.7189215 2440590.1979293 7067670.3436645
 2439102.7793162 7067835.4827699
#Sta/Elev= 30
       0  467.79   36.12  462.16  223.97  460.63  246.29  461.48  249.49  462.74
  272.15  459.71  287.95  461.44  302.15  459.66  316.36  456.25  325.38   455.6
  333.58  453.69  352.24  442.88   359.2  440.98  365.66  440.35  369.58  438.58
   377.7  438.67  382.61  440.97  389.62  446.65  411.65  460.17  425.81  461.28
  530.12  462.29  891.51  460.26 1016.96  460.71 1141.07  459.64 1526.83  459.45
 1553.54  460.15 1653.31  459.79 2065.58  461.04 2163.97  462.47 2181.38  461.96
#Mann= 3 ,0,0
       0     .07       0  302.15     .05       0  411.65     .07       0
Bank Sta=302.15,411.65
XS Rating Curve= 0 ,0
Exp/Cntr=0.3,0.1

Type RM Length L Ch R = 1 ,759     ,313.51,396.92,289.57
BEGIN DESCRIPTION:
729-- From 2009 Lidar
END DESCRIPTION:
XS GIS Cut Line= 4
  2440628.049887 7067011.2390116 2440380.4982175 7067320.9044027
 2440205.3305888 7067519.9446871 2439156.9373444 7067756.0656059
#Sta/Elev= 30
       0  468.08   30.98  462.85   52.33  461.52  132.64  460.52  297.37  460.77
  336.22  463.54  365.38  460.03   379.7  462.31  404.04  461.81  464.17   457.3
  475.99  454.43  485.27  450.15   503.4  444.09  513.15  437.94  523.16  436.93
  532.75  438.46  544.03  446.57  552.54  455.32  558.44  457.99  564.71  459.79
  580.95  461.37  814.49  461.42  842.75  460.41  886.32  461.04 1081.39  459.45
 1234.29  459.68 1306.37  460.94 1482.26  460.46 1719.07  462.96 1736.25  461.96
#Mann= 3 ,0,0
       0     .07       0  464.17     .05       0  558.44     .08       0
Bank Sta=464.17,558.44
XS Rating Curve= 0 ,0
Exp/Cntr=0.3,0.1

Type RM Length L Ch R = 1 ,362     ,250.49,244.88,181.3
BEGIN DESCRIPTION:
362-- From 2009 Lidar
END DESCRIPTION:
XS GIS Cut Line= 4
  2440335.039975 7066966.0789969 2440013.2217211 7067243.4941245
 2439847.4746772  7067353.928943 2439284.7297397 7067623.2791261
#Sta/Elev= 30
       0  468.07   34.73  462.19   86.37  459.79  109.88  460.82  228.18  459.87
  396.59  460.55  412.81   463.3  427.88   460.2  433.96  462.05  447.61  462.55
  465.96  460.05  476.27  456.94  484.15   456.5  496.96  450.21  501.83  449.41
  510.33   445.9   521.4  440.29  530.39  438.74  535.41  436.38  548.84  440.61
   563.4  451.28  582.36  458.27  587.68  459.91  601.74  461.31  723.58  460.62
  928.42  462.34  970.53  460.63    1026  460.48 1187.86  462.14 1247.94  461.75
#Mann= 3 ,0,0
       0     .08       0  484.15     .05       0  582.36     .08       0
Bank Sta=484.15,582.36
XS Rating Curve= 0 ,0
Exp/Cntr=0.3,0.1

Type RM Length L Ch R = 1 ,117     ,0,0,0
BEGIN DESCRIPTION:
117- From 2009 Lidar
END DESCRIPTION:
XS GIS Cut Line= 4
  2440038.505135 7066923.3251454 2439916.0890413 7067034.9289248
 2439790.0217081 7067125.7725751 2439445.5243656 7067468.2522052
#Sta/Elev= 30
       0  467.88   37.16  462.13   80.68  461.21  105.11  462.17  155.06  460.64
  183.91  461.72  187.79  461.15  197.09  457.09  206.75  451.02  216.22  442.19
   226.6   439.3  233.03  435.13  236.65  434.26  271.52  446.85  276.94   450.4
  284.95  453.25  304.08  455.71  314.49  458.87  325.75  460.59  350.24  456.57
  371.78   458.8  399.98     458  406.49  459.13  412.33  458.25  431.22  460.75
   437.4  459.19  457.38  459.96  464.14  459.14  561.06  460.65  806.81  461.39
#Mann= 3 ,0,0
       0     .08       0  197.09     .05       0  284.95     .08       0
Bank Sta=197.09,284.95
XS Rating Curve= 0 ,0
Exp/Cntr=0.3,0.1

River Reach=Elm Fork Split2 ,efs2
Reach XY= 30
2438916.72621064 7066484.92247892438355.550167647065985.51370081
 2437890.51238387064857.339776052437893.527141567063903.21077882
2437984.672956637063645.398302322438047.172831647063013.45370007
2438137.501063057060539.812978062438181.693231887060146.47485398
2438255.911915477060048.818553222438538.998619637060047.65516973
2438610.518489727059901.703689982439019.197462387059276.85684256
2439376.18723397 7058695.05420042439764.042101317058006.41581389
2440213.762002397057312.223960822440413.31704947 7056949.6009984
2440649.422548387056561.776314722440730.897122967056454.94746014
2441171.58521797 7056249.27169042441401.516516647056016.90010789
2441685.213127727055769.888134732441743.878036637055701.39844231
2441877.534265387055485.121315812442333.995294727055120.49376422
2442542.755375897054931.003985732442653.232845227054854.98281232
2442751.275300067054754.503354472442938.240477317054614.52824073
2443337.731476227054716.973245812443516.631613697054741.58965819

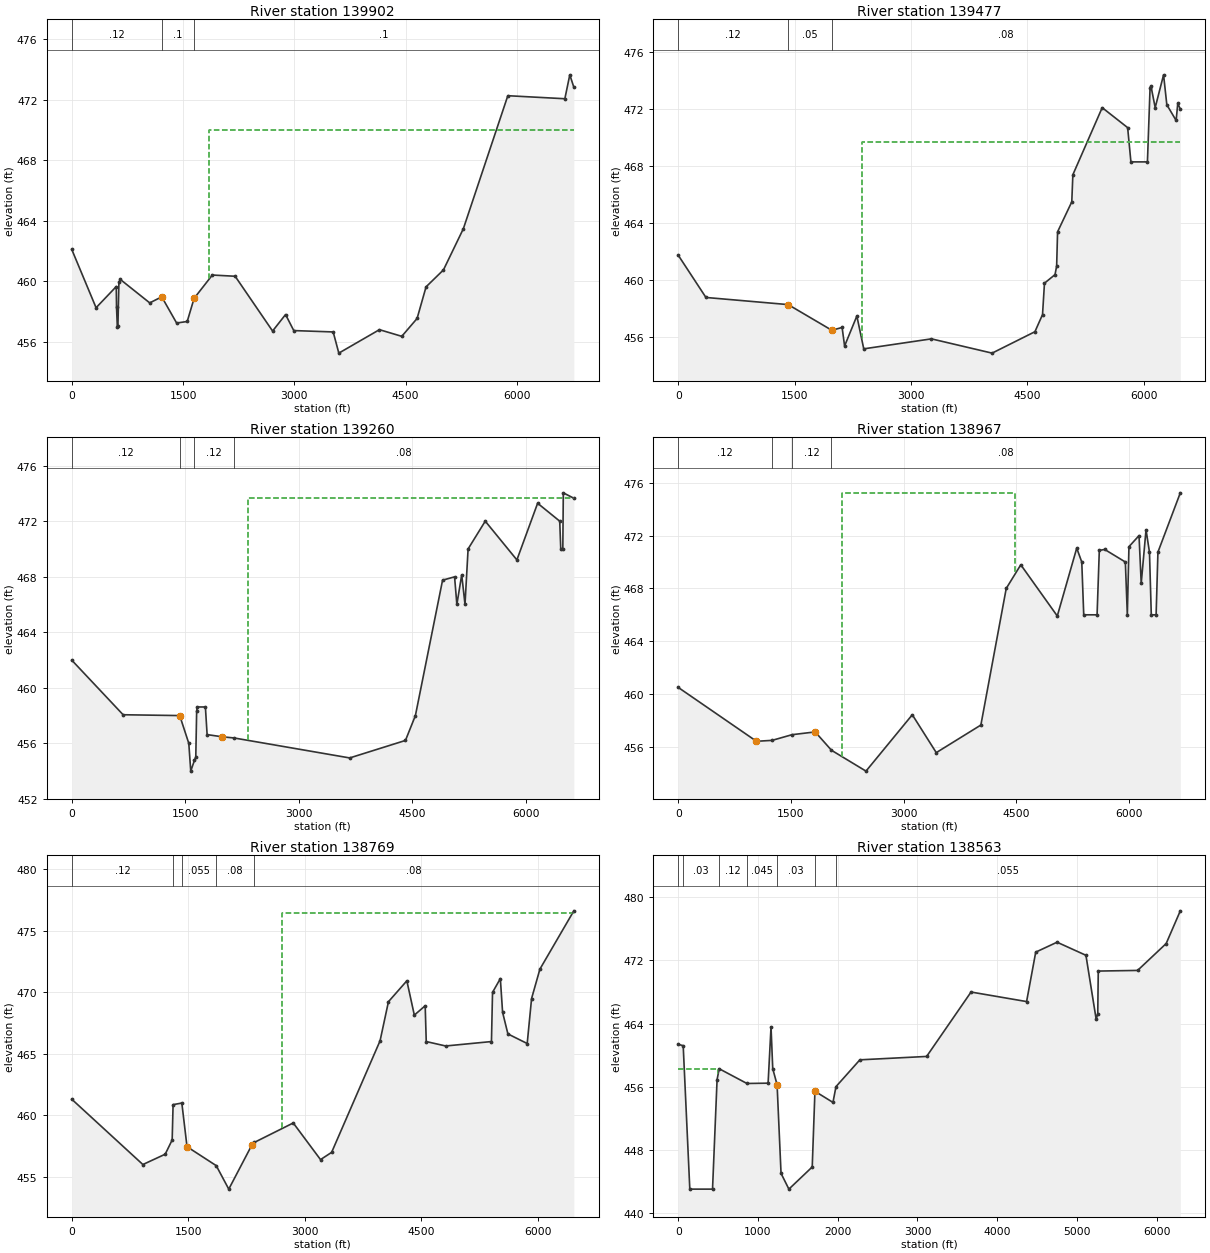
Type RM Length L Ch R = 1 ,139902  ,341.14,425.69,942.49
BEGIN DESCRIPTION:
147204-From Right Overbank Effective model
END DESCRIPTION:
XS GIS Cut Line= 2
2439858.112451237066266.04102689 2433205.5571868 7065024.0139834
#Sta/Elev= 30
       0  462.11   327.6  458.26  599.89  459.66  603.28   458.3  614.32  456.96
  622.09  457.06  635.39  459.94  654.11  460.13 1050.85  458.58 1212.68  458.98
 1413.25  457.25 1556.03  457.35 1648.92  458.88  1894.6  460.42 2202.04  460.34
 2706.82  456.72  2881.7  457.81 2992.41  456.75  3523.7  456.66 3599.58  455.26
 4147.06  456.81    4448  456.37 4654.61  457.55 4775.61  459.64 5010.05  460.76
 5278.15  463.48 5877.61  472.27 6646.26  472.07 6712.94  473.65  6767.5  472.83
#Mann= 3 ,0,0
       0     .12       0 1212.68      .1       0 1648.92      .1       0
#XS Ineff= 2 , 0
                            1850             470
Permanent Ineff=
       F       F
Bank Sta=1212.68,1648.92
XS Rating Curve= 0 ,0
Exp/Cntr=0.3,0.1

Type RM Length L Ch R = 1 ,139477  ,241.06,260.45,210.93
BEGIN DESCRIPTION:
146373-From Right Overbank Effective model
END DESCRIPTION:
XS GIS Cut Line= 4
2439821.828731137065937.634531482439651.26804863 7065945.1637159
2439153.406511567065825.574716232433529.534229137064457.04300448
#Sta/Elev= 30
       0  461.76     357   458.8    1417   458.3    1980   456.5    2112   456.7
    2144   455.4    2302   457.5    2391   455.2    3263   455.9    4045   454.9
    4597   456.4    4695   457.6    4720   459.8    4856   460.4    4877     461
    4889   463.4    5072   465.5    5086   467.4    5464   472.1    5792   470.7
    5834   468.3    6047   468.3    6081   473.5    6093   473.6    6147   472.1
    6255   474.4    6297   472.3    6417   471.2    6438   472.4 6470.74     472
#Mann= 3 ,0,0
       0     .12       0    1417     .05       0    1980     .08       0
#XS Ineff= 2 , 0
                         2365.54        469.7248
Permanent Ineff=
       F       F
Bank Sta=1417,1980
XS Rating Curve= 0 ,0
Exp/Cntr=0.3,0.1

Type RM Length L Ch R = 1 ,139260  ,326.97,352.55,284.95
BEGIN DESCRIPTION:
146190-From Right Overbank Effective model
END DESCRIPTION:
XS GIS Cut Line= 2
2439792.498081137065765.186385562433348.94207063 7064194.3935954
#Sta/Elev= 30
       0  461.99  678.18  458.06 1426.16     458 1545.93     456 1571.69     454
 1620.71  454.78 1638.17  455.01 1649.73  458.33 1659.74  458.62 1765.17  458.62
 1787.86  456.63 1989.98  456.47 2141.88  456.39  3671.2  454.95 4408.12  456.21
 4539.26     458 4898.14  467.75 5056.75  467.99 5086.99     466 5151.12  468.14
 5194.48     466 5235.36     470 5462.03     472  5879.9  469.21 6153.82  473.29
 6445.67     472 6459.47     470 6486.59     470 6493.04  474.04 6632.26  473.65
#Mann= 4 ,-1,0
       0     .12       0 1426.16    .045       0 1620.71     .12       0
 2141.88     .08       0
#XS Ineff= 2 , 0
                          2331.8        473.6515
Permanent Ineff=
       F       F
Bank Sta=1426.16,1989.98
XS Rating Curve= 0 ,0
Exp/Cntr=0.3,0.1

Type RM Length L Ch R = 1 ,138967  ,245.45,228.79,182.57
BEGIN DESCRIPTION:
145775-From Right Overbank Effective model
END DESCRIPTION:
XS GIS Cut Line= 2
2439665.802140317065440.98854314 2433155.5727521 7063854.4129887
#Sta/Elev= 30
       0   460.5 1042.14  456.42 1250.12  456.49 1515.65  456.92 1823.92  457.13
 2040.84  455.74 2500.38  454.16  3117.1  458.43 3436.27  455.56 4030.19  457.65
 4368.16     468 4561.82  469.79    5048  465.91 5306.87  471.05 5373.94     470
 5400.18     466 5577.86     466 5607.57  470.88  5679.6  470.95 5954.33     470
 5980.66     466 6002.25  471.16 6136.49     472  6165.6  468.38 6229.71  472.44
 6275.63  470.74  6299.8     466 6364.06     466 6388.25  470.75 6686.27  475.24
#Mann= 4 ,-1,0
       0     .12       0 1250.12    .045       0 1515.65     .12       0
 2040.84     .08       0
#XS Ineff= 1 ,-1
 2184.52 4485.09 475.238
Permanent Ineff=
       F
Bank Sta=1042.14,1823.92
XS Rating Curve= 0 ,0
Exp/Cntr=0.3,0.1

Type RM Length L Ch R = 1 ,138769  ,252.25,206.06,191.57
BEGIN DESCRIPTION:
145405-From Right Overbank Effective model.
END DESCRIPTION:
XS GIS Cut Line= 2
2439464.193619647065159.219093562433150.965104397063758.55686864
#Sta/Elev= 30
       0  461.31  915.86     456  1203.4  456.84 1293.22     458 1304.95  460.87
 1417.61     461 1484.45  457.45 1860.74  455.91 2022.16     454 2317.36  457.56
 2351.79   457.8 2852.71  459.38 3203.87   456.4 3346.95  456.99 3970.77  466.06
 4078.75  469.24 4315.91  470.94  4412.2  468.15 4552.05  468.91 4565.58     466
 4815.64  465.64  5405.6     466  5419.4     470 5520.09  471.12 5548.94  468.38
 5617.38  466.62 5865.98  465.84 5922.37   469.5 6029.67  471.89 6466.74  476.63
#Mann= 5 ,-1,0
       0     .12       0 1304.95    .045       0 1417.61    .055       0
 1860.74     .08       0 2351.79     .08       0
#XS Ineff= 2 , 0
                         2711.17         476.489
Permanent Ineff=
       F       F
Bank Sta=1484.45,2317.36
XS Rating Curve= 0 ,0
Exp/Cntr=0.3,0.1

Type RM Length L Ch R = 1 ,138563  ,265.25,229.39,220.04
BEGIN DESCRIPTION:
145143-From Right Overbank Effective model
END DESCRIPTION:
XS GIS Cut Line= 2
2439337.236196387064891.939772472433161.146842557063662.24866231
#Sta/Elev= 30
       0  461.37   62.28  461.19  145.18     443  430.13     443  487.19  456.89
  513.54  458.27  861.94   456.4 1127.16  456.44  1163.8  463.58 1185.43  458.27
 1239.84  456.25 1289.42     445 1387.97     443 1680.57  445.81 1714.62  455.41
 1940.72     454 1978.52     456 2278.02   459.4 3115.38  459.83 3672.59     468
 4369.33  466.79 4483.79  473.06 4751.43  474.32 5113.61  472.66 5242.26  464.53
 5261.86  465.27 5268.22  470.66 5761.47  470.74 6119.99  474.15 6297.31   478.3
#Mann= 7 ,-1,0
       0     .12       0   62.28     .03       0  513.54     .12       0
  861.94    .045       0 1239.84     .03       0 1714.62     .08       0
 1978.52    .055       0
#XS Ineff= 2 , 0
             500 458.184
Permanent Ineff=
       F       F
Bank Sta=1239.84,1714.62
XS Rating Curve= 0 ,0
Exp/Cntr=0.3,0.1

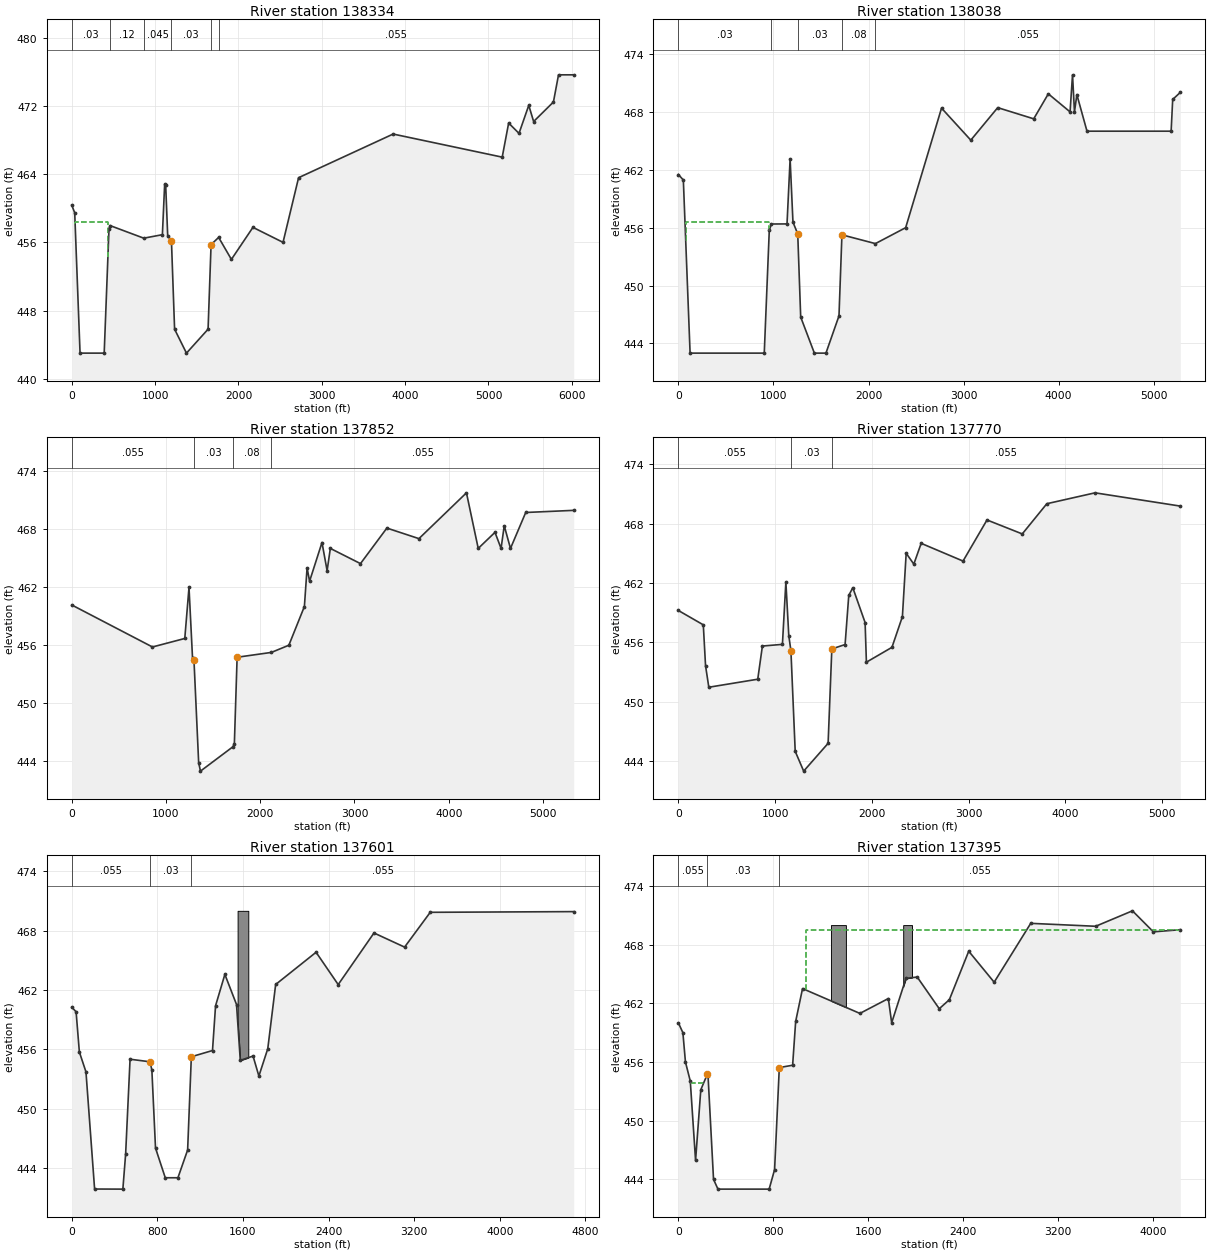
Type RM Length L Ch R = 1 ,138334  ,413.49,295.76,270.15
BEGIN DESCRIPTION:
144901-From Right Overbank Effective model
END DESCRIPTION:
XS GIS Cut Line= 2
2439298.78154889 7064636.26475892433377.850805487063535.20134422
#Sta/Elev= 30
       0  460.36   35.39  459.47   99.42     443  389.05     443   446.5  457.52
  459.27  457.97  864.14  456.49 1087.35   456.9 1114.46  462.79 1126.68  462.77
 1150.93  456.79 1196.04  456.17 1233.77  445.81 1376.26     443 1635.56  445.81
 1671.48  455.74 1762.24  456.58 1915.33     454 2173.81  457.76 2534.84     456
 2721.51  463.59 3855.88  468.71 5164.59     466 5241.84     470 5366.17  468.79
 5483.23  472.08 5541.61  470.18 5779.11  472.47 5840.21  475.66 6022.44  475.66
#Mann= 6 ,-1,0
       0     .03       0  459.27     .12       0  864.14    .045       0
 1196.04     .03       0 1671.48     .08       0 1762.24    .055       0
#XS Ineff= 1 ,-1
   40.53  433.48 458.355
Permanent Ineff=
       F
Bank Sta=1196.04,1671.48
XS Rating Curve= 0 ,0
Exp/Cntr=0.3,0.1

Type RM Length L Ch R = 1 ,138038  ,212.43,185.79,175.86
BEGIN DESCRIPTION:
144676-From Right Overbank Effective model
END DESCRIPTION:
XS GIS Cut Line= 3
2439376.129163227064155.759486322438295.875418227064128.63322823
2434127.947402397063614.20348281
#Sta/Elev= 30
       0  461.51   52.25  460.94  123.28     443  903.47     443  956.27  455.71
  978.11  456.38 1142.87  456.39 1175.44  463.12 1205.33  456.58 1255.64  455.35
 1286.69  446.74 1430.63     443 1552.33     443 1689.56  446.86 1720.47  455.26
 2072.77  454.35 2390.94     456 2768.27  468.39 3076.13  465.07 3359.37  468.44
 3738.03  467.28 3891.59  469.87 4120.39     468 4146.15  471.84 4166.78     468
 4191.85  469.79 4298.44     466 5183.54     466 5199.98  469.29 5280.15  470.02
#Mann= 5 ,-1,0
       0     .03       0  978.11    .045       0 1255.64     .03       0
 1720.47     .08       0 2072.77    .055       0
#XS Ineff= 1 ,-1
   77.24  955.55456.5858
Permanent Ineff=
       F
Bank Sta=1255.64,1720.47
XS Rating Curve= 0 ,0
Exp/Cntr=0.3,0.1

Type RM Length L Ch R = 1 ,137852  ,82.85,82.48,80.51
BEGIN DESCRIPTION:
144554 From Right Overbank Effective model
END DESCRIPTION:
XS GIS Cut Line= 3
 2439418.36365887063940.340625812438287.666773217063930.28716823
2434110.367713147063539.08617897
#Sta/Elev= 30
       0  460.16  856.35  455.82 1199.35   456.7 1244.09  461.97 1281.32  454.71
 1296.67  454.48  1346.6  443.87 1365.81     443 1710.08445.5159 1725.39  445.81
 1754.66  454.76 2118.19  455.26 2303.61     456 2468.53     460 2497.14     464
 2523.49  462.61 2655.23  466.61 2709.57   463.7 2743.85     466 3063.73  464.43
 3343.82   468.1 3683.95  467.01  4188.2  471.74 4313.15     466    4491  467.66
 4555.45     466 4589.14  468.34 4655.37     466 4817.12  469.71 5326.32  469.93
#Mann= 4 ,-1,0
       0    .055       0 1296.67     .03       0 1710.08     .08       0
 2118.19    .055       0
Bank Sta=1296.67,1754.66
XS Rating Curve= 0 ,0
Exp/Cntr=0.3,0.1

Type RM Length L Ch R = 1 ,137770  ,199.6,199.26,205.62
BEGIN DESCRIPTION:
144474-From Right Overbank Effective model
END DESCRIPTION:
XS GIS Cut Line= 3
2439288.521070727063858.444136072438302.439381477063851.33260173
2434117.826031557063459.44657448
#Sta/Elev= 30
       0  459.22  257.72  457.77  280.81  453.65  314.63  451.47  820.57  452.28
  868.62  455.63 1075.69   455.8 1111.28   462.1 1141.48  456.67 1163.51  455.16
 1207.78     445 1295.35     443 1547.97  445.81 1586.37  455.34 1723.45  455.78
 1761.49  460.74 1803.26  461.52 1930.39     458 1943.79     454    2208   455.5
    2316   458.6    2355     465    2434   463.9    2510     466 2942.78  464.21
 3190.59  468.36 3555.06  466.95 3809.01     470 4307.54   471.1 5189.03  469.76
#Mann= 3 ,0,0
       0    .055       0 1163.51     .03       0 1586.37    .055       0
Bank Sta=1163.51,1586.37
XS Rating Curve= 0 ,0
Exp/Cntr=0.3,0.1

Type RM Length L Ch R = 1 ,137601  ,370.43,369.8,381.59
BEGIN DESCRIPTION:
144314-From Right Overbank Effective model
END DESCRIPTION:
XS GIS Cut Line= 3
     2438946.142     7063596.799     2437657.252     7063623.705
      2434272.57     7063276.982
#Sta/Elev= 30
       0  460.25   40.48  459.79   71.08  455.72  132.71  453.71  213.48  441.86
  477.63  441.85  503.57  445.41  544.94  454.99  731.58  454.73  748.74  453.89
  782.85     446  873.95     443  992.32     443    1083  445.81 1117.59  455.24
 1315.44  455.87 1344.05   460.4 1431.08  463.57 1540.08  460.52 1575.22  454.87
 1694.48  455.31 1748.97  453.29 1832.04  456.05  1905.8  462.55 2283.55  465.81
  2490.3  462.54 2824.77  467.76 3110.92  466.33 3350.61  469.85 4691.57  469.92
#Mann= 3 ,0,0
       0    .055       0  731.58     .03       0 1117.59    .055       0
#XS Ineff= 2 , 0
          640.05 454.323
Permanent Ineff=
       F       F
#Block Obstruct= 1 ,-1
    1550    1650     470
Bank Sta=731.58,1117.59
XS Rating Curve= 0 ,0
Exp/Cntr=0.3,0.1

Type RM Length L Ch R = 1 ,137395  ,272.64,272.18,280.86
BEGIN DESCRIPTION:
144148-From Right Overbank Effective model
END DESCRIPTION:
XS GIS Cut Line= 3
     2438590.224      7063041.13      2437440.76     7063400.606
     2434427.706      7063125.34
#Sta/Elev= 30
       0     460   38.03     459    59.6     456  100.34  454.05   144.9  445.93
  188.93  453.16   243.6  454.74  250.06  454.58  296.26     444  333.54     443
  764.94     443  810.88     445  850.56  455.43  962.83  455.67  988.41  460.15
 1046.35  463.51 1529.76  460.97 1769.39  462.49 1797.47  460.01  1917.8  464.55
 2012.65  464.69 2198.57  461.45 2283.49  462.37 2446.84  467.33 2661.13  464.16
 2969.41  470.18 3516.51  469.88 3826.51  471.46 4002.92  469.31 4229.96  469.53
#Mann= 3 ,0,0
       0    .055       0   243.6     .03       0  850.56    .055       0
#XS Ineff= 2 ,-1
     100     210 453.876 1075.26 4480.46  469.53
Permanent Ineff=
       F       F
#Block Obstruct= 2 ,-1
 1285.75 1411.78     470  1894.6 1968.78     470
Bank Sta=243.6,850.56
XS Rating Curve= 0 ,0
Exp/Cntr=0.3,0.1

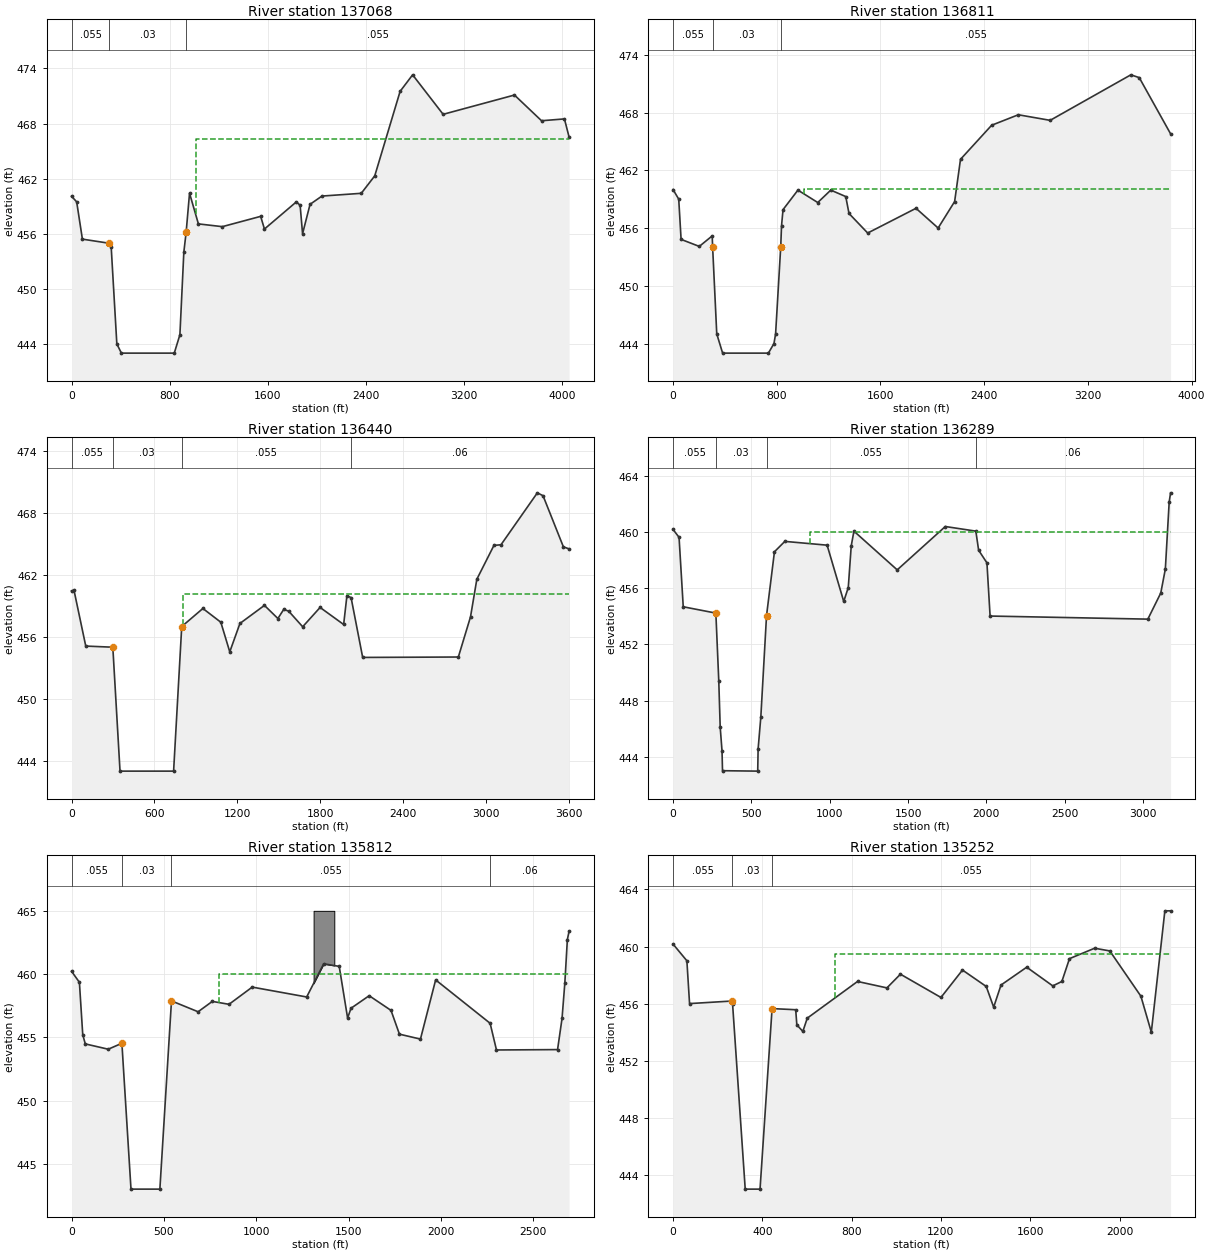
Type RM Length L Ch R = 1 ,137068  ,127.02,126.81,130.85
BEGIN DESCRIPTION:
143756-From Right Overbank Effective model
END DESCRIPTION:
XS GIS Cut Line= 3
     2438509.482     7062755.704     2437576.939     7063089.602
     2434517.585     7062838.207
#Sta/Elev= 30
       0  460.08   41.87  459.47   88.58  455.41  308.83  454.96  323.42  454.58
  369.62     444   406.9     443   838.3     443  884.24     445  916.39     454
  935.22  456.17  962.87  460.41 1035.17  457.07  1230.4  456.77 1543.24  457.89
 1574.15  456.51 1834.73  459.47 1865.34  459.09  1885.2     456 1946.25   459.2
 2043.25   460.1 2364.25   460.4 2474.25   462.3 2681.25   471.5 2783.25   473.3
 3032.25     469 3614.25   471.1 3835.25   468.3 4022.17   468.5 4060.18  466.52
#Mann= 3 ,0,0
       0    .055       0  308.83     .03       0  935.22    .055       0
#XS Ineff= 2 , 0
                         1011.91         466.291
Permanent Ineff=
       F       F
Bank Sta=308.83,935.22
XS Rating Curve= 0 ,0
Exp/Cntr=0.3,0.1

Type RM Length L Ch R = 1 ,136811  ,362.71,362.09,373.64
BEGIN DESCRIPTION:
143265-From Right Overbank Effective model
END DESCRIPTION:
XS GIS Cut Line= 5
     2438507.403     7062738.035     2437664.285      7062832.13
     2437134.705     7062778.963     2436417.209     7062706.931
     2434686.576     7062573.292
#Sta/Elev= 30
       0     460   43.93     459   62.11  454.82  202.49  454.09  302.07  455.18
  305.45     454  337.17     445  382.49     443  735.46     443  778.52     444
  791.01     445  830.38     454  836.84  456.23  848.35  457.91  963.16  459.94
  1116.2  458.65  1216.7  459.94 1332.04  459.27 1357.21  457.51  1501.4  455.48
 1873.94  458.05 2044.55     456 2171.81  458.75 2217.17  463.14 2457.32  466.68
 2663.06  467.77 2908.61  467.19 3530.98  471.92  3595.8  471.63 3837.48  465.79
#Mann= 3 ,0,0
       0    .055       0  305.45     .03       0  830.38    .055       0
#XS Ineff= 2 , 0
                         1010.36        460.0787
Permanent Ineff=
       F       F
Bank Sta=305.45,830.38
XS Rating Curve= 0 ,0
Exp/Cntr=0.3,0.1

Type RM Length L Ch R = 1 ,136440  ,153.14,150.76,152.2
BEGIN DESCRIPTION:
142900-From Right Overbank Effective model
END DESCRIPTION:
XS GIS Cut Line= 3
2438482.719532717062571.696709562437339.328118737062373.83358823
2434904.216847237062167.62927623
#Sta/Elev= 30
       0  460.46      18   460.5     103  455.11     299     455  351.17     443
  739.32     443  798.18     457  951.44  458.75 1081.35  457.42 1146.12  454.55
 1219.71   457.3 1397.29  459.05 1494.73  457.78 1537.02  458.66 1572.99  458.49
 1674.29  456.98 1800.48  458.85 1971.05   457.2 1994.93     460 2024.97   459.8
 2108.97  454.01 2801.94  454.05 2890.07  457.94 2935.81  461.58 3059.75  464.86
 3110.84  464.92 3374.29  469.95 3415.46  469.67 3562.83  464.72 3604.21  464.52
#Mann= 4 ,-1,0
       0    .055       0     299     .03       0  798.18    .055       0
 2024.97     .06       0
#XS Ineff= 2 , 0
                          810.97          460.14
Permanent Ineff=
       F       F
Bank Sta=299,798.18
XS Rating Curve= 0 ,0
Exp/Cntr=0.3,0.1

Type RM Length L Ch R = 1 ,136289  ,467.11,477.16,517.19
BEGIN DESCRIPTION:
142702- From Right Overbank Effective model
END DESCRIPTION:
XS GIS Cut Line= 3
2438477.144740727062418.047410562437259.592057727062210.56160507
2435329.014225977062017.56363148
#Sta/Elev= 30
       0  460.19   38.42  459.63   65.12  454.68  273.26  454.23  291.83  449.42
  300.98   446.1   312.7   444.4  315.68     443  540.45  442.97  542.91  444.54
  560.35  446.84  596.66  454.05  647.21   458.6  713.42  459.34   983.3  459.07
 1089.31  455.06 1118.33  456.05 1137.22  459.02  1154.4  460.07 1430.64  457.31
 1737.52   460.4 1932.45  460.07  1950.2  458.71 2003.19  457.81 2023.45  454.02
 3030.13   453.8 3112.63  455.66 3141.85  457.37 3166.37  462.15 3175.31   462.8
#Mann= 4 ,-1,0
       0    .055       0  273.26     .03       0  596.66    .055       0
 1932.45     .06       0
#XS Ineff= 2 , 0
                          872.18             460
Permanent Ineff=
       F       F
Bank Sta=273.26,596.66
XS Rating Curve= 0 ,0
Exp/Cntr=0.3,0.1

Type RM Length L Ch R = 1 ,135812  ,546.71,559.23,594.27
BEGIN DESCRIPTION:
141891-From Right Overbank Effective model
END DESCRIPTION:
XS GIS Cut Line= 2
2438480.731347727061963.320629732435857.493155887061352.45735015
#Sta/Elev= 30
       0  460.22   42.52  459.35   60.68   455.2   74.46  454.48  198.69  454.06
  272.55  454.53   321.8     443  478.17     443     541  457.88  685.08  457.02
  761.99  457.84  852.47  457.61   978.1  458.97  1272.8  458.19 1364.82  460.81
 1448.99  460.61 1494.34  456.53    1513   457.3 1611.23  458.29 1729.35  457.13
 1774.99  455.25 1888.73  454.86 1971.01  459.54 2265.87  456.11 2300.27     454
 2631.01  454.03 2655.21  456.49 2670.38   459.3 2684.04  462.73 2693.42  463.39
#Mann= 4 ,-1,0
       0    .055       0  272.55     .03       0     541    .055       0
 2265.87     .06       0
#XS Ineff= 2 , 0
                          800.92             460
Permanent Ineff=
       F       F
#Block Obstruct= 1 ,-1
 1310.28 1422.38     465
Bank Sta=272.55,541
XS Rating Curve= 0 ,0
Exp/Cntr=0.3,0.1

Type RM Length L Ch R = 1 ,135252  ,317.56,312.42,308.11
BEGIN DESCRIPTION:
141518-From Right Overbank Effective model
END DESCRIPTION:
XS GIS Cut Line= 2
2438484.872415567061438.317086562436370.415358387060734.05569981
#Sta/Elev= 30
       0  460.17      62     459      74     456  263.41  456.18  266.58     456
  323.35     443  389.72     443  443.59  455.65  549.49  455.57   554.5  454.51
  581.46  454.05  601.25  454.98  826.43  457.55  958.08   457.1 1018.56  458.06
 1200.05  456.43 1296.49  458.35 1402.92   457.2 1436.16  455.75 1469.05   457.3
 1584.19  458.55 1700.94  457.24 1741.66  457.55 1775.82  459.15 1888.44  459.88
 1956.34  459.69 2095.61  456.52 2142.37     454    2203   462.5 2228.66   462.5
#Mann= 3 ,0,0
       0    .055       0  263.41     .03       0  443.59    .055       0
#XS Ineff= 2 , 0
                          723.97           459.5
Permanent Ineff=
       F       F
Bank Sta=263.41,443.59
XS Rating Curve= 0 ,0
Exp/Cntr=0.3,0.1

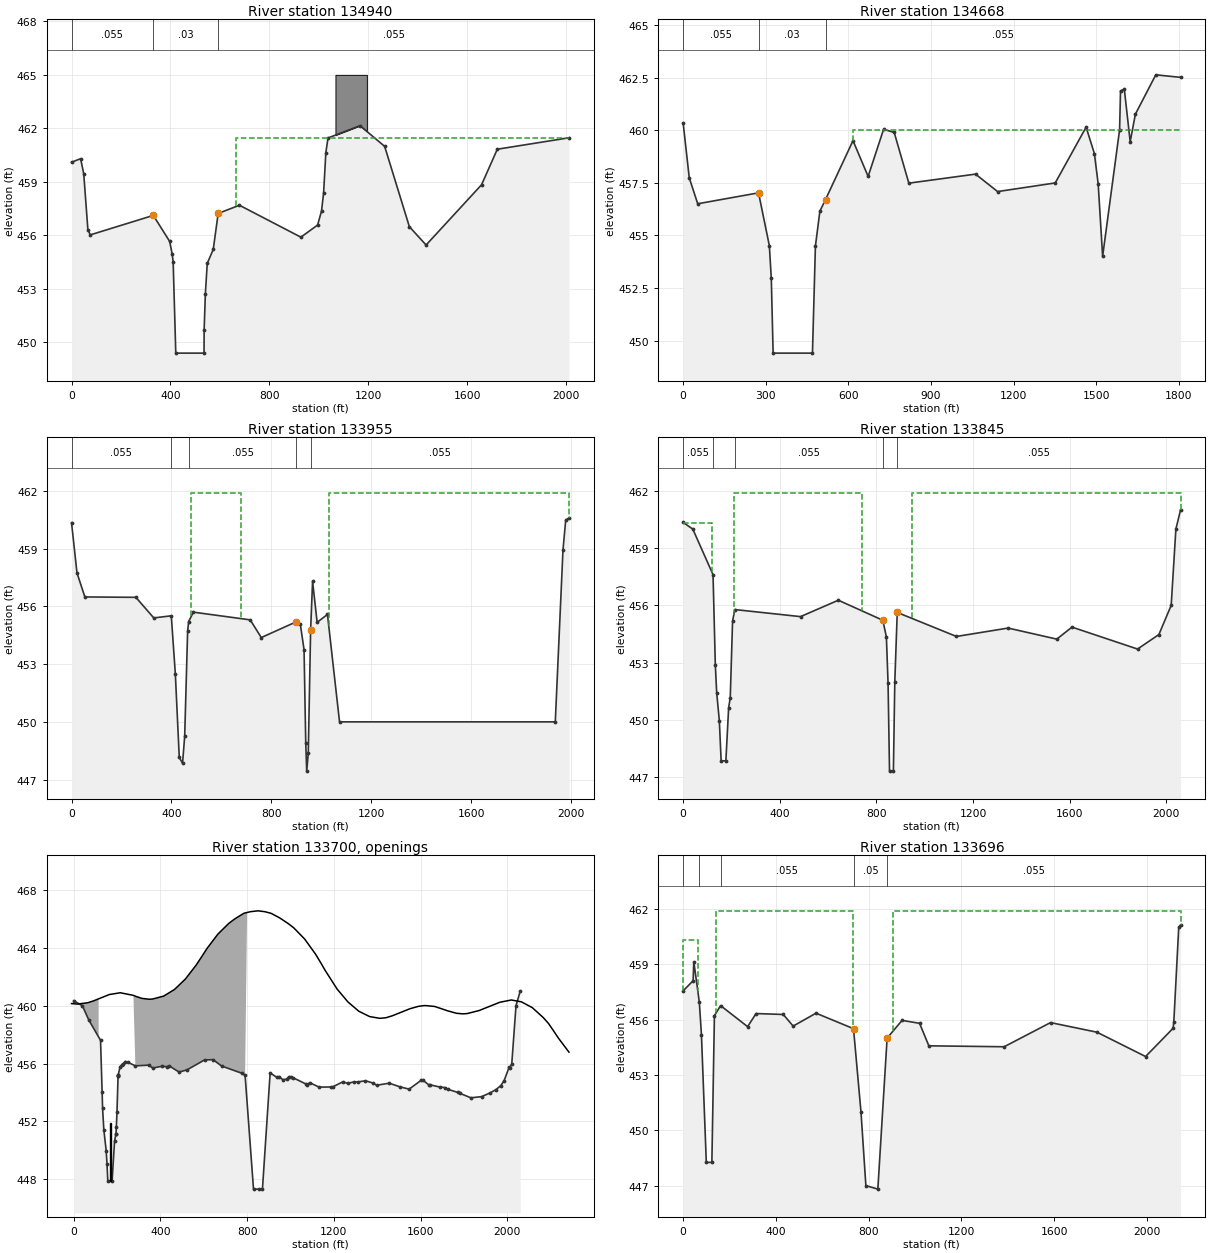
Type RM Length L Ch R = 1 ,134940  ,265.83,271.87,290.76
BEGIN DESCRIPTION:
141274-From Right Overbank Effective model
END DESCRIPTION:
XS GIS Cut Line= 2
2438489.057446557061126.74881206 2436585.26105737060476.89348447
#Sta/Elev= 30
       0   460.1   36.71   460.3   49.33  459.45   66.24   456.3   76.14  456.03
  330.72  457.12  396.98  455.66   407.3  454.93  410.97  454.52  421.62   449.4
  535.86   449.4  536.25   450.7  541.26  452.73  548.82  454.43  573.09  455.21
  593.01  457.23  678.96  457.69  927.56   455.9  995.13  456.58 1010.92  457.36
 1019.38  458.37 1028.47  460.64 1037.25  461.46 1166.64  462.15  1266.3  460.99
 1366.18  456.49 1433.84  455.46 1658.35  458.84 1721.89  460.83 2011.65  461.47
#Mann= 3 ,0,0
       0    .055       0  330.72     .03       0  593.01    .055       0
#XS Ineff= 2 , 0
                           666.9          461.47
Permanent Ineff=
       F       F
#Block Obstruct= 1 ,-1
 1067.32 1194.41     465
Bank Sta=330.72,593.01
XS Rating Curve= 0 ,0
Exp/Cntr=0.3,0.1

Type RM Length L Ch R = 1 ,134668  ,22.26,713.47,805.77
BEGIN DESCRIPTION:
141084-From Right Overbank Effective model
END DESCRIPTION:
XS GIS Cut Line= 2
2438492.947858727060878.538350482436823.331119227060190.97017181
#Sta/Elev= 30
       0  460.35   22.27  457.73   52.99   456.5  273.74  457.02  312.96  454.51
  320.07  452.95  326.72   449.4  469.49   449.4  480.22  454.49  496.46  456.15
  516.89   456.7  616.63   459.5  671.58   457.8  727.67  460.04  766.27  459.89
  819.34  457.48 1061.38  457.91 1141.65  457.08 1350.73  457.49 1462.79  460.14
 1492.87  458.89 1506.75  457.43 1522.81     454  1584.4  460.02 1587.76  461.87
 1601.61  461.94 1622.86  459.45 1641.71  460.76 1715.77  462.63 1805.65  462.51
#Mann= 3 ,0,0
       0    .055       0  273.74     .03       0  516.89    .055       0
#XS Ineff= 2 , 0
                          616.98             460
Permanent Ineff=
       F       F
Bank Sta=273.74,516.89
XS Rating Curve= 0 ,0
Exp/Cntr=0.3,0.1

Type RM Length L Ch R = 1 ,133955  ,99.43,141.96,130.31
BEGIN DESCRIPTION:
Lidar xsec
END DESCRIPTION:
XS GIS Cut Line= 4
  2438497.966549 7060877.1069229 2438312.9459221 7060767.5979556
  2438248.280041 7059955.5175587 2437502.3353386  7059343.031579
#Sta/Elev= 30
       0  460.35   21.79  457.74   53.33  456.49   257.6  456.47  329.29   455.4
  399.39  455.51  415.58   452.5  431.38  448.15  444.45  447.85  453.02  449.24
  464.85  454.71  468.94  455.21  487.72   455.7  715.35   455.3  759.78  454.38
     900   455.2  915.87  455.09     931  453.75  937.72  448.92  941.63  447.44
  947.91  448.37  957.27  454.76  965.13   457.3  983.33  455.17 1024.73  455.58
 1073.04     450 1936.93     450 1967.73  458.93 1978.67  460.49 1991.63  460.58
#Mann= 5 ,-1,0
       0    .055       0  399.39     .05       0  468.94    .055       0
     900     .05       0  957.27    .055       0
#XS Ineff= 2 ,-1
     480     679   461.9    1030    2100   461.9
Permanent Ineff=
       F       F
Bank Sta=900,957.27
XS Rating Curve= 0 ,0
Exp/Cntr=0.5,0.3

Type RM Length L Ch R = 1 ,133845  ,118.17,134.58,148.61
BEGIN DESCRIPTION:
Embankment US-gis7858
END DESCRIPTION:
XS GIS Cut Line= 6
  2438505.062335 7060875.0819926   2438432.32298 7060820.6683875
 2438429.7878801 7060199.8418732 2438382.5655336 7059976.9253243
 2438197.1489096 7059597.0642074 2437685.8412052 7059127.7436237
#Sta/Elev= 30
       0  460.35      40     460  123.81  457.61  133.25  452.89  138.95  451.42
  149.86  449.96  157.35  447.85  176.96  447.85  188.45  450.64  195.07  451.15
  204.72  455.18  214.09  455.78  485.95  455.41  642.57  456.27  826.59  455.22
   841.4  454.35   848.4  451.91  854.42  447.31  870.45  447.31  876.23  451.97
  886.33  455.63 1131.47  454.37 1345.34  454.81  1546.9  454.23 1609.84  454.86
 1881.16  453.71 1969.51  454.47 2020.43     456 2039.88     460 2059.17     461
#Mann= 5 ,-1,0
       0    .055       0  123.81     .05       0  214.09    .055       0
  826.59     .05       0  886.33    .055       0
#XS Ineff= 3 ,-1
       0     120   460.3     210     742   461.9     948    2100   461.9
Permanent Ineff=
       F       F       F
Bank Sta=826.59,886.33
XS Rating Curve= 0 ,0
Exp/Cntr=0.5,0.3

Type RM Length L Ch R = 4 ,133700  ,,,
Bridge Culvert--1,0,-1,-1, 0
Deck Dist Width WeirC Skew NumUp NumDn MinLoCord MaxHiCord MaxSubmerge Is_Ogee
24,83,2.6,0, 68, 68, , , 0.98, 0, 0,0,,
     -10      15   19.05      65      90     115     155     165     215     275
     290     315  349.16     365     415     465     515     565     590     615
     665     715     740     750  784.89   786.9     815     850   881.6   909.7
     915     950     965     990    1015    1065    1115    1140    1160    1215
    1265    1315    1365 1412.24    1440    1470    1515    1550    1590    1615
    1625    1665    1715    1720    1765    1795    1815    1870    1915    1965
 2018.33    2065    2115    2165    2190    2215    2235 2284.07
  460.15  460.12  460.12  460.21  460.33  460.48  460.72  460.78   460.9  460.72
  460.63  460.51  460.45  460.47  460.67  461.13  461.85  462.82  463.39  463.97
  464.96   465.7  465.98  466.08   466.4  466.41  466.51  466.57  466.51   466.4
  466.36  466.08  465.93  465.68  465.39  464.62  463.58  462.96  462.44  461.15
  460.26  459.62  459.25  459.13  459.17  459.31  459.58  459.79  459.96  460.01
  460.01  459.95   459.7  459.67  459.48  459.44  459.46  459.67  459.94  460.24
   460.4  460.27  459.87  459.19  458.77  458.22  457.77  456.79
                                         460.876 461.014  461.08 461.014 460.898
     -40     -15  -10.95      35      60      85     125     135     185     245
     260     285  319.16     335     385     435     485     535     560     585
     635     685     710     720  754.89   756.9     785     820   851.6   879.7
     885     920     935     960     985    1035    1085    1110    1130    1185
    1235    1285    1335 1382.24    1410    1440    1485    1520    1560    1585
    1595    1635    1685    1690    1735    1765    1785    1840    1885    1935
 1988.33    2035    2085    2135    2160    2185    2205 2254.07
  460.15  460.12  460.12  460.21  460.33  460.48  460.72  460.78   460.9  460.72
  460.63  460.51  460.45  460.47  460.67  461.13  461.85  462.82  463.39  463.97
  464.96   465.7  465.98  466.08   466.4  466.41  466.51  466.57  466.51   466.4
  466.36  466.08  465.93  465.68  465.39  464.62  463.58  462.96  462.44  461.15
  460.26  459.62  459.25  459.13  459.17  459.31  459.58  459.79  459.96  460.01
  460.01  459.95   459.7  459.67  459.48  459.44  459.46  459.67  459.94  460.24
   460.4  460.27  459.87  459.19  458.77  458.22  457.77  456.79
                                         460.876 461.014  461.08 461.014 460.898
Abutment Skew #Up #Dn= , 2 , 2
   786.9  815.01
   460.2  450.83
   756.9     800
   460.2  445.83
Abutment Skew #Up #Dn= , 2 , 2
  879.04   909.7
     450  460.22
     838   879.7
  446.32  460.22
BR Coef=-1 , 0 , 0 ,, 0 ,,,0.8,-1,,0,
WSPro=,,,, 1 ,,,, 0 ,,,, 0 ,,,,-1 ,-1 ,-1 , 0 , 0 , 0 , 0 , 0
Culvert=2,4,3,120,0.015,0.5,1,8,3,447.87,170,448.26,110,Exist3'x4'  , 0 ,1
     170     110
BC Culvert Barrel=1,,0
Culvert Bottom n=0.015
BC Mult= 2 ,0,603.59,0,573.25
BC Mult= 3 ,345.47,2059.17,314.62,2145.83
BR U #Sta/Elev= 85
       0  460.35      40     460      70     459  123.81  457.61  131.07  454.02
  133.25  452.89  138.95  451.42  149.86  449.96  153.54  449.07  157.35  447.85
  176.96  447.85  188.45  450.64  194.66  451.11  195.07  451.15  196.64  451.59
  199.54  452.62  204.63  455.15  204.69  455.17  204.72  455.18  204.74  455.18
  214.09  455.78  220.56  455.88  226.09  455.96  238.71  456.14   249.8  456.09
  284.39  455.84  345.47  455.89  364.78  455.69  405.87  455.81  432.31  455.78
  440.11  455.84  485.95  455.41  522.21  455.56  603.59  456.25  642.57  456.27
  682.01  455.83  776.98  455.32  790.46  455.18  829.27  447.31  854.42  447.31
  870.45  447.31  905.97  455.35  937.55  455.04  946.52   455.1  964.64  454.88
  982.33  454.92  992.28  455.09 1004.31  455.08 1012.88  455.01 1070.64  454.59
 1077.93  454.55 1088.35  454.68 1131.47  454.37  1188.4  454.38  1197.7  454.41
 1240.42  454.73 1264.92  454.63 1291.12  454.73 1311.48  454.73 1345.34  454.81
 1378.71  454.66 1397.07   454.5 1455.32  454.64 1504.35  454.39  1546.9  454.23
 1602.25  454.84 1609.84  454.86 1638.05  454.52 1643.13  454.53 1687.26  454.38
 1710.54  454.34  1727.5  454.21 1772.01     454 1779.64  453.95 1831.59  453.63
 1881.16  453.71 1920.34  453.97 1947.51   454.2 1969.51  454.47  1984.8  454.81
 2008.14  455.74 2012.24   455.7 2020.43     456 2039.88     460 2059.17     461
BR U #Mann= 5
       0    .055  123.81     .05  214.09    .055  776.98     .05  905.97    .055
BR U Banks=776.98,905.97
BR D #Sta/Elev= 78
       0  457.56    6.05  457.59    18.6  457.64   25.65  457.56   43.09  458.11
   46.06  459.14   50.54  459.03    52.1  458.54   68.74  457.06   69.85  456.95
      79  455.18     100  448.26     124  448.26     135  456.22  149.01  456.18
  151.84  456.47  161.75  456.76  167.95  456.47   177.4  456.33  184.37  456.76
  194.84  456.31  203.76  456.11  216.14  456.03  243.89  456.06  265.09  456.01
  278.18  455.62  288.36  455.85  314.62  456.33  343.87  456.38  362.57  456.36
  369.21  456.31  406.59  456.25  432.06  456.28  455.96  456.08  465.23  455.91
  474.66  455.65  489.63     456   543.1  456.26  573.25  456.35  610.34  456.22
  648.88  455.95  670.23  455.74  691.34  455.57     735  455.51  741.41  454.29
  750.55  453.39  759.18  452.27  767.24     451  776.84  449.34  784.33  447.97
  786.39  447.47  788.37     447  801.56     447  828.76  446.87  837.35     447
     840  446.81     880     455  933.74  455.78  944.53  455.96 1020.12   455.8
    1060  454.58    1170  454.54    1270  454.48    1385  454.53    1480  455.08
    1585  455.84    1685  455.23    1785  455.32    1895  454.44    1995     454
  2090.2  455.08 2106.78   455.5  2113.6  455.53 2116.82  455.88 2121.94  457.07
 2133.21     460 2138.03     461 2145.83  461.13
BR D #Mann= 5
       0    .055   69.85     .05  161.75    .055     735     .05     880    .055
BC Design=,, 0 ,, 0 ,,,,,,
BC Use User HTab Curves=0
BC User HTab FreeFlow(D)= 0

Type RM Length L Ch R = 1 ,133696  ,307.27,78.95,87.43
BEGIN DESCRIPTION:
Embankment DS face-gis xsec 7724-right overbank from filed surveys 2015
END DESCRIPTION:
XS GIS Cut Line= 6
  2438549.278126 7060862.4278184 2438556.0130213 7060185.9849456
 2438520.2903237 7059978.0791934 2438457.4184022 7059768.7439822
 2438283.0919792 7059450.8122033 2437792.2944044 7058984.3899078
#Sta/Elev= 30
       0  457.56   43.09  458.11   46.06  459.14   69.85  456.95      79  455.18
     100  448.26     124  448.26     135  456.22  161.75  456.76  278.18  455.62
  314.62  456.33  432.06  456.28  474.66  455.65  573.25  456.35     735  455.51
  767.24     451  788.37     447     840  446.81     880     455  944.53  455.96
 1020.12   455.8    1060  454.58    1385  454.53    1585  455.84    1785  455.32
    1995     454  2113.6  455.53 2116.82  455.88 2138.03     461 2145.83  461.13
#Mann= 5 ,-1,0
       0    .055       0   69.85     .05       0  161.75    .055       0
     735     .05       0     880    .055       0
#XS Ineff= 3 ,-1
       0      65   460.3     140     732   461.9     906    2150   461.9
Permanent Ineff=
       F       F       F
Bank Sta=735,880
XS Rating Curve= 0 ,0
Exp/Cntr=0.5,0.3