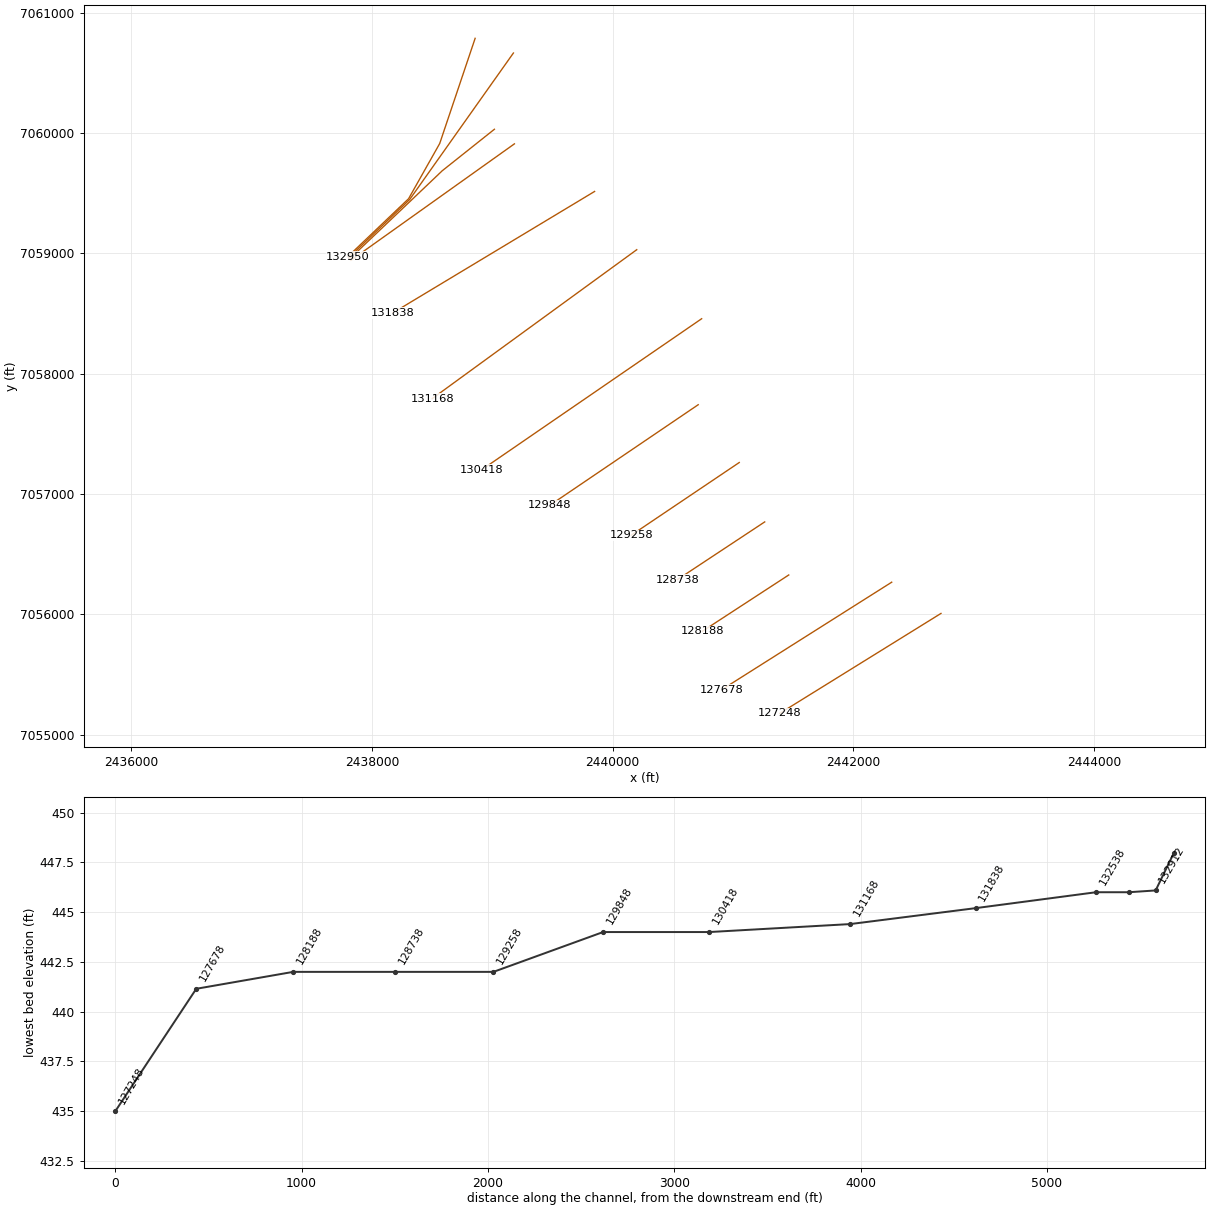
HEC-RAS study CDC_Consolidated_Model.prj: Upper Trinity CDC Consolidated Model

--- CDC_Consolidated_Model.g12 (geometry) --- (continued)

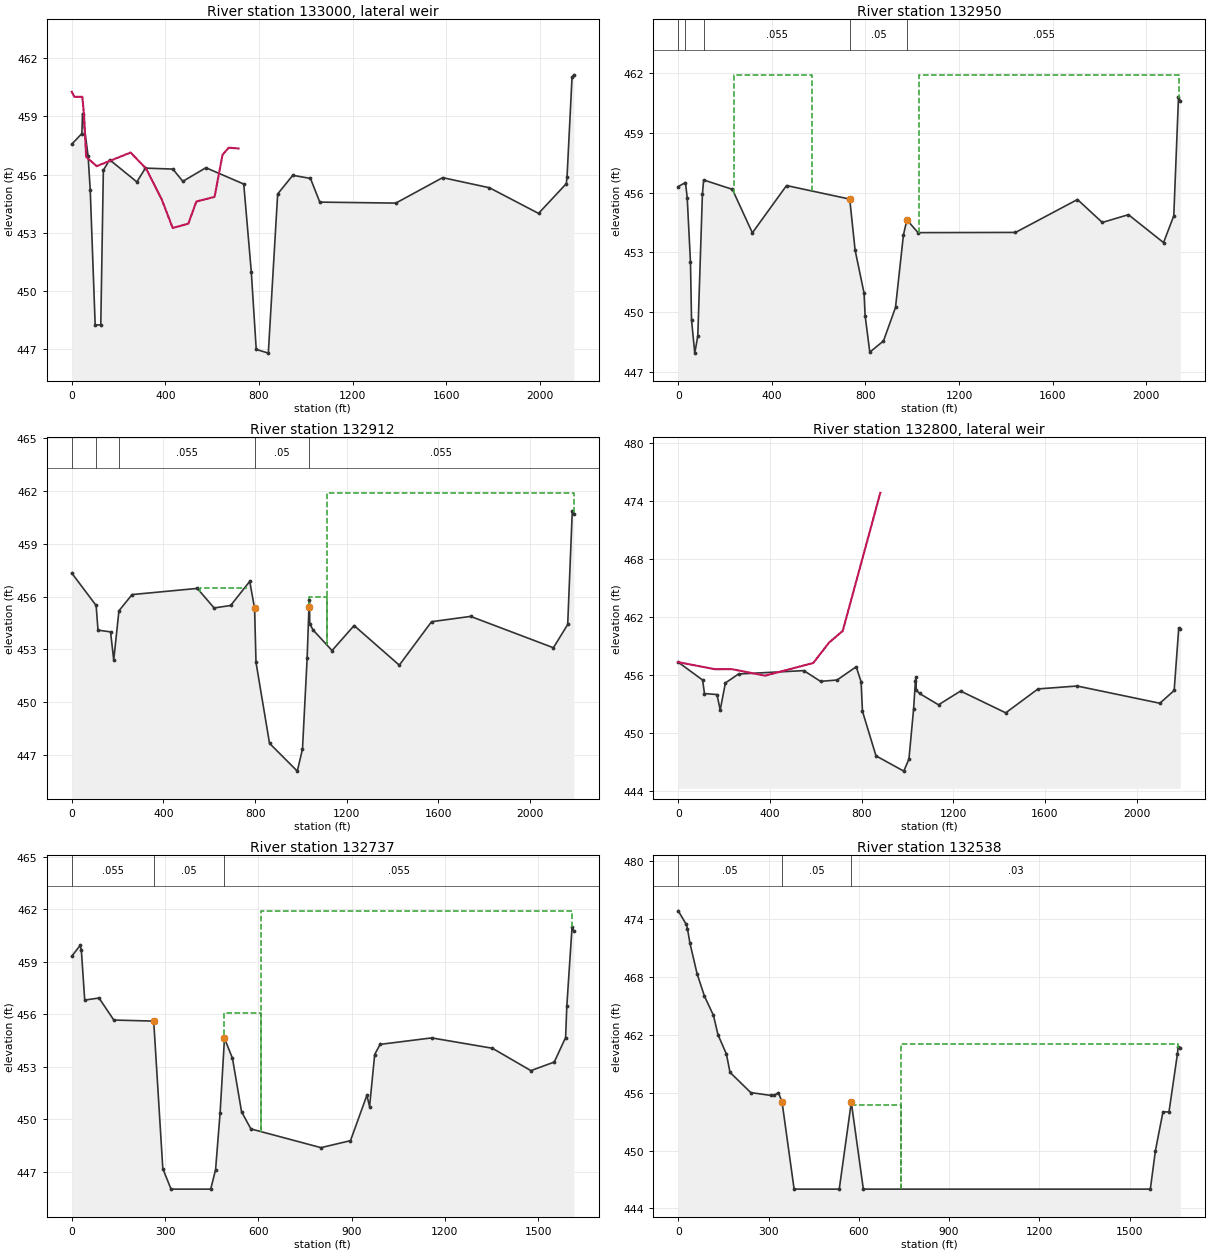
Type RM Length L Ch R = 6 ,133000  ,,,
Lateral Weir Pos= 0
Lateral Weir End=Elm Fork        ,ef4             ,139890  ,
Lateral Weir Distance=0
Lateral Weir TW Multiple XS=0
Lateral Weir WD=5
Lateral Weir Coef=2.6
Lateral Weir Is ZeroHeight=-1
LW OverFlow Method 2D=0
LW OverFlow Use Velocity Into 2D=0
Lateral Weir WSCriteria=-1
Lateral Weir Flap Gates= 0
Lateral Weir Hagers EQN= 0 ,,,,,
Lateral Weir SS=0.05,0.05,
Lateral Weir Type= 0
Lateral Weir Connection Pos and Dist= 3 ,-318
Lateral Weir SE= 18
       0  460.26   10.83     460   45.15     460   52.74     459   56.93     458
   61.14     457   61.29  456.91  106.46  456.43  251.47  457.13     318   456.3
  384.84  454.71  431.32  453.25  498.15  453.47  532.49  454.61   610.3  454.85
  644.39  457.02   670.9  457.38     713  457.34
Lateral Weir Centerline= 0
Lateral Weir HW RS User Defined=-1
Lateral Weir HW RS Station=133696,0
Lateral Weir HW RS Station=132950,318
Lateral Weir HW RS Station=132912,713
LW Div RC= 0 ,False,,

Type RM Length L Ch R = 1 ,132950  ,357.03,96.83,76.43
BEGIN DESCRIPTION:
132950 new lidar gis xsec7645,  inef based on upstream embankment
This section is lined with rock rap rip in the graded portion.
END DESCRIPTION:
XS GIS Cut Line= 4
  2438856.738141 7060787.8131382 2438562.3522475 7059913.8404767
 2438303.5758621 7059454.7291902 2437799.8278539 7058974.4827754
#Sta/Elev= 30
       0   456.3   30.94   456.5   38.34  455.74   52.33   452.5   56.79  449.62
   70.63  447.95   83.59  448.81  103.22  455.91  108.48  456.63  231.26  456.16
  316.77  453.98  462.75  456.35  732.75  455.67  755.62  453.12  793.93  450.96
  798.58  449.82  818.53     448  876.91  448.56  928.34  450.24  962.26  453.88
  977.12  454.63 1024.41  453.99 1441.03     454 1705.77  455.65 1811.86   454.5
 1923.55  454.89 2073.58  453.49 2117.32  454.83 2137.43  460.77 2145.23   460.6
#Mann= 5 ,-1,0
       0    .055       0   30.94    .045       0  108.48    .055       0
  732.75     .05       0  977.12    .055       0
#XS Ineff= 2 ,-1
     240     570   461.9    1030    2140   461.9
Permanent Ineff=
       F       F
Bank Sta=732.75,977.12
XS Rating Curve= 0 ,0
Exp/Cntr=0.5,0.3

Type RM Length L Ch R = 1 ,132912  ,530.11,144.07,109.17
BEGIN DESCRIPTION:
New Lidar xsec gis 7548- right inef based on us embankment
END DESCRIPTION:
XS GIS Cut Line= 3
  2439174.835274 7060665.7277525 2438312.9213159 7059448.8883227
 2437806.6992312 7058965.9506402
#Sta/Elev= 30
       0  457.34   106.3   455.5   114.5   454.1   169.2     454   183.1   452.4
  205.82   455.2   263.2  456.12  547.85  456.47  621.08  455.36  693.25   455.5
  776.59  456.87   797.8  455.33  803.88  452.27  862.92  447.67  984.06  446.09
 1006.71  447.34 1027.02  452.51 1034.97   455.4 1037.23  455.81 1038.41  454.47
 1052.77  454.11  1135.7  452.94 1231.97  454.36 1429.11  452.11 1569.93  454.58
 1740.45  454.88 2101.56   453.1    2164  454.42    2184  460.87 2190.81  460.72
#Mann= 5 ,-1,0
       0    .055       0   106.3    .045       0  205.82    .055       0
   797.8     .05       0 1034.97    .055       0
#XS Ineff= 3 ,-1
     560     765   456.5    1035    1115     456    1115    2200   461.9
Permanent Ineff=
       F       F       F
Bank Sta=797.8,1034.97
XS Rating Curve= 0 ,0
Exp/Cntr=0.3,0.1

Type RM Length L Ch R = 6 ,132800  ,,,
Lateral Weir Pos= 0
Lateral Weir End=Elm Fork        ,ef4             ,139643  ,
Lateral Weir Distance=0
Lateral Weir TW Multiple XS=-1
Lateral Weir WD=5
Lateral Weir Coef=2.6
Lateral Weir Is ZeroHeight=-1
LW OverFlow Method 2D=0
LW OverFlow Use Velocity Into 2D=0
Lateral Weir WSCriteria=-1
Lateral Weir Flap Gates= 0
Lateral Weir Hagers EQN= 0 ,,,,,
Lateral Weir SS=0.05,0.05,
Lateral Weir Type= 0
Lateral Weir Connection Pos and Dist= 3 ,0
Lateral Weir SE= 8
       0  457.34  161.86  456.61  233.56  456.62   379.2  455.95  589.29  457.26
     658  459.36  717.83  460.57  881.73  474.83
Lateral Weir Centerline= 0
Lateral Weir HW RS User Defined=-1
Lateral Weir HW RS Station=132912  ,0
Lateral Weir HW RS Station=132737  ,658
Lateral Weir HW RS Station=132538  ,882
Lateral Weir TW RS User Defined=-1
Lateral Weir TW RS Station=139643  ,0
Lateral Weir TW RS Station=138514  ,882
LW Div RC= 0 ,False,,

Type RM Length L Ch R = 1 ,132737  ,202.12,175.82,171.29
BEGIN DESCRIPTION:
New Lidar xsec gis 7404- inef at 610 based on upstream existing embankment
END DESCRIPTION:
XS GIS Cut Line= 4
  2439016.964527 7060032.1604501 2438582.7101464 7059686.6047107
 2438324.6030511 7059440.7108456 2437814.5286119 7058956.1986912
#Sta/Elev= 30
       0  459.31   26.89  459.92   30.74  459.67   41.67   456.8   87.62  456.92
  135.26  455.66  263.55   455.6  292.85  447.17  319.31     446  446.88     446
  462.56  447.11  477.14  450.36  491.19  454.62  516.99  453.47  546.12  450.42
  576.18  449.44  801.59  448.37  896.55  448.77  949.21  451.36   957.9  450.72
  974.36  453.69  991.76  454.27 1157.65  454.64 1352.72  454.05 1476.74  452.77
  1551.9  453.26 1588.45  454.66 1592.36  456.46 1609.23  460.98 1614.96  460.72
#Mann= 3 ,0,0
       0    .055       0  263.55     .05       0  491.19    .055       0
#XS Ineff= 2 ,-1
  490.37     610 456.037     610    1610   461.9
Permanent Ineff=
       F       F
Bank Sta=263.55,491.19
XS Rating Curve= 0 ,0
Exp/Cntr=0.3,0.1

Type RM Length L Ch R = 1 ,132538  ,666.33,646.78,633.1
BEGIN DESCRIPTION:
132538-gis 7228 Normal pool 446
NOTE: Inef at 741 from Corp ROW existing embankment
NOTE: topo east of railroad tracks updated Feb 2002 by Freese & Nichols, Inc.
END DESCRIPTION:
XS GIS Cut Line= 2
  2439183.281123 7059910.8834616 2437824.6214395 7058943.0658435
#Sta/Elev= 26
       0  474.83   26.83  473.42   30.72  472.97   38.89  471.48   62.49  468.33
      87     466     117     464     132     462     160     460     172   458.1
     241     456     309   455.7     318   455.7     333     456     345     455
     385     446     535     446     575     455     615     446  1568.5     446
  1585.5     450  1610.5     454  1630.5     454  1658.5     460 1660.97  460.73
 1668.12  460.66
#Mann= 3 ,0,0
       0     .05       0     345     .05       0     575     .03       0
#XS Ineff= 2 ,-1
     575     741 454.738     741    1660     461
Permanent Ineff=
       F       F
Bank Sta=345,575
XS Rating Curve= 0 ,0
Exp/Cntr=0.3,0.1

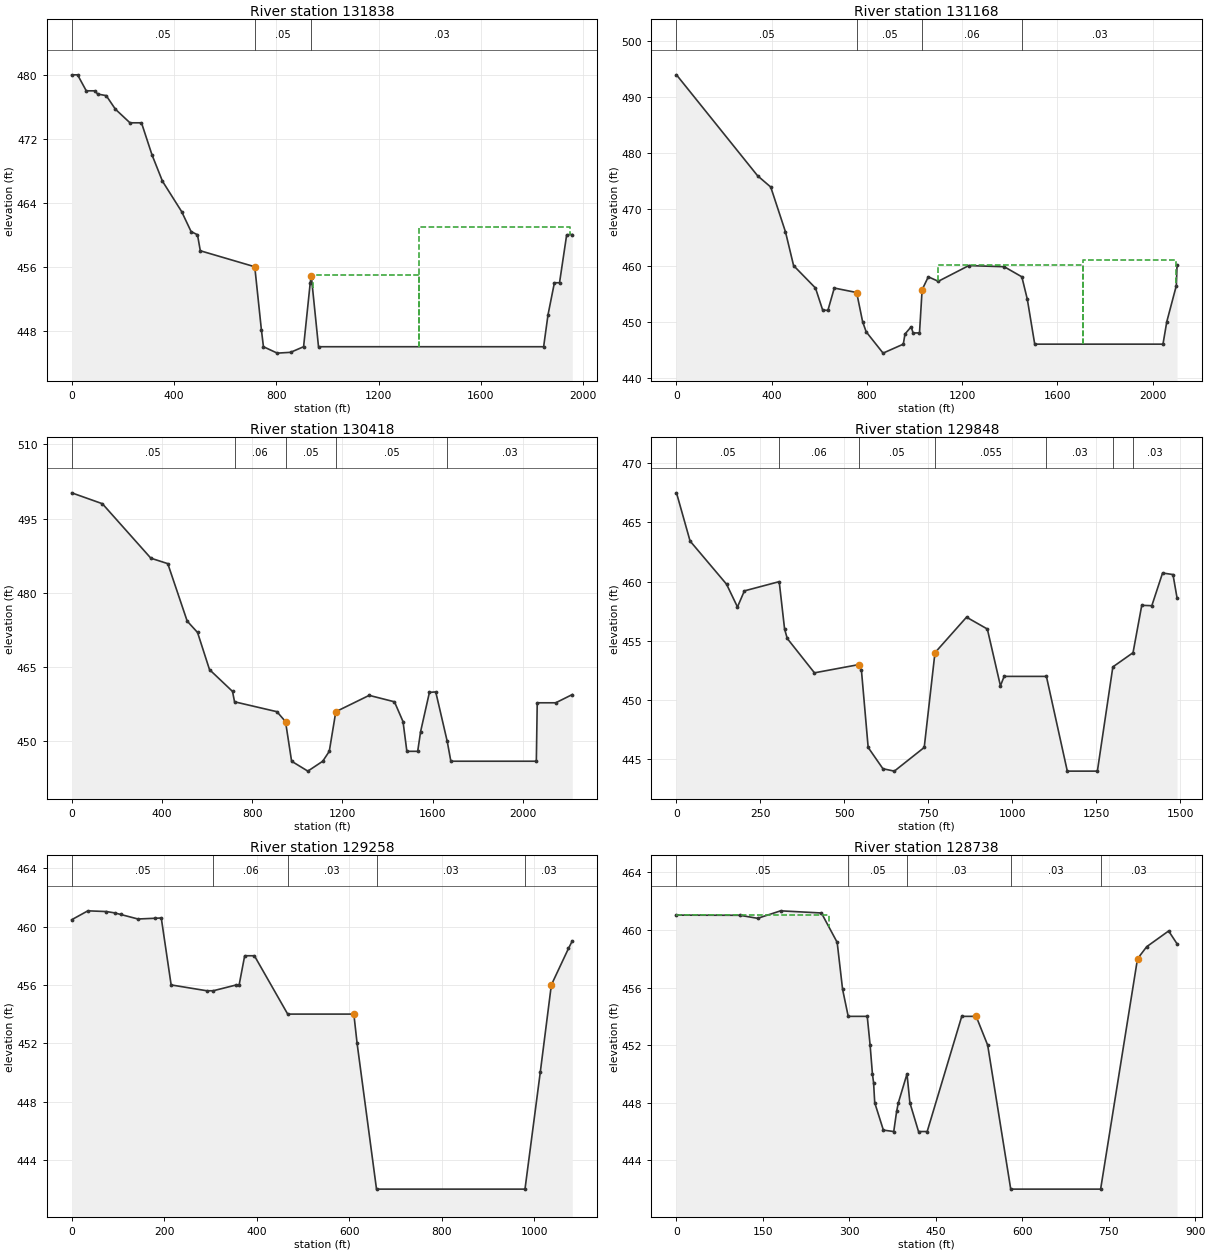
Type RM Length L Ch R = 1 ,131838  ,663.78,673.18,689.22
BEGIN DESCRIPTION:
131838- inef at 1360 based on upstream existing embankment, linear channel n value changed from .03 to .05 based on image
n value changed to CDC 12/18/15
131838
NOTE: topo east of railroad tracks updated Feb 2002 by Freese & Nichols, Inc.
END DESCRIPTION:
XS GIS Cut Line= 2
2439849.429397727059515.168045732438172.092857397058505.50569497
#Sta/Elev= 30
       0     480      23     480      57     478      92     478     101   477.6
     135   477.4     171   475.7     228     474     273     474     314     470
     355   466.7     430   462.9     467   460.4     492     460     503     458
     716     456     742   448.1     750     446     804   445.2     856   445.3
     907     446     933     454     937   454.9  965.33     446 1845.86     446
    1863     450    1888     454    1908     454    1936     460 1957.77  460.03
#Mann= 3 ,-1,0
       0     .05       0     716     .05       0     937     .03       0
#XS Ineff= 2 ,-1
  941.88    1360     455    1360    1950     461
Permanent Ineff=
       F       F
Bank Sta=716,937
XS Rating Curve= 0 ,0
Exp/Cntr=0.3,0.1

Type RM Length L Ch R = 1 ,131168  ,757.56,756.14,750.47
BEGIN DESCRIPTION:
131168-inef at 1710 based on upstream existing embankment, linear channel n value changed from .03 to .05 based on image
n values updated to CDC 12/18/15 BG
131168
NOTE: topo east of railroad tracks updated Feb 2002 by Freese & Nichols, Inc.
END DESCRIPTION:
XS GIS Cut Line= 2
2440199.904090467059031.098147742438499.669301977057793.31683065
#Sta/Elev= 30
       0     494     341     476     396     474     458     466     492     460
     584     456     614   452.1     636     452     663     456     757   455.2
     782     450     797   448.2     868   444.4     953     446     960   447.8
     986   449.1     994     448    1021     448    1032   455.7    1058     458
    1100   457.2    1228     460    1377   459.8    1451     458    1474     454
 1505.11     446    2044     446    2060     450    2100  456.42 2103.07  460.09
#Mann= 4 ,-1,0
       0     .05       0     757     .05       0    1032     .06       0
    1451     .03       0
#XS Ineff= 2 ,-1
    1100    1710 460.087    1710    2100     461
Permanent Ineff=
       F       F
Bank Sta=757,1032
XS Rating Curve= 0 ,0
Exp/Cntr=0.3,0.1

Type RM Length L Ch R = 1 ,130418  ,570.32,569.38,569.31
BEGIN DESCRIPTION:
130418 linear channel n value changed from .03 to .05 based on image
NOTE: topo east of railroad tracks updated Feb 2002 by Freese & Nichols, Inc.
END DESCRIPTION:
XS GIS Cut Line= 2
2440739.29769672 7058457.39719542438909.85778606 7057201.1398654
#Sta/Elev= 30
       0   500.2     136     498     351     487     426   485.9     512   474.3
     558     472     611   464.5     713   460.1     722     458     910     456
     948     454     975     446    1047     444    1113     446    1142     448
    1171     456    1319   459.3    1431     458    1469     454    1486     448
    1534     448    1547     452    1586   459.9    1614     460    1665     450
 1681.01     446    2060     446    2064   457.8    2146   457.8 2219.24  459.46
#Mann= 5 ,-1,0
       0     .05       0     722     .06       0     948     .05       0
    1171     .05       0    1665     .03       0
#XS Ineff= 2 , 0
                            1338          458.25
Permanent Ineff=
       F       F
Bank Sta=948,1171
XS Rating Curve= 0 ,0
Exp/Cntr=0.3,0.1

Type RM Length L Ch R = 1 ,129848  ,587.39,588.53,586.79
BEGIN DESCRIPTION:
129848- linear channel n value changed from .03 to .05 based on image
NOTE: topo east of railroad tracks updated Feb 2002 by Freese & Nichols, Inc.
END DESCRIPTION:
XS GIS Cut Line= 2
2440710.707858897057742.65321806 2439476.55055037056905.84091531
#Sta/Elev= 30
       0   467.5   40.48  463.43  149.23  459.78  181.67  457.86  202.25  459.22
     306     460     322     456     330   455.2     411   452.3     544     453
     551   452.5     571     446     615   444.2     649     444     738     446
     770     454     864     457     926     456     965   451.2     976     452
 1101.96     452  1164.2     444  1253.8     444 1299.89   452.8    1360     454
    1386     458    1416  457.97    1448  460.73    1479   460.6 1491.11  458.63
#Mann= 7 ,-1,0
       0     .05       0     306     .06       0     544     .05       0
     770    .055       0 1101.96     .03       0 1299.89    .055       0
    1360     .03       0
#XS Ineff= 2 ,-1
   11.23  311.24458.1781  897.69  1488.8455.5986
Permanent Ineff=
       F       F
Bank Sta=544,770
XS Rating Curve= 0 ,0
Exp/Cntr=0.3,0.1

Type RM Length L Ch R = 1 ,129258  ,524.18,527.87,522.14
BEGIN DESCRIPTION:
129258- ROB pond n=.02 changed to n=.03 es jan2016
NOTE: topo east of railroad tracks updated Feb 2002 by Freese & Nichols, Inc.
END DESCRIPTION:
XS GIS Cut Line= 2
2441051.878764477057262.34545164 2440154.15155737056658.05040039
#Sta/Elev= 24
       0  460.47      35  461.08   75.18  461.03   92.62  460.94  106.07  460.83
  143.25  460.52  180.33  460.57  193.67  460.59     215     456     292   455.6
     306   455.6     356     456     362     456     374     458     395     458
     467     454     610     454     617     452     659     442     980     442
    1013     450    1037     456    1074   458.5 1082.17  459.01
#Mann= 5 ,-1,0
       0     .05       0     306     .06       0     467     .03       0
     659     .03       0     980     .03       0
Bank Sta=610,1037
XS Rating Curve= 0 ,0
Exp/Cntr=0.5,0.3

Type RM Length L Ch R = 1 ,128738  ,504.83,546.51,475.07
BEGIN DESCRIPTION:
128738-ROB pond n=.02 changed to n=.03 es jan2016  left overbank changed to .05
128738
NOTE: topo east of railroad tracks updated Feb 2002 by Freese & Nichols, Inc.
END DESCRIPTION:
XS GIS Cut Line= 2
2441263.442973887056768.695848392440538.744292057056289.86675356
#Sta/Elev= 30
       0  461.03  109.85  461.02   140.9  460.81  180.67  461.33   251.5  461.18
  278.82  459.14  288.22  455.88     298     454     331     454     336     452
     340     450     342   449.4     344     448     359   446.1     377     446
     382   447.4     385     448     400     450     405     448     420     446
     435     446     495     454     520     454     540     452     580     442
     736     442     800     458     816  458.84     854  459.93   868.6  459.04
#Mann= 5 ,-1,0
       0     .05       0     298     .05       0     400     .03       0
     580     .03       0     736     .03       0
#XS Ineff= 2 , 0
          264.31461.0323
Permanent Ineff=
       F       F
Bank Sta=520,800
XS Rating Curve= 0 ,0
Exp/Cntr=0.3,0.1

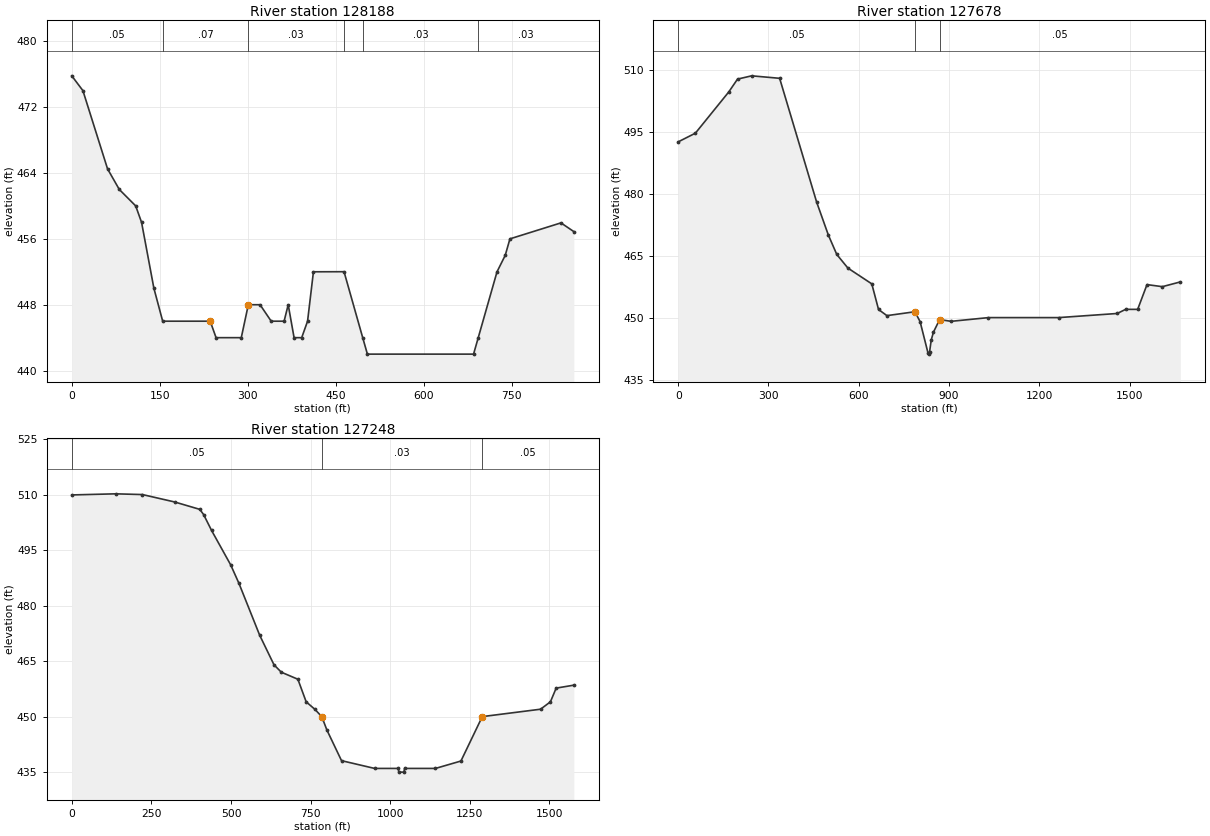
Type RM Length L Ch R = 1 ,128188  ,539.15,520.5,519.99
BEGIN DESCRIPTION:
128188 -ROB pond n=.02 changed to n=.03 es jan2016
NOTE: topo east of railroad tracks updated Feb 2002 by Freese & Nichols, Inc.
END DESCRIPTION:
XS GIS Cut Line= 2
2441463.355303727056327.755129232440746.263233977055860.35383306
#Sta/Elev= 30
       0   475.8      19     474      61   464.5      81     462     109     460
     119     458     140     450     155     446     236     446     246     444
     289     444     301     448     321     448     340     446     362     446
     369     448     379     444     392     444     402     446     412     452
  464.19  452.01     496     444     504     442     685     442     693     444
     725     452     739     454     747     456     834  457.94  855.97  456.88
#Mann= 6 ,-1,0
       0     .05       0     155     .07       0     301     .03       0
  464.19     .03       0     496     .03       0     693     .03       0
Bank Sta=236,301
XS Rating Curve= 0 ,0
Exp/Cntr=0.3,0.1

Type RM Length L Ch R = 1 ,127678  ,460.35,434.56,444.55
BEGIN DESCRIPTION:
n updated to CDC 12/18/15
127678
NOTE: topo east of railroad tracks updated Feb 2002 by Freese & Nichols, Inc.
END DESCRIPTION:
XS GIS Cut Line= 2
2442318.95529856 7056267.6732284 2440908.58115087055375.75801748
#Sta/Elev= 30
       0   492.6      57   494.7     168   504.7     197   507.8     244   508.6
     337     508     460     478     499     470     527   465.3     564     462
  643.31  458.18  665.73  451.97   693.5  450.48  786.54  451.42  803.87  449.03
  829.85  441.51  832.95  441.15  835.24  441.61  840.97   444.6  848.23  446.48
  868.85  449.53     907   449.1    1031     450    1264     450    1459     451
    1487     452    1527     452    1558     458    1609   457.5 1668.73  458.65
#Mann= 3 ,-1,0
       0     .05       0  786.54     .03       0  868.85     .05       0
Bank Sta=786.54,868.85
XS Rating Curve= 0 ,0
Exp/Cntr=0.3,0.1

Type RM Length L Ch R = 1 ,127248  ,447.37,459.41,453.01
BEGIN DESCRIPTION:
n updated to CDC 12/18/15 BG
127248
NOTE: topo east of railroad tracks updated Feb 2002 by Freese & Nichols, Inc.
END DESCRIPTION:
XS GIS Cut Line= 2
2442728.531579147056008.112067732441388.608734067055177.40408348
#Sta/Elev= 30
       0   509.9     138   510.2     222     510     323     508     402     506
     414   504.6     439   500.3     499     491     525     486     590     472
     635     464     658     462     710   460.1     736     454     763     452
     785     450     801   446.4     847   438.1     951     436    1025     436
    1027     435    1043     435    1045     436    1142     436    1222     438
    1289     450    1472     452    1503     454    1521   457.7 1576.54   458.5
#Mann= 3 ,-1,0
       0     .05       0     785     .03       0    1289     .05       0
Bank Sta=785,1289
XS Rating Curve= 0 ,0
Exp/Cntr=0.3,0.1