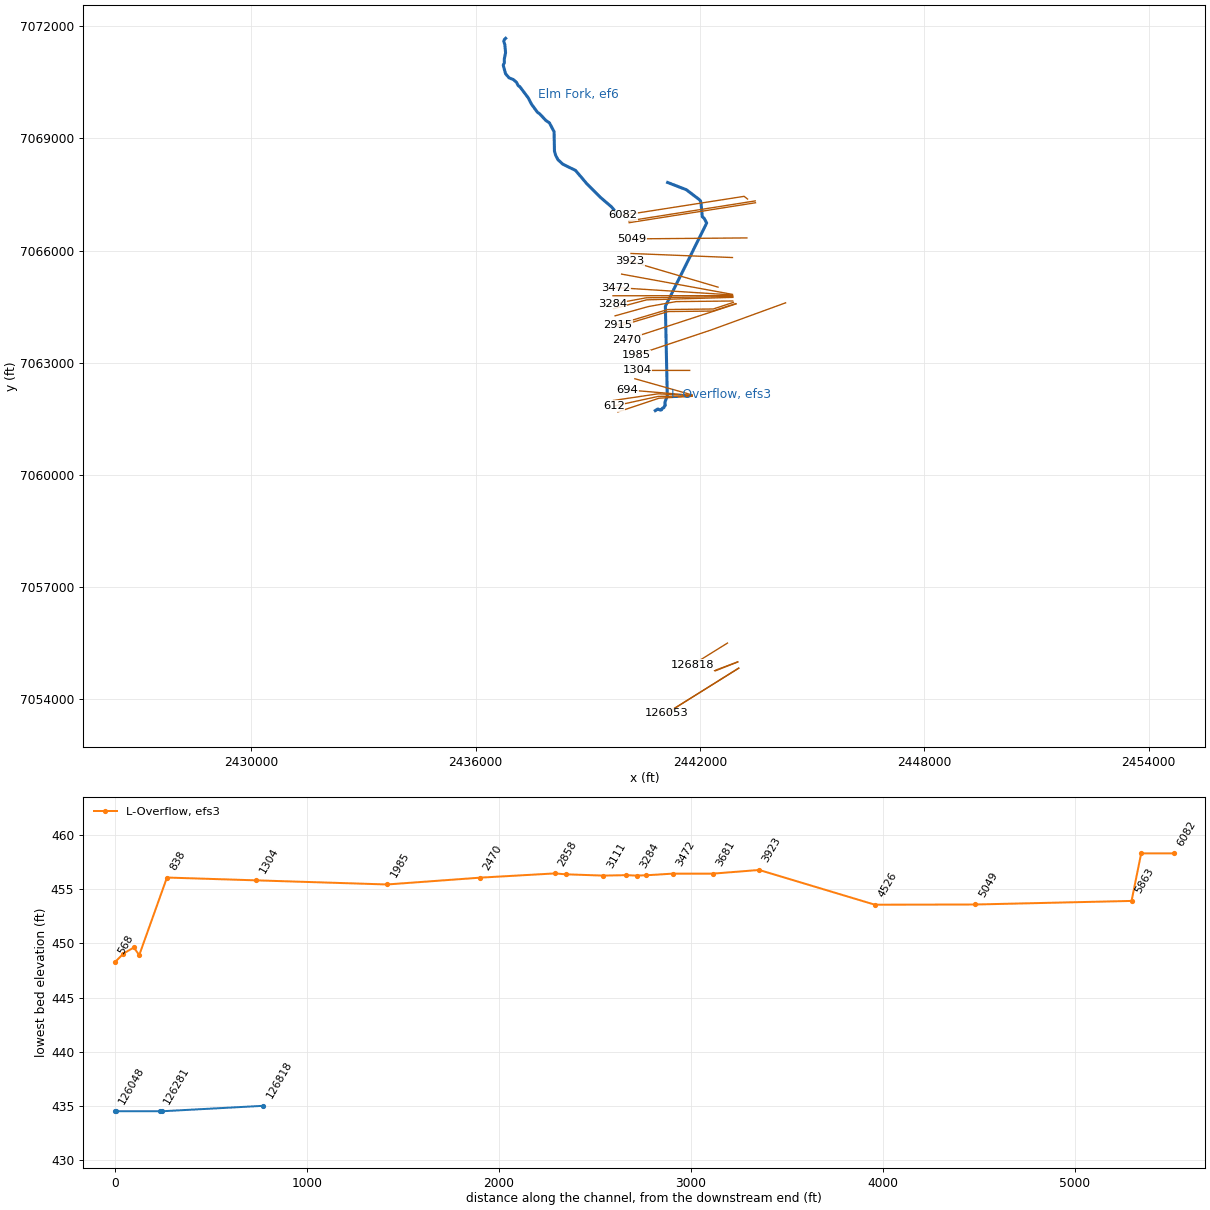
HEC-RAS study CDC_Consolidated_Model.prj: Upper Trinity CDC Consolidated Model

--- CDC_Consolidated_Model.g12 (geometry) --- (continued)

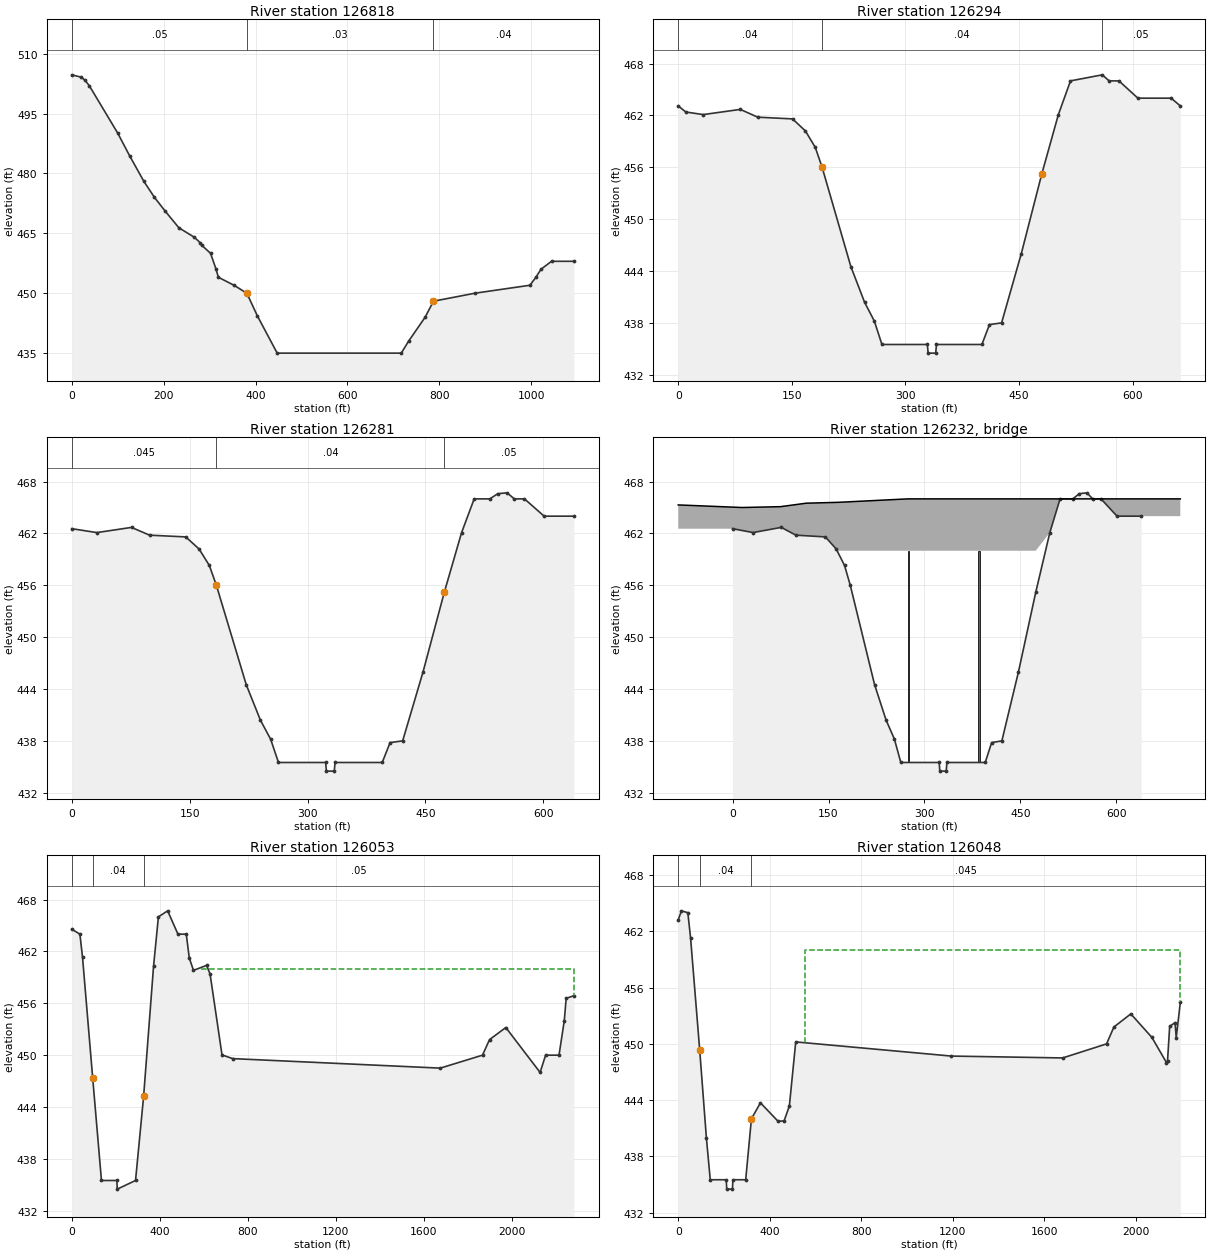
Type RM Length L Ch R = 1 ,126818  ,550.96,524.39,586.6
BEGIN DESCRIPTION:
126818
NOTE: topo east of railroad tracks updated Feb 2002 by Freese & Nichols, Inc.
END DESCRIPTION:
XS GIS Cut Line= 2
2442734.430189397055501.736768142441806.327058727054925.27991581
#Sta/Elev= 30
       0   504.7      21   504.1      29   503.3      38     502     100   490.1
     126   484.4     157     478     180     474     203   470.6     233   466.4
     267     464     279   462.7     283     462     302     460     314     456
     319     454     353     452     381     450     404   444.3     447     435
     717     435     733     438     769     444     787     448     877     450
     997     452    1010     454    1021     456    1044     458 1092.56     458
#Mann= 3 ,-1,0
       0     .05       0     381     .03       0     787     .04       0
Bank Sta=381,787
XS Rating Curve= 0 ,0
Exp/Cntr=0.3,0.1

Type RM Length L Ch R = 1 ,126294  ,9.13,12.75,17.92
BEGIN DESCRIPTION:
n values changed to CDC 12/18/15
126293
NOTE: topo east of railroad tracks updated Feb 2002 by Freese & Nichols, Inc.
END DESCRIPTION:
XS GIS Cut Line= 2
2443007.296441567055000.38639289 2442387.41283887054765.12800515
#Sta/Elev= 30
       0   463.1      10   462.4      33   462.1      82   462.7     105   461.8
     151   461.6     168   460.2     181   458.3     190     456     228   444.5
     246   440.4     259   438.2     269   435.5     329   435.5     330   434.5
     340   434.5     341   435.5     401   435.5     411   437.8     427     438
     453     446     480   455.2     502   462.1     518     466     560   466.7
     569     466     582     466     607     464     651     464  663.02   463.1
#Mann= 3 ,-1,0
       0     .04       0     190     .04       0     560     .05       0
Bank Sta=190,480
XS Rating Curve= 0 ,0
Exp/Cntr=0.5,0.3

Type RM Length L Ch R = 1 ,126281  ,188.63,228.43,238.43
BEGIN DESCRIPTION:
126292
NOTE: topo east of railroad tracks updated Feb 2002 by Freese & Nichols, Inc.
END DESCRIPTION:
XS GIS Cut Line= 2
2443009.446371637054994.521247152442414.756616137054761.22184497
#Sta/Elev= 30
       0  462.55      32   462.1      76   462.7      99   461.8     145   461.6
     162   460.2     175   458.3     184     456     222   444.5     240   440.4
     253   438.2     263   435.5     323   435.5     324   434.5     334   434.5
     335   435.5     395   435.5     405   437.8     421     438     447     446
     474   455.2     496   462.1     512     466     532     466     542   466.6
     554   466.7     563     466     576     466     601     464  638.81     464
#Mann= 3 ,0,0
       0    .045       0     184     .04       0     474     .05       0
Bank Sta=184,474
XS Rating Curve= 0 ,0
Exp/Cntr=0.5,0.3

Type RM Length L Ch R = 3 ,126232  ,,,
BEGIN DESCRIPTION:
Hebron Parkway
END DESCRIPTION:
Node Name=Hebron Parkway
Bridge Culvert--1,0,-1,-1, 0
Deck Dist Width WeirC Skew NumUp NumDn MinLoCord MaxHiCord MaxSubmerge Is_Ogee
1,118,2.6,0, 13, 13, , , 0.95, 0, 0,0,,
     -85      15      75     115     165     165     274   276.5     384   386.5
     500     500     700
   465.3     465   465.1   465.5   465.6   465.6     466     466     466     466
     466     466     466
                                             460     460     460     460     460
     460
    -303    -203    -143    -103     -53     -53      56    58.5     166   168.5
     382     382     582
   465.3     465   465.1   465.5   465.6   465.6     466     466     466     466
     466     466     466
                                             460     460     460     460     460
     460
Pier Skew, UpSta & Num, DnSta & Num=  ,275.25, 2 ,175.25, 2 , 0 , 0 , 0 ,,
     2.5     2.5
       0     461
     2.5     2.5
       0     461
Pier Skew, UpSta & Num, DnSta & Num=  ,385.25, 2 ,285.25, 2 , 0 , 0 , 0 ,,
     2.5     2.5
       0     461
     2.5     2.5
       0     461
BR Coef=-1 , 0 , 0 ,, 0 ,,,0.8,-1,,1,
WSPro=,,,, 1 ,,,, 0 ,,,, 0 ,,,,-1 ,-1 ,-1 , 0 , 0 , 0 , 0 , 0
BC Design=,, 0 ,, 0 ,,,,,,
BC HTab HWMax=465.84
BC Use User HTab Curves=0
BC User HTab FreeFlow(D)= 0

Type RM Length L Ch R = 1 ,126053  ,5.12,5.17,4.82
BEGIN DESCRIPTION:
126172
NOTE: topo east of railroad tracks updated Feb 2002 by Freese & Nichols, Inc.
END DESCRIPTION:
XS GIS Cut Line= 2
 2443033.24619287054832.836531152441097.890155397053621.03416473
#Sta/Elev= 30
       0  464.58      37     464      49   461.3      95   447.4     135   435.5
     205   435.5     207   434.5     290   435.5     327   445.3     372   460.3
     394     466     436   466.7     483     464  520.81     464  534.37  461.25
  553.56  459.81  613.23  460.39  629.03  459.39  683.25  450.03     732   449.6
    1676   448.5    1868     450    1900   451.8    1974   453.2    2130     448
    2155     450    2216     450    2240     454 2248.49  456.57 2283.43  456.88
#Mann= 3 ,0,0
       0    .045       0      95     .04       0     327     .05       0
#XS Ineff= 2 , 0
                          585.53             460
Permanent Ineff=
       F       F
Bank Sta=95,327
XS Rating Curve= 0 ,0
Exp/Cntr=0.5,0.3

Type RM Length L Ch R = 1 ,126048  ,0,0,0
BEGIN DESCRIPTION:
126171
NOTE: topo east of railroad tracks updated Feb 2002 by Freese & Nichols, Inc.
END DESCRIPTION:
XS GIS Cut Line= 2
 2443035.89776237054828.597366392441179.825687057053667.61707681
#Sta/Elev= 30
       0  463.24      14   464.2      42     464      54   461.3      94   449.3
     123     440     140   435.5     210   435.5     212   434.5     237   434.5
     239   435.5     295   435.5     320     442  359.51  443.71  436.55  441.74
  462.81  441.78  485.94  443.37   513.8  450.21    1194   448.7    1681   448.5
    1873     450    1905   451.8    1979   453.2    2071   450.7    2135     448
 2139.43  448.15 2148.96  451.87 2172.42  452.27 2177.58  450.66 2195.44  454.42
#Mann= 3 ,0,0
       0    .045       0      94     .04       0     320    .045       0
#XS Ineff= 2 , 0
                           555.1             460
Permanent Ineff=
       F       F
Bank Sta=94,320
XS Rating Curve= 0 ,0
Exp/Cntr=0.5,0.3

River Reach=L-Overflow      ,efs3
Reach XY= 30
  2441132.601191 7067821.9862019 2441633.6081323 7067627.9342176
 2441978.0504044 7067366.1845525 2442012.0095017 7067328.6972373
 2442026.0001758 7067272.1712325 2442027.7390175 7067253.4465324
 2442060.1428241   7066904.44559 2442110.3671331 7066862.8731666
 2442178.0756591 7066737.8730885 2441072.8695361 7064509.1721653
 2441123.9448933 7062096.5897201 2441101.3757127 7062049.7148139
 2441080.5424211 7061997.6312566 2441063.1812353 7061949.0201334
 2441058.8410209 7061925.5828443 2441063.1812353 7061896.0687957
 2441072.7297726 7061864.8188582 2441059.7088013 7061846.5898921
 2441044.0838326 7061826.6243808 2441038.8755096 7061810.9994121
 2441027.5907553 7061793.6382263 2440996.3408178 7061786.6940145
 2440979.8477406 7061767.5966117 2440971.1673117 7061741.5549972
 2440950.3340201 7061732.0064598 2440928.6326199 7061734.6104572
 2440893.0421399 7061755.4437489 2440869.1707966 7061763.6904516
 2440808.4376503 7061722.5186179 2440803.7829693 7061719.6372299

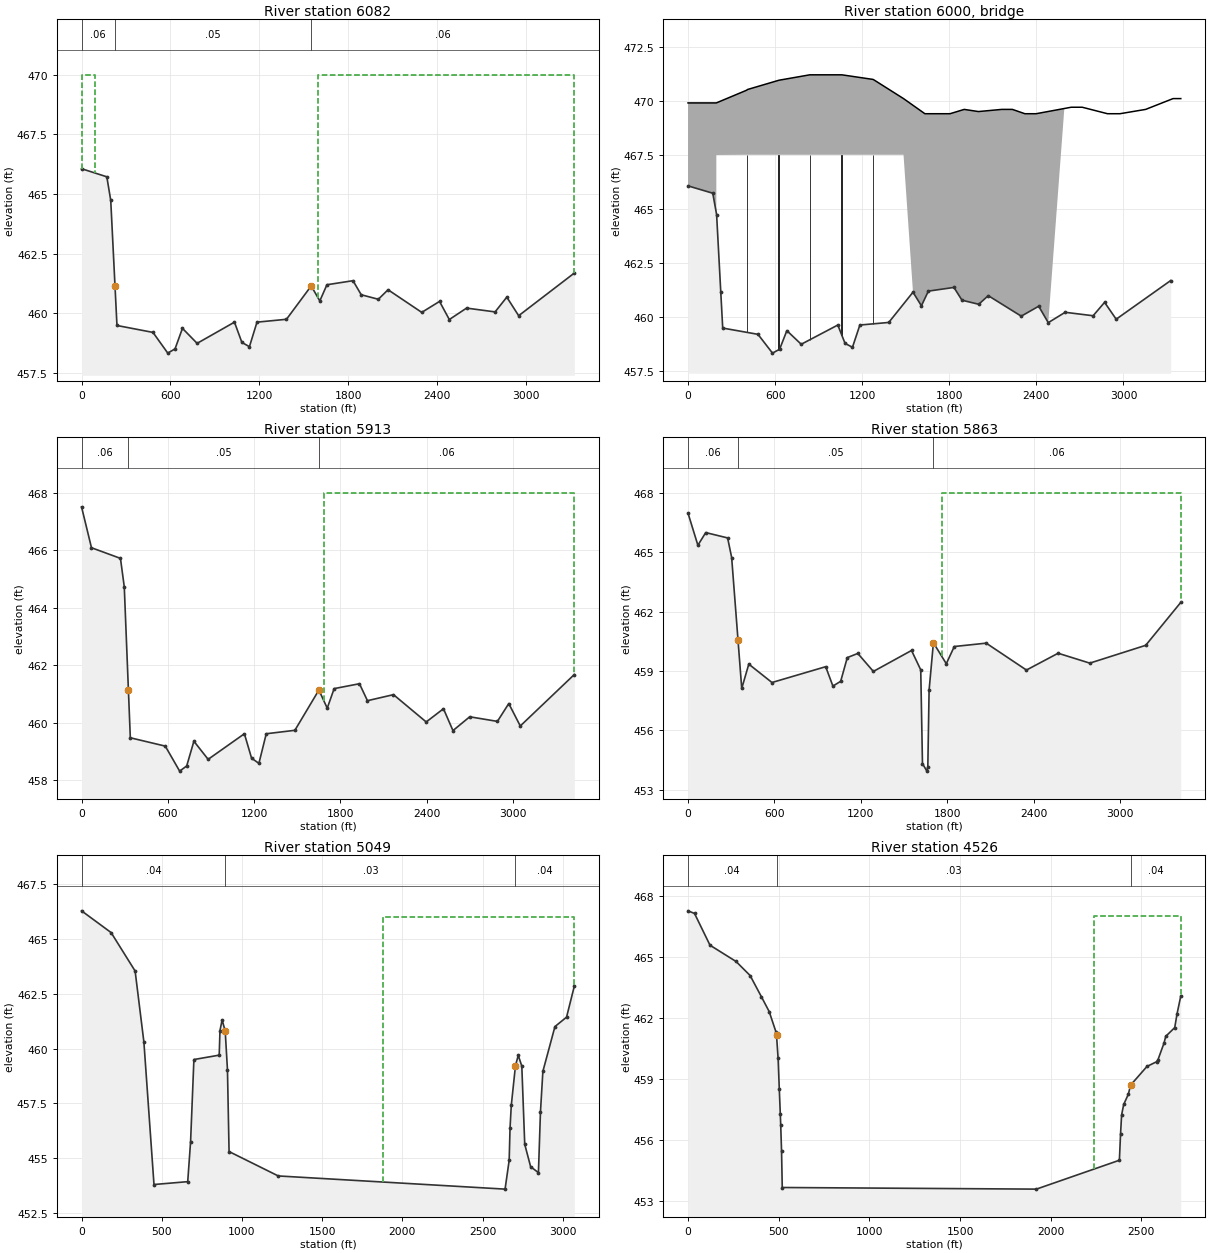
Type RM Length L Ch R = 1 ,6082    ,174.88,169.26,333.85
BEGIN DESCRIPTION:
Lidar XS
END DESCRIPTION:
XS GIS Cut Line= 3
2443271.582002227067378.614261062443180.212762397067451.13806614
2439941.11589414 7066945.5649303
#Sta/Elev= 30
       0  466.06   170.5  465.72     197  464.73  225.72  461.14     239  459.48
     482  459.19     582  458.32     631   458.5     681  459.36     780  458.73
    1032  459.62    1082  458.77    1133  458.59    1184  459.62    1383  459.74
    1550  461.14    1608  460.51    1656  461.19    1832  461.36  1887.5  460.77
    2003  460.58  2068.5  460.98    2296  460.03    2416  460.49    2482  459.73
  2598.5  460.21    2791  460.05    2870  460.67    2950  459.89 3325.62  461.68
#Mann= 3 ,0,0
       0     .06       0  225.72     .05       0    1550     .06       0
#XS Ineff= 2 , 0
              90     470    1595             470
Permanent Ineff=
       F       F
Bank Sta=225.72,1550
XS Rating Curve= 0 ,0
Exp/Cntr=0.5,0.3

Type RM Length L Ch R = 3 ,6000    ,,,
BEGIN DESCRIPTION:
SH 121
END DESCRIPTION:
Node Name=SH 121
Bridge Culvert--1,0,-1,-1, 0
Deck Dist Width WeirC Skew NumUp NumDn MinLoCord MaxHiCord MaxSubmerge Is_Ogee
30,86,2.6,0, 31, 31, , , 0.95, 0, ,,,
       0     195     195   404.5   409.5   621.5   626.5   838.5   843.5  1055.5
  1060.5  1272.5  1277.5  1484.8  1484.8    1632    1805    1903    2001    2161
    2235    2321    2398    2640    2716    2890    2976    3153    3342    3395
    3395
   469.9   469.9   469.9  470.49  470.52  470.94  470.95   471.2   471.2   471.2
   471.2  470.99  470.98   470.1   470.1   469.4   469.4   469.6   469.5   469.6
   469.6   469.4   469.4   469.7   469.7   469.4   469.4   469.6   470.1   470.1
   470.1
                  467.49   467.5   467.5   467.5   467.5   467.5   467.5   467.5
   467.5   467.5   467.5   467.5
       0     297     297     506     511     723     728     940     945    1157
    1162    1374    1379    1587    1587    1734    1907    2005    2103    2263
    2337    2423    2500    2742    2818    2992    3078    3255    3444    3490
    3490
   469.9   469.9   469.9  470.49  470.52  470.94  470.95   471.2   471.2   471.2
   471.2  470.99  470.98   470.1   470.1   469.4   469.4   469.6   469.5   469.6
   469.6   469.4   469.4   469.7   469.7   469.4   469.4   469.6   470.1   470.1
   470.1
                  467.49   467.5   467.5   467.5   467.5   467.5   467.5   467.5
   467.5   467.5   467.5   467.5
Pier Skew, UpSta & Num, DnSta & Num=  ,407, 2 ,509, 2 , 0 , 0 , 0 ,,
       5       5
     455     468
       5       5
     455     468
Pier Skew, UpSta & Num, DnSta & Num=  ,624, 2 ,726, 2 , 0 , 0 , 0 ,,
       5       5
     455     468
       5       5
     455     468
Pier Skew, UpSta & Num, DnSta & Num=  ,841, 2 ,943, 2 , 0 , 0 , 0 ,,
       5       5
     455     468
       5       5
     455     468
Pier Skew, UpSta & Num, DnSta & Num=  ,1058, 2 ,1160, 2 , 0 , 0 , 0 ,,
       5       5
     455     468
       5       5
     455     468
Pier Skew, UpSta & Num, DnSta & Num=  ,1275, 2 ,1377, 2 , 0 , 0 , 0 ,,
       5       5
     455     468
       5       5
     455     468
BR Coef= 1 , 0 , 0 ,1.05, 0 ,,,0.8,-1,0.5,1,
WSPro=,,,, 1 ,,,, 0 ,,,, 0 ,,,,-1 ,-1 ,-1 , 0 , 0 , 0 , 0 , 0
BC Design=,, 0 ,, 0 ,,,,,,
BC HTab HWMax=470.1
BC Use User HTab Curves=0
BC User HTab FreeFlow(D)= 0

Type RM Length L Ch R = 1 ,5913    ,52.3,50.1,52.16
BEGIN DESCRIPTION:
Lidar XS
END DESCRIPTION:
XS GIS Cut Line= 2
2443476.416894397067328.862720152440092.675630397066794.88544165
#Sta/Elev= 30
       0  467.51      69  466.09   270.5  465.72     297  464.73  325.72  461.14
     339  459.48     582  459.19     682  458.32     731   458.5     781  459.36
     880  458.73    1132  459.62    1182  458.77    1233  458.59    1284  459.62
    1483  459.74    1650  461.14    1708  460.51    1756  461.19    1932  461.36
  1987.5  460.77  2168.5  460.98    2396  460.03    2516  460.49    2582  459.73
  2698.5  460.21    2891  460.05    2970  460.67    3050  459.89 3425.62  461.68
#Mann= 3 ,0,0
       0     .06       0  325.72     .05       0    1650     .06       0
#XS Ineff= 2 , 0
                            1686             468
Permanent Ineff=
       F       F
Bank Sta=325.72,1650
XS Rating Curve= 0 ,0
Exp/Cntr=0.5,0.3

Type RM Length L Ch R = 1 ,5863    ,983.74,813.43,559.42
BEGIN DESCRIPTION:
Lidar XS
END DESCRIPTION:
XS GIS Cut Line= 2
2443483.948375397067279.432700892440104.052576147066746.06237656
#Sta/Elev= 30
       0  466.97    68.5  465.35     123  465.99     275  465.72     303  464.73
  347.09  460.56     373  458.11     422  459.34     583  458.41     956  459.21
    1006  458.23    1060  458.47    1106  459.67    1179  459.88    1287  458.97
    1552  460.03    1616  459.05    1628  454.31 1658.71  453.93 1665.21  454.15
 1674.02  458.02    1704  460.42  1793.5  459.36    1849  460.23  2070.5   460.4
    2350  459.04    2570  459.89    2790  459.39    3178  460.29 3421.72  462.46
#Mann= 3 ,0,0
       0     .06       0  347.09     .05       0    1704     .06       0
#XS Ineff= 2 , 0
                         1761.54             468
Permanent Ineff=
       F       F
Bank Sta=347.09,1704
XS Rating Curve= 0 ,0
Exp/Cntr=0.3,0.1

Type RM Length L Ch R = 1 ,5049    ,635.45,523.54,424.39
BEGIN DESCRIPTION:
Lidar XS
END DESCRIPTION:
XS GIS Cut Line= 2
2443253.018719147066338.980185482440181.485492147066313.01370198
#Sta/Elev= 30
       0  466.27  184.23  465.28   333.9  463.53  388.55   460.3  451.52  453.81
  661.81  453.94  679.67  455.76  700.36   459.5  858.12   459.7  862.87  460.82
  876.24   461.3  895.46   460.8  909.48  459.04  919.56  455.31 1226.22   454.2
 2639.99   453.6 2665.62  454.91 2670.98  456.38 2678.73  457.41 2704.88  459.22
 2722.22  459.69 2744.38   459.2 2762.59  455.64  2799.4  454.62    2848  454.35
  2860.6  457.11  2875.7  458.96 2950.92     461 3023.32  461.43 3071.64  462.84
#Mann= 3 ,0,0
       0     .04       0  895.46     .03       0 2704.88     .04       0
#XS Ineff= 2 , 0
                            1878             466
Permanent Ineff=
       F       F
Bank Sta=895.46,2704.88
XS Rating Curve= 0 ,0
Exp/Cntr=0.3,0.1

Type RM Length L Ch R = 1 ,4526    ,767.55,602.84,362.72
BEGIN DESCRIPTION:
Lidar XS
END DESCRIPTION:
XS GIS Cut Line= 2
2442867.940092977065813.895277652440153.114813977065923.01087306
#Sta/Elev= 30
       0  467.26   35.93  467.13  121.14  465.57  264.85  464.77  342.37  464.08
  405.03  463.03  447.45  462.31  484.41  461.32  487.97  461.15  496.69  460.01
  503.25  458.51  508.87  457.26   511.1  456.73  515.69  455.46  519.58  453.66
 1920.87  453.58 2378.55     455 2384.81  456.27 2390.81  457.23 2402.23  457.74
  2428.1  458.25 2440.19  458.69 2530.51  459.61 2583.33  459.84 2590.88  459.93
 2625.06  460.77 2634.07  461.09 2683.66  461.52 2696.77  462.21 2717.02  463.07
#Mann= 3 ,0,0
       0     .04       0  487.97     .03       0 2440.19     .04       0
#XS Ineff= 2 , 0
                            2238             467
Permanent Ineff=
       F       F
Bank Sta=487.97,2440.19
XS Rating Curve= 0 ,0
Exp/Cntr=0.3,0.1

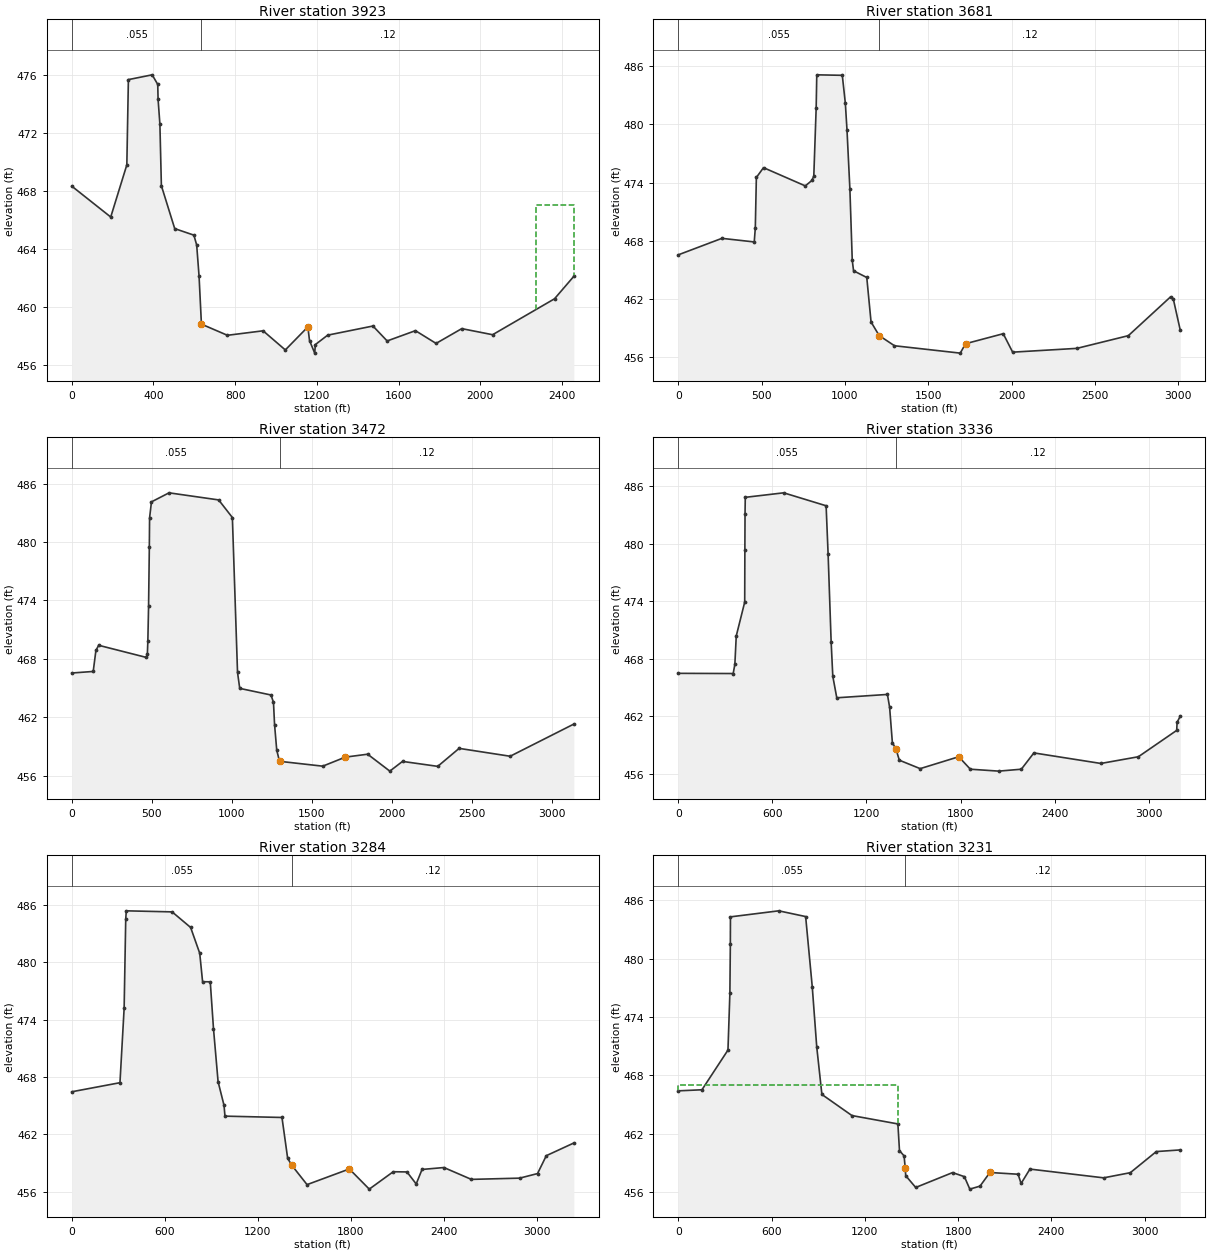
Type RM Length L Ch R = 1 ,3923    ,218.49,241.38,314.39
BEGIN DESCRIPTION:
Lidar XS
END DESCRIPTION:
XS GIS Cut Line= 2
2442481.910353217065022.028423062440124.054176557065717.22453922
#Sta/Elev= 30
       0  468.31  190.74  466.18  269.62  469.78  277.22  475.66  393.64  475.99
  420.93  475.33  422.54  474.31  431.48  472.59  438.75  468.34  504.04  465.38
  597.84  464.93   611.6  464.25  623.22   462.1  634.82  458.79  762.09  458.02
  936.68  458.33 1045.55  457.01 1155.92   458.6 1164.02  457.66 1189.49  456.79
 1192.58  457.38 1252.91  458.03 1474.58  458.66 1544.11  457.63 1682.65  458.34
 1783.65  457.46 1909.53  458.48 2060.45  458.06 2363.69  460.54 2458.21  462.09
#Mann= 2 ,-1,0
       0    .055       0  634.82     .12       0
#XS Ineff= 2 , 0
                            2272             467
Permanent Ineff=
       F       F
Bank Sta=634.82,1155.92
XS Rating Curve= 0 ,0
Exp/Cntr=0.3,0.1

Type RM Length L Ch R = 1 ,3681    ,186.18,209.73,274.39
BEGIN DESCRIPTION:
Banks moved to L-Spillway 12/29/15 BG, treed area set to n=0.12
Lidar XS
END DESCRIPTION:
XS GIS Cut Line= 2
2442865.660569977064829.019622732439902.684540557065370.42011473
#Sta/Elev= 30
       0  466.57  261.82  468.27  455.96   467.9  462.35  469.32  468.71  474.54
  511.65  475.55  762.47  473.67  801.47  474.23  813.24  474.67   827.5   481.7
   831.1  485.11   984.2  485.06 1002.49  482.18 1012.42  479.43 1029.71  473.37
 1043.95  466.01  1051.8  464.93 1131.06  464.24 1156.73  459.66 1205.34  458.26
 1297.23  457.21 1691.86  456.45 1723.66  457.42 1949.77  458.45 2006.14  456.55
 2391.51  456.94 2700.39  458.25 2953.82  462.25 2969.93  462.03 3012.03  458.79
#Mann= 2 ,-1,0
       0    .055       0 1205.34     .12       0
Bank Sta=1205.34,1723.66
XS Rating Curve= 0 ,0
Exp/Cntr=0.3,0.1

Type RM Length L Ch R = 1 ,3472    ,126.11,135.9,163.08
BEGIN DESCRIPTION:
Banks moved to L-Spillway 12/29/15 BG, treed area set to n=0.12
Lidar XS
END DESCRIPTION:
XS GIS Cut Line= 2
2442868.334449147064813.930742142439738.155013967065012.21545056
#Sta/Elev= 30
       0  466.54  133.96   466.7  150.83  468.86   168.1  469.39  466.58  468.14
  472.31   468.5   475.3  469.83  479.86  473.46  484.52  479.45  486.06  482.49
  497.81  484.14  607.76  485.07  917.69  484.34 1003.27  482.53 1035.48   466.6
 1049.27  464.96 1244.38  464.28 1260.07  463.53 1266.79  461.24 1280.41  458.61
 1297.68  457.46 1567.83  456.96 1708.82  457.89 1848.38  458.19 1986.92  456.45
 2066.11  457.45 2286.21  456.94 2419.79  458.79 2738.54  457.98 3136.45  461.29
#Mann= 2 ,-1,0
       0    .055       0 1297.68     .12       0
Bank Sta=1297.68,1708.82
XS Rating Curve= 0 ,0
Exp/Cntr=0.3,0.1

Type RM Length L Ch R = 1 ,3336    ,51.61,51.84,54.87
BEGIN DESCRIPTION:
Banks moved to L-Spillway 12/29/15 BG, treed area set to n=0.12
Lidar XS
END DESCRIPTION:
XS GIS Cut Line= 2
2442871.737001397064794.731305482439671.335265737064791.70998606
#Sta/Elev= 30
       0   466.5  350.26  466.48  360.96  467.44  369.82   470.4  423.71  473.93
  424.78  479.38  425.79   483.1  427.32  484.86  672.15  485.33   942.6  483.98
  955.39  478.92  974.84  469.72  985.22   466.2 1010.59  463.95 1333.44   464.3
  1347.4  462.96 1364.92  459.28 1388.81  458.56 1409.26  457.44 1542.14  456.56
    1788   457.8    1862   456.5    2043   456.3    2187   456.5    2267   458.2
    2694   457.1    2933   457.8 3177.39  460.55 3179.99   461.4  3200.4  462.04
#Mann= 2 ,-1,0
       0    .055       0 1388.81     .12       0
Bank Sta=1388.81,1788
XS Rating Curve= 0 ,0
Exp/Cntr=0.3,0.1

Type RM Length L Ch R = 1 ,3284    ,52.84,52.71,55.02
BEGIN DESCRIPTION:
Banks moved to L-Spillway 12/29/15 BG, treed area set to n=0.12
Lidar XS
END DESCRIPTION:
XS GIS Cut Line= 3
 2442875.5949333 7064772.01219082440563.907299477064737.32000297
2439652.154529817064570.56246248
#Sta/Elev= 30
       0  466.46  310.92  467.41  337.84  475.21  348.14  484.54  351.71   485.4
   647.3  485.29  766.73  483.66  825.43  480.96   843.9  477.98  893.39  477.97
  914.25  473.06  943.82  467.52   982.3  465.03  988.16  463.91 1356.01  463.77
 1392.72  459.49    1420  458.75 1517.79  456.74 1790.57  458.38  1919.1  456.27
 2073.74  458.09 2162.22  458.07 2221.88  456.81  2259.6  458.33 2400.62  458.53
 2577.78  457.29 2889.45  457.42 3004.71   457.9 3061.08  459.77 3238.82   461.1
#Mann= 2 ,-1,0
       0    .055       0    1420     .12       0
Bank Sta=1420,1790.57
XS Rating Curve= 0 ,0
Exp/Cntr=0.3,0.1

Type RM Length L Ch R = 1 ,3231    ,85.09,120.65,189.72
BEGIN DESCRIPTION:
Banks moved to L-Spillway 12/29/15 BG, treed area set to n=0.12
Lidar XS
END DESCRIPTION:
XS GIS Cut Line= 3
 2442879.54964987064748.724507732440569.975200717064682.33651714
2439683.218115977064443.05287498
#Sta/Elev= 30
       0  466.41  152.49  466.52  319.82   470.6  332.21  476.45  335.17  481.49
  335.81  484.29  646.42  484.91  819.39  484.32  861.95   477.1  890.74  470.92
  923.91  466.04 1117.21  463.87 1412.68  463.01 1422.88  460.27 1452.64  459.72
 1459.86  458.47 1463.03  457.69 1527.28  456.48 1764.37  458.01 1840.39  457.59
 1875.24  456.31 1941.02  456.62 2004.46  458.02 2185.83  457.84 2205.02  456.89
 2261.81  458.37 2735.88  457.47 2907.55     458 3074.63  460.17    3229  460.34
#Mann= 2 ,-1,0
       0    .055       0 1459.86     .12       0
#XS Ineff= 2 , 0
            1414     467
Permanent Ineff=
       F       F
Bank Sta=1459.86,2004.46
XS Rating Curve= 0 ,0
Exp/Cntr=0.3,0.1

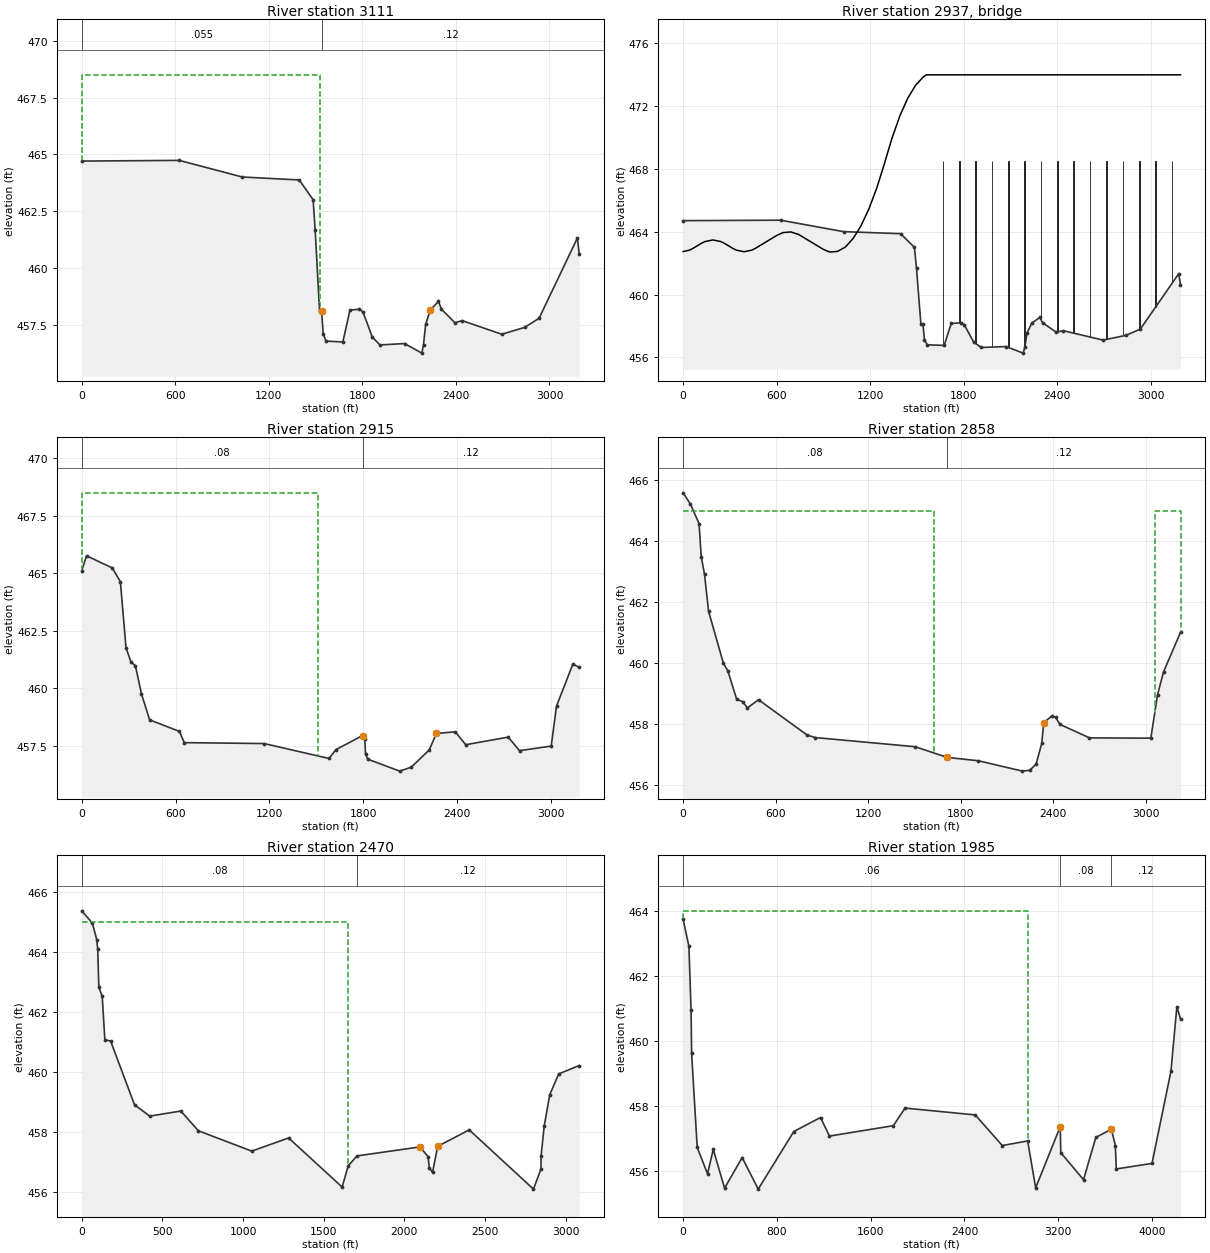
Type RM Length L Ch R = 1 ,3111    ,209.59,196.05,239.73
BEGIN DESCRIPTION:
Banks moved to L-Spillway 12/29/15 BG, treed area set to n=0.12 No true channel in this section.
Lidar XS
END DESCRIPTION:
XS GIS Cut Line= 4
2442873.923020637064651.483560472441359.022179057064635.47178148
2440612.865206817064501.495015312439728.952276477064255.32359165
#Sta/Elev= 30
       0  464.71  625.24  464.74 1028.99  464.01 1394.84  463.88 1483.89  463.01
 1497.11  461.67 1525.36  458.11 1538.32  458.12 1548.41  457.12 1565.98   456.8
  1674.5  456.76 1720.13  458.16 1779.45   458.2 1802.97  458.09 1863.87  456.97
 1912.82  456.63  2070.8  456.69 2181.44  456.27 2191.97  456.64 2205.66  457.54
 2236.63  458.18 2287.88  458.54    2307   458.2    2394   457.6    2439   457.7
    2694   457.1    2840   457.4    2933   457.8 3179.08  461.33 3190.63  460.63
#Mann= 2 ,-1,0
       0    .055       0 1538.32     .12       0
#XS Ineff= 2 , 0
            1525   468.5
Permanent Ineff=
       F       F
Bank Sta=1538.32,2236.63
XS Rating Curve= 0 ,0
Exp/Cntr=0.3,0.1

Type RM Length L Ch R = 3 ,2937    ,,,
Bridge Culvert--1,0,-1,-1, 0
Deck Dist Width WeirC Skew NumUp NumDn MinLoCord MaxHiCord MaxSubmerge Is_Ogee
34,83,2.6,0, 47, 47, , , 0.98, 0, 0,0,,
       0      41      66      91     116     141     191     241     266     291
     316     341     391     441     466     491     541     591     601     641
     691     741     751     791     841     891     901     941     991    1041
    1091    1141    1191    1241    1291    1301    1306    1341    1391    1441
    1491    1541    1556    1561    1563    1563    3191
  462.74  462.83  462.96  463.11  463.26  463.38  463.48  463.38  463.26  463.11
  462.96  462.83  462.73  462.83  462.96  463.11  463.41  463.71  463.77  463.95
  463.99  463.83  463.77  463.53  463.23  462.93  462.87  462.71  462.75  463.03
  463.58  464.38  465.44  466.75  468.33  468.67  468.84     470   471.4  472.51
  473.33  473.87  473.97     474     474     474     474
                                           468.5   468.5
       0      37      62      87     112     137     187     237     262     287
     312     337     387     437     462     487     537     587     597     637
     687     737     747     787     837     887     897     937     987    1037
    1087    1137    1187    1237    1287    1297    1302    1337    1387    1437
    1487    1537    1552    1557    1559    1559    3182
  462.75  462.83  462.96  463.11  463.26  463.38  463.48  463.38  463.26  463.11
  462.96  462.83  462.73  462.83  462.96  463.11  463.41  463.71  463.77  463.95
  463.99  463.83  463.77  463.53  463.23  462.93  462.87  462.71  462.75  463.03
  463.58  464.38  465.44  466.75  468.33  468.67  468.84     470   471.4  472.51
  473.33  473.87  473.97     474     474     474     474
                                           468.5   468.5
Pier Skew, UpSta & Num, DnSta & Num=  ,1666, 2 ,1662, 2 , 0 , 0 , 0 ,,
       4       4
     450   468.5
       4       4
     450   468.5
Pier Skew, UpSta & Num, DnSta & Num=  ,1771, 2 ,1767, 2 , 0 , 0 , 0 ,,
       4       4
     450   468.5
       4       4
     450   468.5
Pier Skew, UpSta & Num, DnSta & Num=  ,1876, 2 ,1872, 2 , 0 , 0 , 0 ,,
       4       4
     450   468.5
       4       4
     450   468.5
Pier Skew, UpSta & Num, DnSta & Num=  ,1981, 2 ,1977, 2 , 0 , 0 , 0 ,,
       4       4
     450   468.5
       4       4
     450   468.5
Pier Skew, UpSta & Num, DnSta & Num=  ,2086, 2 ,2082, 2 , 0 , 0 , 0 ,,
       4       4
     450   468.5
       4       4
     450   468.5
Pier Skew, UpSta & Num, DnSta & Num=  ,2191, 2 ,2187, 2 , 0 , 0 , 0 ,,
       4       4
     450   468.5
       4       4
     450   468.5
Pier Skew, UpSta & Num, DnSta & Num=  ,2296, 2 ,2292, 2 , 0 , 0 , 0 ,,
       4       4
     450   468.5
       4       4
     450   468.5
Pier Skew, UpSta & Num, DnSta & Num=  ,2401, 2 ,2397, 2 , 0 , 0 , 0 ,,
       4       4
     450   468.5
       4       4
     450   468.5
Pier Skew, UpSta & Num, DnSta & Num=  ,2506, 2 ,2502, 2 , 0 , 0 , 0 ,,
       4       4
     450   468.5
       4       4
     450   468.5
Pier Skew, UpSta & Num, DnSta & Num=  ,2611, 2 ,2607, 2 , 0 , 0 , 0 ,,
       4       4
     450   468.5
       4       4
     450   468.5
Pier Skew, UpSta & Num, DnSta & Num=  ,2716, 2 ,2712, 2 , 0 , 0 , 0 ,,
       4       4
     450   468.5
       4       4
     450   468.5
Pier Skew, UpSta & Num, DnSta & Num=  ,2821, 2 ,2817, 2 , 0 , 0 , 0 ,,
       4       4
     450   468.5
       4       4
     450   468.5
Pier Skew, UpSta & Num, DnSta & Num=  ,2926, 2 ,2922, 2 , 0 , 0 , 0 ,,
       4       4
     450   468.5
       4       4
     450   468.5
Pier Skew, UpSta & Num, DnSta & Num=  ,3031, 2 ,3027, 2 , 0 , 0 , 0 ,,
       4       4
     450   468.5
       4       4
     450   468.5
Pier Skew, UpSta & Num, DnSta & Num=  ,3136, 2 ,3132, 2 , 0 , 0 , 0 ,,
       4       4
     450   468.5
       4       4
     450   468.5
Abutment Skew #Up #Dn= , 2 , 2
    1563    1623
   468.5   453.5
    1559    1619
   468.5   453.5
BR Coef=-1 , 0 , 0 ,, 0 ,,,0.8,-1,,0,
WSPro=,,,, 1 ,,,, 0 ,,,, 0 ,,,,-1 ,-1 ,-1 , 0 , 0 , 0 , 0 , 0
BC Design=,, 0 ,, 0 ,,,,,,
BC Use User HTab Curves=0
BC User HTab FreeFlow(D)= 0

Type RM Length L Ch R = 1 ,2915    ,55.07,57.04,57.48
BEGIN DESCRIPTION:
Banks moved to L-Spillway 12/29/15 BG, treed area set to n=0.12
Lidar XS
END DESCRIPTION:
XS GIS Cut Line= 4
2442892.676920137064614.43901515 2442351.88928787064437.77401415
2441137.221113477064423.540118722439797.230683227064022.59144557
#Sta/Elev= 30
       0  465.12   30.35  465.76  195.69  465.23  246.96  464.63  282.82  461.76
  314.33  461.15  343.21  460.97  381.89  459.75  434.07  458.62  624.21  458.12
  655.69  457.63 1166.68  457.59 1582.11  456.94  1624.8  457.32 1796.65  457.94
 1810.58  457.78 1815.14  457.14 1829.21  456.91 2034.26  456.39 2107.36  456.56
 2222.87  457.31 2268.36  458.03 2389.48   458.1 2456.06  457.54 2728.44  457.87
 2800.47  457.28 3003.29  457.48 3037.19  459.22 3141.43  461.04 3182.35  460.91
#Mann= 2 ,-1,0
       0     .08       0 1796.65     .12       0
#XS Ineff= 2 , 0
            1514   468.5
Permanent Ineff=
       F       F
Bank Sta=1796.65,2268.36
XS Rating Curve= 0 ,0
Exp/Cntr=0.3,0.1

Type RM Length L Ch R = 1 ,2858    ,328.5,387.39,405.81
BEGIN DESCRIPTION:
Banks moved to L-Spillway 12/29/15 BG, treed area set to n=0.12
Lidar XS
END DESCRIPTION:
XS GIS Cut Line= 4
2442950.106923397064580.600172062442344.258397557064382.68094848
2441145.588222737064368.634388642439812.592857237063970.22836131
#Sta/Elev= 30
       0  465.59    47.5  465.22   103.4  464.58  117.56   463.5  138.69  462.92
  165.05  461.71  261.48     460  290.05  459.76  346.99  458.83   388.1  458.74
  416.74  458.54  489.09  458.81  805.29  457.65  857.33  457.57 1505.62  457.27
 1713.32  456.92 1915.61  456.81 2201.92  456.47 2249.68   456.5 2290.05   456.7
 2326.96  457.38 2339.76  458.06 2393.13  458.28 2416.88  458.23 2445.25     458
 2636.63  457.56 3034.67  457.55 3077.85  458.97 3116.82  459.72 3227.37  461.02
#Mann= 2 ,-1,0
       0     .08       0 1713.32     .12       0
#XS Ineff= 2 , 0
            1630     465    3059             465
Permanent Ineff=
       F       F
Bank Sta=1713.32,2339.76
XS Rating Curve= 0 ,0
Exp/Cntr=0.3,0.1

Type RM Length L Ch R = 1 ,2470    ,493.88,485.61,495.2
BEGIN DESCRIPTION:
Banks moved to L-Spillway 12/29/15 BG, treed area set to n=0.12  No real channel for this XS.
Lidar XS
END DESCRIPTION:
XS GIS Cut Line= 3
2442967.555051227064575.779971732442203.023115727064326.02194107
2440036.451661477063618.24514139
#Sta/Elev= 30
       0  465.38   65.34  464.97   92.65  464.42   98.69  464.09  105.77  462.82
  126.52  462.53  143.02  461.07  178.54  461.03  326.84   458.9  421.18  458.52
  614.01  458.69  722.69  458.03 1053.54  457.35 1282.12  457.79 1613.84  456.15
 1651.81  456.86 1706.24  457.19 2095.75  457.49 2146.59  457.17 2154.11  456.79
 2174.26  456.64 2206.13  457.51 2401.76  458.06 2800.12  456.08 2846.22  456.75
 2847.32  457.19 2866.31  458.18 2901.22  459.24 2956.51  459.93 3083.54  460.21
#Mann= 2 ,-1,0
       0     .08       0 1706.24     .12       0
#XS Ineff= 2 , 0
            1650     465
Permanent Ineff=
       F       F
Bank Sta=2095.75,2206.13
XS Rating Curve= 0 ,0
Exp/Cntr=0.3,0.1

Type RM Length L Ch R = 1 ,1985    ,755.03,680.37,503.09
BEGIN DESCRIPTION:
Banks moved to L-Spillway 12/29/15 BG, treed area set to n=0.12 No real channel in this section.
Lidar XS
END DESCRIPTION:
XS GIS Cut Line= 3
2444288.765991467064602.811741812442298.064920387063877.10485989
2440283.132270477063203.96513006
#Sta/Elev= 30
       0  463.74   49.23  462.91   67.79  460.95   72.45  459.62  120.15  456.73
  208.21  455.92  256.89  456.67   353.6  455.48  503.43  456.42  640.54  455.45
  943.83  457.22 1171.88  457.65  1248.4  457.08 1793.57   457.4 1893.03  457.94
 2491.88  457.73 2722.18  456.79 2939.15  456.93 3007.38  455.49 3216.94  457.37
 3221.76  456.57 3415.59  455.74 3520.73  457.04 3652.86  457.29 3687.29  456.79
 3695.02  456.07 3999.74  456.24  4161.3  459.07  4211.8  461.05 4243.25  460.68
#Mann= 3 ,-1,0
       0     .06       0 3216.94     .08       0 3652.86     .12       0
#XS Ineff= 2 , 0
            2940     464
Permanent Ineff=
       F       F
Bank Sta=3216.94,3652.86
XS Rating Curve= 0 ,0
Exp/Cntr=0.3,0.1

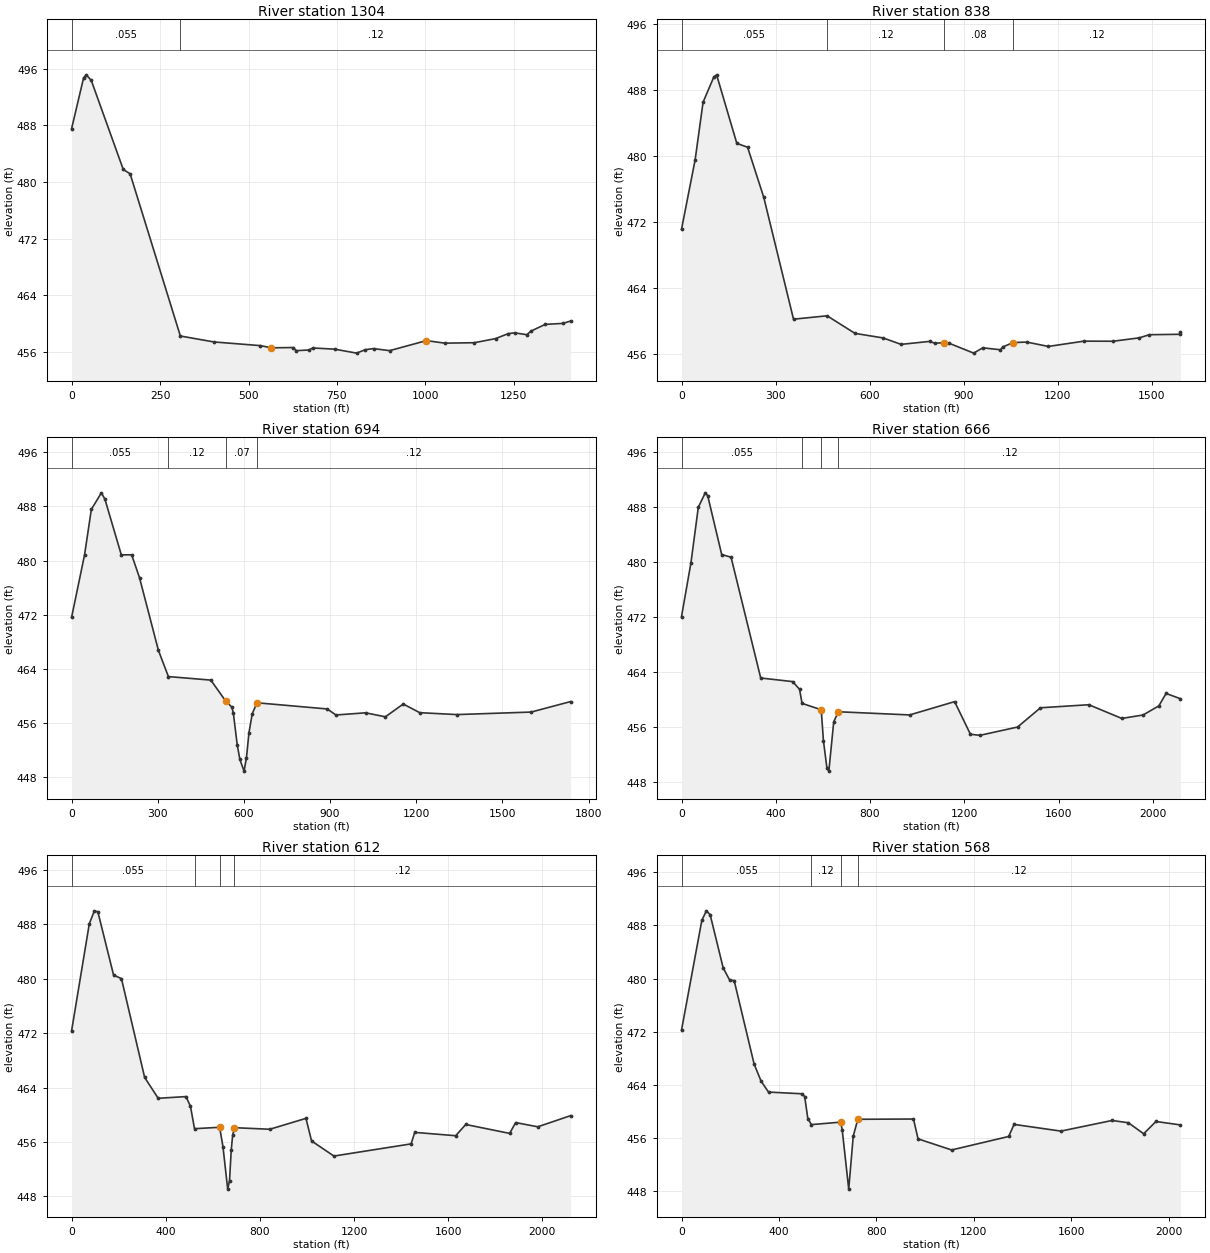
Type RM Length L Ch R = 1 ,1304    ,508.2,466.1,299.54
BEGIN DESCRIPTION:
Banks moved to L-Spillway 12/29/15 BG, treed area set to n=0.12
Lidar XS
END DESCRIPTION:
XS GIS Cut Line= 2
2441723.820005897062794.578153572440313.501960387062795.30026498
#Sta/Elev= 30
       0  487.55   33.87  494.73    41.4  495.15   55.48  494.37  145.97  481.78
  165.36  481.17  307.36  458.25  402.15  457.41  533.57  456.89  564.65  456.58
  626.29  456.62  635.02  456.18  670.22  456.27  681.78  456.56  743.23  456.39
  805.73  455.83  829.47  456.31  853.39  456.47  898.83  456.18 1002.94   457.6
 1054.32  457.24 1138.26   457.3 1198.17  457.88 1233.37  458.57  1251.9   458.7
 1286.79  458.43 1297.94  458.93 1338.51  459.89 1388.46  460.03 1410.32  460.36
#Mann= 2 ,-1,0
       0    .055       0  307.36     .12       0
Bank Sta=564.65,1002.94
XS Rating Curve= 0 ,0
Exp/Cntr=0.3,0.1

Type RM Length L Ch R = 1 ,838     ,114.48,144.46,262.17
BEGIN DESCRIPTION:
Banks moved to L-Spillway 12/29/15 BG, treed area set to n=0.12
Lidar XS
END DESCRIPTION:
XS GIS Cut Line= 2
2441788.056097887062140.064370722440256.699580557062572.29841439
#Sta/Elev= 30
       0  471.08   43.52  479.51   68.81  486.48  102.86  489.51  111.94  489.79
  176.39  481.49  210.74  481.02  262.38  474.95  357.19   460.2  464.31  460.61
  553.31  458.48  642.89  457.93  700.15  457.15  791.02  457.51  806.99   457.3
  836.81  457.34  852.62   457.3  931.72  456.09  960.58  456.73 1017.26   456.5
 1024.35  456.84 1057.85  457.37 1100.76  457.43 1169.86   456.9 1283.11  457.54
  1376.2  457.53 1459.91  457.94  1491.8  458.32 1588.17  458.37 1591.19  458.61
#Mann= 4 ,-1,0
       0    .055       0  464.31     .12       0  836.81     .08       0
 1057.85     .12       0
Bank Sta=836.81,1057.85
XS Rating Curve= 0 ,0
Exp/Cntr=0.3,0.1

Type RM Length L Ch R = 1 ,694     ,23.73,28.07,130.99
BEGIN DESCRIPTION:
Banks moved to L-Spillway 12/29/15 BG, treed area set to n=0.12
Lidar XS
END DESCRIPTION:
XS GIS Cut Line= 2
2441787.438973147062128.391821892440056.373209557062274.29933847
#Sta/Elev= 30
       0  471.64   44.92  480.82   68.78  487.57  103.61  490.01  116.02  489.06
  173.03  480.85  209.06  480.86  236.37  477.48  302.12  466.76  336.96  462.88
  484.69  462.36  536.53  459.26   557.8  458.38  563.06  457.49  576.78  452.75
  585.88  450.64  600.44  448.92  608.85  450.92  617.44  454.59  629.01  457.41
  645.53  459.01  889.94   458.1  920.35  457.21 1023.46  457.53 1092.47  456.94
 1154.65  458.83 1212.01  457.55    1341  457.27 1599.89  457.64  1737.2  459.19
#Mann= 4 ,-1,0
       0    .055       0  336.96     .12       0  536.53     .07       0
  645.53     .12       0
Bank Sta=536.53,645.53
XS Rating Curve= 0 ,0
Exp/Cntr=0.3,0.1

Type RM Length L Ch R = 1 ,666     ,44.97,53.9,102.16
BEGIN DESCRIPTION:
Banks moved to L-Spillway 12/29/15 BG, treed area set to n=0.12  12 12/29/15 BG
Lidar XS
END DESCRIPTION:
XS GIS Cut Line= 3
2441786.955706397062120.573924142440880.734421727062169.45637231
2439684.471722387061991.27267356
#Sta/Elev= 30
       0  472.06   40.11  479.89   71.27  487.94  100.83  490.04  111.06  489.63
  170.52  481.08  210.22  480.69   336.1  463.15  471.44  462.63  500.74  461.52
   511.5  459.47  590.03  458.57  593.55  458.21  602.24  454.03  616.79  450.12
  625.15  449.63  645.86   456.8  665.71  458.25  968.09  457.79 1158.72  459.72
 1225.93  454.98 1266.44  454.83 1425.75  456.03 1523.13  458.83 1728.16  459.27
 1868.08  457.28 1958.25  457.78 2025.17   459.1    2056  460.91    2117  460.14
#Mann= 4 ,-1,0
       0    .055       0   511.5     .12       0  590.03     .07       0
  665.71     .12       0
Bank Sta=590.03,665.71
XS Rating Curve= 0 ,0
Exp/Cntr=0.3,0.1

Type RM Length L Ch R = 1 ,612     ,32.35,43.27,110.14
BEGIN DESCRIPTION:
Banks moved to L-Spillway 12/29/15 BG, treed area set to n=0.12
Lidar XS
END DESCRIPTION:
XS GIS Cut Line= 3
2441787.953735897062109.484707472440885.074964237062100.01195739
2439696.058641467061841.72638473
#Sta/Elev= 30
       0  472.35   75.18  488.07   96.64  489.97  111.52  489.82  178.32  480.52
   211.7  480.01  310.27  465.48  367.86  462.42  485.75  462.67  504.89  461.25
  522.08  457.95  628.81  458.16  643.06  455.29  663.06  449.07  670.86  450.33
  678.25  454.88  684.34  457.03  691.91   458.1  841.98  457.87  995.55  459.47
 1019.34  456.15 1114.33  453.93 1442.14  455.72 1457.61  457.41 1631.54  456.92
 1674.39  458.57 1860.78  457.26 1886.48  458.85 1980.37  458.23 2119.68  459.87
#Mann= 4 ,-1,0
       0    .055       0  522.08     .12       0  628.81     .07       0
  691.91     .12       0
Bank Sta=628.81,691.91
XS Rating Curve= 0 ,0
Exp/Cntr=0.3,0.1

Type RM Length L Ch R = 1 ,568     ,113.56,598,241.57
BEGIN DESCRIPTION:
Banks moved to L-Spillway 12/29/15 BG, treed area set to n=0.12
Lidar XS
END DESCRIPTION:
XS GIS Cut Line= 3
2441789.911409147062102.063462482440902.268827477062051.16133331
2439802.91472697 7061684.3336549
#Sta/Elev= 30
       0  472.23    83.5  488.78  102.03  490.21  117.59  489.63  171.12   481.6
  197.39   479.8  216.27  479.69  297.99  467.14  326.59  464.56  357.16  462.91
  495.57  462.65  505.59  462.23   518.6   458.9  533.32  458.01   653.2  458.38
  659.64  457.22  686.37  448.29  704.91  456.28  723.72  458.81   952.2  458.85
  970.98  455.86 1108.62  454.19 1342.85  456.22 1365.03  458.04  1557.2  457.03
 1767.02  458.63  1834.1  458.29 1897.02  456.63 1947.34  458.48 2048.04  457.96
#Mann= 4 ,-1,0
       0    .055       0  533.32     .12       0   653.2     .07       0
  723.72     .12       0
Bank Sta=653.2,723.72
XS Rating Curve= 0 ,0
Exp/Cntr=0.3,0.1

River Reach=Elm Fork        ,ef6
Reach XY= 30
2436799.505379477071677.498051732436765.235434897071646.50172265
2436750.237761477071596.998212722436777.978191557071512.00822523
2436798.261943647071293.510958812436762.725925487071116.47161473
2436766.743633977071027.476057812436735.739430897070959.01523672
 2436798.52244187070728.51012032 2436891.51635037070620.98572905
2437008.74774313 7070574.01666292437091.517262647070498.48991106
2437137.00962572 7070411.50123992437179.00822939 7070384.4816089
2437406.502853147070081.473684732437492.500384557069914.98812531
2437653.224800637069696.525963812437707.244705727069662.48436522
2437875.497321967069480.974229562437970.519769717069418.01011665
2438095.724899897069180.488281982438106.24751663 7068659.9811209
2438138.497452147068547.975767482438198.477975227068433.01996064
2438330.742146397068310.518893322438669.008530217068144.97526114
2438969.979056887067789.986141732439327.999994387067429.97734731
2439638.733952977067163.520203052439781.733275337066985.49287523