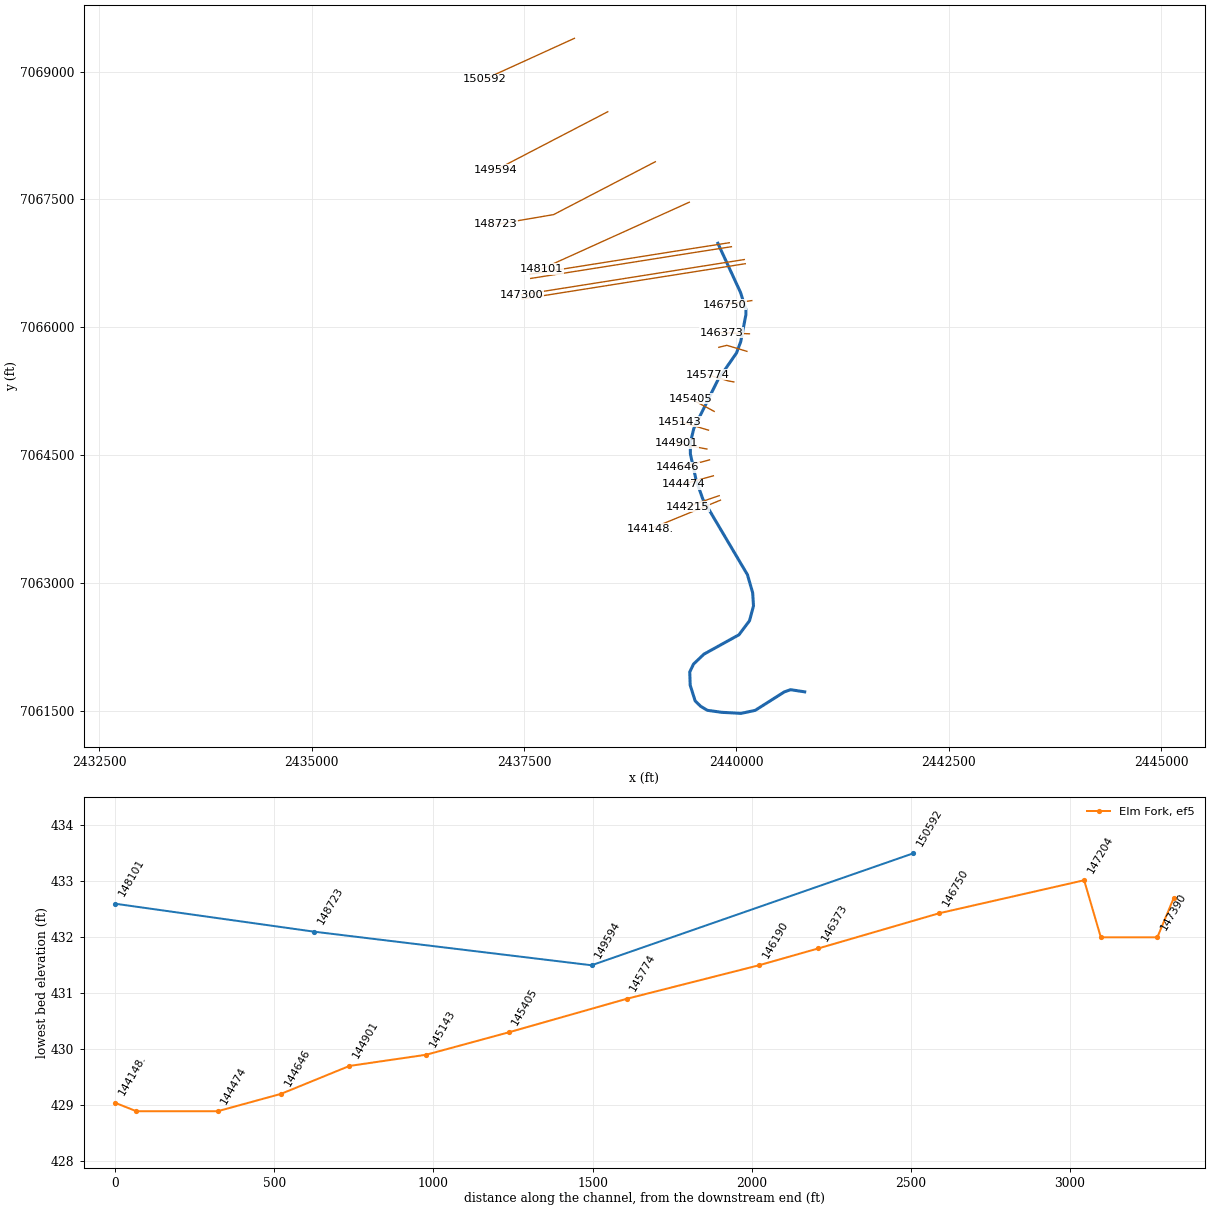
HEC-RAS study CDC_Consolidated_Model.prj: Upper Trinity CDC Consolidated Model

--- CDC_Consolidated_Model.g12 (geometry) --- (continued)

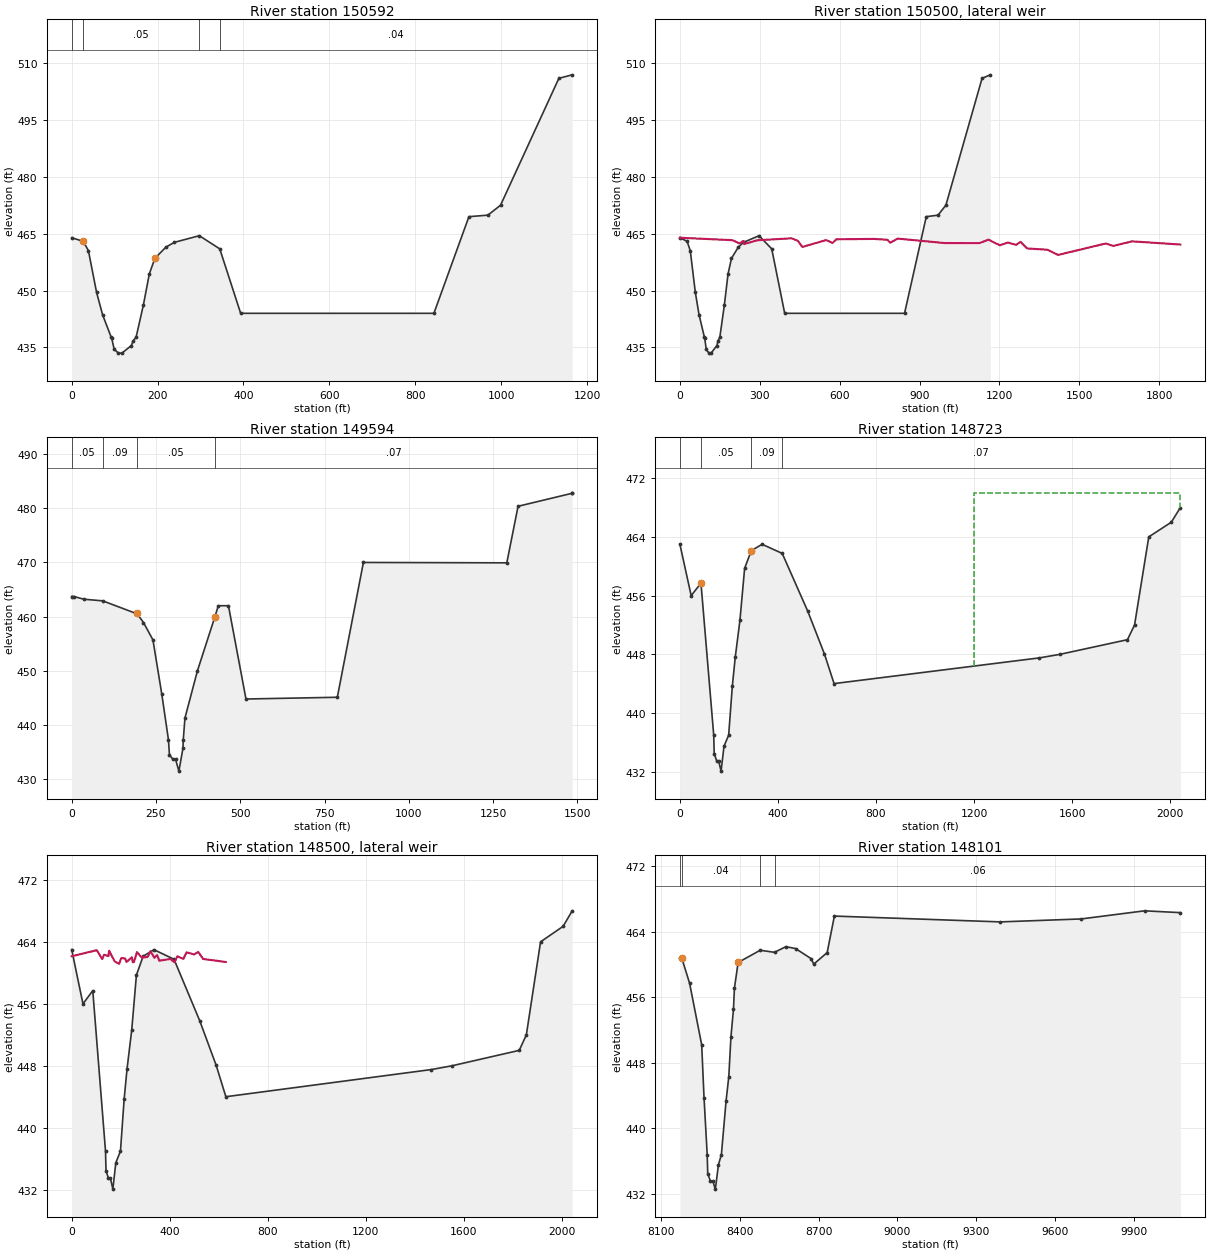
Type RM Length L Ch R = 1 ,150592  ,964.2,1010.3,998.06
BEGIN DESCRIPTION:
150592- ROB modified using 2009Lidar-CDC pond is shifted but still the same
END DESCRIPTION:
XS GIS Cut Line= 2
2438092.835798057069391.868436652437031.596778817068909.89367881
#Sta/Elev= 27
       0  463.92      27     463      39   460.5      58   449.5      72   443.6
      92   437.7      93   437.5      99   434.5     109   433.5     117   433.5
     139   435.5     143   436.7     150   437.7     167   446.2  180.81   454.4
  193.76   458.5  219.32  461.45   239.1  462.72  297.24  464.47  344.81     461
  393.51     444  843.51     444  925.08  469.49  969.27  469.89  998.71  472.51
 1134.57  505.98 1165.56   506.9
#Mann= 4 ,-1,0
       0     .09       0      27     .05       0  297.24     .08       0
  344.81     .04       0
#XS Ineff= 2 , 0
                             300             459
Permanent Ineff=
       F       T
Bank Sta=27,193.76
XS Rating Curve= 0 ,0
Exp/Cntr=0.3,0.1

Type RM Length L Ch R = 6 ,150500  ,,,
Lateral Weir Pos= 0
Lateral Weir End=Elm Fork L-Spill,efl2            ,2879    ,
Lateral Weir Distance=0
Lateral Weir TW Multiple XS=0
Lateral Weir WD=5
Lateral Weir Coef=2
LW OverFlow Method 2D=0
LW OverFlow Use Velocity Into 2D=0
Lateral Weir WSCriteria=-1
Lateral Weir Flap Gates= 0
Lateral Weir Hagers EQN= 0 ,,,,,
Lateral Weir SS=0.05,0.05,
Lateral Weir Type= 0
Lateral Weir Connection Pos and Dist= 3 ,
Lateral Weir SE= 30
       0  463.93  197.53  463.29  223.48  462.43  238.25  463.08  241.22  462.26
  291.06  463.27  419.13  463.78  442.53  463.15  459.75   461.5  549.11  463.32
  573.11  462.56  587.72  463.53  729.26  463.62  779.58  463.39  789.27  462.61
   817.9   463.7  993.96  462.53  1124.2  462.51 1158.82  463.42  1201.5  461.94
 1231.57  462.66 1262.41  462.05 1278.91  462.83 1303.44  461.11 1379.92  460.77
 1420.21   459.4 1599.41  462.42 1626.96  461.76 1697.91  462.98 1879.23  462.14
Lateral Weir Centerline= 0
Lateral Weir HW RS User Defined=-1
Lateral Weir HW RS Station=150592  ,0
Lateral Weir HW RS Station=149594  ,1060
Lateral Weir HW RS Station=148723  ,1879.23
LW Div RC= 0 ,False,,

Type RM Length L Ch R = 1 ,149594  ,845.49,871.23,780.18
BEGIN DESCRIPTION:
149594-LOB stationing past station 1500 not in CDC XS.Taken from 2009 Lidar
END DESCRIPTION:
XS GIS Cut Line= 2
2438485.243805897068530.099162822437167.254437367067846.66093868
#Sta/Elev= 28
       0   463.7       7   463.7      36   463.2      92   462.9     190   460.6
     193   460.6     213   458.9     241   455.7     267   445.8     287   437.3
     290   434.5     300   433.7     308   433.7     318   431.5     330   435.7
     331   437.3     336   441.3     373     450     425     460     435     462
     465     462     517   444.8  787.97  445.12  865.31  469.98 1290.71  469.91
 1324.11  480.34 1483.95  482.73 1484.65  482.82
#Mann= 4 ,-1,0
       0     .05       0      92     .09       0     193     .05       0
     425     .07       0
#XS Ineff= 1 ,-1
     425    1044     459
Permanent Ineff=
       F
Bank Sta=193,425
XS Rating Curve= 0 ,0
Exp/Cntr=0.3,0.1

Type RM Length L Ch R = 1 ,148723  ,622.79,625.44,545.07
BEGIN DESCRIPTION:
148723 -XS did not match CDC well.
END DESCRIPTION:
XS GIS Cut Line= 3
2439045.45889281 7067943.28767242437847.343506897067322.24134231
2437164.613479577067206.39454717
#Sta/Elev= 27
       0     463      46     456      86   457.7     138     437     140   434.5
     150   433.5     158   433.5     168   432.1     180   435.5     199     437
     214   443.7  225.86  447.61  244.91  452.62  264.14  459.72  291.35  462.13
  335.56  462.99   417.5  461.75     522  453.85  589.64  448.06     629  444.02
 1466.22  447.52    1550     448    1826     450    1855     452    1913     464
    2005     466    2042     468
#Mann= 4 ,-1,0
       0     .09       0      86     .05       0  291.35     .09       0
   417.5     .07       0
#XS Ineff= 2 , 0
                         1200.71             470
Permanent Ineff=
       F       F
Bank Sta=86,291.35
XS Rating Curve= 0 ,0
Exp/Cntr=0.3,0.1

Type RM Length L Ch R = 6 ,148500  ,,,
Lateral Weir Pos= 0
Lateral Weir End=Elm Fork L-Spill,efl1            ,1396    ,
Lateral Weir Distance=0
Lateral Weir TW Multiple XS=0
Lateral Weir WD=5
Lateral Weir Coef=2
LW OverFlow Method 2D=0
LW OverFlow Use Velocity Into 2D=0
Lateral Weir WSCriteria=-1
Lateral Weir Flap Gates= 0
Lateral Weir Hagers EQN= 0 ,,,,,
Lateral Weir SS=0.05,0.05,
Lateral Weir Type= 0
Lateral Weir Connection Pos and Dist= 3 ,0
Lateral Weir SE= 30
       0  462.14  102.39  462.92  124.56  461.78  132.29  462.34  149.86  462.15
  152.62  462.86  175.06  461.48  193.72  461.17  202.21  461.91  218.14  461.85
  223.36   461.4  245.57  462.01  249.33  461.36  254.11  461.39  266.21  462.67
  286.02  461.97  309.98  462.05  321.38  462.79  337.42  461.94  348.67  462.29
  357.66  461.56  402.23  461.79  419.23  461.36  431.01  462.13   455.7   461.8
  468.81  462.65  499.21  462.37   516.2   462.7  536.21  461.79  628.34   461.4
Lateral Weir Centerline= 0
Lateral Weir HW RS User Defined=-1
Lateral Weir HW RS Station=148723,0
Lateral Weir HW RS Station=148101,628.34
LW Div RC= 0 ,False,,

Type RM Length L Ch R = 1 ,148101  ,595.76,637.23,262.06
BEGIN DESCRIPTION:
148101-Are mods to left bank and LOB pond built? as shown in CDC?
148101----CDC LEW012804-01 Lewisville Landfill
Cross-section 148101-152100 Located in LOB.----EF u/s of Stewart Creek. The 2, 5, 10, 25-year discharges are discharge-frequency releases from Lewisville Lake and are considered critical discharges as they exceed the local discharges.  7000 cfs is released from the Lewisville Lake outlet per normal lake regulation plan for flood control. During the 50-year and 100-year flood events,the
END DESCRIPTION:
XS GIS Cut Line= 2
2439445.524037557067468.252205152437708.173181557066684.12549256
#Sta/Elev= 30
    8172   460.8    8179   460.8    8209   457.7    8255   450.2    8264   443.7
    8276   436.8    8278   434.5    8288   433.6    8297   433.6    8307   432.6
    8319   435.6    8330   436.8    8348   443.4  8358.3  446.33 8366.43  451.18
 8376.03  454.52 8379.64  457.09 8393.75  460.24 8477.75  461.73 8532.34  461.48
 8575.65  462.17 8612.35  461.94 8671.35  460.72 8681.94  460.04 8732.89  461.45
 8760.36   465.9 9392.84  465.19 9700.03  465.55  9941.6  466.5410078.11  466.32
#Mann= 4 ,-1,0
    8172     .09       0    8179     .04       0 8477.75     .08       0
 8532.34     .06       0
#XS Ineff= 2 , 0
                         9234.74
Permanent Ineff=
       F       F
Bank Sta=8179,8393.75
XS Rating Curve= 0 ,0
Exp/Cntr=0.3,0.1

River Reach=Elm Fork        ,ef5
Reach XY= 30
2439781.733275337066985.492875232440048.012333887066409.01777506
2440111.517456227066212.016528652440111.736615887066147.97367772
 2440050.47656787065830.508105312440000.495368567065696.98770306
2439785.745469977065388.985366312439498.234233987064811.47799115
2439457.00892273 7064641.0009699 2439458.02302837064512.01041423
2439527.731878387064196.522200062439606.501733977063978.02854256
2440129.48986122 7063095.5158719 2440191.00384587062884.03007439
2440200.975610647062729.491013392440154.011465717062554.47692773
2440029.730874397062389.492349572439618.020411717062162.47672747
2439494.728335477062045.512066392439450.515825477061952.51750173
2439455.756956737061797.970238642439513.98879564 7061614.0050554
2439578.995883467061549.995997062439657.009835057061503.01249523
2439826.239155387061479.505652472440054.752805967061466.99419457
 2440221.26756487061502.493467392440563.774097647061718.98614465
2440637.019029897061745.00774615 2440803.7829693 7061719.6372299

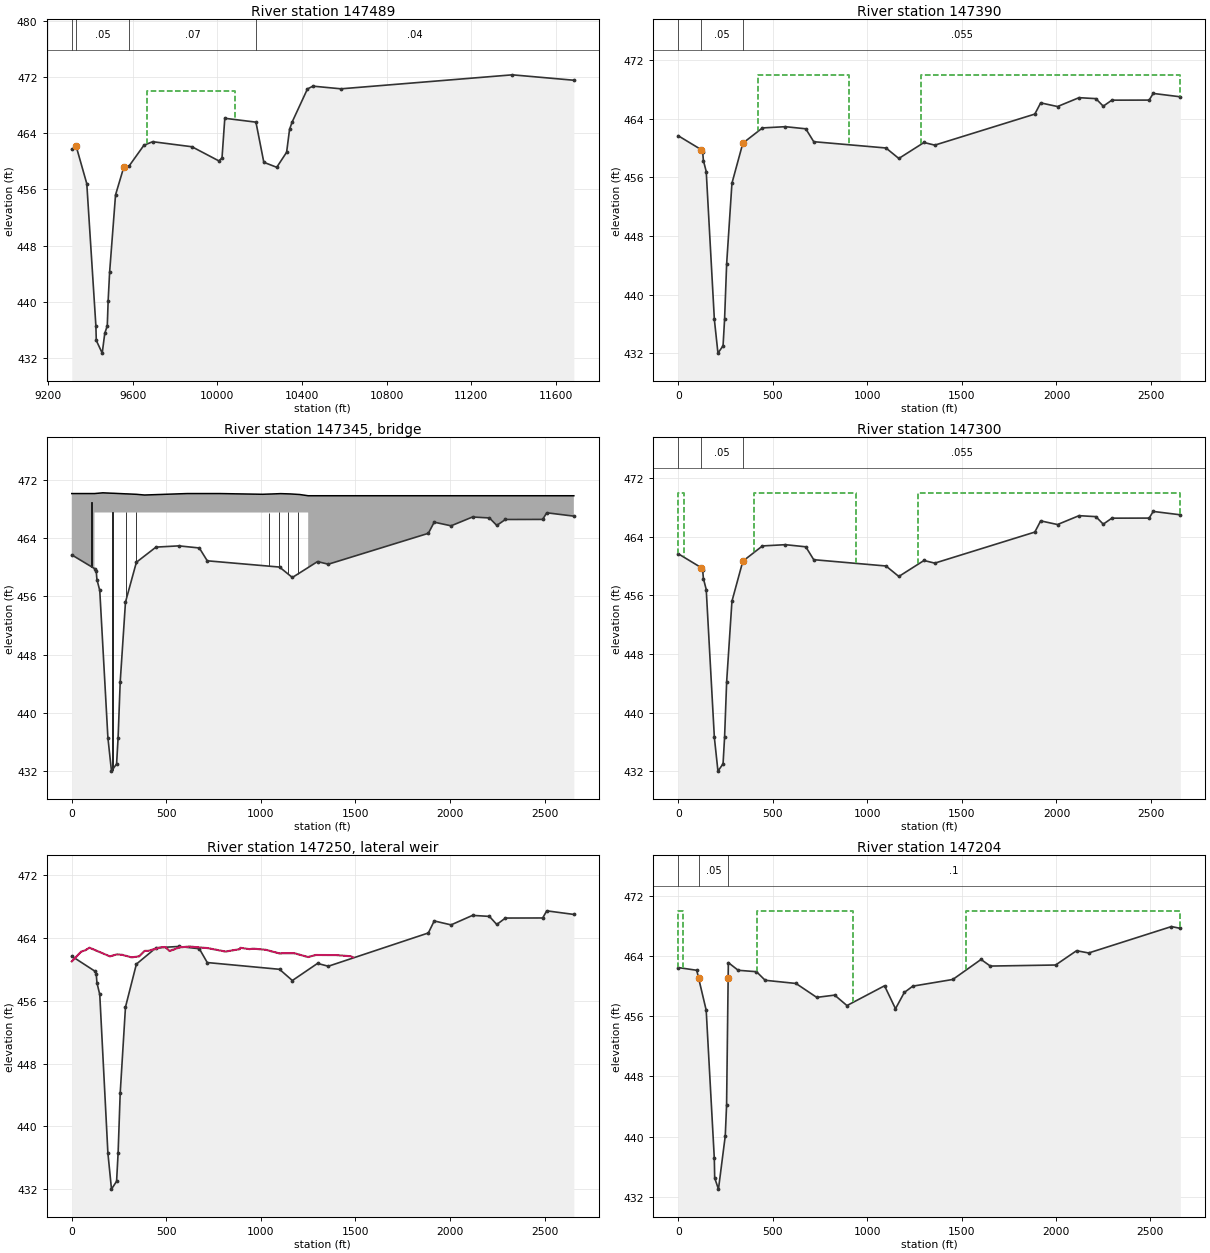
Type RM Length L Ch R = 1 ,147489  ,51.91,51.3,58.69
BEGIN DESCRIPTION:
147489- top of rd (sh121) removed from xsec
Cross-section EF173.  100 feet upstream of SH 121.  Effective flow limit set at sta 6020 in LOB, at sta 10530 in ROB.  Ineffective flow from sta 7440 - 9280, sta 9835 - 10160 due to bridge openings.  Approx. 50 feet  downstream of left bank of McWhorter Creek.
Channel data from NDM Elm Fork channel survey.
END DESCRIPTION:
XS GIS Cut Line= 3
2439916.294421467066992.282028482439334.128591057066901.42886373
2437570.533364977066622.53375223
#Sta/Elev= 30
    9311  461.67    9332   462.1    9382   456.8    9425   436.6    9427   434.5
    9455   432.7    9467   435.5    9479   436.6    9483   440.1    9490   444.2
    9518   455.2 9556.94  459.14 9582.31  459.32 9652.11  462.26 9693.66  462.77
 9879.46  462.0510006.72  460.0410021.62  460.4510034.79   466.1 10182.1  465.55
10219.38  459.8410280.49  459.1310327.21  461.2710341.06  464.5210353.03  465.55
10425.67  470.2710451.59  470.67 10584.4  470.2911394.74  472.2811685.72  471.51
#Mann= 4 ,-1,0
    9311     .06       0    9332     .05       0 9582.31     .07       0
 10182.1     .04       0
#XS Ineff= 2 ,-1
    9668   10083     47010464.7611685.72     470
Permanent Ineff=
       F       F
Bank Sta=9332,9556.94
XS Rating Curve= 0 ,0
Exp/Cntr=0.5,0.3

Type RM Length L Ch R = 1 ,147390  ,179.14,177.64,203.37
BEGIN DESCRIPTION:
147390-US Bus. SH 121- top of rd removed from xsec
END DESCRIPTION:
XS GIS Cut Line= 3
2439941.11589414 7066945.56493032439341.888418057066852.03460556
2437578.343388727066573.14736806
#Sta/Elev= 30
       0  461.68  121.05  459.79  129.36  459.44     133   458.3     148   456.8
     191   436.6     210     432     237     433     245   436.6     256   444.2
     284   455.2  341.65  460.67  445.38  462.75  566.38  462.92  674.38  462.63
  716.38  460.87 1098.38  460.01 1166.38  458.58 1299.38  460.76 1356.38   460.4
 1885.38  464.64 1916.35  466.17 2005.44  465.67 2119.01  466.88 2208.23  466.75
 2247.18  465.72 2292.77  466.54 2489.93  466.55 2511.28  467.46 2654.65     467
#Mann= 3 ,0,0
       0    .055       0  121.05     .05       0  341.65    .055       0
#XS Ineff= 2 ,-1
  419.85     905     470 1284.35 2654.65     470
Permanent Ineff=
       F       F
Bank Sta=121.05,341.65
XS Rating Curve= 0 ,0
Exp/Cntr=0.5,0.3

Type RM Length L Ch R = 3 ,147345  ,,,
BEGIN DESCRIPTION:
SH 121
END DESCRIPTION:
Node Name=SH 121
Bridge Culvert--1,0,-1,-1, 0
Deck Dist Width WeirC Skew NumUp NumDn MinLoCord MaxHiCord MaxSubmerge Is_Ogee
30,86,2.6,0, 29, 29, , , 0.95, 0, ,,,
       0  120.08  120.08  163.88  164.88  215.88  218.88  252.38  285.88  288.88
  338.88  339.88  384.68  384.68  609.38  784.38 1009.48 1053.88 1054.88 1103.88
 1104.88 1153.88 1154.88 1203.88 1204.88 1249.98 1249.98 2464.38 2654.65
   470.1   470.1   470.1   470.2   470.2  470.14  470.14   470.1  470.06  470.06
     470     470   469.9   469.9   470.1   470.1     470  470.04  470.04  470.09
  470.09  470.05  470.05  469.97  469.97   469.8   469.8   469.8   469.8
                   467.5   467.5   467.5   467.5   467.5   467.5   467.5   467.5
   467.5   467.5   467.5                          467.49   467.5   467.5   467.5
   467.5   467.5   467.5   467.5   467.5   467.5
       0   85.08   85.08  128.88  129.88  180.88  183.88  217.38  250.88  253.88
  303.88  304.88  349.68  349.68  574.38  749.38  974.48 1018.88 1019.88 1068.88
 1069.88 1118.88 1119.88 1168.88 1169.88 1214.98 1214.98 2429.38 2654.65
   470.1   470.1   470.1   470.2   470.2  470.14  470.14   470.1  470.06  470.06
     470     470   469.9   469.9   470.1   470.1     470  470.04  470.04  470.09
  470.09  470.05  470.05  469.97  469.97   469.8   469.8   469.8   469.8
                   467.5   467.5   467.5   467.5   467.5   467.5   467.5   467.5
   467.5   467.5   467.5                          467.49   467.5   467.5   467.5
   467.5   467.5   467.5   467.5   467.5   467.5
Pier Skew, UpSta & Num, DnSta & Num=  ,104.38, 2 ,166.4, 2 , 0 , 0 , 0 ,,
       1       1
     430     469
       1       1
     430     469
Pier Skew, UpSta & Num, DnSta & Num=  ,214.38, 2 ,216.4, 2 , 0 , 0 , 0 ,,
       3       3
     430     469
       3       3
     430     469
Pier Skew, UpSta & Num, DnSta & Num=  ,287.38, 2 ,289.4, 2 , 0 , 0 , 0 ,,
       1       1
     430     469
       1       1
     430     469
Pier Skew, UpSta & Num, DnSta & Num=  ,339.38, 2 ,341.4, 2 , 0 , 0 , 0 ,,
       3       3
     430     469
       3       3
     430     469
Pier Skew, UpSta & Num, DnSta & Num=  ,1044.38, 2 ,1016.38, 2 , 0 , 0 , 0 ,,
       1       1
     430     469
       1       1
     430     469
Pier Skew, UpSta & Num, DnSta & Num=  ,1094.38, 2 ,1066.38, 2 , 0 , 0 , 0 ,,
       1       1
     430     469
       1       1
     430     469
Pier Skew, UpSta & Num, DnSta & Num=  ,1144.38, 2 ,1116.38, 2 , 0 , 0 , 0 ,,
       1       1
     430     469
       1       1
     430     469
Pier Skew, UpSta & Num, DnSta & Num=  ,1194.38, 2 ,1166.38, 2 , 0 , 0 , 0 ,,
       1       1
     430     469
       1       1
     430     469
BR Coef= 1 , 0 , 0 ,1.05, 0 ,,,0.8,-1,0.5,1,
WSPro=,,,, 1 ,,,, 0 ,,,, 0 ,,,,-1 ,-1 ,-1 , 0 , 0 , 0 , 0 , 0
BC Design=,, 0 ,, 0 ,,,,,,
BC HTab HWMax=470.1
BC Use User HTab Curves=0
BC User HTab FreeFlow(D)= 0

Type RM Length L Ch R = 1 ,147300  ,51.9,52.39,58.7
BEGIN DESCRIPTION:
147300-DS Bus. SH 121-top of sh121 road removed from xsec
One-foot downstream of SH 121.  Duplication of following bridge cross-section (147301) without bridge piers.
Channel data from NDM Elm Fork channel survey.
END DESCRIPTION:
XS GIS Cut Line= 2
2440092.675630397066794.88544165 2437470.47385387066381.08443198
#Sta/Elev= 30
       0  461.68  121.05  459.79  129.36  459.44     133   458.3     148   456.8
     191   436.6     210     432     237     433     245   436.6     256   444.2
     284   455.2  341.65  460.67  445.38  462.75  566.38  462.92  674.38  462.63
  716.38  460.87 1098.38  460.01 1166.38  458.58 1299.38  460.76 1356.38   460.4
 1885.38  464.64 1916.35  466.17 2005.44  465.67 2119.01  466.88 2208.23  466.75
 2247.18  465.72 2292.77  466.54 2489.93  466.55 2511.28  467.46 2654.65     467
#Mann= 3 ,0,0
       0    .055       0  121.05     .05       0  341.65    .055       0
#XS Ineff= 3 ,-1
       0   30.16     470     400     940     470    1270 2654.65     470
Permanent Ineff=
       F       F       F
Bank Sta=121.05,341.65
XS Rating Curve= 0 ,0
Exp/Cntr=0.5,0.3

Type RM Length L Ch R = 6 ,147250  ,,,
Lateral Weir Pos= 0
Lateral Weir End=L-Overflow      ,efs3            ,5913    ,
Lateral Weir Distance=0
Lateral Weir TW Multiple XS=-1
Lateral Weir WD=5
Lateral Weir Coef=2
Lateral Weir Is ZeroHeight=-1
LW OverFlow Method 2D=0
LW OverFlow Use Velocity Into 2D=0
Lateral Weir WSCriteria=-1
Lateral Weir Flap Gates= 0
Lateral Weir Hagers EQN= 0 ,,,,,
Lateral Weir SS=0.05,0.05,
Lateral Weir Type= 0
Lateral Weir Connection Pos and Dist= 3 ,0
Lateral Weir SE= 30
       0  461.01      50  462.27   70.37  462.42   93.68  462.76  202.11  461.65
  238.46  461.92  269.43  461.84  315.78  461.53  355.85  461.66  385.84  462.36
  401.24  462.35  469.58  462.79  493.23  462.85  517.24  462.34  569.63   462.8
  621.86  462.91  718.68  462.71  812.72  462.27  888.55  462.58  891.06  462.75
  938.61  462.58  960.49  462.64 1026.33  462.49 1096.76  462.04 1177.29  462.05
 1249.74  461.57 1289.33  461.83 1397.37  461.82 1475.54  461.67    1488  461.53
Lateral Weir Centerline= 0
Lateral Weir HW RS User Defined=-1
Lateral Weir HW RS Station=147300,0
Lateral Weir HW RS Station=147204,50
Lateral Weir HW RS Station=146750,490
Lateral Weir HW RS Station=146373,888
Lateral Weir HW RS Station=146190,1096
Lateral Weir HW RS Station=145774,1488
Lateral Weir TW RS User Defined=-1
Lateral Weir TW RS Station=5913,0
Lateral Weir TW RS Station=5863,50
Lateral Weir TW RS Station=5049,490
Lateral Weir TW RS Station=4526,888
Lateral Weir TW RS Station=3923,1096
Lateral Weir TW RS Station=3681,1488
LW Div RC= 0 ,False,,

Type RM Length L Ch R = 1 ,147204  ,456.24,455.52,1278.53
BEGIN DESCRIPTION:
147204- sh121 top of road removed from xsec
Cross-section EF171.  97 feet downstream of SH 121.  Effective flow limit set at sta 6250 in LOB, at sta 10700 in ROB.  Connell project in LOB. Channel data from NDM Elm Fork channel survey - cross-section EF#171 surveyed
January 1994
END DESCRIPTION:
XS GIS Cut Line= 2
2440104.052576147066746.062376562437478.267801467066331.69575123
#Sta/Elev= 30
       0  462.46      98   462.1   108.3  461.01     148   456.8     191   437.1
     193   434.5     213  433.02     249   440.1     256   444.2  264.28  461.08
  265.28  463.12  317.28   462.1  414.28  461.91  460.28  460.77  623.28  460.35
  733.28   458.5  828.28   458.8  893.28  457.41 1092.28  460.04 1150.28  456.99
 1196.87  459.15 1241.78  459.99 1453.78  460.88 1603.28  463.54 1652.28  462.66
    1998   462.8    2109   464.7    2173   464.4 2611.39  467.91 2658.28  467.67
#Mann= 3 ,0,0
       0     .08       0   108.3     .05       0  264.28      .1       0
#XS Ineff= 3 ,-1
       0   23.36     470     417     927     470    1521 2658.28     470
Permanent Ineff=
       F       F       F
Bank Sta=108.3,264.28
XS Rating Curve= 0 ,0
Exp/Cntr=0.3,0.1

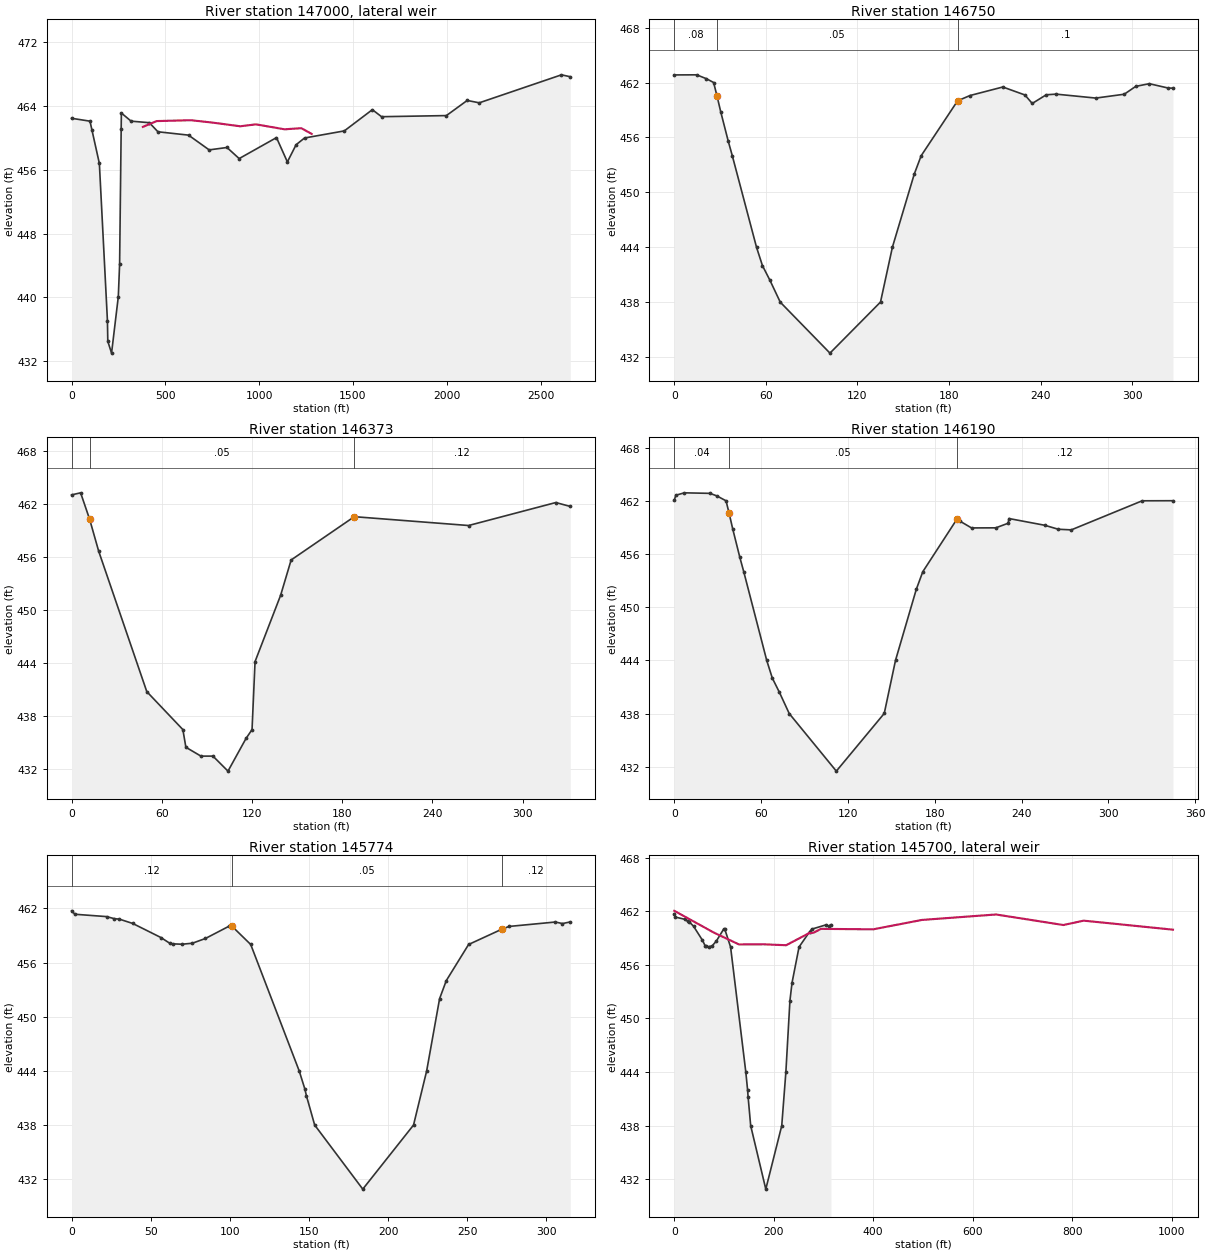
Type RM Length L Ch R = 6 ,147000  ,,,
Lateral Weir Pos= 3
Lateral Weir End=Elm Fork Split2 ,efs2            ,139902  ,
Lateral Weir Distance=35
Lateral Weir TW Multiple XS=-1
Lateral Weir WD=5
Lateral Weir Coef=2
Lateral Weir Is ZeroHeight=-1
LW OverFlow Method 2D=0
LW OverFlow Use Velocity Into 2D=0
Lateral Weir WSCriteria=-1
Lateral Weir Flap Gates= 0
Lateral Weir Hagers EQN= 0 ,,,,,
Lateral Weir SS=0.05,0.05,
Lateral Weir Type= 0
Lateral Weir Connection Pos and Dist= 0 ,0
Lateral Weir SE= 9
     380  461.38  453.26  462.11  635.32  462.22  751.84  461.92  898.82  461.46
  983.22   461.7 1135.46  461.08 1224.65  461.22    1280   460.5
Lateral Weir Centerline= 0
Lateral Weir HW RS User Defined=-1
Lateral Weir HW RS Station=147204,380
Lateral Weir HW RS Station=146750,415
Lateral Weir HW RS Station=146373,745
Lateral Weir HW RS Station=146190,920
Lateral Weir HW RS Station=145774,1280
Lateral Weir TW RS Station=139902,415
Lateral Weir TW RS Station=139477,745
Lateral Weir TW RS Station=139260,920
Lateral Weir TW RS Station=138967,1280
LW Div RC= 0 ,False,,

Type RM Length L Ch R = 1 ,146750  ,397.19,380.54,355
BEGIN DESCRIPTION:
New xsection- from Lidar? Ask Holly- flowline interpolated
END DESCRIPTION:
XS GIS Cut Line= 2
2440181.485492147066313.013701982439858.112451237066266.04102689
#Sta/Elev= 30
       0  462.83   14.66  462.84   20.97  462.42   25.76     462   27.92  460.57
   30.42   458.8   35.31  455.61      38     454   53.87     444   57.74     442
   62.69  440.38   69.43     438     102  432.43  135.12  438.01  142.91     444
  157.25     452  161.77     454  185.64     460   193.8  460.58  215.27  461.51
  229.75  460.64  234.55  459.71  243.73  460.66  250.19  460.73  276.22   460.3
  294.84  460.72   302.4  461.58  311.27  461.87  323.53   461.4  326.77  461.38
#Mann= 3 ,0,0
       0     .08       0   27.92     .05       0  185.64      .1       0
Bank Sta=27.92,185.64
XS Rating Curve= 0 ,0
Exp/Cntr=0.3,0.1

Type RM Length L Ch R = 1 ,146373  ,205.05,185.76,158.46
BEGIN DESCRIPTION:
top of bank modified 1/6/16
Cross Section Truncated due to Ineffective Flow Areas
- End Lewisville CLOMR.
Proposed Park Improvements - 13863.99-14110 (not shown)
END DESCRIPTION:
XS GIS Cut Line= 2
2440153.125312647065923.010216892439821.828731137065937.63453148
#Sta/Elev= 19
       0  463.07       6   463.3      12   460.3      18   456.7      50   440.8
      74   436.5      76   434.5      86   433.5      94   433.5     104   431.8
     116   435.5     120   436.5     122   444.2     139   451.7     146   455.7
     188   460.6     264   459.6     322   462.2  331.62  461.76
#Mann= 3 ,0,0
       0     .09       0      12     .05       0     188     .12       0
Bank Sta=12,188
XS Rating Curve= 0 ,0
Exp/Cntr=0.3,0.1

Type RM Length L Ch R = 1 ,146190  ,406.61,415.79,411.6
BEGIN DESCRIPTION:
top of bank modified 1/6/16
END DESCRIPTION:
XS GIS Cut Line= 3
2440124.054176557065717.224539222439887.171776317065787.79296765
2439792.415404147065764.70049414
#Sta/Elev= 30
       0  462.09    1.08  462.63    6.94   462.9   24.66  462.84   29.45  462.55
   35.76     462   37.92  460.57   40.42   458.8   45.31  455.61      48     454
   63.87     444   67.74     442   72.69  440.38   79.43     438     112   431.5
  145.12  438.01  152.91     444  167.25     452  171.77     454  195.64     460
  197.69  459.68  205.47  458.94  222.24  458.95  230.78  459.47  231.31     460
  256.06  459.24  265.43  458.79  274.41  458.72  323.42     462   344.7  462.01
#Mann= 3 ,0,0
       0     .04       0   37.92     .05       0  195.64     .12       0
Bank Sta=37.92,195.64
XS Rating Curve= 0 ,0
Exp/Cntr=0.3,0.1

Type RM Length L Ch R = 1 ,145774  ,392.27,371.27,353.04
BEGIN DESCRIPTION:
left overbank n value from CDC is .04 corrected to 0.12- treed area
END DESCRIPTION:
XS GIS Cut Line= 3
2439969.530207387065358.205900312439902.684540557065370.42011473
2439665.802140317065440.98854314
#Sta/Elev= 30
       0  461.73    2.09  461.35   22.07  461.09   27.03  460.86   30.18  460.81
   38.64  460.33   56.46  458.77    62.1  458.13   64.27  458.07   69.73  458.03
   76.31  458.14   84.61  458.67    99.2     460  101.43  460.01  113.19     458
  143.82     444  147.39     442  148.43  441.22  153.61     438     184   430.9
  216.08     438  224.38     444  232.55     452  236.78     454  250.87     458
  272.08  459.71  276.43     460  305.67  460.49  310.18  460.32  315.12   460.5
#Mann= 3 ,0,0
       0     .12       0  101.43     .05       0  272.08     .12       0
Bank Sta=101.43,272.08
XS Rating Curve= 0 ,0
Exp/Cntr=0.3,0.1

Type RM Length L Ch R = 6 ,145700  ,,,
Lateral Weir Pos= 0
Lateral Weir End=L-Overflow      ,efs3            ,3681    ,
Lateral Weir Distance=0
Lateral Weir TW Multiple XS=-1
Lateral Weir WD=5
Lateral Weir Coef=2
Lateral Weir Is ZeroHeight=-1
LW OverFlow Method 2D=0
LW OverFlow Use Velocity Into 2D=0
Lateral Weir WSCriteria=-1
Lateral Weir Flap Gates= 0
Lateral Weir Hagers EQN= 0 ,,,,,
Lateral Weir SS=0.05,0.05,
Lateral Weir Type= 0
Lateral Weir Connection Pos and Dist= 3 ,0
Lateral Weir SE= 15
       0  462.05      80   459.6     130  458.29     180   458.3     225   458.2
     270  459.52     280   459.6     295  460.03     400  459.98     498  461.03
     647  461.64   704.7  461.14   782.5  460.46  823.41  460.95 1002.92  459.94
Lateral Weir Centerline= 0
Lateral Weir HW RS User Defined=-1
Lateral Weir HW RS Station=145774,0
Lateral Weir HW RS Station=145405,416
Lateral Weir HW RS Station=145143,647
Lateral Weir HW RS Station=144901,872
Lateral Weir HW RS Station=144646,1003
Lateral Weir TW RS User Defined=-1
Lateral Weir TW RS Station=3681,0
Lateral Weir TW RS Station=3472,416
Lateral Weir TW RS Station=3336,647
Lateral Weir TW RS Station=3284,872
Lateral Weir TW RS Station=3231,1003
LW Div RC= 0 ,False,,

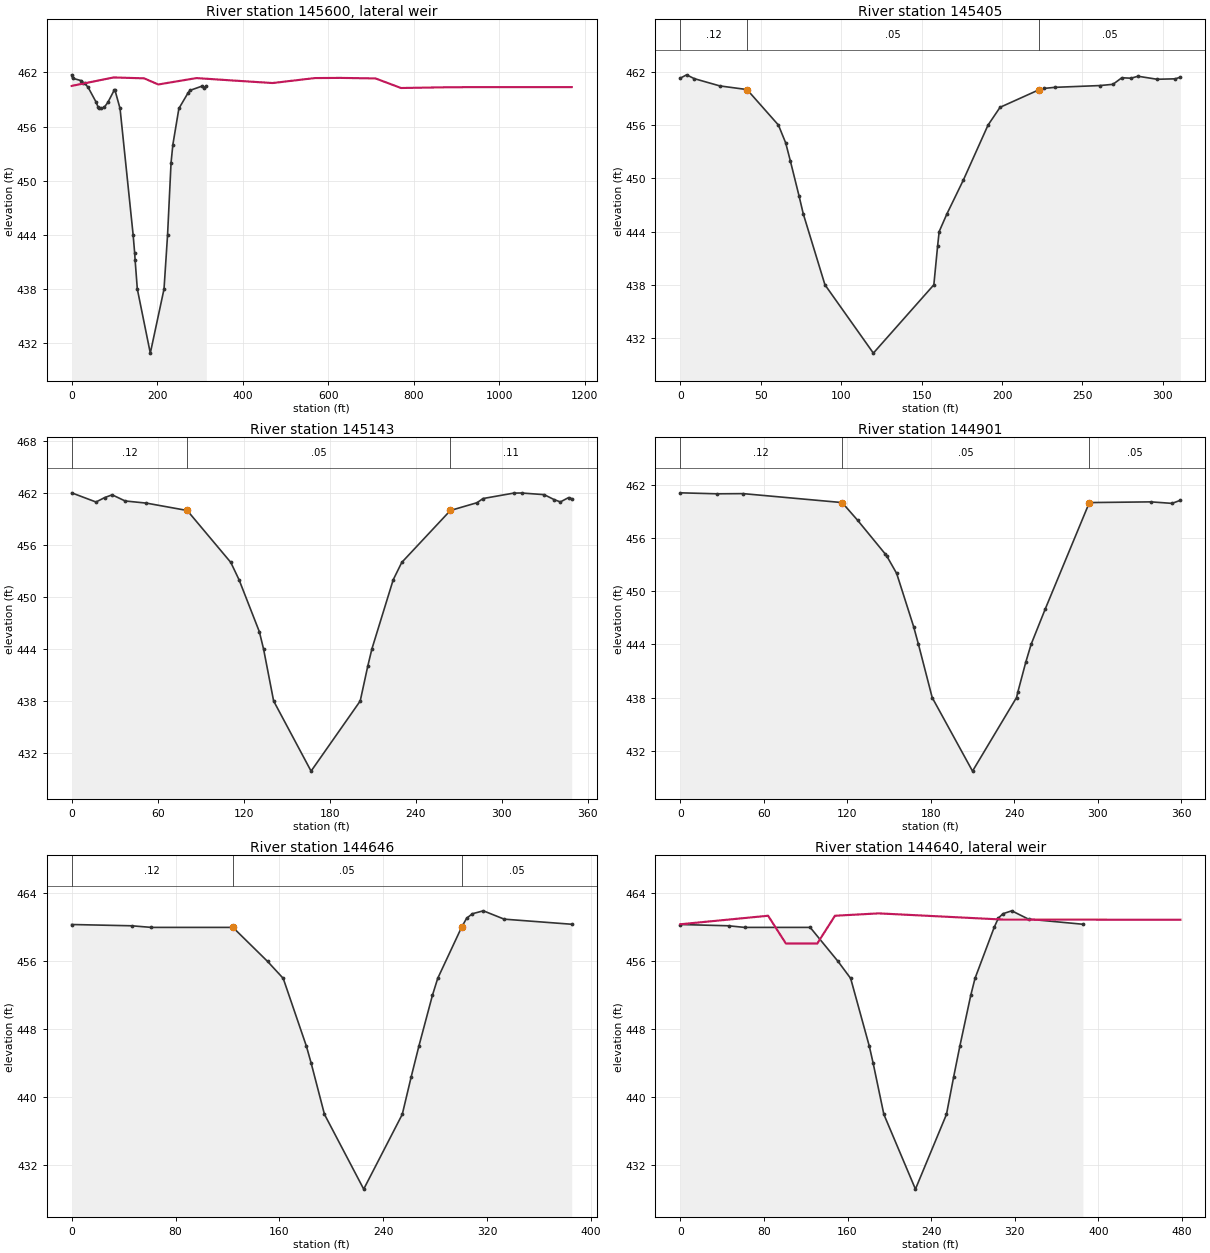
Type RM Length L Ch R = 6 ,145600  ,,,
Lateral Weir Pos= 3
Lateral Weir End=Elm Fork Split2 ,efs2            ,138967  ,
Lateral Weir Distance=0
Lateral Weir TW Multiple XS=-1
Lateral Weir WD=5
Lateral Weir Coef=2
Lateral Weir Is ZeroHeight=-1
LW OverFlow Method 2D=0
LW OverFlow Use Velocity Into 2D=0
Lateral Weir WSCriteria=-1
Lateral Weir Flap Gates= 0
Lateral Weir Hagers EQN= 0 ,,,,,
Lateral Weir SS=0.05,0.05,
Lateral Weir Type= 0
Lateral Weir Connection Pos and Dist= 0 ,0
Lateral Weir SE= 13
       0   460.5   98.02  461.44  169.58  461.34  202.73  460.66  291.84  461.37
  371.19  461.12  469.98  460.82  568.83  461.37  628.24  461.39  711.17  461.33
  770.47  460.27     890  460.36    1170  460.37
Lateral Weir Centerline= 0
Lateral Weir HW RS User Defined=-1
Lateral Weir HW RS Station=145774,0
Lateral Weir HW RS Station=145405,335
Lateral Weir HW RS Station=145143,630
Lateral Weir HW RS Station=144901,890
Lateral Weir HW RS Station=144646,1170
Lateral Weir TW RS User Defined=-1
Lateral Weir TW RS Station=138967  ,0
Lateral Weir TW RS Station=138769  ,335
Lateral Weir TW RS Station=138563  ,630
Lateral Weir TW RS Station=138334  ,890
Lateral Weir TW RS Station=138038  ,1380
LW Div RC= 0 ,False,,

Type RM Length L Ch R = 1 ,145405  ,245.53,258.84,276.49
BEGIN DESCRIPTION:
n updated to CDC 12/16/15 BG
END DESCRIPTION:
XS GIS Cut Line= 2
2439738.155013967065012.215450562439464.193619647065159.21909356
#Sta/Elev= 30
       0  461.29    3.89  461.66    8.64  461.23   24.56  460.41   41.45     460
   60.97     456   65.47     454   68.33     452   73.81     448   76.41     446
    89.9     438     120   430.3  157.61     438  159.97  442.41  160.92     444
  165.76     446  176.02  449.83  191.31     456  198.78     458  223.27     460
   226.2  460.13  232.82  460.25  260.73  460.45  268.97  460.59  274.48  461.33
  280.17  461.28  284.55   461.5  296.42  461.16  307.71  461.21  310.91   461.4
#Mann= 3 ,0,0
       0     .12       0   41.45     .05       0  223.27     .05       0
Bank Sta=41.45,223.27
XS Rating Curve= 0 ,0
Exp/Cntr=0.3,0.1

Type RM Length L Ch R = 1 ,145143  ,237.27,241.1,249.13
XS GIS Cut Line= 2
2439671.335265737064791.709986062439337.236196387064891.93977247
#Sta/Elev= 28
       0  462.04   16.96  460.98      23  461.49   28.24  461.81   37.29   461.1
   52.19  460.85   80.61     460  111.01     454  116.76     452  130.92     446
  133.86     444  140.88     438     167   429.9  201.27     438  206.51     442
   209.4     444  224.29     452  230.24     454  264.15     460  282.78   460.9
  286.93  461.38  308.42  462.01  313.79  462.02  329.62  461.83  336.51  461.26
  340.89  460.99  346.61  461.49  348.81  461.37
#Mann= 3 ,0,0
       0     .12       0   80.61     .05       0  264.15     .11       0
Bank Sta=80.61,264.15
XS Rating Curve= 0 ,0
Exp/Cntr=0.3,0.1

Type RM Length L Ch R = 1 ,144901  ,164.07,215.29,252.43
XS GIS Cut Line= 2
2439652.154529817064570.562462482439298.78154889 7064636.2647589
#Sta/Elev= 21
       0   461.1    26.4  460.99   45.12  461.01  116.28     460  127.43     458
  147.33  454.19  148.25     454  155.49     452  167.68     446  171.15     444
  181.02     438     210   429.7  241.63     438  242.54   438.6   248.3     442
   252.1     444  262.29     448  293.97     460  338.27  460.08   353.4  459.91
  359.43  460.26
#Mann= 3 ,0,0
       0     .12       0  116.28     .05       0  293.97     .05       0
Bank Sta=116.28,293.97
XS Rating Curve= 0 ,0
Exp/Cntr=0.3,0.1

Type RM Length L Ch R = 1 ,144646  ,193.35,199.16,204.24
XS GIS Cut Line= 3
2439683.218115977064443.052874982439593.174988977064418.75535139
2439308.218865987064355.02910089
#Sta/Elev= 21
       0  460.34   46.15  460.19   61.44     460  124.24     460  150.91     456
  162.99     454  180.89     446  184.56     444  194.77     438     225   429.2
  254.71     438  261.53  442.38  267.56  446.06  277.93     452  282.01     454
  300.36     460  304.29  461.08  308.75  461.61  317.19  461.95  333.24  460.97
  385.26  460.37
#Mann= 3 ,0,0
       0     .12       0  124.24     .05       0  300.36     .05       0
Bank Sta=124.24,300.36
XS Rating Curve= 0 ,0
Exp/Cntr=0.3,0.1

Type RM Length L Ch R = 6 ,144640  ,,,
Lateral Weir Pos= 3
Lateral Weir End=Elm Fork Split2 ,efs2            ,138334  ,
Lateral Weir Distance=0
Lateral Weir TW Multiple XS=-1
Lateral Weir WD=5
Lateral Weir Coef=2
Lateral Weir Is ZeroHeight=-1
LW OverFlow Method 2D=0
LW OverFlow Use Velocity Into 2D=0
Lateral Weir WSCriteria=-1
Lateral Weir Flap Gates= 1
Lateral Weir Hagers EQN= 0 ,,,,,
Lateral Weir SS=0.05,0.05,
Lateral Weir Type= 0
Lateral Weir Connection Pos and Dist= 0 ,280
Lateral Weir SE= 8
       0  460.37      84  461.37     101   458.1     131   458.1     148  461.37
  189.72  461.65  308.91  460.92  478.61   460.9
Lateral Weir Centerline= 0
Lateral Weir HW RS User Defined=-1
Lateral Weir HW RS Station=144646,0
Lateral Weir HW RS Station=144474,210
Lateral Weir HW RS Station=144215,478.61
Lateral Weir TW RS User Defined=-1
Lateral Weir TW RS Station=138334,-280
Lateral Weir TW RS Station=138038,210
Lateral Weir TW RS Station=137852,431
Lateral Weir TW RS Station=137770,615
LW Culv=2,7,7,55,0.015,0.5,1,8,1,442.28,442.86, 1 ,Culvert #1  , 0 ,
     116     116
LW Culvert Barrel=1,Barrel #1,0
LW Culv Bottom n=0.015
LW Div RC= 0 ,False,,

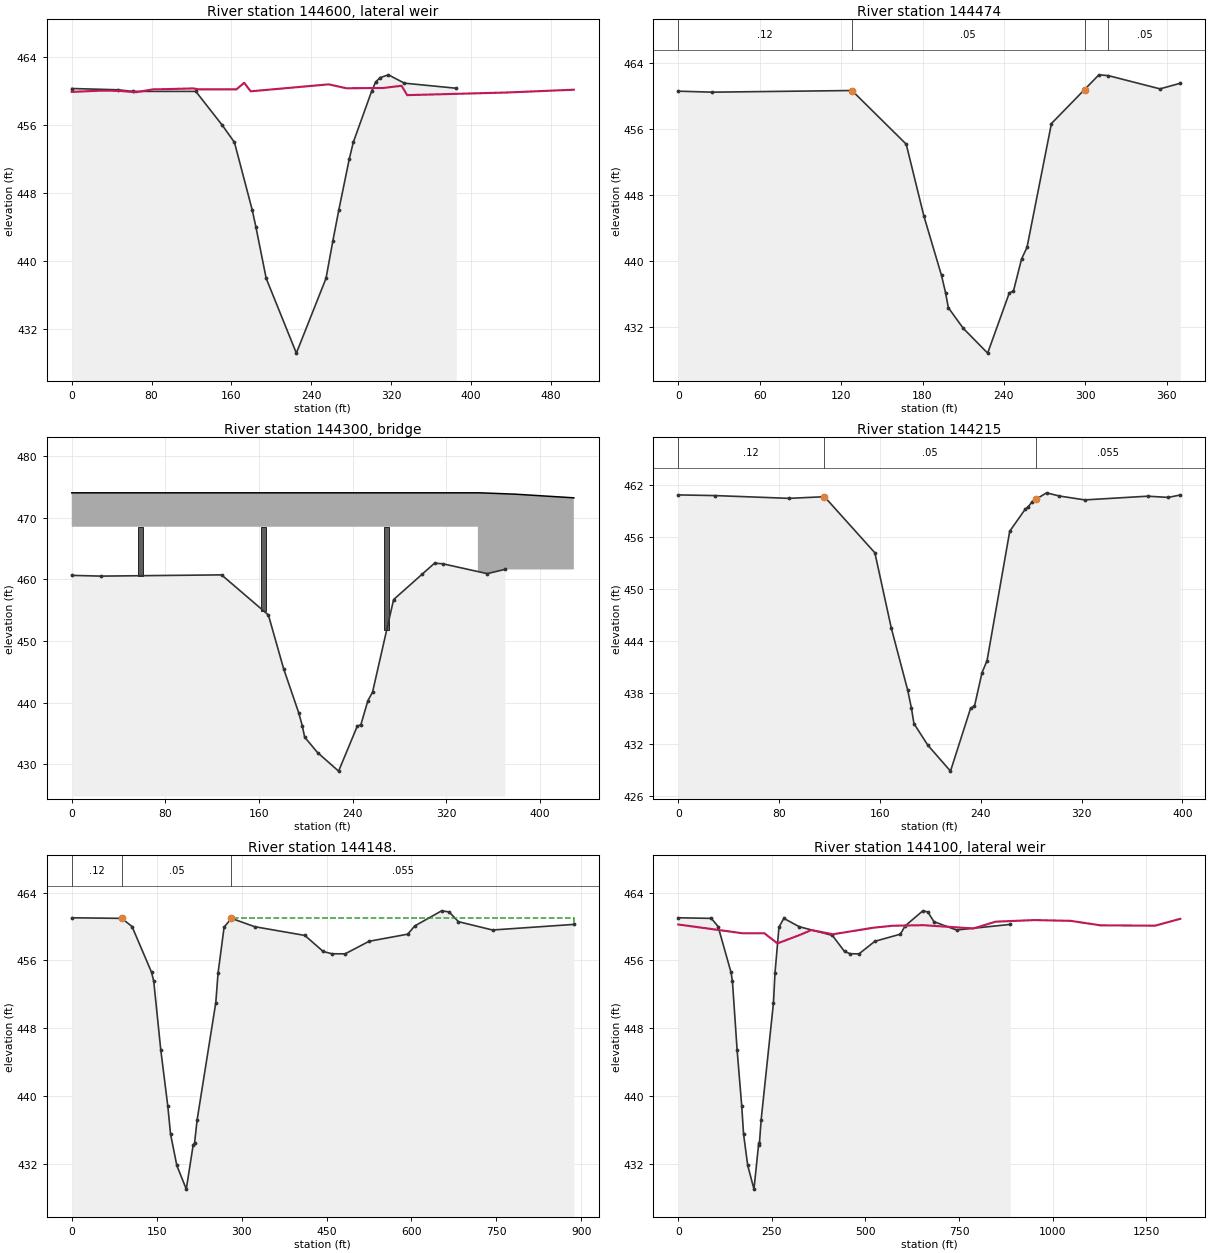
Type RM Length L Ch R = 6 ,144600  ,,,
Lateral Weir Pos= 0
Lateral Weir End=L-Overflow      ,efs3            ,3231    ,
Lateral Weir Distance=0
Lateral Weir TW Multiple XS=-1
Lateral Weir WD=5
Lateral Weir Coef=2
Lateral Weir Is ZeroHeight=-1
LW OverFlow Method 2D=0
LW OverFlow Use Velocity Into 2D=0
Lateral Weir WSCriteria=-1
Lateral Weir Flap Gates= 0
Lateral Weir Hagers EQN= 0 ,,,,,
Lateral Weir SS=0.05,0.05,
Lateral Weir Type= 0
Lateral Weir Connection Pos and Dist= 3 ,0
Lateral Weir SE= 18
       0  459.94   27.32  460.08   46.97  460.07   64.28   459.9   81.38  460.24
   91.65  460.26  121.23  460.35  127.48  460.24  165.06  460.24  172.73  461.02
  179.22  460.01   257.4  460.83  275.08  460.37  311.78   460.4  330.44  460.66
     336  459.56     436  459.87     503   460.2
Lateral Weir Centerline= 0
Lateral Weir HW RS User Defined=-1
Lateral Weir HW RS Station=144646  ,0
Lateral Weir HW RS Station=144474  ,192
Lateral Weir HW RS Station=144215  ,436
Lateral Weir HW RS Station=144148. ,503
Lateral Weir TW RS User Defined=-1
Lateral Weir TW RS Station=3231    ,0
Lateral Weir TW RS Station=3111    ,192
Lateral Weir TW RS Station=2915    ,436
Lateral Weir TW RS Station=2858    ,503
LW Div RC= 0 ,False,,

Type RM Length L Ch R = 1 ,144474  ,247.02,255.22,261.23
BEGIN DESCRIPTION:
144474
END DESCRIPTION:
XS GIS Cut Line= 3
2439728.731804487064256.229101642439558.584178887064208.84271348
2439372.584550897064156.05148047
#Sta/Elev= 20
       0  460.62      25   460.5     128   460.7     168   454.2     181   445.5
     194   438.3     197   436.2     199   434.4     210   431.9     228  428.89
     244   436.2     247   436.4     253   440.3     257   441.7     275   456.7
  299.37  460.81     310   462.6     317   462.5     355   460.9  369.97  461.58
#Mann= 4 ,-1,0
       0     .12       0     128     .05       0  299.37      .1       0
     317     .05       0
Bank Sta=128,299.37
XS Rating Curve= 0 ,0
Exp/Cntr=0.3,0.1

Type RM Length L Ch R = 3 ,144300  ,,,
Bridge Culvert--1,0,-1,-1, 0
Deck Dist Width WeirC Skew NumUp NumDn MinLoCord MaxHiCord MaxSubmerge Is_Ogee
160,83,2.6,0, 5, 5, , , 0.98, 0, 0,0,,
       0     347     349     379     429
     474     474     474  473.78  473.19
   468.5   468.5
       0     343     345     375     425
     474     474     474  473.78  473.19
   468.5   468.5
Pier Skew, UpSta & Num, DnSta & Num=  ,59, 2 ,55, 2 , 0 , 0 , 0 ,,
       4       4
     420   468.5
       4       4
     420   468.5
Pier Skew, UpSta & Num, DnSta & Num=  ,164, 2 ,160, 2 , 0 , 0 , 0 ,,
       4       4
     420   468.5
       4       4
     420   468.5
Pier Skew, UpSta & Num, DnSta & Num=  ,269, 2 ,265, 2 , 0 , 0 , 0 ,,
       4       4
     420   468.5
       4       4
     420   468.5
Abutment Skew #Up #Dn= , 2 , 2
     295     347
   455.5   468.5
     291     343
   455.5   468.5
BR Coef=-1 , 0 , 0 ,, 0 ,,,0.8,-1,,0,
WSPro=,,,, 1 ,,,, 0 ,,,, 0 ,,,,-1 ,-1 ,-1 , 0 , 0 , 0 , 0 , 0
BR U #Sta/Elev= 20
       0  460.62      25   460.5     128   460.7     168   454.2     181   445.5
     194   438.3     197   436.2     199   434.4     210   431.9     228  428.89
     244   436.2     247   436.4     253   440.3     257   441.7     275   456.7
  299.37 460.808     310   462.6     317   462.5     355   460.9  369.97  461.58
BR U #Mann= 4
       0     .12     128    .052  299.37      .1     317     .05
BR D #Sta/Elev= 33
       0  460.91   15.13  460.86    29.4  460.83      88  460.51     116   460.7
     156   454.2     169   445.5     182   438.3     185   436.2     187   434.4
     198   431.9     216  428.89     232   436.2     235   436.4     241   440.3
     245   441.7     263   456.7  275.42  459.28  277.53   459.5  280.68  460.11
  283.88  460.41  292.23  461.15  302.41  460.78   317.3   460.4  322.57  460.33
  334.79  460.46  336.13  460.44  339.19   460.5  354.66  460.61  359.99   460.7
  372.43  460.76  388.78  460.62  398.33   460.9
BR D #Mann= 3
       0     .12     116    .052  283.88    .055
BC Design=,, 0 ,, 0 ,,,,,,
BC Use User HTab Curves=0
BC User HTab FreeFlow(D)= 0

Type RM Length L Ch R = 1 ,144215  ,58.46,66.26,73.83
BEGIN DESCRIPTION:
144314
Added cross-section
END DESCRIPTION:
XS GIS Cut Line= 3
2439797.230683227064022.591445572439782.736617717064018.25451198
2439420.335439647063893.71998414
#Sta/Elev= 26
       0  460.91    29.4  460.83      88  460.51     116   460.7     156   454.2
     169   445.5     182   438.3     185   436.2     187   434.4     198   431.9
     216  428.89     232   436.2     235   436.4     241   440.3     245   441.7
     263   456.7  275.42  459.28  277.53   459.5  280.68  460.11  283.88  460.41
  292.23  461.15  302.41  460.78  322.57  460.33  372.43  460.76  388.78  460.62
  398.33   460.9
#Mann= 3 ,-1,0
       0     .12       0     116     .05       0  283.88    .055       0
Bank Sta=116,283.88
XS Rating Curve= 0 ,0
Exp/Cntr=0.3,0.1

Type RM Length L Ch R = 1 ,144148. ,410.4,401.61,382.07
BEGIN DESCRIPTION:
144148
LOB moved up 2 points 12/28/15
Added XS for Lewisville Atheltic Complex CLOMR.
END DESCRIPTION:
XS GIS Cut Line= 2
2439812.592857237063970.228033232438991.611887637063634.69688015
#Sta/Elev= 30
       0  461.02   88.43  460.95  106.44  459.99  140.99  454.59  144.78  453.54
  157.23  445.45  169.69  438.79  174.48  435.53  185.56  431.83  202.28  429.04
  214.56  434.28  216.87  434.44  221.47  437.22  254.42  451.02  258.41   454.5
  269.12  459.93  282.13  460.95  323.16  459.97  411.77  458.94   444.1  457.05
  459.48  456.78  482.88  456.77  525.16  458.25  593.47  459.09  605.91  460.06
   653.3  461.84  666.46  461.71  683.09  460.56  743.29  459.58   886.9  460.24
#Mann= 3 ,-1,0
       0     .12       0   88.43     .05       0  282.13    .055       0
#XS Ineff= 2 , 0
                          287.44          461.04
Permanent Ineff=
       F       F
Bank Sta=88.43,282.13
XS Rating Curve= 0 ,0
Exp/Cntr=0.3,0.1

Type RM Length L Ch R = 6 ,144100  ,,,
Lateral Weir Pos= 0
Lateral Weir End=L-Overflow      ,efs3            ,2858    ,
Lateral Weir Distance=0
Lateral Weir TW Multiple XS=-1
Lateral Weir WD=5
Lateral Weir Coef=2
Lateral Weir Is ZeroHeight=-1
LW OverFlow Method 2D=0
LW OverFlow Use Velocity Into 2D=0
Lateral Weir WSCriteria=-1
Lateral Weir Flap Gates= 0
Lateral Weir Hagers EQN= 0 ,,,,,
Lateral Weir SS=0.05,0.05,
Lateral Weir Type= 0
Lateral Weir Connection Pos and Dist= 3 ,0
Lateral Weir SE= 17
       0  460.23  170.99   459.2     230   459.2     265     458     325     459
  355.39  459.57  413.53  459.08  521.63  459.85  572.52  460.08  654.28  460.15
  788.18  459.76  847.79  460.56  951.19  460.75 1048.08  460.66 1127.54  460.13
 1273.58  460.09    1341   460.9
Lateral Weir Centerline= 0
Lateral Weir HW RS User Defined=-1
Lateral Weir HW RS Station=144148.,0
Lateral Weir HW RS Station=143756,423
Lateral Weir HW RS Station=143265,930
Lateral Weir HW RS Station=142900,1341
Lateral Weir TW RS User Defined=-1
Lateral Weir TW RS Station=2858,0
Lateral Weir TW RS Station=2470,423
Lateral Weir TW RS Station=1985,930
Lateral Weir TW RS Station=1304,1341
LW Div RC= 0 ,False,,