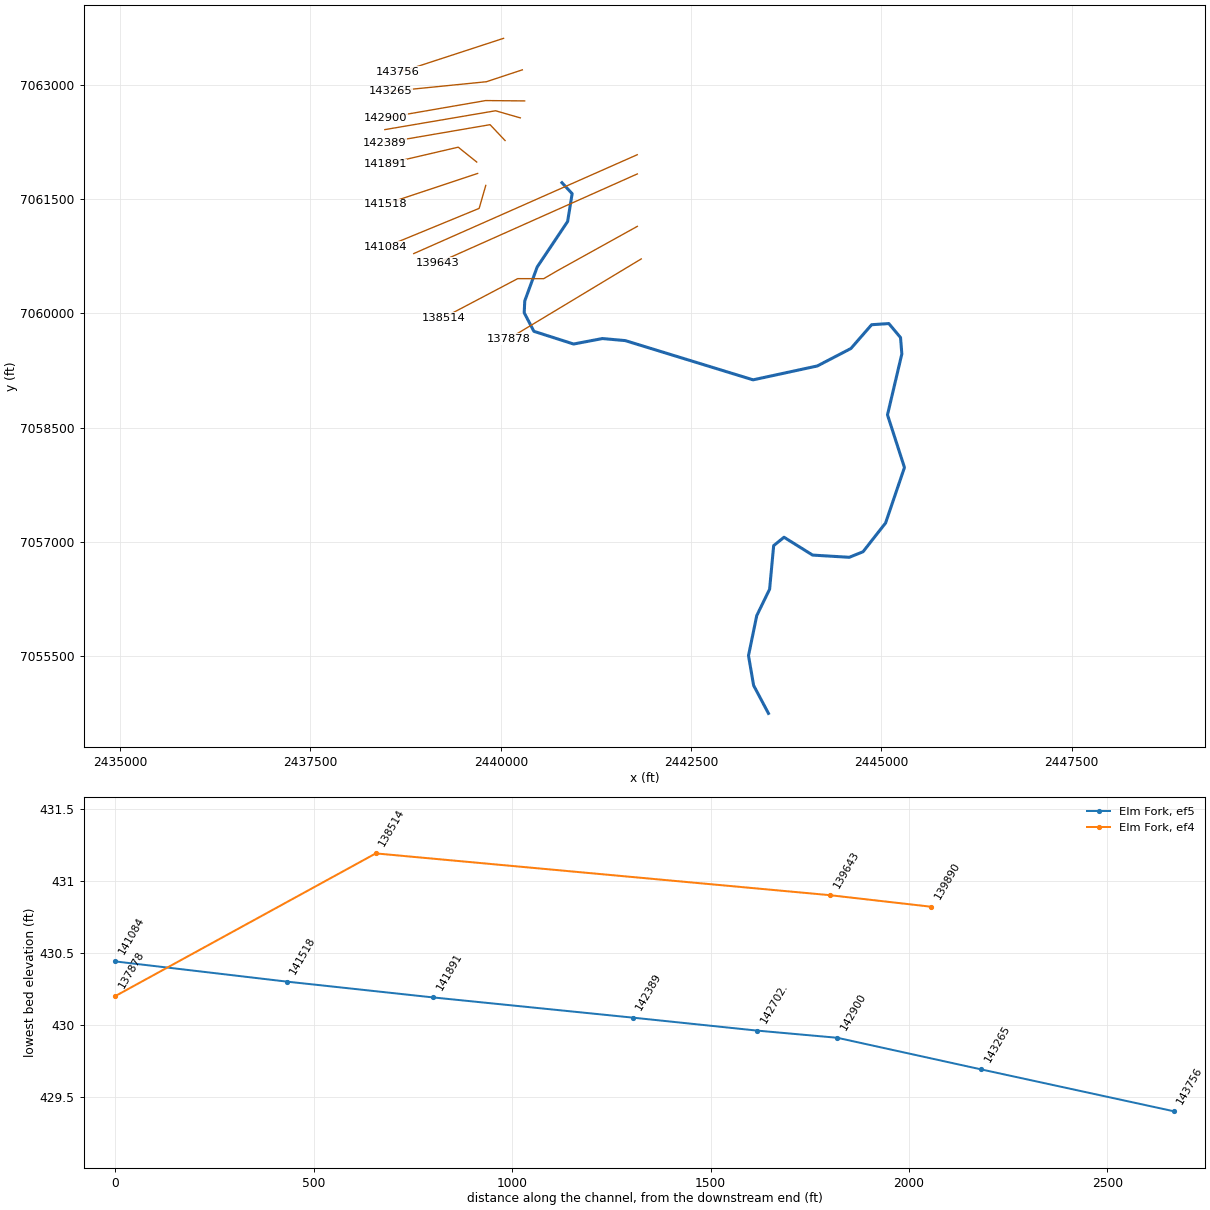
HEC-RAS study CDC_Consolidated_Model.prj: Upper Trinity CDC Consolidated Model

--- CDC_Consolidated_Model.g12 (geometry) --- (continued)

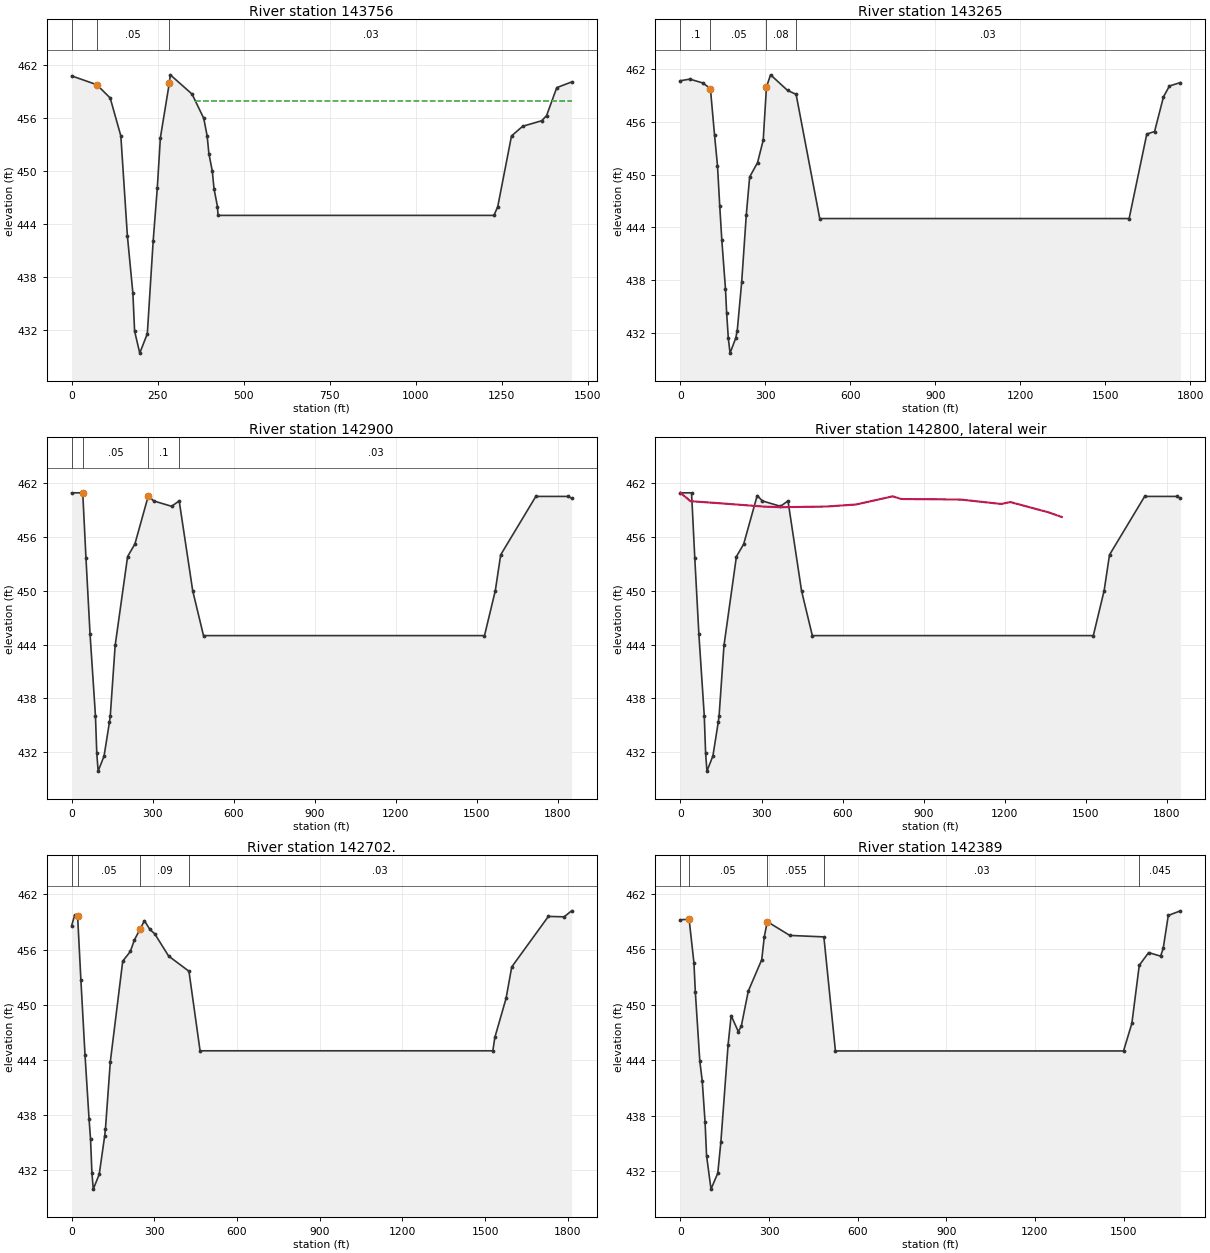
Type RM Length L Ch R = 1 ,143756  ,483.08,484.38,452.53
BEGIN DESCRIPTION:
143756
Proposed Park Improvements - 13187.64-14694.95
END DESCRIPTION:
XS GIS Cut Line= 3
2440036.451661477063618.245141392438700.961878397063181.96648639
 2438652.36322237063177.97305606
#Sta/Elev= 30
       0   460.8      73   459.8     112   458.3     143     454     162   442.7
     178   436.2     183   431.9     198   429.4     220   431.6     237   442.1
     249   448.1     258   453.8     284     460  286.86  460.92  350.05  458.74
     384     456     394     454     399     452     409     450     414     448
     424     446  425.51     445 1228.05     445    1239     446    1279     454
 1311.29  455.09 1366.77  455.72 1380.94   456.3 1410.58  459.47 1453.71  460.11
#Mann= 3 ,0,0
       0     .12       0      73     .05       0     284     .03       0
#XS Ineff= 2 , 0
                          361.46             458
Permanent Ineff=
       F       T
Bank Sta=73,284
XS Rating Curve= 0 ,0
Exp/Cntr=0.3,0.1

Type RM Length L Ch R = 1 ,143265  ,394.85,363.29,360.57
XS GIS Cut Line= 3
2440283.132270477063203.965130062439811.656835477063047.71248981
2438549.622286057062921.01195581
#Sta/Elev= 30
       0  460.68   32.92  460.86   78.38  460.43  105.65  459.79  120.25  454.49
  130.65  451.03  138.51  446.48  145.98  442.53  158.88  436.99  162.92  434.28
  168.93  431.37  175.02  429.69  195.04   431.4  200.39  432.24  215.97  437.73
  232.35  445.42  244.22  449.73  272.02  451.36  292.13  453.92  303.55  459.97
  318.06  461.35  377.94  459.58  408.24  459.13  491.65     445 1583.99     445
 1646.32  454.61 1673.81   454.9 1705.31  458.85 1726.29  460.08 1765.07  460.47
#Mann= 4 ,-1,0
       0      .1       0  105.65     .05       0  303.55     .08       0
  408.24     .03       0
#XS Ineff= 2 , 0
                          391.75             454
Permanent Ineff=
       F       T
Bank Sta=105.65,303.55
XS Rating Curve= 0 ,0
Exp/Cntr=0.3,0.1

Type RM Length L Ch R = 1 ,142900  ,223.14,202.73,220.73
BEGIN DESCRIPTION:
142900
Proposed Park Improvements
END DESCRIPTION:
XS GIS Cut Line= 3
2440313.501960387062795.300264982439801.955083227062799.98988815
2438482.719532717062571.69670956
#Sta/Elev= 25
       0   460.9      41   460.9      53   453.6      68   445.2      88   436.1
      93   431.9      98  429.91     120   431.6     140   435.4     143   436.1
     161   443.9     207   453.8     234   455.2     284   460.6     303     460
     370   459.4     398     460     448     450     488     445    1528     445
    1568     450    1588     454    1718   460.5    1838   460.5 1850.41   460.3
#Mann= 4 ,-1,0
       0     .12       0      41     .05       0     284      .1       0
     398     .03       0
#XS Ineff= 2 , 0
                          464.68             447
Permanent Ineff=
       F       T
Bank Sta=41,284
XS Rating Curve= 0 ,0
Exp/Cntr=0.3,0.1

Type RM Length L Ch R = 6 ,142800  ,,,
Lateral Weir Pos= 0
Lateral Weir End=L-Overflow      ,efs3            ,1304    ,
Lateral Weir Distance=0
Lateral Weir TW Multiple XS=-1
Lateral Weir WD=5
Lateral Weir Coef=2
Lateral Weir Is ZeroHeight=-1
LW OverFlow Method 2D=0
LW OverFlow Use Velocity Into 2D=0
Lateral Weir WSCriteria=-1
Lateral Weir Flap Gates= 0
Lateral Weir Hagers EQN= 0 ,,,,,
Lateral Weir SS=0.05,0.05,
Lateral Weir Type= 0
Lateral Weir Connection Pos and Dist= 3 ,0
Lateral Weir SE= 15
       0   460.9   36.76  459.97  153.84  459.72  312.01  459.36  372.13   459.3
   538.2  459.37   649.7   459.6  785.17  460.51  817.16  460.21  958.92  460.18
 1039.81  460.14 1187.42  459.66    1221  459.87 1363.04  458.72 1411.11  458.21
Lateral Weir Centerline= 0
Lateral Weir HW RS User Defined=-1
Lateral Weir HW RS Station=142900  ,0
Lateral Weir HW RS Station=142702. ,230
Lateral Weir HW RS Station=142389  ,594
Lateral Weir HW RS Station=141891  ,1071
Lateral Weir HW RS Station=141518  ,1221
Lateral Weir HW RS Station=141084  ,1412
Lateral Weir TW RS User Defined=-1
Lateral Weir TW RS Station=1304    ,0
Lateral Weir TW RS Station=838     ,230
Lateral Weir TW RS Station=694     ,594
Lateral Weir TW RS Station=666     ,1071
Lateral Weir TW RS Station=612     ,1221
Lateral Weir TW RS Station=568     ,1412
LW Div RC= 0 ,False,,

Type RM Length L Ch R = 1 ,142702. ,346,313.16,243.63
BEGIN DESCRIPTION:
142702
Added XS for Lewisville Atheltic Complex CLOMR.
END DESCRIPTION:
XS GIS Cut Line= 3
2440256.699580557062572.298414392439931.224509727062665.84022206
2438477.144740727062418.04741056
#Sta/Elev= 30
       0  458.61   11.17  459.78   21.56  459.67   33.53  452.67   48.49  444.52
   63.19  437.55   68.45  435.42   73.43  431.75   78.42  429.96   99.99  431.57
  119.59   435.7  122.53  436.49  140.18   443.8  185.27  454.75  212.86   455.8
  227.82  457.07  248.21  458.23  263.95  459.15  283.37  458.21   301.4  457.72
  351.83   455.3  425.53  453.65  465.87     445    1528     445 1535.18  446.45
 1576.05  450.71 1596.49  454.12 1729.34  459.61 1786.71  459.57 1813.69  460.22
#Mann= 4 ,-1,0
       0     .12       0   21.56     .05       0  248.21     .09       0
  425.53     .03       0
Bank Sta=21.56,248.21
XS Rating Curve= 0 ,0
Exp/Cntr=0.3,0.1

Type RM Length L Ch R = 1 ,142389  ,478.69,502.3,356.1
XS GIS Cut Line= 3
2440056.373209557062274.299338472439859.210218067062482.88947248
2438473.964957067062245.04513189
#Sta/Elev= 30
       0  459.19   29.23  459.25   45.56  454.54   50.22  451.41   65.36  443.93
   73.74  441.73   83.26   437.3   88.29  433.68  103.36  430.05  126.31  431.78
  136.74  435.15  161.13  445.64  171.53  448.83  195.83  447.09  205.92  447.69
   229.5  451.47  275.13  454.88  283.69  457.34  293.87  458.99  370.05   457.5
  485.47  457.34  524.57     445    1500     445  1528.2  447.99 1553.22  454.27
  1584.9  455.64 1625.46  455.26 1634.28   456.1 1651.43  459.66 1692.54  460.16
#Mann= 5 ,-1,0
       0     .12       0   29.23     .05       0  293.87    .055       0
  485.47     .03       0 1553.22    .045       0
Bank Sta=29.23,293.87
XS Rating Curve= 0 ,0
Exp/Cntr=0.3,0.1

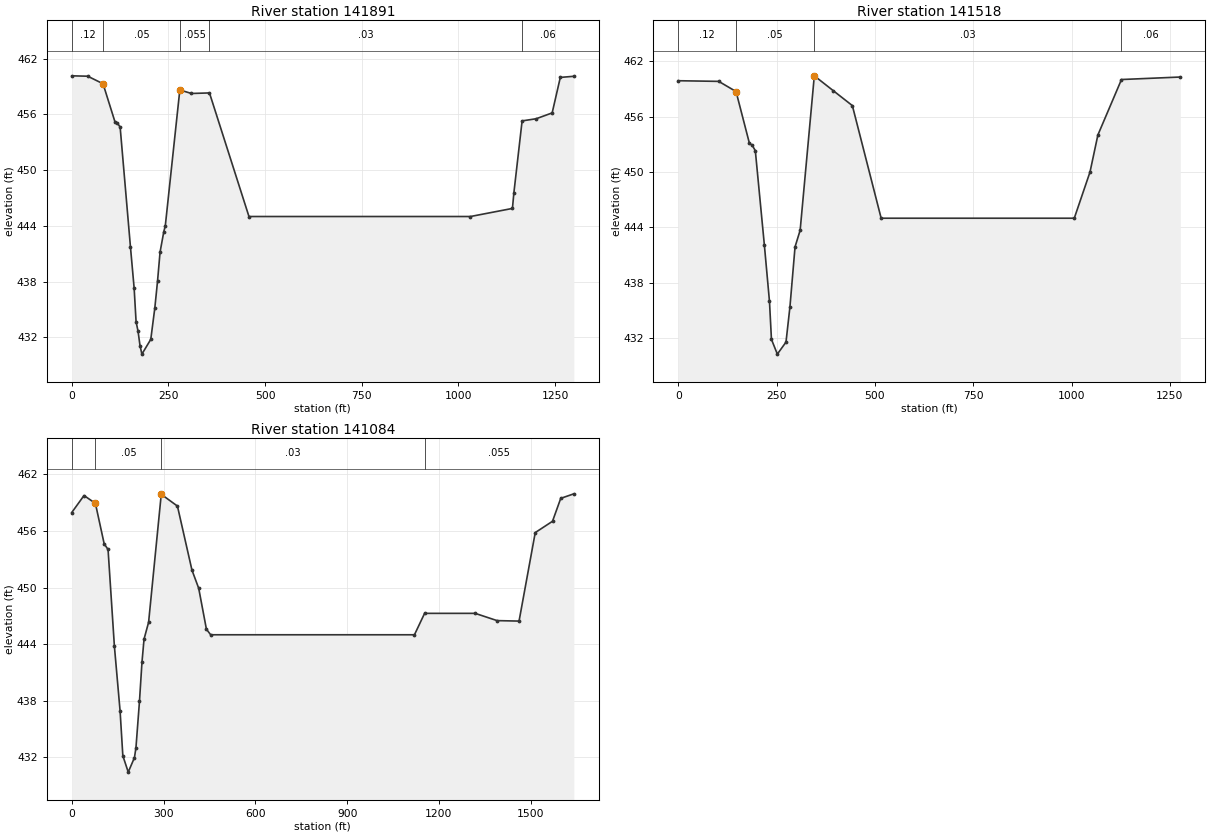
Type RM Length L Ch R = 1 ,141891  ,211.7,369.28,456.69
BEGIN DESCRIPTION:
141891
Added XS for Lewisville Atheltic Complex CLOMR.
END DESCRIPTION:
XS GIS Cut Line= 3
2439684.471722387061991.272673562439440.918403717062186.91565497
2438480.731347727061963.32062973
#Sta/Elev= 30
       0  460.14   41.09   460.1   80.83  459.29  111.54  455.21  117.86  455.06
  125.09  454.62  151.74  441.73  161.26   437.3  166.29  433.68  171.49  432.63
  176.42  431.11  181.36  430.19  204.31  431.78  214.74  435.15  221.84  438.07
   228.3  441.17  238.03  443.38  241.86     444  279.41  458.62  309.42  458.24
  356.07   458.3  458.19     445    1031     445 1139.49  445.87 1143.31  447.58
 1164.49  455.29 1200.76  455.52 1242.22  456.15 1263.29  459.97 1298.28  460.09
#Mann= 5 ,-1,0
       0     .12       0   80.83     .05       0  279.41    .055       0
  356.07     .03       0 1164.49     .06       0
Bank Sta=80.83,279.41
XS Rating Curve= 0 ,0
Exp/Cntr=0.3,0.1

Type RM Length L Ch R = 1 ,141518  ,246.52,431.69,493.6
BEGIN DESCRIPTION:
141518
Proposed Park Improvements
END DESCRIPTION:
XS GIS Cut Line= 2
2439696.058641467061841.726384732438484.872415567061438.31708656
#Sta/Elev= 23
       0  459.87     103   459.8     147   458.7     181   453.1     188   452.9
     196   452.3     219   442.1     232     436     237   431.9     252   430.3
     274   431.6     284   435.4     297   441.9     310   443.7     346   460.4
     394   458.8  442.72  457.18  515.95     445    1007     445    1047     450
    1067     454    1127     460  1276.6  460.27
#Mann= 4 ,-1,0
       0     .12       0     147     .05       0     346     .03       0
    1127     .06       0
Bank Sta=147,346
XS Rating Curve= 0 ,0
Exp/Cntr=0.3,0.1

Type RM Length L Ch R = 1 ,141084  ,735.17,1206.23,331.19
BEGIN DESCRIPTION:
141084
Added XS for Lewisville Atheltic Complex CLOMR.
Swale normal pool elevation 453.5
END DESCRIPTION:
XS GIS Cut Line= 3
2439802.91472697 7061684.33365492439715.718379057061382.08983681
2438489.299900137060877.03605689
#Sta/Elev= 30
       0  457.96   40.02  459.76   77.21  458.93  105.94  454.64  118.61  454.04
  139.27   443.8  157.92  436.92   166.9  432.18  184.57  430.44  204.88  431.98
  209.82  433.04  221.29  437.95   229.4  442.07  236.21  444.54  251.13  446.33
  292.45  459.89  345.35  458.64  392.74  451.86  414.84  449.93  440.08  445.59
     454     445    1120     445 1153.13  447.27 1318.43  447.27 1390.06   446.5
 1461.85  446.45 1514.72  455.83 1571.16  457.03 1598.07  459.46 1640.91  459.94
#Mann= 4 ,-1,0
       0     .11       0   77.21     .05       0  292.45     .03       0
 1153.13    .055       0
Bank Sta=77.21,292.45
XS Rating Curve= 0 ,0
Exp/Cntr=0.3,0.1

River Reach=Elm Fork        ,ef4
Reach XY= 30
 2440803.7829693 7061719.63722992440937.50563364 7061575.5169434
2440878.233770557061210.014065472440478.228993137060611.51329398
2440315.010159467060165.010906152440307.725397147060009.97479889
2440434.985969387059765.478568732440956.50100248 7059598.4972754
2441335.520913727059670.486304642441635.477662897059643.48045315
2443314.770564147059127.477220062444158.771172727059309.99194689
2444599.738794717059539.510844812444872.267121057059852.48626873
2445098.231236067059867.481645552445252.019642387059683.47676423
2445268.988768557059467.498521642445080.496363397058667.00471582
2445303.47623238 7057975.01430192445055.747069057057245.98557623
2444759.757831637056867.518813482444578.728338057056794.02486598
2444096.750299387056823.011028482443721.246129147057057.48431282
 2443585.25493137056947.515372652443531.736337567056374.52472073
2443363.009968977056027.471609062443254.480658477055501.00382997
2443321.774487147055109.001005052443516.631613697054741.58965819

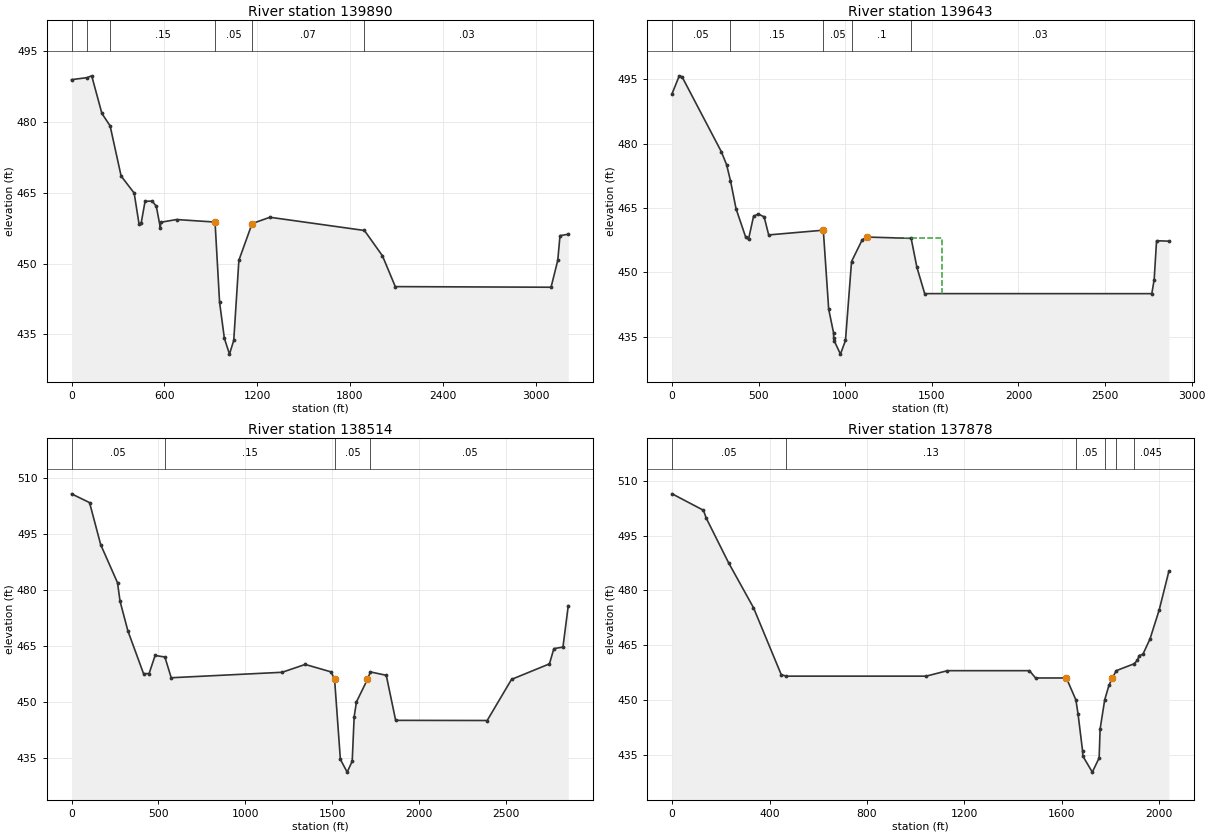
Type RM Length L Ch R = 1 ,139890  ,248.08,254.42,372.2
BEGIN DESCRIPTION:
n updated to CDC 12/16/15 BG
139890
Added XS for Lewisville Atheltic Complex CLOMR.
Swale normal pool elevation 453.5
END DESCRIPTION:
XS GIS Cut Line= 2
2441793.06888314 7062087.77740182438856.738141647060787.81313823
#Sta/Elev= 30
       0     489   99.79  489.42  130.54  489.81  196.46  481.84  249.62   479.2
  320.73  468.57  405.05  464.96  436.74  458.37  449.95  458.51   475.4   463.2
  521.21  463.27  548.06  462.17  574.14  457.66  576.94  458.77  679.58  459.35
  927.94  458.81  957.17  441.81  988.28  434.15 1021.28  430.82 1048.79  433.74
 1081.99  450.71 1167.37  458.49 1282.55  459.83  1893.5  457.03 2009.83  451.67
 2093.09  445.13    3100     445  3143.4  450.72 3157.79  455.93 3211.22  456.23
#Mann= 6 ,-1,0
       0     .05       0   99.79     .09       0  249.62     .15       0
  927.94     .05       0 1167.37     .07       0  1893.5     .03       0
Bank Sta=927.94,1167.37
XS Rating Curve= 0 ,0
Exp/Cntr=0.3,0.1

Type RM Length L Ch R = 1 ,139643  ,732.06,1144.33,1021.86
BEGIN DESCRIPTION:
n values updated to CDC 12/16/15 BG
139643
---------------------------------------------------------------------
CDC LEW110305-1 Lewisville Athletic Complex
Cross-section 139643 - 146373
Project located in ROB.
---------------------------------------------------------------------
END DESCRIPTION:
XS GIS Cut Line= 2
2441794.045587237061835.381909222439174.835274477060665.72775248
#Sta/Elev= 30
       0  491.67   41.17   495.8   57.12  495.59   284.5  478.08  314.48  475.08
  336.95  471.33  369.14   464.8  425.21  458.13  441.13  457.68  470.28  463.06
  497.09  463.58  531.33  462.91  557.59   458.7     873   459.8     904   441.4
     932   435.9     933   434.6     937   433.9     972   430.9    1001   434.1
    1036   452.5    1098   457.6    1126   458.2 1380.23   457.9 1413.27  451.17
 1458.39  445.01  2769.9     445 2783.52  448.29  2797.3  457.35 2868.51  457.24
#Mann= 5 ,-1,0
       0     .05       0  336.95     .15       0     873     .05       0
    1036      .1       0 1380.23     .03       0
#XS Ineff= 1 ,-1
    1286    1560     458
Permanent Ineff=
       T
Bank Sta=873,1126
XS Rating Curve= 0 ,0
Exp/Cntr=0.3,0.1

Type RM Length L Ch R = 1 ,138514  ,468.45,656.14,695.62
BEGIN DESCRIPTION:
n value updated to CDC. 12/16/15 BG
138514
ROCK RIP RAP PORTION OF POND
END DESCRIPTION:
XS GIS Cut Line= 5
2441794.193224717061145.68217315 2440748.0932828 7060565.2374679
2440563.837417727060457.832170892440222.638296987060458.25605457
2439244.625161147059942.96541847
#Sta/Elev= 30
       0  505.64   103.8  503.29  167.78  492.05  264.48  481.86  279.18   476.9
  324.19  468.97  414.18  457.54     446  457.55  480.66  462.39  536.93  461.99
  573.29  456.44    1211   457.9  1343.8     460  1492.6     458  1512.7     456
    1546   434.6    1585  431.19    1614   434.1  1625.2     446  1638.5     450
  1701.8     456  1718.6     458 1809.85  457.09 1863.81  445.04    2390     445
    2530     456 2748.05  460.15  2773.5  464.23 2825.67  464.64 2856.28  475.72
#Mann= 4 ,-1,0
       0     .05       0  536.93     .15       0  1512.7     .05       0
  1718.6     .05       0
#XS Ineff= 2 , 0
                            1745             452
Permanent Ineff=
       F       T
Bank Sta=1512.7,1701.8
XS Rating Curve= 0 ,0
Exp/Cntr=0.3,0.1

Type RM Length L Ch R = 1 ,137878  ,423.34,542.03,612.8
BEGIN DESCRIPTION:
n value updated to CDC 12/16/15 BG
137878
END DESCRIPTION:
XS GIS Cut Line= 3
2441845.720680717060717.937621822440973.188633137060191.39832056
 2440099.38001337059664.73795655
#Sta/Elev= 30
       0  506.46  128.67  501.95  139.68  499.85  231.81  487.56  333.88  475.28
     448   456.9     469   456.5    1043   456.5  1130.2     458  1466.8     458
    1492     456  1618.5     456  1657.5     450  1666.7     446    1685     436
    1686   434.6    1725   430.2    1753   434.1    1757     442  1775.8     450
  1793.3     454  1807.4     456  1823.2     458 1895.77  459.87 1910.07   460.8
 1917.17  462.15 1932.53  462.47 1961.96  466.73 1999.54  474.65 2039.35  485.27
#Mann= 6 ,-1,0
       0     .05       0     469     .13       0  1657.5     .05       0
  1775.8      .1       0  1823.2     .07       0 1895.77    .045       0
Bank Sta=1618.5,1807.4
XS Rating Curve= 0 ,0
Exp/Cntr=0.3,0.1