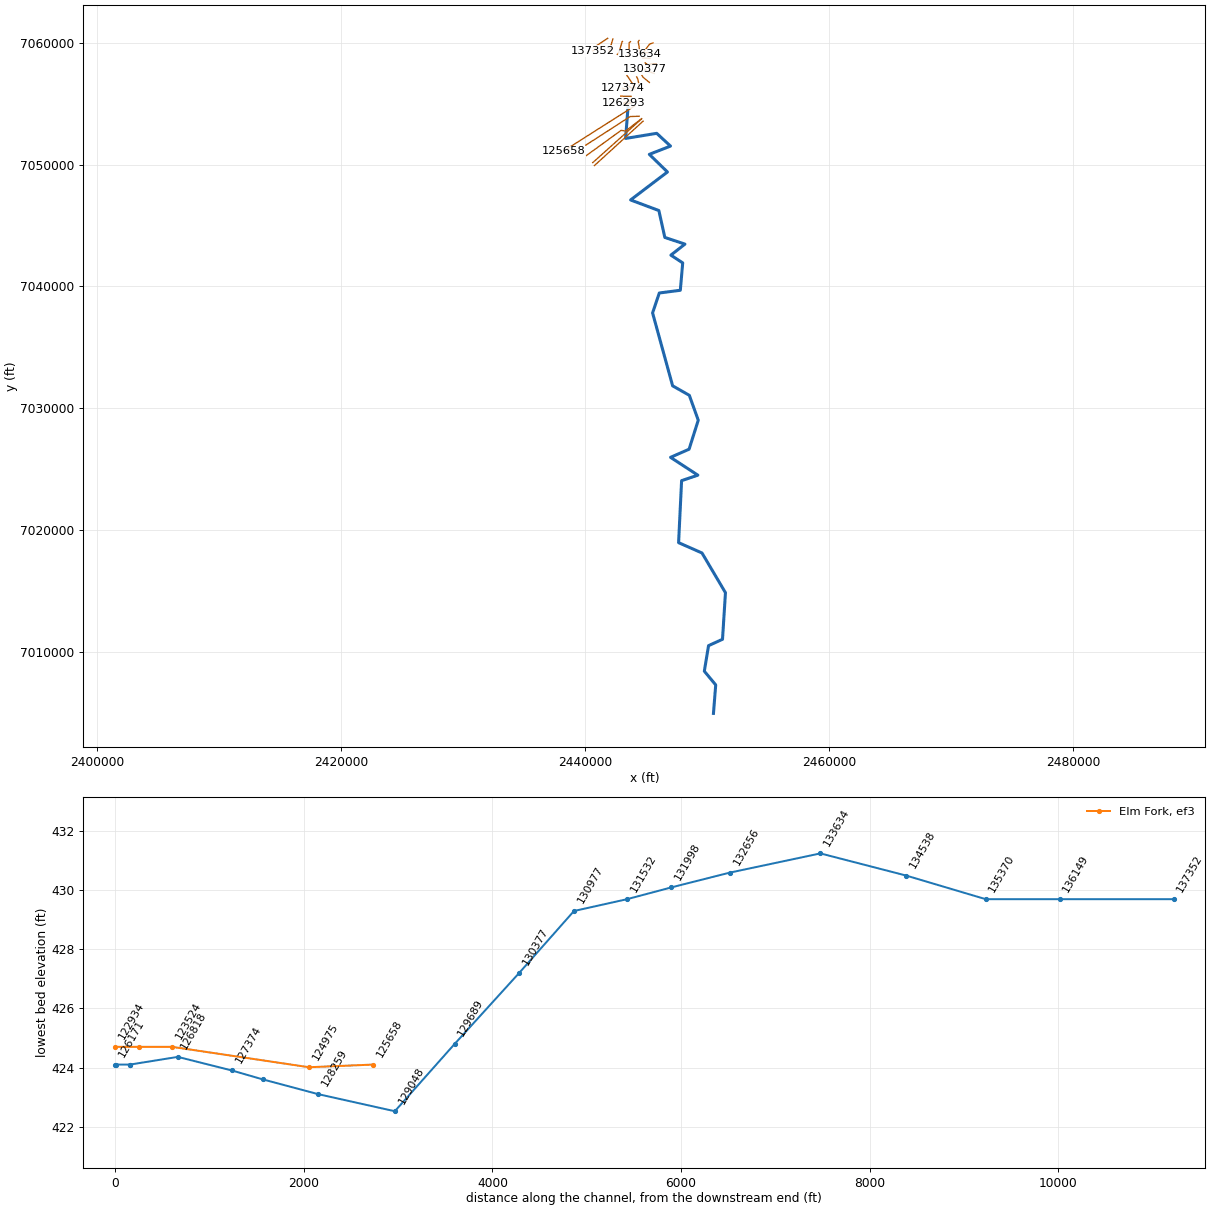
HEC-RAS study CDC_Consolidated_Model.prj: Upper Trinity CDC Consolidated Model

--- CDC_Consolidated_Model.g12 (geometry) --- (continued)

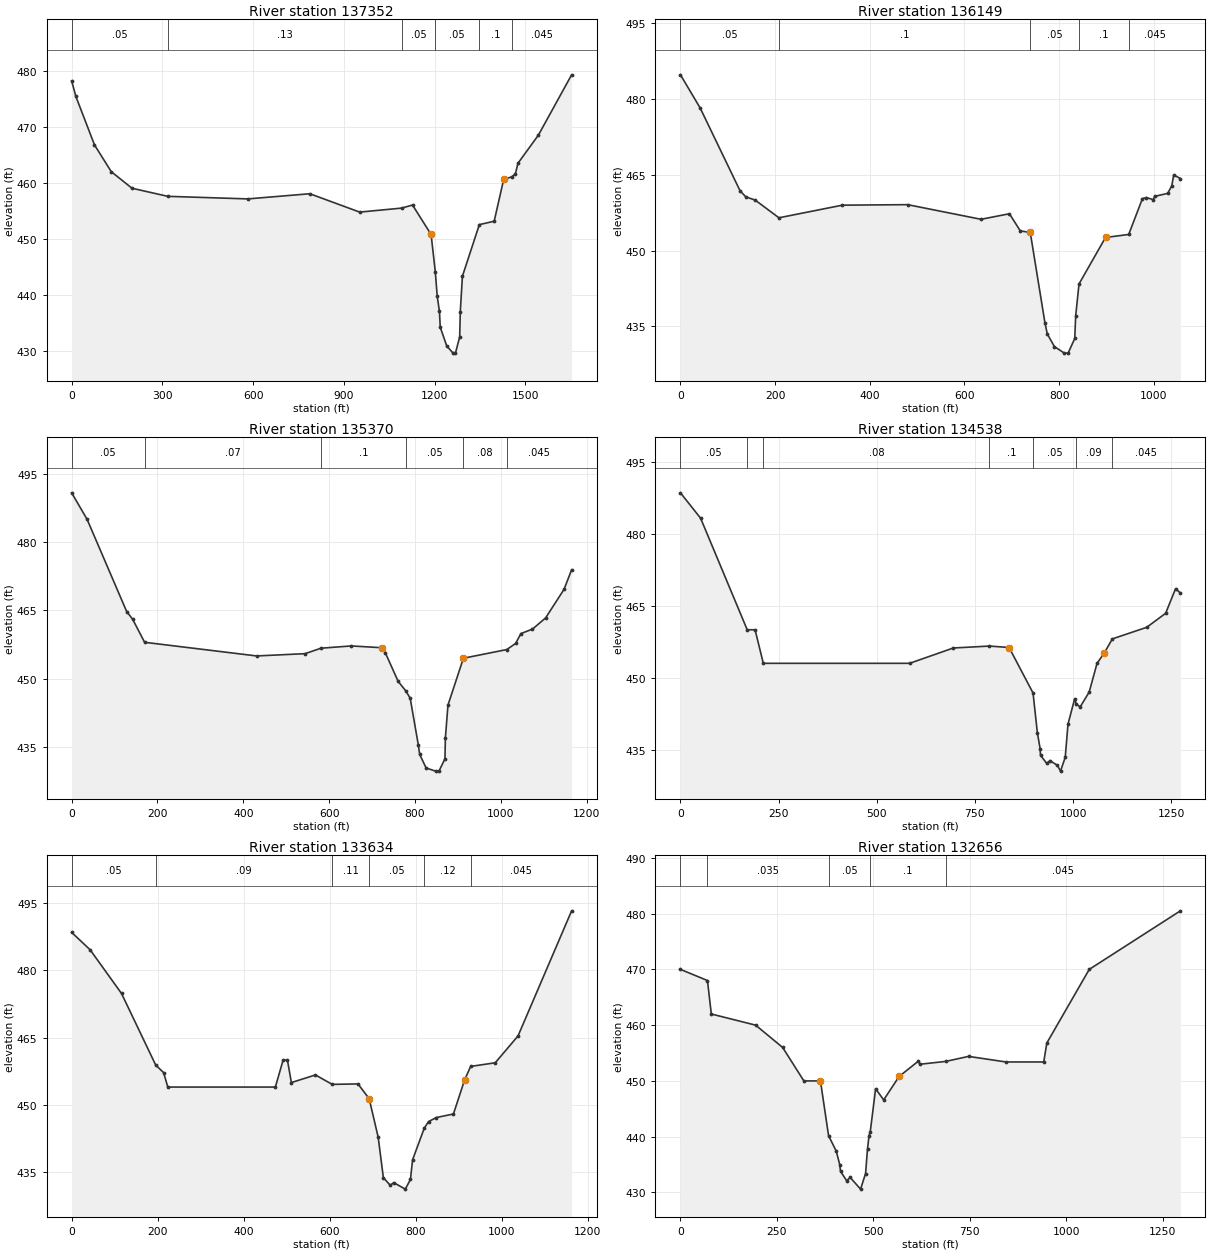
Type RM Length L Ch R = 1 ,137352  ,578.84,1210.07,1220.76
BEGIN DESCRIPTION:
n value updated to reflect CDC 12/16/15 BG
137352
END DESCRIPTION:
XS GIS Cut Line= 4
2441843.886694897060360.939648152440933.140156817059754.84998105
2440762.16904205 7059419.91856432440605.878672217059324.61954232
#Sta/Elev= 30
       0   478.2   13.83  475.45   75.48   466.8  131.02  462.03  199.53  459.08
  317.73  457.64  582.43  457.18  787.41   458.1  952.31  454.83 1090.85  455.54
    1127  456.09 1188.44  450.84 1202.25  444.24 1208.79   439.8 1216.05  437.13
  1218.7  434.32    1240     431    1261   429.7    1269   429.7    1283   432.6
    1285   437.1    1292   443.4    1348   452.6    1397   453.2  1428.4  460.64
 1454.69  461.11 1467.01  461.62 1475.78  463.54 1543.16  468.54 1653.08  479.29
#Mann= 6 ,-1,0
       0     .05       0  317.73     .13       0 1090.85     .05       0
 1202.25     .05       0    1348      .1       0 1454.69    .045       0
Bank Sta=1188.44,1428.4
XS Rating Curve= 0 ,0
Exp/Cntr=0.3,0.1

Type RM Length L Ch R = 1 ,136149  ,793.64,782.45,776.13
BEGIN DESCRIPTION:
n value updated to CDC 12/16/15 BG
136149
END DESCRIPTION:
XS GIS Cut Line= 4
2442274.684061637060306.818037232442242.025990477060209.91829665
2442167.873251637059960.88139315 2441972.28177937059294.87747581
#Sta/Elev= 30
       0  484.81    41.6  478.25  125.84  461.86     138  460.65  158.12  459.99
     208   456.5     342     459     480   459.1     635   456.2     695   457.3
     718   453.9     739   453.6     770   435.7     775   433.5     790     431
     811   429.7     819   429.7     833   432.6     835   437.1     842   443.4
     898   452.6     947   453.2     976   460.3     984   460.5     999   460.1
 1001.54  460.73 1029.33  461.34  1037.9  462.82 1042.11  464.97 1056.23  464.28
#Mann= 5 ,-1,0
       0     .05       0     208      .1       0     739     .05       0
     842      .1       0     947    .045       0
Bank Sta=739,898
XS Rating Curve= 0 ,0
Exp/Cntr=0.3,0.1

Type RM Length L Ch R = 1 ,135370  ,651.11,843.93,857.35
BEGIN DESCRIPTION:
n value updated to CDC. 12/16/15 BG
135370
END DESCRIPTION:
XS GIS Cut Line= 5
2443055.028957647060104.724937482443027.869563137060082.30897181
2442921.18080014 7059703.17587182442720.330151987059103.92903881
2442633.141021897059047.05513681
#Sta/Elev= 30
       0  490.83   36.01     485  128.18  464.76  142.13  463.06     170     458
     431     455     544   455.5     581   456.7     652   457.2     724   456.8
     731   455.7     761   449.4     779   447.3     789   445.7     808   435.4
     811   433.4     826   430.4     848   429.7     856   429.7     870   432.4
     871     437     877   444.2     913   454.5    1014   456.4 1034.67  457.74
 1046.93  459.91 1074.01   460.9 1104.54  463.35 1147.52  469.63 1165.18  473.93
#Mann= 6 ,-1,0
       0     .05       0     170     .07       0     581      .1       0
     779     .05       0     913     .08       0    1014    .045       0
Bank Sta=724,913
XS Rating Curve= 0 ,0
Exp/Cntr=0.3,0.1

Type RM Length L Ch R = 1 ,134538  ,795.75,909.19,923.68
BEGIN DESCRIPTION:
n value updated to CDC. 12/16/15 BG
134538
END DESCRIPTION:
XS GIS Cut Line= 5
2443711.462684147060084.073075892443602.348072987059994.26518464
2443605.817226147059544.289050472443580.04529606 7058962.9631134
2443496.093364227058908.39268447
#Sta/Elev= 30
       0  488.58   51.31  483.28     170     460     190     460     211     453
  583.74     453     695   456.2     787   456.6     837   456.3     898   446.8
     909   438.5     916   435.2     917   433.8     933   432.1     941   432.7
     960   431.7     968   430.5     980   433.4     987   440.3    1004   445.6
    1008   444.5    1018   443.9    1041     447    1061     453    1079   455.1
    1100   458.1 1187.46  460.51  1235.7  463.44 1261.02  468.58 1273.34  467.68
#Mann= 7 ,-1,0
       0     .05       0     170     .03       0     211     .08       0
     787      .1       0     898     .05       0    1008     .09       0
    1100    .045       0
Bank Sta=837,1079
XS Rating Curve= 0 ,0
Exp/Cntr=0.3,0.1

Type RM Length L Ch R = 1 ,133634  ,672.61,959.49,488.22
BEGIN DESCRIPTION:
n values updated to reflect CDC. 12/16/15 BG
133634
---------------------------------------------------------------------
CDC LEW063011-1 Camelot Landfill
Cross-section 133634 - 134538
Located in LOB.
---------------------------------------------------------------------
END DESCRIPTION:
XS GIS Cut Line= 4
2444425.426807397060184.382258472444349.264230067060096.94345698
2444416.557730637059699.39569564 2444505.08380037059061.80641964
#Sta/Elev= 30
       0  488.47   43.02  484.59  115.96  474.86  195.46  458.91  213.96  457.21
  223.59     454  473.79     454  491.79     460  501.92     460     511     455
     567   456.7     606   454.6     666   454.7     692   451.4     713   442.8
     725   433.8     741   432.1     749   432.7     776  431.25     788   433.4
     793   437.8     820   444.8     830   446.3     848   447.2     888     448
     914   455.6     928   458.6  985.21  459.41 1038.25   465.4 1162.87  493.28
#Mann= 6 ,-1,0
       0     .05       0  195.46     .09       0     606     .11       0
     692     .05       0     820     .12       0     928    .045       0
Bank Sta=692,914
XS Rating Curve= 0 ,0
Exp/Cntr=0.3,0.1

Type RM Length L Ch R = 1 ,132656  ,715.87,619.91,251.84
BEGIN DESCRIPTION:
n value updated to CDC. 12/16/15 BG
132656
---------------------------------------------------------------------
CDC CAR110497-1 Coyote Ridge Golf Club
Cross-section 132656
Project located in LOB.
---------------------------------------------------------------------
END DESCRIPTION:
XS GIS Cut Line= 3
2445559.80347563 7059983.76422142445280.977589737059885.25884098
2444683.574913137059082.45828123
#Sta/Elev= 30
       0     470      70     468      80     462     195     460     265     456
     320     450     363     450     384   440.2     404   437.4     413     435
     415   433.8     431   432.1     440   432.7     467   430.6     480   433.4
     485   437.8     489   440.2     492   440.8     506   448.6     527   446.6
     567   450.8     616   453.5     622     453     688   453.5     747   454.4
     844   453.4     942   453.4     950   456.8    1060     470  1296.4   480.5
#Mann= 5 ,-1,0
       0     .05       0      70    .035       0     384     .05       0
     492      .1       0     688    .045       0
Bank Sta=363,567
XS Rating Curve= 0 ,0
Exp/Cntr=0.3,0.1

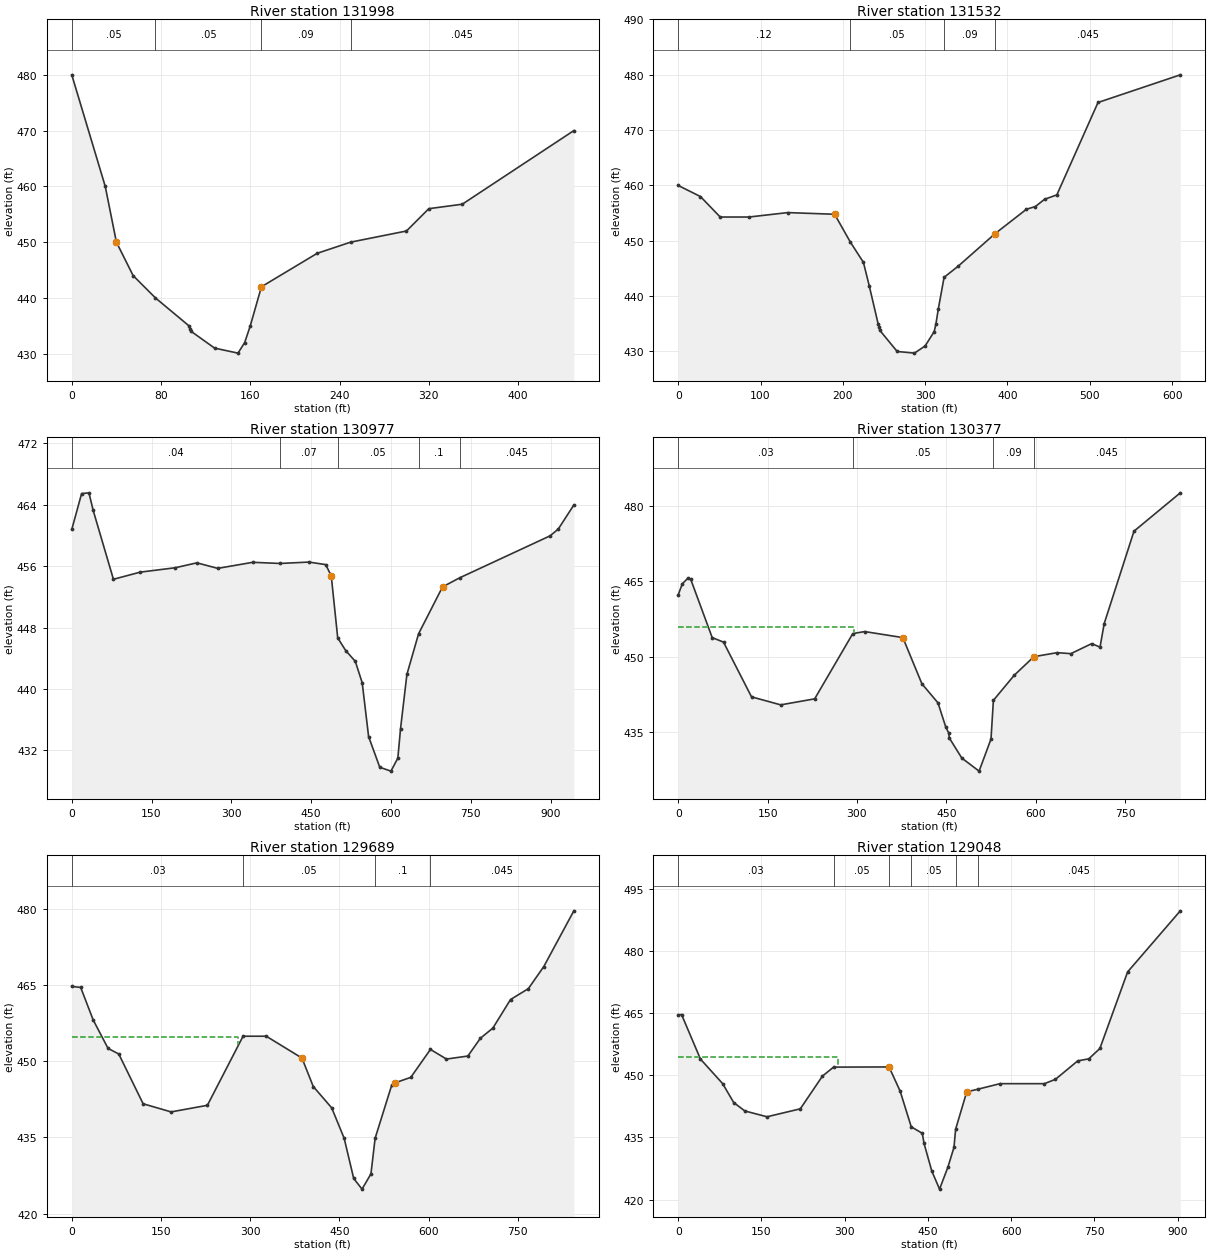
Type RM Length L Ch R = 1 ,131998  ,462.33,470.74,447.47
BEGIN DESCRIPTION:
n value updated to CDC 12/16/15 BG
131998
END DESCRIPTION:
XS GIS Cut Line= 2
2445344.714995067059182.956439812444895.879278567059178.70316748
#Sta/Elev= 19
       0     480      30     460      40     450      55     444      75     440
     105     435     106   434.4     107     434     128     431     149   430.1
     155     432     160     435     170     442     220     448     250     450
     300     452     320     456     350   456.8     450     470
#Mann= 4 ,-1,0
       0     .05       0      75     .05       0     170     .09       0
     250    .045       0
Bank Sta=40,170
XS Rating Curve= 0 ,0
Exp/Cntr=0.3,0.1

Type RM Length L Ch R = 1 ,131532  ,556.24,562.66,415.05
BEGIN DESCRIPTION:
n values updated to CDC. 12/16/15 BG
131532
END DESCRIPTION:
XS GIS Cut Line= 3
2445337.130364557058718.918653982444729.480333137058737.88187064
2444727.431342867058737.94581443
#Sta/Elev= 27
       0     460      27     458      51   454.3      86   454.3     133   455.1
     190   454.8     209   449.8     225   446.1     232   441.9     243   434.9
     244   434.4     245   433.8     266     430     287   429.7     300     431
     311   433.6     313   434.9     316   437.7     323   443.4     340   445.4
     385   451.3     423   455.7     434   456.2     445   457.5     460   458.3
     510     475     610     480
#Mann= 4 ,-1,0
       0     .12       0     209     .05       0     323     .09       0
     385    .045       0
Bank Sta=190,385
XS Rating Curve= 0 ,0
Exp/Cntr=0.3,0.1

Type RM Length L Ch R = 1 ,130977  ,657.58,581.93,640.54
BEGIN DESCRIPTION:
n value updated to CDC model. 12/16/15 BG
130977
END DESCRIPTION:
XS GIS Cut Line= 3
2445817.978484217058238.05937947 2445138.26166787058193.86294556
2444920.738808897058341.10838598
#Sta/Elev= 30
       0  460.78    18.5  465.45    32.3  465.55   40.29  463.25    78.3  454.29
  128.79  455.22  194.44  455.79  235.15  456.43  274.44  455.71  340.29   456.5
  391.35  456.35  445.83  456.53  477.43   456.2  487.81  454.73  499.94  446.65
     515     445     533   443.6     546   440.8     558   433.8     579   429.8
     600   429.3     613     431     618   434.8     630   441.9     652   447.2
     697   453.3  729.22  454.48  899.22  459.95  914.55  460.83  943.83  463.97
#Mann= 5 ,-1,0
       0     .04       0  391.35     .07       0  499.94     .05       0
     652      .1       0  729.22    .045       0
Bank Sta=487.81,697
XS Rating Curve= 0 ,0
Exp/Cntr=0.3,0.1

Type RM Length L Ch R = 1 ,130377  ,755.47,683.07,596.49
BEGIN DESCRIPTION:
n value updated to CDC 12/16/15 BG
130377
END DESCRIPTION:
XS GIS Cut Line= 3
2445663.062783557057477.514312642445051.023325227057698.34556389
2444903.369749147057821.21999006
#Sta/Elev= 30
       0  462.33    6.84  464.51   15.74  465.58      21   465.4      57   453.8
      76   452.9     123     442     172   440.4     229   441.6     293   454.6
     313     455     377   453.8     409   444.6     436   440.8     449     436
     454   434.8     455   433.8     476   429.8     505   427.2     525   433.6
     529   441.3     564   446.3     597     450     636   450.8     659   450.6
     694   452.6     708   451.9     715   456.6     765     475  842.75  482.64
#Mann= 4 ,-1,0
       0     .03       0     293     .05       0     529     .09       0
     597    .045       0
#XS Ineff= 2 , 0
             295   455.9
Permanent Ineff=
       F       F
Bank Sta=377,597
XS Rating Curve= 0 ,0
Exp/Cntr=0.3,0.1

Type RM Length L Ch R = 1 ,129689  ,756.25,634.35,487.97
BEGIN DESCRIPTION:
n value updated to CDC 12/16/15 BG
129689
END DESCRIPTION:
XS GIS Cut Line= 3
2445261.826709397056742.898327812444753.318868137057164.71835031
2444659.972926217057322.62551481
#Sta/Elev= 30
       0   464.7      15   464.5      36   458.1      61   452.5      79   451.4
     120   441.6     167     440     228   441.3     288   454.9     327   454.9
     387   450.6     406     445     437   440.8     458   434.8     474   426.9
     488   424.8     503   427.8     510   434.8     538   445.3     543   445.7
     570   446.8     603   452.3     630   450.4     666     451     687   454.5
     708   456.5  737.64  462.12  767.67  464.26  793.65  468.62  844.13  479.58
#Mann= 4 ,-1,0
       0     .03       0     288     .05       0     510      .1       0
     603    .045       0
#XS Ineff= 2 , 0
             280   454.7
Permanent Ineff=
       F       F
Bank Sta=387,543
XS Rating Curve= 0 ,0
Exp/Cntr=0.3,0.1

Type RM Length L Ch R = 1 ,129048  ,473.26,815.22,776.33
BEGIN DESCRIPTION:
n updated to CDC 12/16/15 BG
129048
END DESCRIPTION:
XS GIS Cut Line= 3
2444459.335204147056333.880445062444319.247229737057010.03099564
2444225.239543727057202.80291981
#Sta/Elev= 30
       0  464.63       6   464.7      40  453.95      80  448.02     100  443.44
     120  441.41     160     440     220  441.92     260  449.84     280     452
     380  452.04     400  446.19     420  437.57     440     436     443   433.6
     457   426.9     471  422.52     486   427.8     497   432.6     500     437
     520  446.02     540  446.66     580     448     660     448     680  449.06
     720   453.5     740     454     760   456.5     810     475  904.98  489.76
#Mann= 6 ,-1,0
       0     .03       0     280     .05       0     380      .1       0
     420     .05       0     500      .1       0     540    .045       0
#XS Ineff= 2 , 0
           288.8  454.42
Permanent Ineff=
       F       F
Bank Sta=380,520
XS Rating Curve= 0 ,0
Exp/Cntr=0.3,0.1

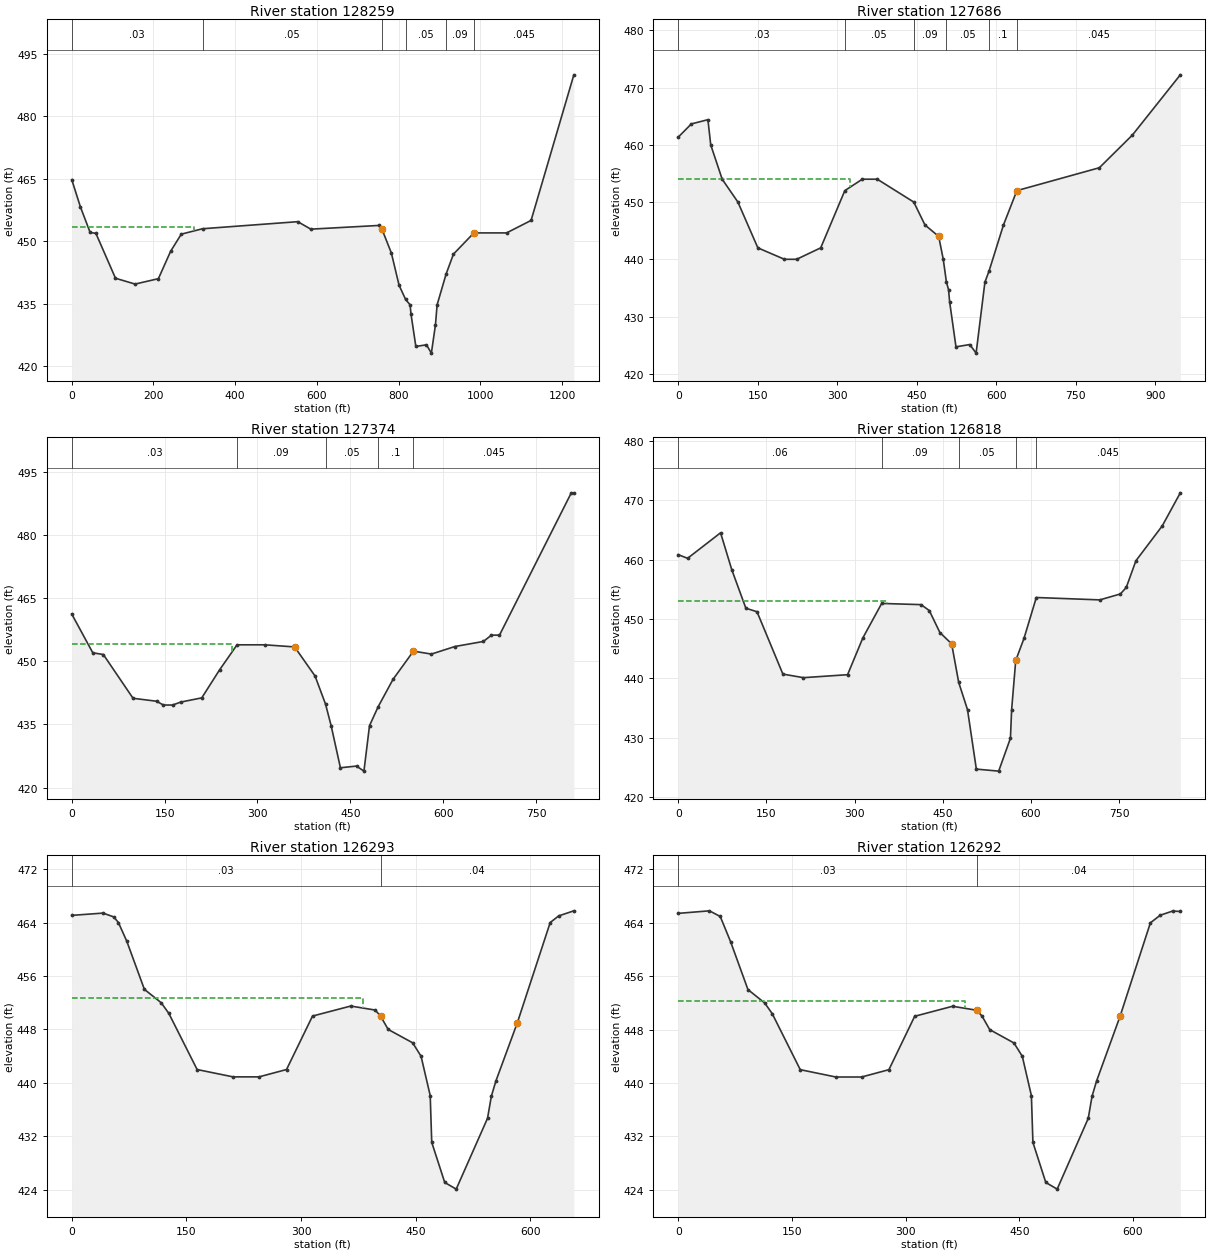
Type RM Length L Ch R = 1 ,128259  ,292.08,586.97,576.06
BEGIN DESCRIPTION:
n valuve updated to reflect CDC. 12/16/15 BG
128259
END DESCRIPTION:
XS GIS Cut Line= 3
2444103.848054227056284.132184982443596.320525977057074.74707356
2443425.287075397057307.87423198
#Sta/Elev= 30
       0   464.8      21   458.3      45   452.1      59   451.9     107   441.1
     155   439.7     212     441     242   447.6     268   451.7     320     453
     553   454.7     585   452.9     753   453.8     759   452.9     782   447.2
     801   439.4     817     436     828   434.7     830   432.6     842   424.7
     868   425.1     880   423.1     890   429.9     894   434.7     916   442.1
     934   446.9     984     452    1064     452    1124     455 1228.64     490
#Mann= 6 ,-1,0
       0     .03       0     320     .05       0     759     .09       0
     817     .05       0     916     .09       0     984    .045       0
#XS Ineff= 2 , 0
             300   453.4
Permanent Ineff=
       F       F
Bank Sta=759,984
XS Rating Curve= 0 ,0
Exp/Cntr=0.3,0.1

Type RM Length L Ch R = 1 ,127686  ,273.63,325.44,381.28
BEGIN DESCRIPTION:
n value updated to reflect CDC. 12/16/15 BG
127686
END DESCRIPTION:
XS GIS Cut Line= 3
2444002.692416647056163.688528222443591.33497164 7056419.4977279
2443201.243232137056668.60845014
#Sta/Elev= 30
       0  461.35   24.76  463.66      56   464.4    61.3     460    82.9     454
   112.6     450   150.2     442   200.4     440   223.4     440   268.8     442
   314.3     452   347.3     454   375.5     454   444.4     450   465.5     446
   491.4     444     500     440     506     436     510   434.7     512   432.6
     524   424.7     550   425.1     562   423.6   578.6     436   586.6     438
   613.6     446   638.9     452   794.5     456   856.9  461.72  947.26  472.24
#Mann= 6 ,-1,0
       0     .03       0   314.3     .05       0   444.4     .09       0
     506     .05       0   586.6      .1       0   638.9    .045       0
#XS Ineff= 2 , 0
             325  454.12
Permanent Ineff=
       F       F
Bank Sta=491.4,638.9
XS Rating Curve= 0 ,0
Exp/Cntr=0.3,0.1

Type RM Length L Ch R = 1 ,127374  ,487.62,573.83,623.73
BEGIN DESCRIPTION:
n value updated to reflect CDC 12/16/15. BG
127374
END DESCRIPTION:
XS GIS Cut Line= 2
2443827.925705817056012.504119312443061.024352487056276.64073014
#Sta/Elev= 30
       0   461.2      34     452      51   451.6      99   441.2     137   440.5
     148   439.6     163   439.6     176   440.3     210   441.3     239     448
     267   453.9     312   453.9     360   453.4     393   446.5     410   439.8
     419   434.7     434   424.7     460   425.1     472   423.9     481   434.7
     495   439.2     519   445.7     552   452.4     581   451.7     619   453.5
     665   454.7     678   456.2     691   456.2     807     490  811.11     490
#Mann= 5 ,-1,0
       0     .03       0     267     .09       0     410     .05       0
     495      .1       0     552    .045       0
#XS Ineff= 2 , 0
          258.83  454.08
Permanent Ineff=
       F       F
Bank Sta=360,552
XS Rating Curve= 0 ,0
Exp/Cntr=0.3,0.1

Type RM Length L Ch R = 1 ,126818  ,367.32,506.38,572.98
BEGIN DESCRIPTION:
n value updated to CDC model
12/16/2015 BG
126818
END DESCRIPTION:
XS GIS Cut Line= 2
2443769.284746977055599.521677552442915.515785227055614.21128073
#Sta/Elev= 30
       0  460.82    15.9   460.2      72   464.5      91   458.3     115   451.8
     134   451.2     178   440.7     213   440.1     288   440.6     314   446.8
     346   452.6     413   452.4     427   451.4     445   447.7     465   445.8
     477   439.3     492   434.7     507   424.7     545  424.36     565   429.9
     567   434.7     574     443     588   446.7     609   453.6     717   453.2
     752   454.2     762   455.3  778.38  459.79  823.17  465.66   853.9  471.23
#Mann= 5 ,-1,0
       0     .06       0     346     .09       0     477     .05       0
     574     .08       0     609    .045       0
#XS Ineff= 2 , 0
          354.47  453.05
Permanent Ineff=
       F       F
Bank Sta=465,574
XS Rating Curve= 0 ,0
Exp/Cntr=0.3,0.1

Type RM Length L Ch R = 1 ,126293  ,7.99,5.23,4.49
BEGIN DESCRIPTION:
n value updated to CDC. 12/16/15 BG
126293
END DESCRIPTION:
XS GIS Cut Line= 2
2443772.135134977055328.235802812443180.528050477055042.62384123
#Sta/Elev= 30
       0  465.07   40.91  465.41   54.91  464.84      61     464      72   461.2
      95     454     117     452     127   450.4     164     442     211   440.9
     245   440.9     281     442     315     450     365   451.5     397   450.9
     404     450     414     448     446     446     457     444     469   438.1
     471   431.1     488   425.1     503   424.1     544   434.7     549     438
     555   440.3     583     449     626     464  637.09  464.99  656.94  465.75
#Mann= 2 ,-1,0
       0     .03       0     404     .04       0
#XS Ineff= 2 , 0
          381.28  452.64
Permanent Ineff=
       F       F
Bank Sta=404,583
XS Rating Curve= 0 ,0
Exp/Cntr=0.5,0.3

Type RM Length L Ch R = 1 ,126292  ,202.64,147.96,128.63
BEGIN DESCRIPTION:
n value updated to CDC 12/16/15 BG.
126292
END DESCRIPTION:
XS GIS Cut Line= 2
2443773.002915387055318.687265472443174.233115557055035.19833115
#Sta/Elev= 30
       0  465.42   41.23   465.8   55.44  464.95      69   461.2      92     454
     114     452     124   450.4     161     442     208   440.9     242   440.9
     278     442     312     450     362   451.5     394   450.9     401     450
     411     448     443     446     454     444     466   438.1     468   431.1
     485   425.1     500   424.1     541   434.7     546     438     552   440.3
     583     450     623     464  635.97  465.14  652.46  465.77  662.49   465.7
#Mann= 2 ,-1,0
       0     .03       0     394     .04       0
#XS Ineff= 2 , 0
          378.06  452.32
Permanent Ineff=
       F       F
Bank Sta=394,583
XS Rating Curve= 0 ,0
Exp/Cntr=0.5,0.3

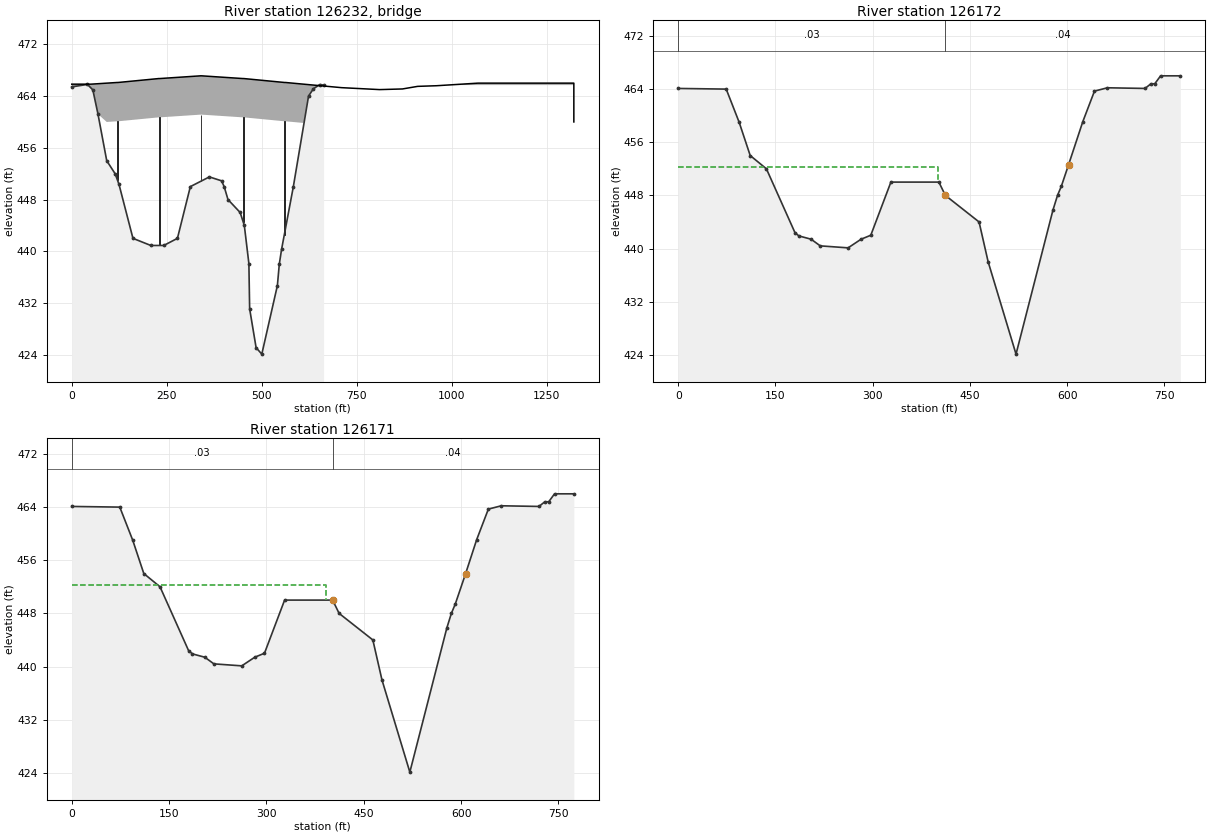
Type RM Length L Ch R = 3 ,126232  ,,,
BEGIN DESCRIPTION:
Hebron Parkway
END DESCRIPTION:
Node Name=Hebron Parkway
Bridge Culvert--1,0,-1,-1, 0
Deck Dist Width WeirC Skew NumUp NumDn MinLoCord MaxHiCord MaxSubmerge Is_Ogee
1,118,2.6,0, 26, 26, , , 0.95, 0, ,,,
       0      50     119   121.5     229   231.5     339   341.5     450   452.5
     560   562.5     610     610     710     810     870     910     960     960
    1069  1071.5    1179  1181.5    1321    1321
  465.84  465.84   466.1   466.1  466.71  466.71  467.13  467.13  466.71  466.71
   466.1   466.1  465.84  465.84   465.3     465   465.1   465.5   465.6   465.6
     466     466     466     466     466     460
          459.84   460.1   460.1  460.71  460.71  461.13  461.13  460.71  460.71
   460.1   460.1  459.84
       0      50     119   121.5     229   231.5     339   341.5     450   452.5
     560   562.5     610     610     710     810     870     910     930     930
    1069  1071.5    1179  1181.5    1263    1263
  465.84  465.84   466.1   466.1  466.71  466.71  467.13  467.13  466.71  466.71
   466.1   466.1  465.84  465.84   465.3     465   465.1   465.5   465.6   465.6
     466     466     466     466     466     460
          459.84   460.1   460.1  460.71  460.71  461.13  461.13  460.71  460.71
   460.1   460.1  459.84
Pier Skew, UpSta & Num, DnSta & Num=  ,120, 2 ,131, 2 , 0 , 0 , 0 ,,
     2.5     2.5
       0   460.5
     2.5     2.5
       0   460.5
Pier Skew, UpSta & Num, DnSta & Num=  ,230, 2 ,241, 2 , 0 , 0 , 0 ,,
     2.5     2.5
       0     461
     2.5     2.5
       0     461
Pier Skew, UpSta & Num, DnSta & Num=  ,340, 2 ,351, 2 , 0 , 0 , 0 ,,
     2.5     2.5
       0   461.5
     2.5     2.5
       0   461.5
Pier Skew, UpSta & Num, DnSta & Num=  ,451, 2 ,462, 2 , 0 , 0 , 0 ,,
     2.5     2.5
       0     461
     2.5     2.5
       0     461
Pier Skew, UpSta & Num, DnSta & Num=  ,559, 2 ,570, 2 , 0 , 0 , 0 ,,
     2.5     2.5
       0   460.5
     2.5     2.5
       0   460.5
BR Coef= 1 , 0 , 0 ,1.05, 0 ,,,0.8,-1,0.5,1,
WSPro=,,,, 1 ,,,, 0 ,,,, 0 ,,,,-1 ,-1 ,-1 , 0 , 0 , 0 , 0 , 0
BC Design=,, 0 ,, 0 ,,,,,,
BC HTab HWMax=465.84
BC Use User HTab Curves=0
BC User HTab FreeFlow(D)= 0

Type RM Length L Ch R = 1 ,126172  ,3.76,4.42,4.62
BEGIN DESCRIPTION:
n value updated to CDC 12/16/15 BG
126172
END DESCRIPTION:
XS GIS Cut Line= 2
2443883.017459147055102.256595982443134.216135227054904.79701714
#Sta/Elev= 30
       0   464.1      74     464      94     459     111     454     136     452
     180   442.4     186   441.9     205   441.4     219   440.4     262   440.1
     282   441.4     297     442     328     450     402     450     412     448
     464     444     478     438     521   424.1     578   445.8     585     448
     591   449.4     602   452.6     624   459.1     642   463.7     662   464.2
     720   464.1     729   464.8     735   464.8     744     466   774.4     466
#Mann= 2 ,-1,0
       0     .03       0     412     .04       0
#XS Ineff= 2 , 0
          399.94  452.33
Permanent Ineff=
       F       F
Bank Sta=412,602
XS Rating Curve= 0 ,0
Exp/Cntr=0.5,0.3

Type RM Length L Ch R = 1 ,126171  ,443.77,539.04,571.87
BEGIN DESCRIPTION:
n value updated to relfect CDC model 12/16/15 BG.
126171
END DESCRIPTION:
XS GIS Cut Line= 2
2443884.03681405 7055099.22674642443136.307994567054900.23337798
#Sta/Elev= 30
       0   464.1      74     464      94     459     111     454     136     452
     180   442.4     186   441.9     205   441.4     219   440.4     262   440.1
     282   441.4     297     442     328     450     402     450     412     448
     464     444     478     438     521   424.1     578   445.8     585     448
     591   449.4     607     454     624   459.1     642   463.7     662   464.2
     720   464.1     729   464.8     735   464.8     744     466  773.75     466
#Mann= 2 ,-1,0
       0     .03       0     402     .04       0
#XS Ineff= 2 , 0
          391.42   452.2
Permanent Ineff=
       F       F
Bank Sta=402,607
XS Rating Curve= 0 ,0
Exp/Cntr=0.3,0.1

River Reach=Elm Fork        ,ef3
Reach XY= 30
2443516.631613697054741.58965819      2443313.02       7052145.4
      2445868.22      7052564.08      2446998.56      7051517.39
      2445261.13      7050837.78      2446747.18      7049390.79
      2443724.81      7047095.96      2446042.79      7046227.23
      2446533.18      7044018.46      2448182.62      7043471.38
      2447028.23      7042565.46      2447998.71      7041928.89
      2447803.01      7039683.01      2446079.96      7039459.22
      2445527.69      7037824.95      2447171.93      7031838.88
      2448540.99      7031061.07      2449273.49       7029018.6
      2448521.48      7026637.83      2447000.53      7025969.64
       2449243.1      7024505.45      2447907.61      7024057.09
      2447661.34       7018966.6      2449579.68      7018119.64
      2451504.25      7014860.54      2451262.61      7011037.61
       2450116.3      7010513.16      2449772.04      7008416.84
       2450705.4      7007292.08      2450520.46       7004955.1

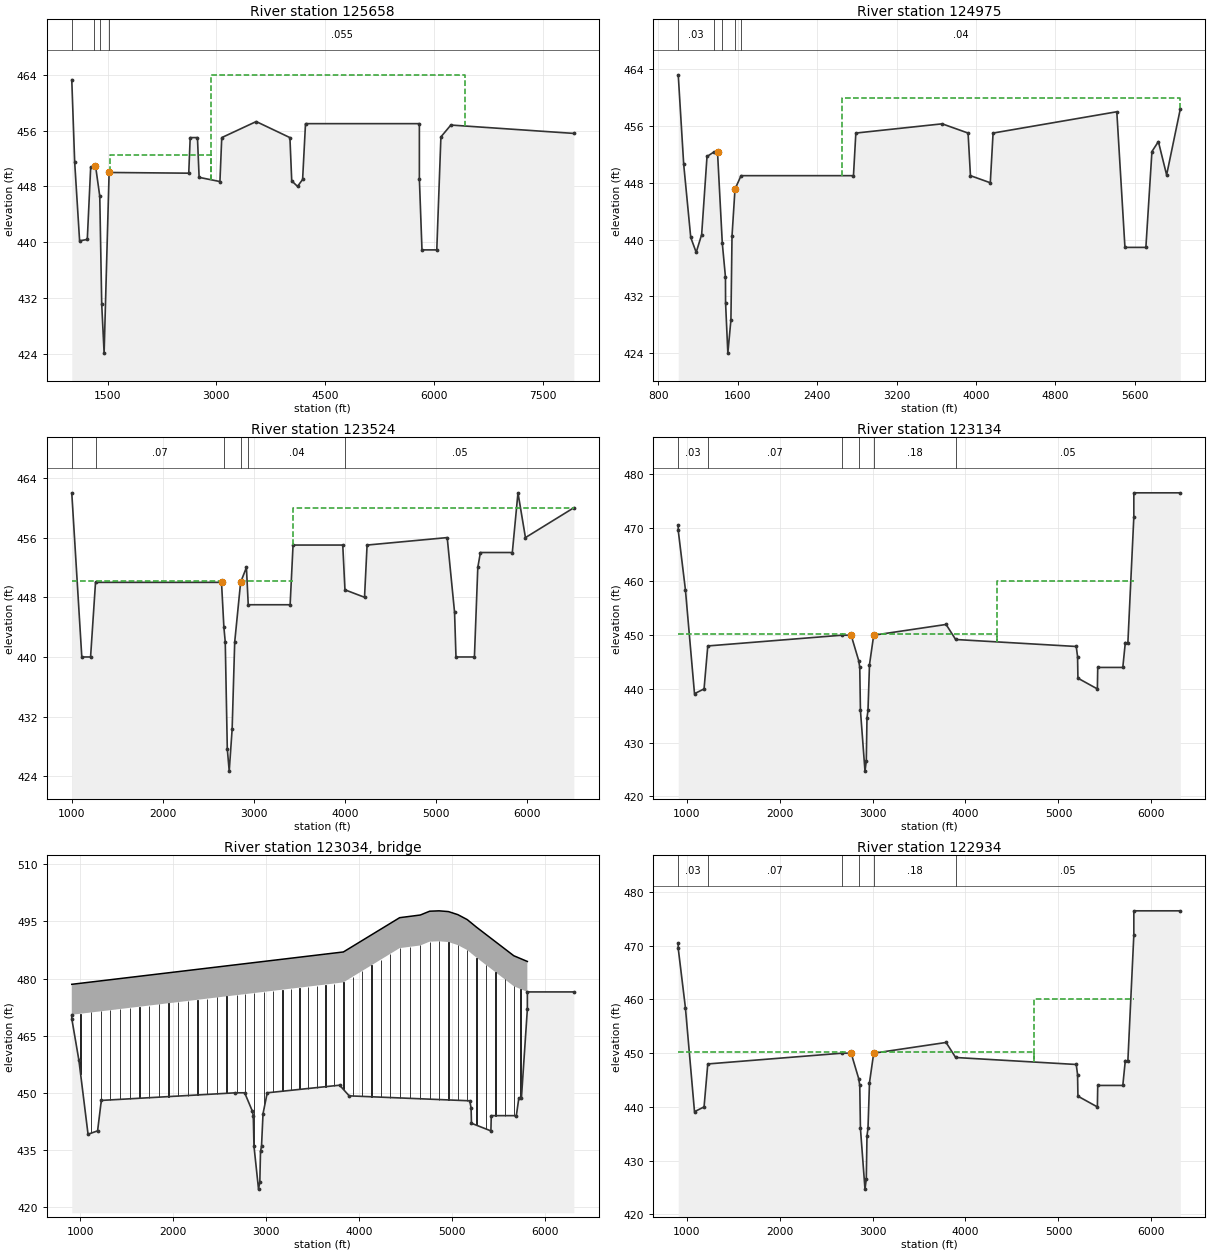
Type RM Length L Ch R = 1 ,125658  ,850,683,550
BEGIN DESCRIPTION:
This cross section corresponds to cross section 125658 of the non-georeferenced CDC model which was the source of this model.
ROB skewed 40 deg   start 1550   2 Proposed fills.
---------------------------------------------------------------------
CDC LEW121406-1 Waste Management Systems Landfill
Cross-section 125658 - 144474.  Includes split flow reach efs2.
This CDC incorporates CDC LEW102202-02
---------------------------------------------------------------------
END DESCRIPTION:
XS GIS Cut Line= 3
2444055.669007667054814.836976132439478.530524167051906.44712363
2438212.495522327051101.98744527
#Sta/Elev= 30
    1007   463.3    1047   451.5    1115   440.2    1221   440.4    1268   450.8
    1311   450.8    1334     451    1393   446.6    1420   431.1    1453   424.1
    1522     450    2620   449.9    2640     455    2740     455    2763   449.3
    3050   448.7    3075     455    3550   457.3    4015     455    4040   448.8
    4120     448    4190     449    4230     457    5800     457    5800   449.1
    5836   438.9    6040   438.9    6097   455.1    6234   456.8    7930   455.6
#Mann= 4 ,-1,0
    1007     .03       0    1311     .07       0    1393     .05       0
    1522    .055       0
#XS Ineff= 3 ,-1
    1007    1334   450.8    1533    2930   452.5    2930    6430     464
Permanent Ineff=
       F       F       F
Bank Sta=1334,1522
XS Rating Curve= 0 ,0
Exp/Cntr=0.3,0.1

Type RM Length L Ch R = 1 ,124975  ,500,1451,570
BEGIN DESCRIPTION:
This cross section corresponds to cross section 124975 of the non-georeferenced CDC model which was the source of this model.
ROB skewed 37 deg.start 1737   1 lake 2 fills.
END DESCRIPTION:
XS GIS Cut Line= 3
2444422.009154267053966.009933642443685.355115747053940.60808155
2440054.028060857051595.18724747
#Sta/Elev= 30
    1000   463.2    1055   450.6    1126   440.3    1181   438.2    1236   440.7
    1290   451.7    1356   452.3    1396   452.3    1444   439.5    1476   434.7
    1477   431.1    1500  424.01    1531   428.7    1542   440.5    1572   447.1
    1633     449    2766     449    2790     455    3660   456.3    3921     455
    3945     449    4145     448    4173     455    5420     458    5502   438.9
    5713   438.9    5774   452.4    5839   453.8    5922   449.1    6060   458.4
#Mann= 5 ,-1,0
    1000     .03       0    1356     .07       0    1444     .05       0
    1572    .055       0    1633     .04       0
#XS Ineff= 3 ,-1
    1000    1396     451    1572    2650   447.1    2650    6060     460
Permanent Ineff=
       F       F       F
Bank Sta=1396,1572
XS Rating Curve= 0 ,0
Exp/Cntr=0.3,0.1

Type RM Length L Ch R = 1 ,123524  ,36,347,534
BEGIN DESCRIPTION:
This cross section corresponds to cross section 123524 of the non-georeferenced CDC model which was the source of this model.
ROB skewed 48 deg.from original start 2970    Only 1 pond & 1 fill shown
END DESCRIPTION:
XS GIS Cut Line= 4
   2444573.66683   7053727.27222 2443308.5848719 7052752.3411011
 2442949.3510104  7052807.722224 2440071.9335368 7050722.6827589
#Sta/Elev= 30
    1000     462 1110.15     440 1206.55     440 1260.84     450 2644.49     450
 2670.44     444  2685.5     442    2708   427.7    2729   424.7    2761   430.3
 2789.39     442 2854.18     450    2918     452    2938     447    3398     447
    3430     455    3976     455    4000     449    4215     448    4243     455
    5123     456 5203.66     446  5219.3     440 5421.82     440 5458.97     452
 5487.67     454    5838     454 5900.17     462 5982.19     456  6513.7     460
#Mann= 6 ,-1,0
    1000     .03       0 1260.84     .07       0 2670.44    .055       0
 2854.18     .07       0    2938     .04       0    4000     .05       0
#XS Ineff= 3 ,-1
    1000 2644.49   450.2 2854.18    3430   450.2    3430  6513.7     460
Permanent Ineff=
       F       F       F
Bank Sta=2644.49,2854.18
XS Rating Curve= 0 ,0
Exp/Cntr=0.3,0.1

Type RM Length L Ch R = 1 ,123134  ,257,257,257
BEGIN DESCRIPTION:
This cross section corresponds to cross section 123134 of the non-georeferenced CDC model which was the source of this model.
Upstream bounding cross section for S.H. 121 Lewisville Bypass Bridge
END DESCRIPTION:
XS GIS Cut Line= 3
   2444641.21169   7053764.75067   2440996.06212   7050494.45151
2440623.890792167050160.55256911
#Sta/Elev= 30
     910   470.5     910   469.5     987   458.5    1085  439.12 1187.82     440
 1227.84     448    2670     450    2770     450 2851.71  445.24 2862.58     444
    2870     436    2919   424.7    2933   426.6 2940.33   434.6 2951.24     436
 2967.41  444.52 3012.64     450 3791.38     452  3894.3   449.2 5191.51   447.9
 5205.77     446 5209.59     442 5418.76     440 5422.75     444 5692.37     444
 5719.38  448.64 5746.79  448.52    5811     472    5811   476.5    6311   476.5
#Mann= 6 ,-1,0
     910     .03       0 1227.84     .07       0    2670     .06       0
 2851.71    .055       0 3012.64     .18       0  3894.3     .05       0
#XS Ineff= 3 ,-1
     910    2770   450.2 3012.64    4340   450.2    4340    5811     460
Permanent Ineff=
       F       F       F
Bank Sta=2770,3012.64
XS Rating Curve= 0 ,0
Exp/Cntr=0.3,0.1

Type RM Length L Ch R = 3 ,123034  ,,,
BEGIN DESCRIPTION:
State Highway 121 Lewisville Bypass
Note:  This bridge was modeled from plans dated Oct. 1995 and supplied by TXDOT Aug. 1999.
END DESCRIPTION:
Node Name=SH 121
Bridge Culvert--1,0,-1,-1, 0
Deck Dist Width WeirC Skew NumUp NumDn MinLoCord MaxHiCord MaxSubmerge Is_Ogee
10,237,2.6,0, 12, 12, , , 0.95, 0, 0,0,,
     910    3832    4437    4659    4760    4861    4962    5063    5164    5264
    5665    5811
   478.5     487     496   496.7   497.7   497.8   497.6   496.8   495.5   493.5
     486   484.5
   470.5     479     488   488.7   489.7   489.8   489.6   488.8   487.5   485.5
     478   476.5
     910    3832    4437    4659    4760    4861    4962    5063    5164    5264
    5665    5811
   478.5     487     496   496.7   497.7   497.8   497.6   496.8   495.5   493.5
     486   484.5
   470.5     479     488   488.7   489.7   489.8   489.6   488.8   487.5   485.5
     478   476.5
Pier Skew, UpSta & Num, DnSta & Num=  ,1005, 2 ,1005, 2 , 0 , 0 , 0 ,,
       3       3
     400     475
       3       3
     400     475
Pier Skew, UpSta & Num, DnSta & Num=  ,1115, 2 ,1115, 2 , 0 , 0 , 0 ,,
       3       3
     400     475
       3       3
     400     475
Pier Skew, UpSta & Num, DnSta & Num=  ,1225, 2 ,1225, 2 , 0 , 0 , 0 ,,
       3       3
     400     475
       3       3
     400     475
Pier Skew, UpSta & Num, DnSta & Num=  ,1325, 2 ,1325, 2 , 0 , 0 , 0 ,,
       3       3
     400     475
       3       3
     400     475
Pier Skew, UpSta & Num, DnSta & Num=  ,1430, 2 ,1430, 2 , 0 , 0 , 0 ,,
       3       3
     400     475
       3       3
     400     475
Pier Skew, UpSta & Num, DnSta & Num=  ,1534, 2 ,1534, 2 , 0 , 0 , 0 ,,
       3       3
     400     475
       3       3
     400     475
Pier Skew, UpSta & Num, DnSta & Num=  ,1638, 2 ,1638, 2 , 0 , 0 , 0 ,,
       3       3
     400     480
       3       3
     400     480
Pier Skew, UpSta & Num, DnSta & Num=  ,1742, 2 ,1742, 2 , 0 , 0 , 0 ,,
       3       3
     400     480
       3       3
     400     480
Pier Skew, UpSta & Num, DnSta & Num=  ,1846, 2 ,1846, 2 , 0 , 0 , 0 ,,
       3       3
     400     480
       3       3
     400     480
Pier Skew, UpSta & Num, DnSta & Num=  ,1950, 2 ,1950, 2 , 0 , 0 , 0 ,,
       3       3
     400     480
       3       3
     400     480
Pier Skew, UpSta & Num, DnSta & Num=  ,2054, 2 ,2054, 2 , 0 , 0 , 0 ,,
       3       3
     400     480
       3       3
     400     480
Pier Skew, UpSta & Num, DnSta & Num=  ,2158, 2 ,2158, 2 , 0 , 0 , 0 ,,
       3       3
     400     480
       3       3
     400     480
Pier Skew, UpSta & Num, DnSta & Num=  ,2262, 2 ,2262, 2 , 0 , 0 , 0 ,,
       3       3
     400     480
       3       3
     400     480
Pier Skew, UpSta & Num, DnSta & Num=  ,2366, 2 ,2366, 2 , 0 , 0 , 0 ,,
       3       3
     400     480
       3       3
     400     480
Pier Skew, UpSta & Num, DnSta & Num=  ,2470, 2 ,2470, 2 , 0 , 0 , 0 ,,
       3       3
     400     480
       3       3
     400     480
Pier Skew, UpSta & Num, DnSta & Num=  ,2574, 2 ,2574, 2 , 0 , 0 , 0 ,,
       3       3
     400     480
       3       3
     400     480
Pier Skew, UpSta & Num, DnSta & Num=  ,2684, 2 ,2684, 2 , 0 , 0 , 0 ,,
       3       3
     400     480
       3       3
     400     480
Pier Skew, UpSta & Num, DnSta & Num=  ,2777, 2 ,2777, 2 , 0 , 0 , 0 ,,
       3       3
     400     480
       3       3
     400     480
Pier Skew, UpSta & Num, DnSta & Num=  ,2870, 2 ,2870, 2 , 0 , 0 , 0 ,,
       3       3
     400     480
       3       3
     400     480
Pier Skew, UpSta & Num, DnSta & Num=  ,2980, 2 ,2980, 2 , 0 , 0 , 0 ,,
       3       3
     400     480
       3       3
     400     480
Pier Skew, UpSta & Num, DnSta & Num=  ,3076, 2 ,3076, 2 , 0 , 0 , 0 ,,
       3       3
     400     480
       3       3
     400     480
Pier Skew, UpSta & Num, DnSta & Num=  ,3176, 2 ,3176, 2 , 0 , 0 , 0 ,,
       3       3
     400     480
       3       3
     400     480
Pier Skew, UpSta & Num, DnSta & Num=  ,3265, 2 ,3265, 2 , 0 , 0 , 0 ,,
       3       3
     400     480
       3       3
     400     480
Pier Skew, UpSta & Num, DnSta & Num=  ,3359, 2 ,3359, 2 , 0 , 0 , 0 ,,
       3       3
     400     480
       3       3
     400     480
Pier Skew, UpSta & Num, DnSta & Num=  ,3452, 2 ,3452, 2 , 0 , 0 , 0 ,,
       3       3
     400     480
       3       3
     400     480
Pier Skew, UpSta & Num, DnSta & Num=  ,3546, 2 ,3546, 2 , 0 , 0 , 0 ,,
       3       3
     400     480
       3       3
     400     480
Pier Skew, UpSta & Num, DnSta & Num=  ,3639, 2 ,3639, 2 , 0 , 0 , 0 ,,
       3       3
     400     480
       3       3
     400     480
Pier Skew, UpSta & Num, DnSta & Num=  ,3732, 2 ,3732, 2 , 0 , 0 , 0 ,,
       3       3
     400     480
       3       3
     400     480
Pier Skew, UpSta & Num, DnSta & Num=  ,3832, 2 ,3832, 2 , 0 , 0 , 0 ,,
       3       3
     400     480
       3       3
     400     480
Pier Skew, UpSta & Num, DnSta & Num=  ,3932, 2 ,3932, 2 , 0 , 0 , 0 ,,
       3       3
     400     485
       3       3
     400     485
Pier Skew, UpSta & Num, DnSta & Num=  ,4033, 2 ,4033, 2 , 0 , 0 , 0 ,,
       3       3
     400     485
       3       3
     400     485
Pier Skew, UpSta & Num, DnSta & Num=  ,4133, 2 ,4133, 2 , 0 , 0 , 0 ,,
       3       3
     400     485
       3       3
     400     485
Pier Skew, UpSta & Num, DnSta & Num=  ,4233, 2 ,4233, 2 , 0 , 0 , 0 ,,
       3       3
     400     490
       3       3
     400     490
Pier Skew, UpSta & Num, DnSta & Num=  ,4334, 2 ,4334, 2 , 0 , 0 , 0 ,,
       3       3
     400     490
       3       3
     400     490
Pier Skew, UpSta & Num, DnSta & Num=  ,4437, 2 ,4437, 2 , 0 , 0 , 0 ,,
       3       3
     400     490
       3       3
     400     490
Pier Skew, UpSta & Num, DnSta & Num=  ,4547, 2 ,4547, 2 , 0 , 0 , 0 ,,
       3       3
     400     490
       3       3
     400     490
Pier Skew, UpSta & Num, DnSta & Num=  ,4659, 2 ,4659, 2 , 0 , 0 , 0 ,,
       3       3
     400     490
       3       3
     400     490
Pier Skew, UpSta & Num, DnSta & Num=  ,4760, 2 ,4760, 2 , 0 , 0 , 0 ,,
       3       3
     400     490
       3       3
     400     490
Pier Skew, UpSta & Num, DnSta & Num=  ,4861, 2 ,4861, 2 , 0 , 0 , 0 ,,
       3       3
     400     490
       3       3
     400     490
Pier Skew, UpSta & Num, DnSta & Num=  ,4962, 2 ,4962, 2 , 0 , 0 , 0 ,,
       3       3
     400     490
       3       3
     400     490
Pier Skew, UpSta & Num, DnSta & Num=  ,5063, 2 ,5063, 2 , 0 , 0 , 0 ,,
       3       3
     400     490
       3       3
     400     490
Pier Skew, UpSta & Num, DnSta & Num=  ,5164, 2 ,5164, 2 , 0 , 0 , 0 ,,
       3       3
     400     490
       3       3
     400     490
Pier Skew, UpSta & Num, DnSta & Num=  ,5265, 2 ,5265, 2 , 0 , 0 , 0 ,,
       3       3
     400     490
       3       3
     400     490
Pier Skew, UpSta & Num, DnSta & Num=  ,5366, 2 ,5366, 2 , 0 , 0 , 0 ,,
       3       3
     400     490
       3       3
     400     490
Pier Skew, UpSta & Num, DnSta & Num=  ,5467, 2 ,5467, 2 , 0 , 0 , 0 ,,
       3       3
     400     488
       3       3
     400     488
Pier Skew, UpSta & Num, DnSta & Num=  ,5568, 2 ,5568, 2 , 0 , 0 , 0 ,,
       3       3
     400     485
       3       3
     400     485
Pier Skew, UpSta & Num, DnSta & Num=  ,5665, 2 ,5665, 2 , 0 , 0 , 0 ,,
       3       3
     400     485
       3       3
     400     485
Pier Skew, UpSta & Num, DnSta & Num=  ,5736, 2 ,5736, 2 , 0 , 0 , 0 ,,
       3       3
     400     484
       3       3
     400     484
BR Coef=-1 , 0 , 0 ,, 0 ,,,0.8,-1,,0,
WSPro=,,,, 1 ,,,, 0 ,,,, 0 ,,,,-1 ,-1 ,-1 , 0 , 0 , 0 , 0 , 0
BC Design=,, 0 ,, 0 ,,,,,,
BC HTab HWMax=476.5
BC Use User HTab Curves=0
BC User HTab FreeFlow(D)= 0

Type RM Length L Ch R = 1 ,122934  ,904,2168,596
BEGIN DESCRIPTION:
This cross section corresponds to cross section 122934 of the non-georeferenced CDC model which was the source of this model.
Downstream bounding cross section for S.H. 121 Lewisville Bypass Bridge
END DESCRIPTION:
XS GIS Cut Line= 3
   2444750.11247   7053563.61165   2441131.48579   7050257.81637
2440762.336105677049920.57979049
#Sta/Elev= 30
     910   470.5     910   469.5     987   458.5    1085  439.12 1187.82     440
 1227.84     448    2670     450    2770     450 2851.71  445.24 2862.58     444
    2870     436    2919   424.7    2933   426.6 2940.33   434.6 2951.24     436
 2967.41  444.52 3012.64     450 3791.38     452  3894.3   449.2 5191.51   447.9
 5205.77     446 5209.59     442 5418.76     440 5422.75     444 5692.37     444
 5719.38  448.64 5746.79  448.52    5811     472    5811   476.5    6311   476.5
#Mann= 6 ,-1,0
     910     .03       0 1227.84     .07       0    2670     .06       0
 2851.71    .055       0 3012.64     .18       0  3894.3     .05       0
#XS Ineff= 3 ,-1
     910    2770   450.2 3012.64    4740   450.2    4740    5811     460
Permanent Ineff=
       F       F       F
Bank Sta=2770,3012.64
XS Rating Curve= 0 ,0
Exp/Cntr=0.3,0.1