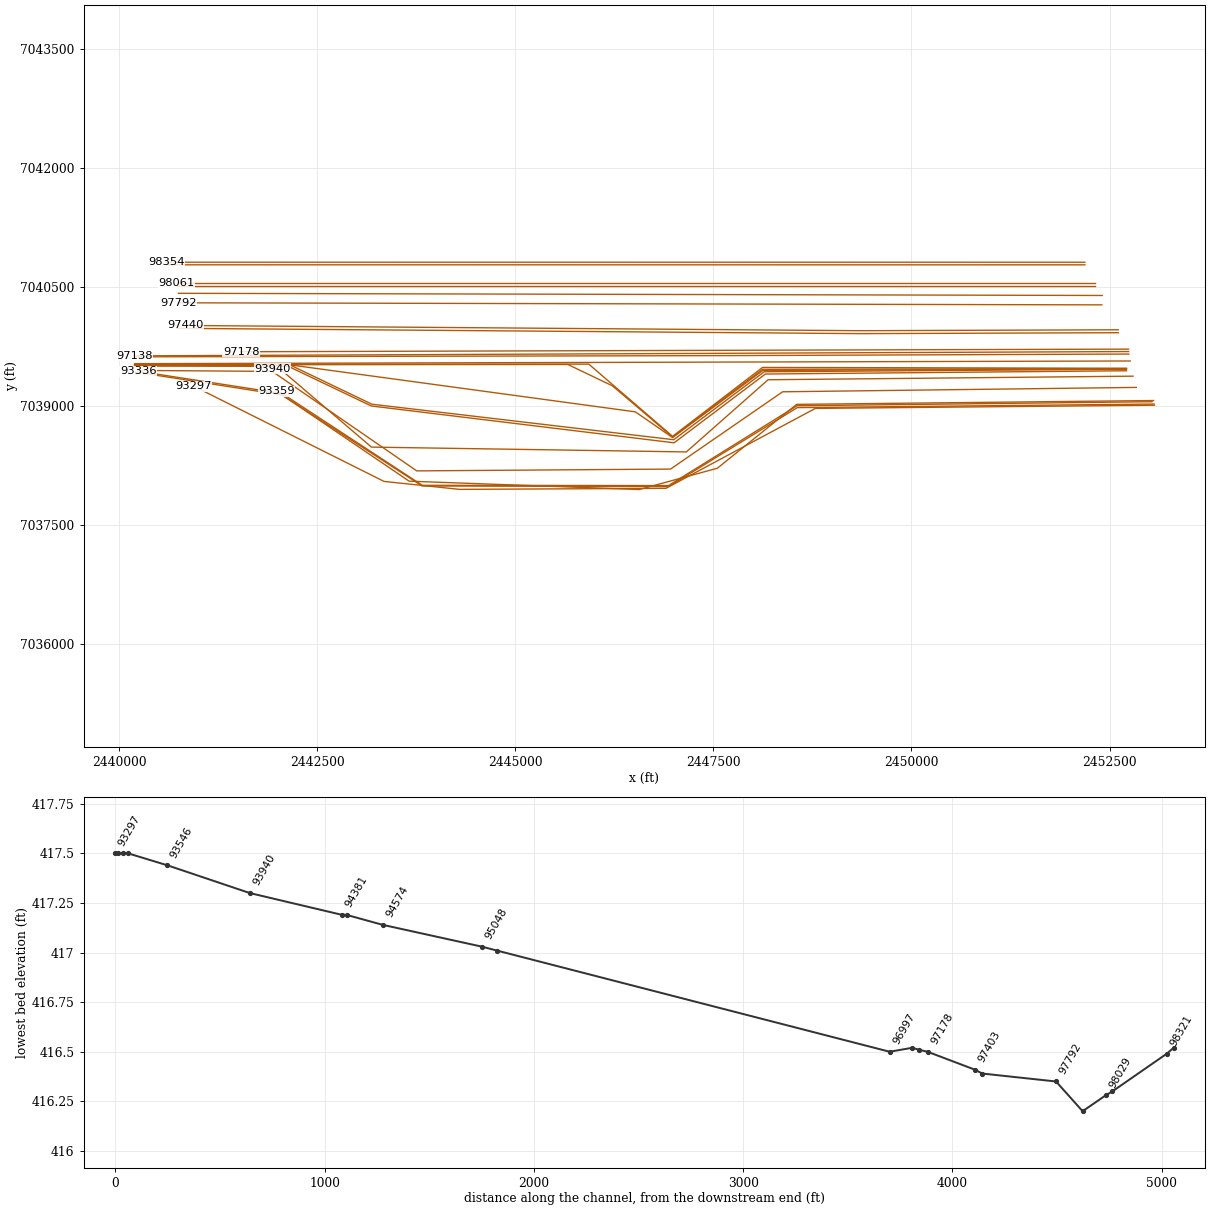
HEC-RAS study CDC_Consolidated_Model.prj: Upper Trinity CDC Consolidated Model

--- CDC_Consolidated_Model.g12 (geometry) --- (continued)

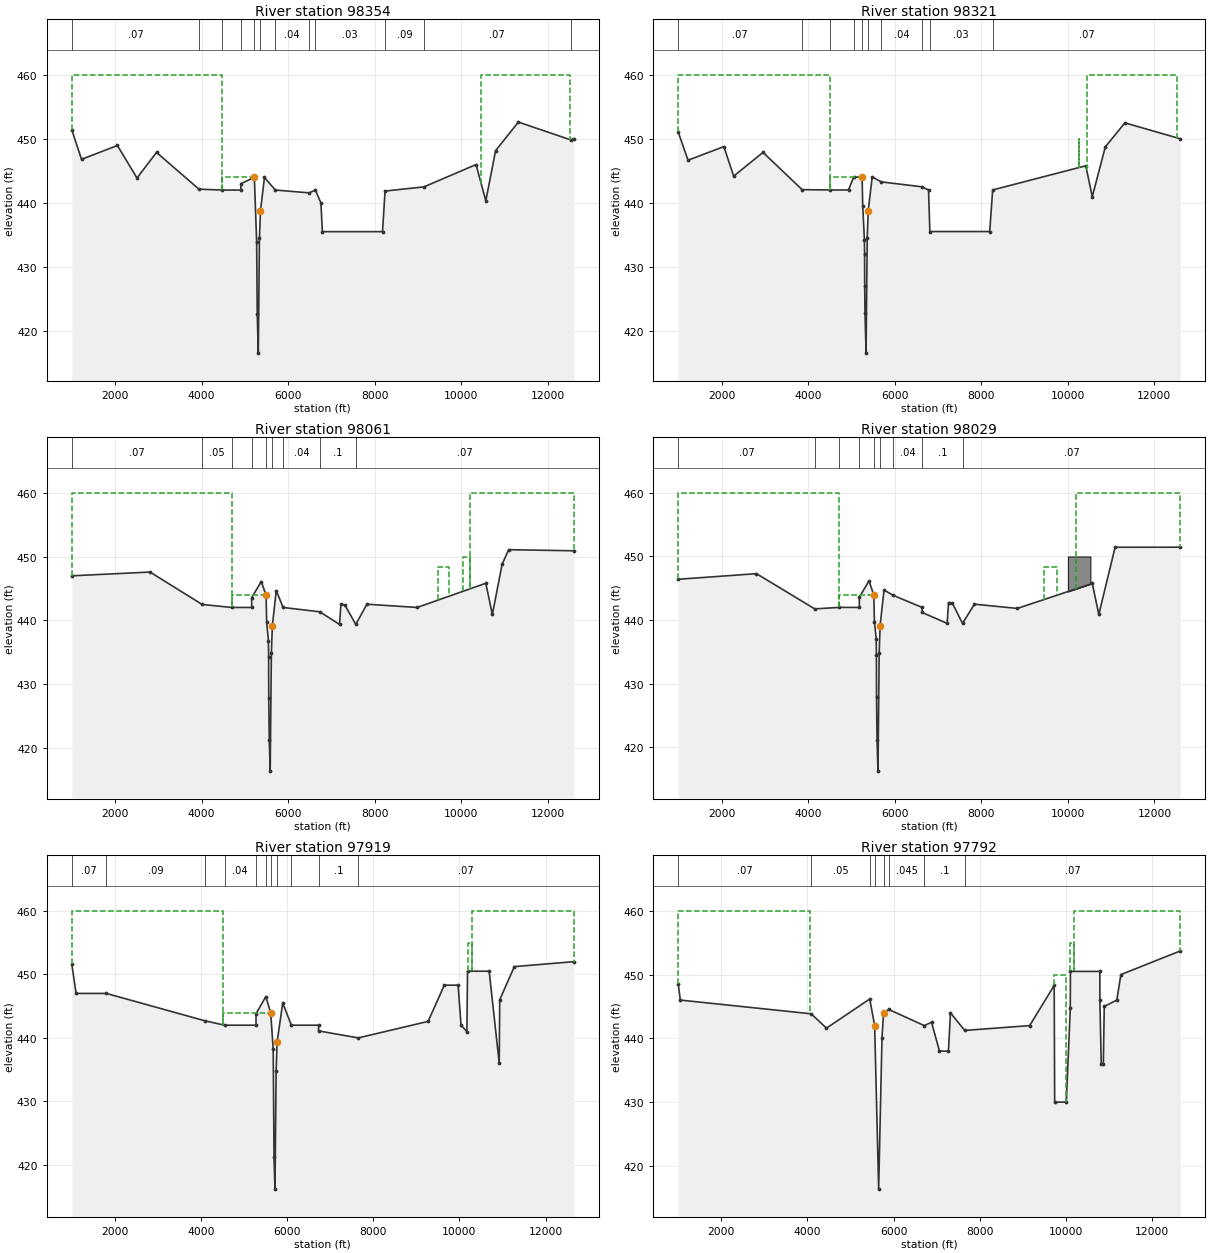
Type RM Length L Ch R = 1 ,98354   ,30,33,30
BEGIN DESCRIPTION:
added
END DESCRIPTION:
XS GIS Cut Line= 2
  2452189.3365647040812.573866682440597.756703567040813.00789447
#Sta/Elev= 30
    1000  451.42 1225.94   446.8  2054.4  448.96 2506.28  443.88 2958.16  447.88
 3937.24  442.14 4473.44     442 4905.67     442 4905.67  442.99 5217.91  443.99
 5270.71   433.9 5284.34  422.62 5308.69  416.52 5335.11  434.44  5358.6  438.71
 5451.01  443.96 5703.33     442 6483.15  441.56 6628.29     442 6754.83     440
 6789.88   435.5 8178.63   435.5 8236.96  441.84 9133.91  442.4910338.93  445.98
10564.87  440.3210790.82  448.1611318.01  452.6212523.04  449.8412598.35  450.03
#Mann= 12 ,-1,0
    1000     .07       0 3937.24     .05       0 4473.44     .04       0
 4905.67      .1       0 5217.91     .05       0  5358.6      .1       0
 5703.33     .04       0 6483.15    .045       0 6628.29     .03       0
 8236.96     .09       0 9133.91     .07       012523.04     .07       0
#XS Ineff= 4 ,-1
    1000 4473.44     460 4473.44 5217.91  443.99 6483.15 8360.52  441.56
   1046012513.47     460
Permanent Ineff=
       F       F       T       F
Bank Sta=5217.91,5358.6
XS Rating Curve= 0 ,0
Exp/Cntr=0.3,0.1

Type RM Length L Ch R = 1 ,98321   ,230,260,230
BEGIN DESCRIPTION:
added
END DESCRIPTION:
XS GIS Cut Line= 2
  2452189.335329 7040779.57386672440597.755467927040780.00789449
#Sta/Elev= 30
    1000  451.05 1225.98  446.65 2054.57  448.78 2280.56  444.16  2958.5  447.87
 3862.42  442.05 4498.56     442 4933.92     442 5054.38  444.03 5248.41  443.98
 5262.39  439.53 5301.53  434.22 5305.26  431.96 5308.06  427.04 5315.24   422.7
 5339.75  416.49 5366.13  434.42 5389.58  438.76 5481.73  444.04 5693.02  443.26
 6624.88   442.5 6783.21     442 6813.58   435.5 8196.83   435.5 8264.47     442
10415.85  445.78 10566.5  440.9610867.81  448.7411319.77  452.4912600.32     450
#Mann= 10 ,-1,0
    1000     .07       0 3862.42     .05       0 4498.56     .04       0
 5054.38      .1       0 5248.41     .05       0 5389.58      .1       0
 5693.02     .04       0 6624.88    .045       0 6813.58     .03       0
 8264.47     .07       0
#XS Ineff= 5 ,-1
    1000 4498.56     460 4498.56 5248.41  443.98 6510.98 8383.09  441.53
 10257.4 10259.4     450   1043512524.39     460
Permanent Ineff=
       F       F       T       T       F
Bank Sta=5248.41,5389.58
XS Rating Curve= 0 ,0
Exp/Cntr=0.3,0.1

Type RM Length L Ch R = 1 ,98061   ,30,32,30
BEGIN DESCRIPTION:
added
END DESCRIPTION:
XS GIS Cut Line= 2
  2452319.9789257040547.382894472440726.228925787040547.38289447
#Sta/Elev= 30
    1000  446.97 2807.72  447.56 4012.86  442.47 4696.47     442 5156.46     442
 5156.46  443.54 5377.98  446.07 5488.74  443.93 5503.38  439.64 5544.37  436.79
 5548.28  434.25  5551.2  427.79 5562.92  421.11 5584.39   416.3 5611.55  434.83
 5633.68  439.11  5723.8  444.66 5882.45     442 6730.25  441.32  7186.9  439.34
 7218.28  442.49 7307.39  442.41 7561.47  439.34 7818.71  442.51 8978.99     442
10565.83   445.810716.48   440.910942.44  448.7811093.08  451.0712599.51   450.9
#Mann= 9 ,-1,0
    1000     .07       0 4012.86     .05       0 4696.47     .04       0
 5156.46      .1       0 5488.74     .05       0 5633.68      .1       0
 5882.45     .04       0 6730.25      .1       0 7561.47     .07       0
#XS Ineff= 6 ,-1
    1000 4696.47     460 4696.47 5488.74  443.93 5633.68    9471  439.11
    9471    9724   448.3 10027.410210.18     45010210.1812610.47     460
Permanent Ineff=
       F       F       T       T       T       F
Bank Sta=5488.74,5633.68
XS Rating Curve= 0 ,0
Exp/Cntr=0.3,0.1

Type RM Length L Ch R = 1 ,98029   ,111,110,105
BEGIN DESCRIPTION:
added
END DESCRIPTION:
XS GIS Cut Line= 2
  2452319.9789257040515.382894472440726.228925787040515.38289447
#Sta/Elev= 30
    1000  446.42 2807.57   447.3 4153.04  441.77 4720.83     442 5183.85     442
 5183.85   443.6 5406.83  446.17 5518.32  443.92 5533.04  439.65 5574.26  437.11
 5578.19  434.53 5581.13  427.88 5592.91  421.13  5614.5  416.28 5641.62  434.82
 5663.73  439.15 5753.59  444.74 5959.62  443.91 6636.07     442 6636.07   441.2
 7212.61  439.49 7243.91  442.77 7332.76  442.68 7567.02  439.49 7842.66  442.51
 8832.82  441.8410565.08  445.7610715.71   440.911092.29  451.45 12598.6  451.46
#Mann= 9 ,-1,0
    1000     .07       0 4153.04     .05       0 4720.83     .04       0
 5183.85      .1       0 5518.32     .05       0 5663.73      .1       0
 5959.62     .04       0 6636.07      .1       0 7567.02     .07       0
#XS Ineff= 5 ,-1
    1000 4720.83     460 4720.83 5518.32  443.92 5663.73    9440  439.15
    9440    9759   448.3   1018012621.06     460
Permanent Ineff=
       F       F       F       T       F
#Block Obstruct= 1 ,-1
   10000   10522     450
Bank Sta=5518.32,5663.73
XS Rating Curve= 0 ,0
Exp/Cntr=0.3,0.1

Type RM Length L Ch R = 1 ,97919   ,117,127,117
BEGIN DESCRIPTION:
97919
Cross-section EF122.  Effective flow limit set at sta 4517 in LOB, at sta 10300 in ROB.  Denton Creek removed from conveyance in ROB.
Channel data from NDM Elm Fork channel survey - cross-section EF#122 surveyed December 1993.
END DESCRIPTION:
XS GIS Cut Line= 2
  2452408.0719227040392.980977392440749.103770437040420.18794397
#Sta/Elev= 30
    1000   451.6    1101     447    1804     447    4087   442.7    4547     442
    5278     442    5278  443.81    5506   446.5    5620   443.9    5677   438.2
    5696   421.2    5718   416.2    5745   434.8    5767   439.3    5898   445.5
    6099     442    6730     442    6730   441.1    7652     440    9274   442.6
 9649.71   448.3 9971.06   448.310037.94     442   10174     441   10189   450.5
 10691.5   450.510925.35     43610936.24     44611276.13  451.2212657.48     452
#Mann= 11 ,-1,0
    1000     .07       0    1804     .09       0    4087     .05       0
    4547     .04       0    5278      .1       0    5506      .1       0
    5620     .05       0    5767      .1       0    6099     .04       0
    6730      .1       0    7652     .07       0
#XS Ineff= 5 ,-1
    1000    4517     460    4517    5620   443.9    5767   10189   439.3
   10189   10300     455   10300   12659     460
Permanent Ineff=
       F       F       F       F       F
Bank Sta=5620,5767
XS Rating Curve= 0 ,0
Exp/Cntr=0.3,0.1

Type RM Length L Ch R = 1 ,97792   ,331,352,317
BEGIN DESCRIPTION:
97792
END DESCRIPTION:
XS GIS Cut Line= 2
  2452402.9867387040274.498779892440744.132571617040300.54044655
#Sta/Elev= 30
    1000   448.5 1048.73     446    4087  443.85 4441.55   441.6    5447  446.17
    5561     442    5654  416.35 5731.01     440    5767     444 5887.97  444.53
    6713     442 6882.22  442.52 7065.58     438 7273.81     438 7321.58     444
    7652  441.24 9160.29     442    9730   448.3 9741.17     430   10011     430
10103.67  444.6910107.49   450.5   10790   450.510790.66     446 10822.2     436
10871.24     43610892.32     44511184.31     44611278.98     45012658.57  453.71
#Mann= 8 ,-1,0
    1000     .07       0    4087     .05       0    5447      .1       0
    5561     .05       0    5767      .1       0 5887.97    .045       0
    6713      .1       0    7652     .07       0
#XS Ineff= 6 ,-1
    1000    4060     460    4060    5561     442    5767    9550     444
    9730   10011     450   10108   10180     455   1018012658.57     460
Permanent Ineff=
       F       F       F       T       F       F
Bank Sta=5561,5767
XS Rating Curve= 0 ,0
Exp/Cntr=0.3,0.1

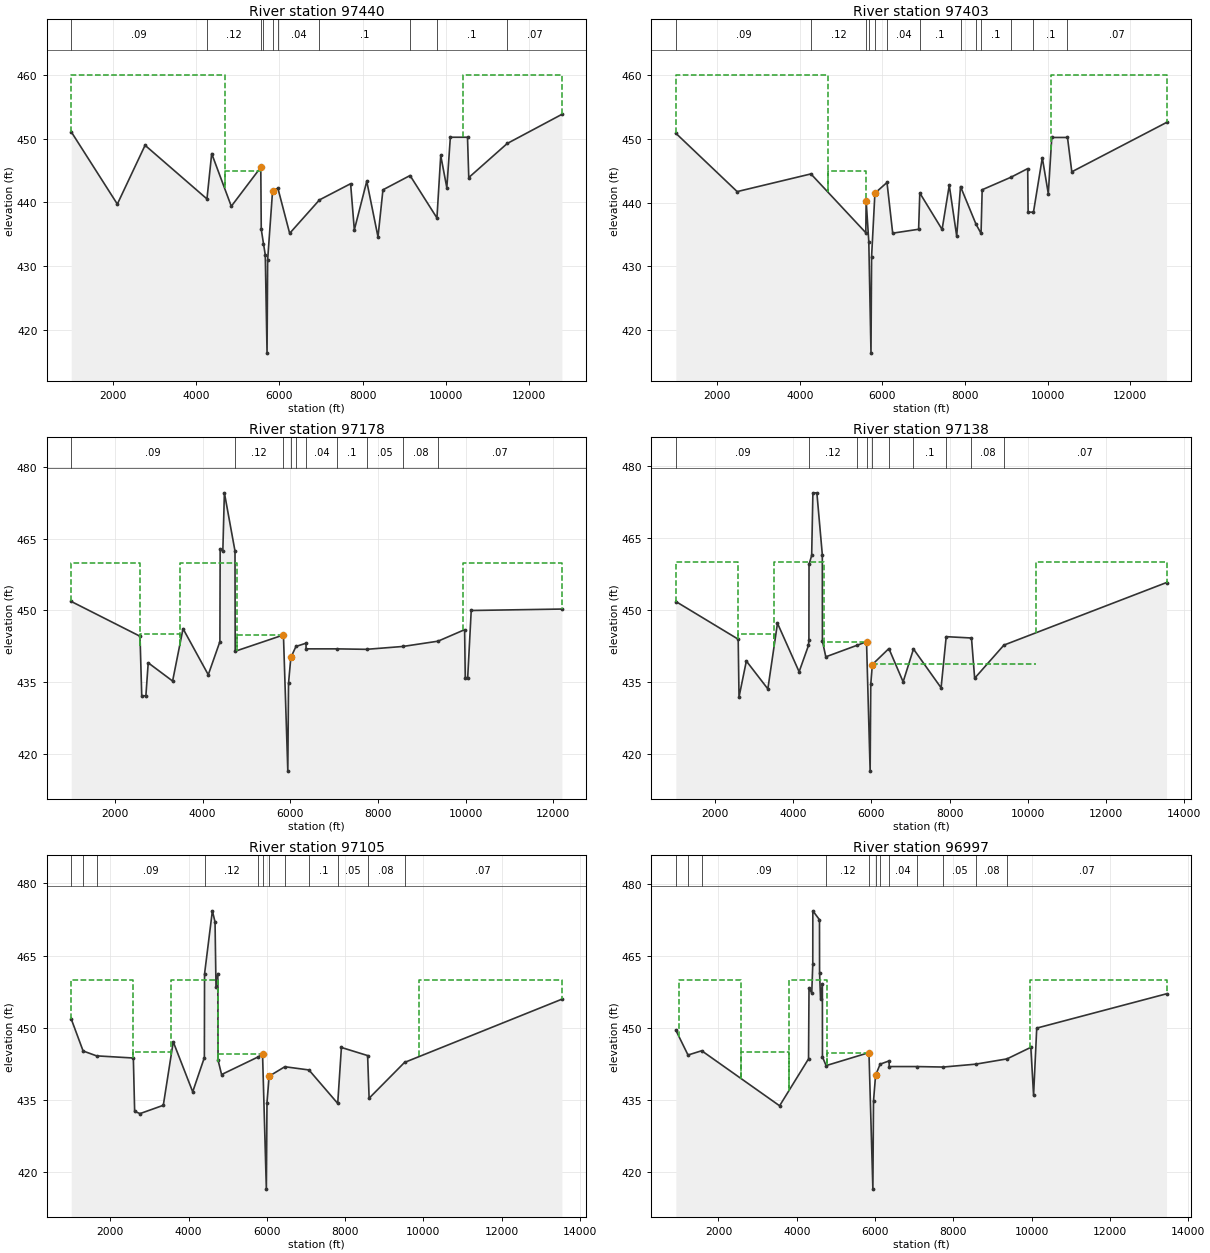
Type RM Length L Ch R = 1 ,97440   ,37,37,36
BEGIN DESCRIPTION:
New cross section. The bottom of the channel has been interpolated between the original xs from plan 1.
END DESCRIPTION:
XS GIS Cut Line= 3
  2452610.3923997039959.937668532449347.299228317039948.36359447
2440831.674228287040014.33581668
#Sta/Elev= 30
    1000  451.08 2108.08  439.74 2774.41  448.96 4260.98  440.55 4374.51  447.66
 4845.69   439.4 5553.79  445.51 5565.11   435.8 5618.13  433.56  5661.4  431.79
 5704.09  416.39 5718.45  430.99 5836.35  441.76 5964.49  442.23 6247.25  435.16
 6962.53   440.4 7711.21  442.94 7800.51   435.7 8099.03  443.32 8369.22   434.6
  8487.7  441.98 9139.16  444.22 9784.93  437.57 9875.85  447.3610022.38  442.31
10106.88  450.2210518.97  450.2210549.31   443.911473.08  449.2412786.92  453.81
#Mann= 10 ,-1,0
    1000     .09       0 4260.98     .12       0 5553.79     .05       0
 5618.13    .045       0 5836.35      .1       0 5964.49     .04       0
 6962.53      .1       0 9139.16     .08       0 9784.93      .1       0
11473.08     .07       0
#XS Ineff= 4 ,-1
    1000  4685.5     460  4685.5 5553.79   444.9 5869.0810421.28   440.2
10421.2812786.92     460
Permanent Ineff=
       F       F       F       F
Bank Sta=5553.79,5836.35
XS Rating Curve= 0 ,0
Exp/Cntr=0.3,0.1

Type RM Length L Ch R = 1 ,97403   ,215,225,230
XS GIS Cut Line= 3
  2452610.5236367039922.937901272449347.221525467039911.36308613
2440731.35364258 7039978.2692757
#Sta/Elev= 30
    1000  450.85 2485.24  441.71 4270.65  444.48 5599.63  435.27 5607.84   440.3
 5672.42  433.85 5725.38  416.41 5739.97  431.53 5820.43  441.46    6113  443.14
 6250.84   435.2 6878.51  435.81 6907.29  441.49 7447.04  435.78 7620.69   442.7
 7800.84  434.73 7893.32   442.5 8267.86  436.61 8390.23  435.16 8417.43     442
 9113.96  443.96 9519.88  445.31 9530.33  438.51 9658.96438.4692 9873.57  447.01
 10018.6  441.38 10102.5  450.19 10483.2  450.1910587.73  444.8112881.87  452.54
#Mann= 13 ,-1,0
    1000     .09       0 4270.65     .12       0 5607.84     .05       0
 5672.42    .045       0 5820.43      .1       0    6113     .04       0
 6907.29      .1       0 7893.32     .05       0 8267.86     .08       0
 8390.23      .1       0 9113.96     .08       0 9658.96      .1       0
 10483.2     .07       0
#XS Ineff= 4 ,-1
    1000    4680     460    4680 5607.84   444.9 5820.43 10084.5   440.2
 10084.512881.87     460
Permanent Ineff=
       F       F       F       F
Bank Sta=5607.84,5820.43
XS Rating Curve= 0 ,0
Exp/Cntr=0.3,0.1

Type RM Length L Ch R = 1 ,97178   ,42,41,52
BEGIN DESCRIPTION:
This cross section corresponds to cross section 97178 of the non-georeferenced CDC model which was the source of this model.
Cross-section EF121.  Effective flow limit set at sta 4780 in LOB, at sta 9950 in ROB.  Denton Creek removed from conveyance in ROB.
Channel data from NDM Elm Fork channel survey.
END DESCRIPTION:
XS GIS Cut Line= 2
  2452739.6519677039715.766124472441539.700942527039682.66481271
#Sta/Elev= 30
    1000  451.89 2570.58  444.63 2609.74  432.22 2704.39  432.21 2757.61  439.09
 3314.35  435.29 3552.33  446.21 4128.39   436.6  4393.8  443.51 4399.84  462.83
 4460.64  462.36 4496.27  474.54 4738.44   462.4    4743   441.5    5844   444.9
    5944   416.5    5960   434.8    6013   440.2    6130   442.5    6360  443.18
    6360     442    7060     442    7740   441.9    8571   442.5    9372   443.6
 9979.15     446 9993.89     43610049.34     43610129.84     450   12200   450.3
#Mann= 10 ,-1,0
    1000     .09       0 4738.44     .12       0    5844     .05       0
    6013    .045       0    6130      .1       0    6360     .04       0
    7060      .1       0    7740     .05       0    8571     .08       0
    9372     .07       0
#XS Ineff= 6 ,-1
    1000    2577     460    2577    3475     445    3475    4780     460
    4780    5844   444.9    6013    9950   440.2    9950   12200     460
Permanent Ineff=
       F       T       F       F       F       F
Bank Sta=5844,6013
XS Rating Curve= 0 ,0
Exp/Cntr=0.3,0.1

Type RM Length L Ch R = 1 ,97138   ,34,32,22
BEGIN DESCRIPTION:
New cross section. The bottom of the channel has been interpolated between the original xs from plan 1.
END DESCRIPTION:
XS GIS Cut Line= 3
  2452741.439853 7039685.03894172440201.63216081  7039630.750773
2440195.560818527039630.85897477
#Sta/Elev= 30
    1000  451.83 2594.03  443.98    2615  431.93 2802.51  439.44 3352.16  433.63
 3598.27   447.3 4151.37   437.2 4390.86  442.68 4401.32  443.86 4404.61  459.54
 4472.32  461.42 4503.48  474.44  4605.1  474.46 4744.53  461.56  4746.7   443.6
 4833.62  440.31 5631.02  442.71 5874.45  443.45 5966.82  416.51 5982.84  434.61
 6023.18  438.71 6446.02  442.03 6810.21   435.1 7074.19  441.94 7780.46  433.86
 7910.97  444.51 8557.43  444.23  8638.4  435.85 9385.77  442.7513543.55  455.78
#Mann= 10 ,-1,0
    1000     .09       0 4404.61     .12       0 5631.02     .05       0
 5874.45    .045       0 6023.18      .1       0 6446.02     .04       0
 7074.19      .1       0 7910.97     .05       0 8557.43     .08       0
 9385.77     .07       0
#XS Ineff= 6 ,-1
    1000 2594.03     460 2594.03  3507.6     445  3507.6    4780     460
    4780 5874.45  443.45 6025.92   10205  438.88   1020513543.55     460
Permanent Ineff=
       F       F       F       F       F       F
Bank Sta=5874.45,6023.18
XS Rating Curve= 0 ,0
Exp/Cntr=0.3,0.1

Type RM Length L Ch R = 1 ,97105   ,109,108,67
BEGIN DESCRIPTION:
New cross section. The bottom of the channel has been interpolated between the original xs from plan 1.
END DESCRIPTION:
XS GIS Cut Line= 3
  2452743.3314917039653.72629702 2447805.96169947039634.28185257
2440197.152253727039618.41684513
#Sta/Elev= 30
    1000  451.88 1304.47  445.21 1647.25   444.2 2588.11  443.75 2621.45  432.66
 2760.16  432.21 3353.57  433.93 3607.71  447.11 4105.04  436.73 4403.17  443.85
 4407.52   461.2 4607.62  474.32 4675.68  472.01 4700.12  458.59 4746.44  461.29
 4752.61  443.32 4842.93  440.32 5785.47  444.01 5889.99  444.56 5987.17  416.52
 6003.19  434.45 6057.43  439.97 6459.09  441.94 7075.57  441.27 7810.71  434.32
  7904.9  445.94 8574.81  444.26 8613.02   435.4 9517.57  442.8313540.31  455.97
#Mann= 12 ,-1,0
    1000     .09       0 1304.47    .045       0 1647.25     .09       0
 4407.52     .12       0 5785.47     .05       0 5889.99    .045       0
 6057.43      .1       0 6459.09     .04       0 7075.57      .1       0
 7810.71     .05       0 8574.81     .08       0 9517.57     .07       0
#XS Ineff= 6 ,-1
  938.59 2588.11     460 2588.11    3557     445    3557 4763.94     460
 4763.94 5891.83  444.65 6057.43    9900  439.97    9900   13553     460
Permanent Ineff=
       F       T       F       F       F       F
Bank Sta=5889.99,6057.43
XS Rating Curve= 0 ,0
Exp/Cntr=0.3,0.1

Type RM Length L Ch R = 1 ,96997   ,1420,1876,91
BEGIN DESCRIPTION:
97178
Cross-section EF121.  Effective flow limit set at sta 4780 in LOB, at sta 9950 in ROB.  Denton Creek removed from conveyance in ROB.
Channel data from NDM Elm Fork channel survey.
END DESCRIPTION:
XS GIS Cut Line= 2
  2452761.367025 7039566.12047652440197.695150087039532.16141979
#Sta/Elev= 30
     910  449.57 1221.18   444.4 1570.68  445.29  3560.9  433.84 4300.15   443.6
 4312.51  458.29 4382.31   457.3 4408.63  463.28 4409.99   474.4 4580.08  472.54
 4582.06  461.56 4606.98  456.11 4653.55  459.24 4655.93  443.99 4749.05   442.2
    5844   444.9    5944   416.5    5960   434.8    6013   440.2    6130   442.5
    6360  443.18    6360     442    7060     442    7740   441.9    8571   442.5
    9372   443.6 9979.15     44610049.34     43610129.84     45013446.46  457.14
#Mann= 12 ,-1,0
     910     .09       0 1221.18    .045       0 1570.68     .09       0
 4749.05     .12       0    5844     .05       0    6013    .045       0
    6130      .1       0    6360     .04       0    7060      .1       0
    7740     .05       0    8571     .08       0    9372     .07       0
#XS Ineff= 6 ,-1
    1000    2577     460  2577.1 3800.37     445 3800.38    4780     460
  4780.1    5844   444.9    6013    9950   440.2    995013446.46     460
Permanent Ineff=
       F       T       F       F       F       F
#Block Obstruct= 1 ,-1
   11796   12231     450
Bank Sta=5844,6013
XS Rating Curve= 0 ,0
Exp/Cntr=0.3,0.1

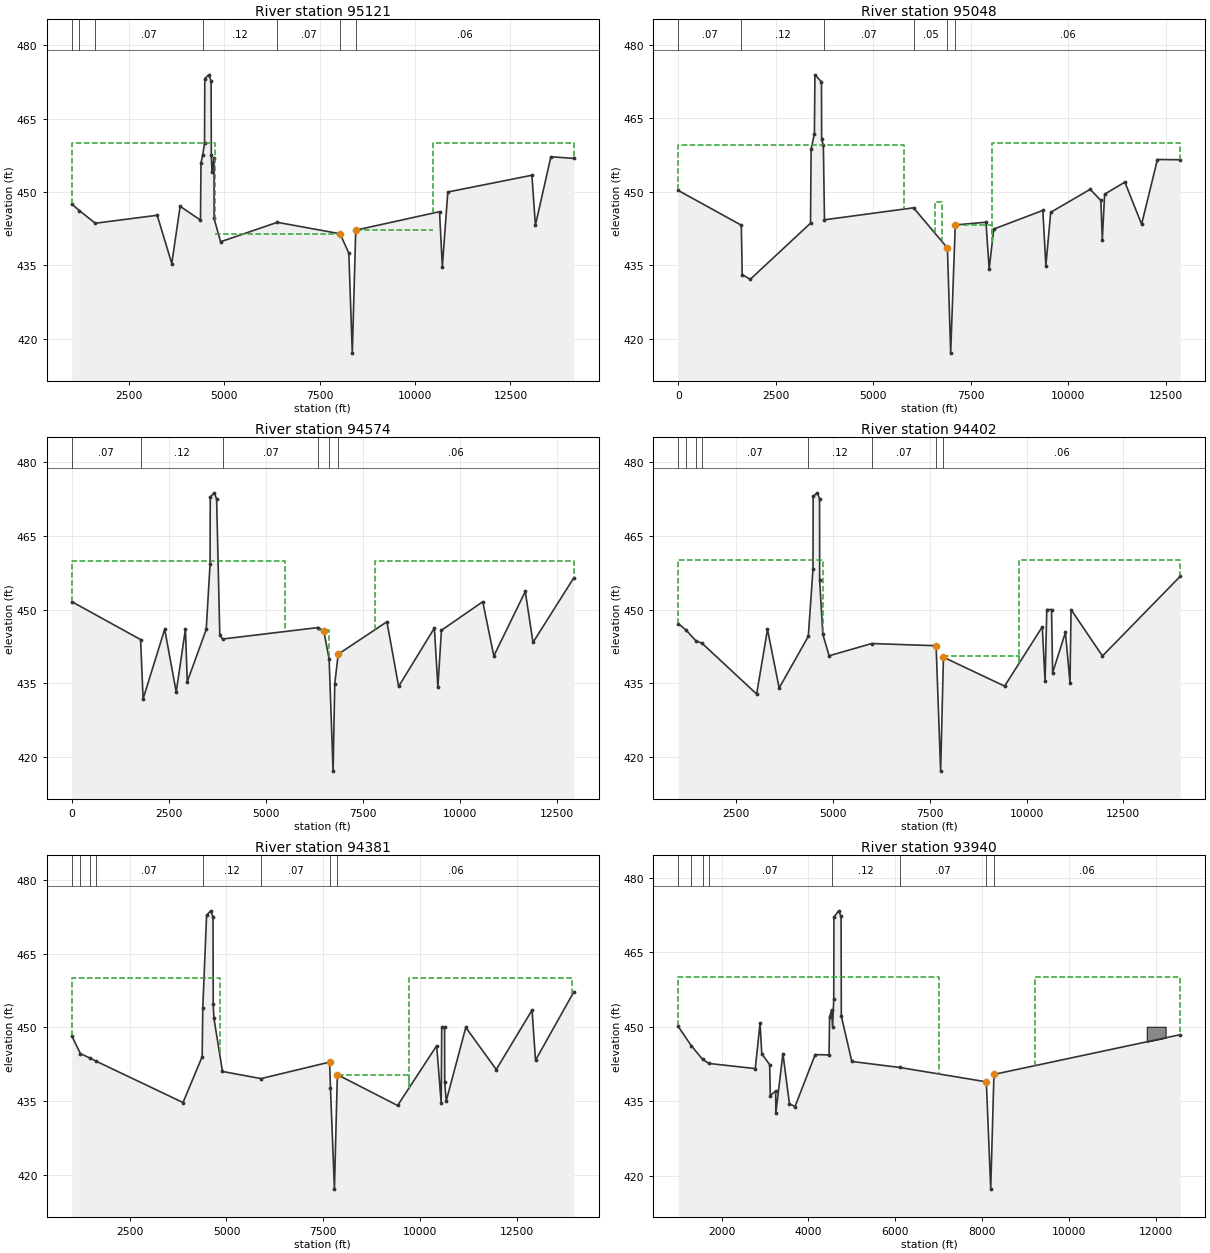
Type RM Length L Ch R = 1 ,95121   ,26,73,193
BEGIN DESCRIPTION:
New cross section. The bottom of the channel has been interpolated between the original xs from plan 1.
END DESCRIPTION:
XS GIS Cut Line= 5
  2452714.2313757039474.308617622448120.481375347039484.72528429
2446985.064708657038614.933617612445927.773041997039526.39195095
2440194.439708627039524.43882596
#Sta/Elev= 30
    1000  447.54 1196.76  446.21 1616.92   443.6 3239.38  445.24 3621.41  435.36
 3840.51  447.07 4374.13  444.24 4387.02  455.97 4433.51  457.61 4480.45  460.09
 4487.02  473.21 4589.79  473.99 4652.24  472.77 4658.07  457.57 4676.24  454.13
 4728.93  457.01 4731.32  444.58 4900.26  439.81  6387.6  443.79 8034.74  441.45
 8262.81  437.46 8353.79  417.01 8444.11  442.1910640.29  445.97 10714.1  434.72
10857.74     45013061.73  453.4313153.72  443.2113559.43  457.2114161.27  456.88
#Mann= 7 ,-1,0
    1000     .07       0 1196.76    .045       0 1616.92     .07       0
 4433.51     .12       0  6387.6     .07       0 8034.74     .05       0
 8444.11     .06       0
#XS Ineff= 4 ,-1
  991.55 4750.42  460.05 4750.42 8034.74   441.5 8444.1110474.37  442.29
10474.3714179.16  460.05
Permanent Ineff=
       F       F       F       F
Bank Sta=8034.74,8444.11
XS Rating Curve= 0 ,0
Exp/Cntr=0.3,0.1

Type RM Length L Ch R = 1 ,95048   ,170,474,440
XS GIS Cut Line= 6
2452712.304684297039470.057216282448121.503744447039460.90076074
 2446985.04709787038606.539467172446226.592918237039252.10207296
2445663.519686257039522.049311222440196.054408467039517.86238991
#Sta/Elev= 30
       0  450.27  1617.6  443.16  1639.6  433.09  1846.4  432.11  3391.7  443.58
  3406.7  458.72  3491.1  461.82  3504.7  473.89  3672.4  472.46  3676.7   460.7
  3720.7  459.47  3749.7  444.27  6032.2  446.72  6901.4  438.52  6984.9  417.03
  7102.4  443.22  7890.1  443.78  7971.5  434.22  8089.5  442.38  9347.5  446.19
  9425.5  434.91  9549.5   445.8 10562.5   450.5 10835.5  448.22 10872.5  440.24
   10932   449.5 11451.1  451.97 11879.7  443.36 12285.5  456.5912872.34  456.54
#Mann= 6 ,-1,0
       0     .07       0  1617.6     .12       0  3749.7     .07       0
  6032.2     .05       0  6901.4     .05       0  7102.4     .06       0
#XS Ineff= 4 ,-1
       0 5795.95 459.634  6573.9 6768.75     448  7102.4  8047.4  443.22
  8047.412872.34     460
Permanent Ineff=
       F       T       F       F
Bank Sta=6901.4,7102.4
XS Rating Curve= 0 ,0
Exp/Cntr=0.3,0.1

Type RM Length L Ch R = 1 ,94574   ,62,172,133
BEGIN DESCRIPTION:
---------------------------------------------------------------------
CDC CAR051319-01 Southwest Wholesale Nursery
Project located at cross-section 93359, 94574, and 95048 located in LOB.
---------------------------------------------------------------------
END DESCRIPTION:
XS GIS Cut Line= 6
2452713.163634037039466.207316652448123.602185667039446.79123253
2446985.396181767038599.485446492446515.072058987038924.22813065
2442183.766531077039513.378741722440194.546002047039513.75553716
#Sta/Elev= 30
       0  451.65  1773.1  443.93  1838.1  431.85  2394.2  446.03  2691.1  433.25
  2928.1  446.05  2976.1  435.36    3464  445.99  3563.1   459.3  3568.1  472.97
  3671.1  473.81  3732.1  472.55  3814.1  444.81  3884.1  444.04  6350.4  446.38
  6492.8  445.66  6630.8     440    6733  417.14  6776.4  434.96  6865.1  440.95
  8120.1  447.56  8421.7  434.38  9342.9  446.28  9432.9  434.23    9524  445.82
 10589.4  451.64 10874.6   440.6 11684.7  453.72 11883.7  443.3512935.94  456.52
#Mann= 6 ,-1,0
       0     .07       0  1773.1     .12       0  3884.1     .07       0
  6350.4     .05       0  6630.8     .05       0  6865.1     .06       0
#XS Ineff= 4 ,-1
       0    5504     460    6350    6620   445.9  6865.1  7810.1  440.95
  7810.112935.94     460
Permanent Ineff=
       F       T       F       F
Bank Sta=6492.8,6865.1
XS Rating Curve= 0 ,0
Exp/Cntr=0.3,0.1

Type RM Length L Ch R = 1 ,94402   ,24,21,19
BEGIN DESCRIPTION:
New cross section. The bottom of the channel has been interpolated between the original xs from plan 1.
END DESCRIPTION:
XS GIS Cut Line= 6
  2452714.1011677039462.190562052448141.560657777039430.11590929
2446999.199546617038572.477020382443190.171768847039020.39368705
 2442169.33843557039509.977020382440195.553713327039511.01868707
#Sta/Elev= 30
    1000  447.16 1197.41  445.87    1463   443.6 1609.67   443.2  3026.2  432.84
 3306.51  445.98 3607.47  434.07 4360.36  444.54 4482.02  458.22 4486.36  472.96
 4593.59   473.7 4651.55   472.5 4654.34  455.91 4736.35  444.97 4898.84  440.61
 5998.97   443.1 7663.18  442.65 7780.57  417.19 7852.88  440.32 9433.02  434.45
10406.81  446.49 10478.7  435.3910523.68     45010646.68     45010674.57  437.17
 11004.9  445.3511123.57  435.1311150.34     45011961.36  440.5713973.59  456.76
#Mann= 8 ,-1,0
    1000     .07       0 1197.41     .09       0    1463    .045       0
 1609.67     .07       0 4360.36     .12       0 5998.97     .07       0
 7663.18     .05       0 7852.88     .06       0
#XS Ineff= 4 ,-1
  871.43 4736.35     460 4736.35 7642.86  442.65 7857.14 9814.29  440.48
 9814.2913985.71  460.05
Permanent Ineff=
       F       F       F       F
Bank Sta=7663.18,7852.88
XS Rating Curve= 0 ,0
Exp/Cntr=0.3,0.1

Type RM Length L Ch R = 1 ,94381   ,313,441,494
BEGIN DESCRIPTION:
New cross section. The bottom of the channel has been interpolated between the original xs from plan 1.
END DESCRIPTION:
XS GIS Cut Line= 6
  2452713.5875677039442.702714832448156.295900827039401.47007596
2447003.952150797038533.414520382443182.77159527 7038998.2582704
2442135.89659524 7039498.25827042440194.924373037039501.73049261
#Sta/Elev= 30
    1000   448.3 1222.68  444.69 1466.12   443.8 1616.55   443.2 3876.45  434.76
 4371.87  444.07 4387.62     454 4485.89  472.76 4592.65  473.66 4652.21  472.43
 4657.61  454.67 4675.78  451.85  4897.1  441.06 5894.01  439.62 7666.49  442.97
 7688.88  437.75  7791.5  417.19 7867.03  440.42 9424.64  434.1610435.66  446.29
10551.95  434.6310565.78     45010639.78     45010642.61  438.9810681.53  435.06
   11188     45011975.54  441.4612901.31  453.52 12990.8  443.34 13981.9  457.22
#Mann= 8 ,-1,0
    1000     .07       0 1222.68     .09       0 1466.12    .045       0
 1616.55     .07       0 4387.62     .12       0 5894.01     .07       0
 7688.88     .05       0 7867.03     .06       0
#XS Ineff= 4 ,-1
  957.14 4828.57  460.05 4828.57 7666.49  442.97 7871.43 9728.57  440.42
 9728.5713942.86  460.05
Permanent Ineff=
       F       F       F       F
Bank Sta=7666.49,7867.03
XS Rating Curve= 0 ,0
Exp/Cntr=0.3,0.1

Type RM Length L Ch R = 1 ,93940   ,500,394,280
BEGIN DESCRIPTION:
93940
--------------------------------------------
CDC CAR062309-1 WTP Pre-Sedimentation Basins
Cross-section 93940 - 105167
--------------------------------------------
Bridge blocked ROB as part of the project for SPF only.
No other impacts to 100-year or SPF conveyance models.
C/s generated from topo file.  Channel data from NDM channel survey.
--------------------------------------------
CDC COP050812-01 River Oaks Assisted Living and Memory Care.  Cross-section 93359 - 93940. In ROB.
--------
END DESCRIPTION:
XS GIS Cut Line= 6
  2452796.7640677039374.54100426 2448190.27787357039329.19398209
2447158.798965337038418.323100422443184.572005677038479.04804459
2442031.742946517039465.824942422441936.719186437039466.55624017
#Sta/Elev= 30
    1000  450.05 1298.67   446.2 1563.17   443.4 1709.27   442.6 2775.04  441.57
 2885.57  450.72 2925.31  444.57  3106.3  442.37 3122.45  436.13 3245.02  437.08
 3249.03   432.6 3412.43   444.6 3561.72  434.51 3690.96  433.92 4155.18  444.38
 4474.93  444.32 4488.12  451.99 4534.08  453.37 4556.86  449.88 4584.03  455.62
 4587.47  472.04    4697  473.33 4752.94   472.2  4757.9  452.15    5000     443
    6100   441.8    8100   438.9    8201   417.3    8275   440.4   12570   448.4
#Mann= 8 ,-1,0
    1000     .07       0 1298.67     .09       0 1563.17    .045       0
 1709.27     .07       0 4534.08     .12       0    6100     .07       0
    8100     .05       0    8275     .06       0
#XS Ineff= 4 ,-1
    1000    7000     460    7000    8100   438.9    8275    9220   440.4
    9220   12570     460
Permanent Ineff=
       F       F       F       F
#Block Obstruct= 1 ,-1
   11796   12231     450
Bank Sta=8100,8275
XS Rating Curve= 0 ,0
Exp/Cntr=0.3,0.1

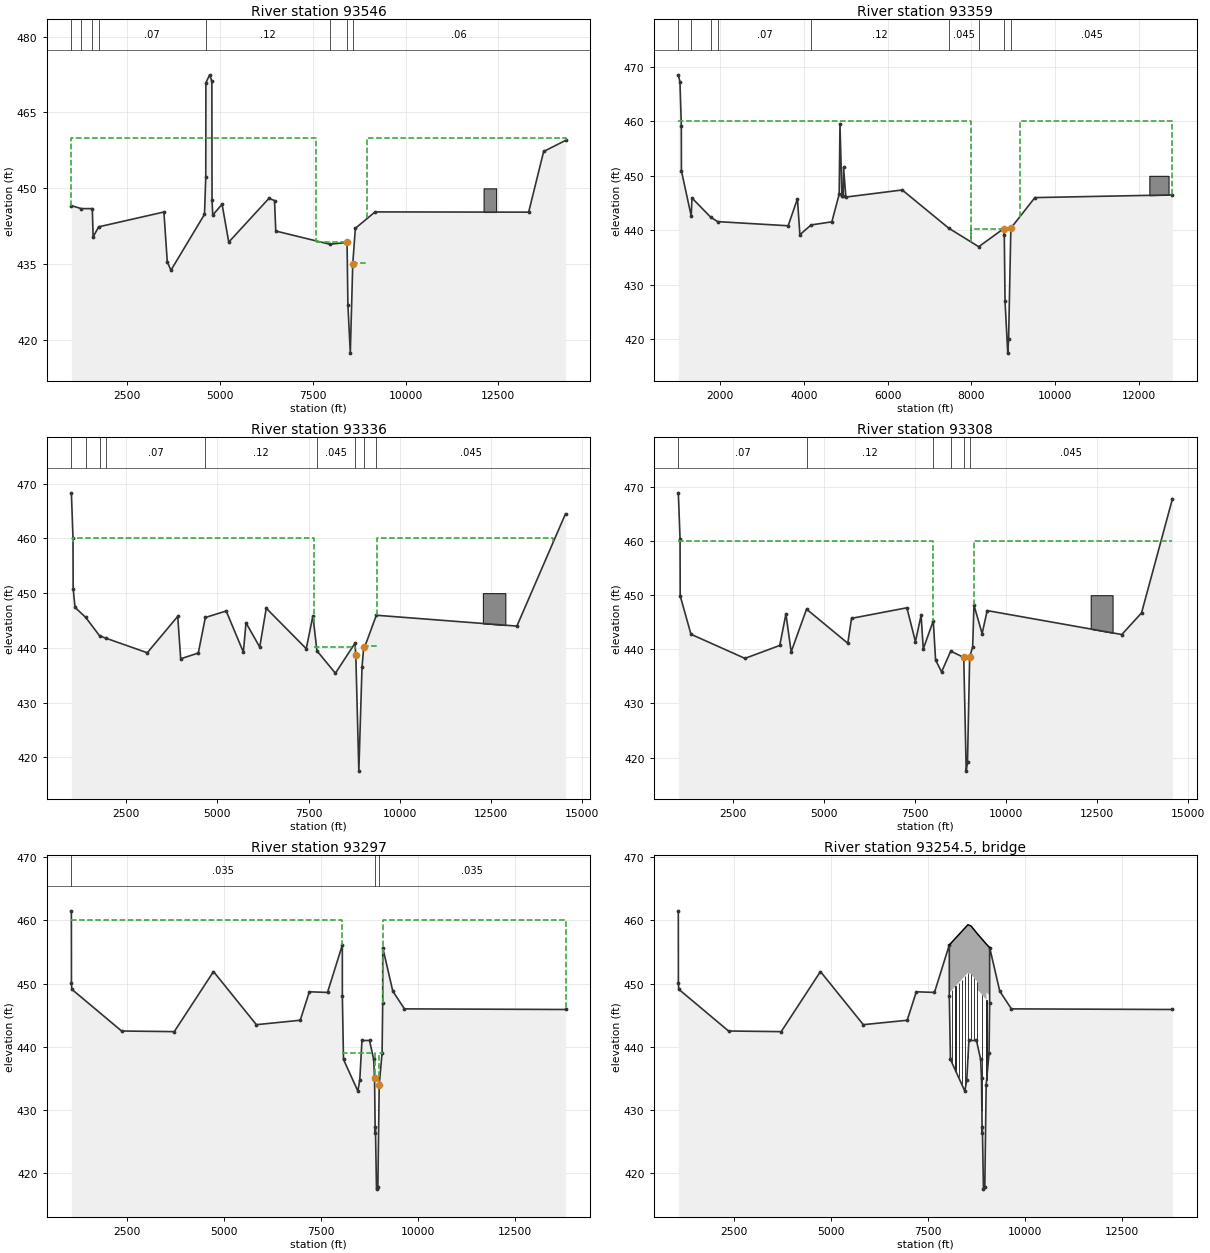
Type RM Length L Ch R = 1 ,93546   ,151,187,181
BEGIN DESCRIPTION:
New cross section. The bottom of the channel has been interpolated between the original xs from plan 1.
END DESCRIPTION:
XS GIS Cut Line= 6
  2452838.0488827039232.511535512448374.232938567039177.39436327
2446959.302383047038201.699918822443756.177383047038179.13047439
2441933.260716387039434.686029942440252.827528577039446.89955637
#Sta/Elev= 30
    1000  446.59 1264.74     446 1563.74     446 1586.14   440.4 1735.71   442.4
 3492.32  445.33 3583.16  435.48 3681.65  433.82 4585.55  444.87 4619.87  452.26
 4622.97  470.87 4724.26  472.44 4784.08   471.2 4788.68  447.65 4807.51  444.72
 5058.99  446.87 5238.94  439.38 6320.33  448.02 6471.76   447.6 6505.33  441.57
 7960.75  438.96 8425.14  439.31 8447.69     427 8512.69  417.44 8578.69   435.1
 8648.37  442.11 9179.75  445.3513316.03   445.313720.15  457.2914308.77  459.48
#Mann= 8 ,-1,0
    1000     .07       0 1264.74     .09       0 1563.74    .045       0
 1735.71     .07       0 4619.87     .12       0 7960.75    .045       0
 8425.14     .05       0 8578.69     .06       0
#XS Ineff= 4 ,-1
  991.55    7600  460.05    7600 8425.14   439.4 8578.69 8969.01   435.2
 8969.0114332.39  459.88
Permanent Ineff=
       F       F       F       F
#Block Obstruct= 1 ,-1
 12101.2 12441.2     450
Bank Sta=8425.14,8578.69
XS Rating Curve= 0 ,0
Exp/Cntr=0.3,0.1

Type RM Length L Ch R = 1 ,93359   ,51,23,23
BEGIN DESCRIPTION:
93359
Cross-section EF120.  62 feet u/s Sandy Lake Road.  Effective flow limit set at sta 8000 in LOB, at sta 9150 in ROB.  Channel data from NDM Elm Fork survey c/s EF#120 surveyed January 1994.
-------------------------------------------------------------
CDC COP050812-01 River Oaks Assisted Living and Memory Care.  Cross-section 93359 - 93940. Located in ROB.
--------------------------------------------
CDC COP 092717-01 Holmes Builders Blackberry Farm Addition. Cross-section 93359 - 98354.  In ROB.
END DESCRIPTION:
XS GIS Cut Line= 6
  2453055.8189957039066.976002592448551.367046347039018.64998375
2447550.309009097038212.535126182446565.057042587037943.82995492
2443660.830895687038049.00986268 2441985.52650357039186.21657775
#Sta/Elev= 30
    1000   468.5 1039.07  467.17 1071.69  459.18 1073.87  450.91 1308.28  442.61
 1325.55  445.93 1775.16   442.4 1938.78   441.6  3622.4  440.84 3844.58  445.78
 3902.42   439.2 4170.33  440.99 4666.03  441.56  4841.1  446.61 4860.26   459.4
 4906.88  446.25    4938  446.29 4945.07  451.57 5001.24   446.1    6347   447.4
    7457   440.4    8174     437    8766   440.3    8784   439.1    8802     427
    8867   417.5    8887     420    8941   440.4    9515     446   12800   446.5
#Mann= 9 ,-1,0
    1000     .07       0 1308.28     .09       0 1775.16    .045       0
 1938.78     .07       0 4170.33     .12       0    7457    .045       0
    8174    .035       0    8766     .05       0    8941    .045       0
#XS Ineff= 4 ,-1
    1000    8000     460    8000    8766   440.3    8941    9150   440.4
    9150   12800     460
Permanent Ineff=
       F       F       F       F
#Block Obstruct= 1 ,-1
   12248   12707     450
Bank Sta=8766,8941
XS Rating Curve= 0 ,0
Exp/Cntr=0.3,0.1

Type RM Length L Ch R = 1 ,93336   ,29,28,20
BEGIN DESCRIPTION:
New cross section. The bottom of the channel has been interpolated between the original xs from plan 1.
END DESCRIPTION:
XS GIS Cut Line= 6
  2453036.4147687039051.906066782448555.05806965 7039001.0485002
2446934.181333547037993.670027972443826.542444657037996.92523633
2442057.879250237039155.779402992440239.756782117039436.51254825
#Sta/Elev= 30
    1000  468.33 1044.56  460.14 1049.07  450.84  1100.3   447.4 1391.73  445.59
 1774.59   442.2 1937.97   441.8 3080.55  439.12 3914.43  445.77 3996.18  438.02
 4478.21  439.07 4671.84  445.56  5242.8  446.75 5713.54  439.23 5785.38  444.59
 6162.25  440.16 6340.45  447.25 7437.52  439.86 7619.38  445.88 7729.59  439.48
  8235.5  435.38 8772.46  440.86 8795.19  438.68 8878.01   417.5 8965.03   436.5
 9012.95  440.14 9031.83  440.06 9357.53  445.9713209.59  443.9914541.94   464.5
#Mann= 9 ,-1,0
    1000     .07       0 1391.73     .09       0 1774.59    .045       0
 1937.97     .07       0 4671.84     .12       0 7729.59    .045       0
 8772.46    .035       0 9031.83     .05       0 9357.53    .045       0
#XS Ineff= 4 ,-1
  1044.9 7644.59  460.02 7644.59 8783.67  440.16 9012.25 9371.43  440.37
 9371.4314204.08  460.02
Permanent Ineff=
       F       F       F       F
#Block Obstruct= 1 ,-1
 12276.1 12894.1     450
Bank Sta=8795.19,9012.95
XS Rating Curve= 0 ,0
Exp/Cntr=0.3,0.1

Type RM Length L Ch R = 1 ,93308   ,11,11,19
BEGIN DESCRIPTION:
New cross section. The bottom of the channel has been interpolated between the original xs from plan 1-
---------------------------------------------------------------------
CDC CAR061818-01 Sandy Lake Ardinger Tract
Project located in LOB.
Cross-sections 93308 - 97138
---------------------------------------------------------------------
END DESCRIPTION:
XS GIS Cut Line= 6
  2453062.7982317039022.547342812448558.446379847038977.31586131
2446935.529713187037980.78808355 2443823.80517627037988.63530576
2442052.867676177039137.611000212440226.518934857039423.92574272
#Sta/Elev= 30
    1000  468.92 1047.65  460.38 1051.75  449.89 1346.98  442.79 2829.74  438.33
 3785.06  440.72 3954.34  446.54 4098.62  439.53 4520.57  447.43 5652.72  441.13
 5756.09  445.73 7275.89  447.68 7510.43  441.42 7666.39  446.29 7725.43  440.08
 8000.69  445.27 8063.63  438.03 8227.98  435.83 8479.47  439.67 8837.23  438.51
 8904.82   417.5 8940.18  419.17 8999.92  438.62 9081.53  440.43 9117.45  448.18
 9341.49   442.9 9481.05  447.1613177.26  442.7413718.71  446.7314567.81  467.83
#Mann= 6 ,-1,0
    1000     .07       0 4520.57     .12       0 8000.69    .045       0
 8479.47    .035       0 8837.23     .05       0 8999.92    .045       0
#XS Ineff= 4 ,-1
    1000 8000.69     460 8000.69 8837.23  438.51 8837.23 9117.45  438.62
 9117.4514549.01     460
Permanent Ineff=
       F       F       F       F
#Block Obstruct= 1 ,-1
12321.9612923.96     450
Bank Sta=8837.23,8999.92
XS Rating Curve= 0 ,0
Exp/Cntr=0.3,0.1

Type RM Length L Ch R = 1 ,93297   ,113,113,113
BEGIN DESCRIPTION:
This cross section corresponds to cross section 93297 of the non-georeferenced CDC model which was the source of this model.
Upstream bounding cross-section for Sandy Lake Road bridge
END DESCRIPTION:
XS GIS Cut Line= 6
2453066.561747017039007.696674472448786.985660497038967.59209588
2446901.668565017037959.034729792444298.008746097037945.72931021
2443344.115968857038045.839674292440940.747899967039248.27824411
#Sta/Elev= 30
    1068   461.5    1070   450.1    1079   449.1    2362   442.5    3719   442.4
    4730   451.9    5835   443.5    6965   444.2    7200   448.7    7668   448.6
    8050   456.1    8050     448    8080     438    8450     433    8500   434.8
    8555     441    8750     441    8858     438    8880     435    8897   426.3
    8902   427.4    8930   417.5    8965   417.8    9000     434    9074     439
    9090     447    9090   455.7    9350   448.8    9650     446   13800   445.9
#Mann= 3 ,0,0
    1068    .035       0    8880     .03       0    9000    .035       0
#XS Ineff= 4 ,-1
    1068    8050     460    8050    8880     439    9000    9090     439
    9090   13800     460
Permanent Ineff=
       F       F       F       F
Bank Sta=8880,9000
XS Rating Curve= 0 ,0
Exp/Cntr=0.3,0.1

Type RM Length L Ch R = 3 ,93254.5 ,,,
BEGIN DESCRIPTION:
Sandy Lake Road
Note:  Bridge and roadway modeled from plans dated Dec. 1996 and stamped Dec. 1997.
END DESCRIPTION:
Node Name=Sandy Lake Road
Bridge Culvert--1,0,-1,-1, 0
Deck Dist Width WeirC Skew NumUp NumDn MinLoCord MaxHiCord MaxSubmerge Is_Ogee
10,83,2.6,0, 8, 8, , , 0.95, 0, ,,,
    8050    8530    8610    8770    8770    9010    9010    9090
   456.1   459.3   459.1   457.9   457.9   456.2   456.2   455.7
   448.5   451.7   451.5   450.3   449.1   447.4   448.6   448.1
    8050    8530    8610    8770    8770    9010    9010    9090
   456.1   459.3   459.1   457.9   457.9   456.2   456.2   455.7
   448.5   451.7   451.5   450.3   449.1   447.4   448.6   448.1
Pier Skew, UpSta & Num, DnSta & Num=  ,8130, 2 ,8130, 2 , 0 , 0 , 0 ,,
     2.5     2.5
     425     452
     2.5     2.5
     425     452
Pier Skew, UpSta & Num, DnSta & Num=  ,8210, 2 ,8210, 2 , 0 , 0 , 0 ,,
     2.5     2.5
     425     452
     2.5     2.5
     425     452
Pier Skew, UpSta & Num, DnSta & Num=  ,8290, 2 ,8290, 2 , 0 , 0 , 0 ,,
     2.5     2.5
     425     452
     2.5     2.5
     425     452
Pier Skew, UpSta & Num, DnSta & Num=  ,8370, 2 ,8370, 2 , 0 , 0 , 0 ,,
     2.5     2.5
     425     452
     2.5     2.5
     425     452
Pier Skew, UpSta & Num, DnSta & Num=  ,8450, 2 ,8450, 2 , 0 , 0 , 0 ,,
     2.5     2.5
     425     452
     2.5     2.5
     425     452
Pier Skew, UpSta & Num, DnSta & Num=  ,8530, 2 ,8530, 2 , 0 , 0 , 0 ,,
     2.5     2.5
     425     453
     2.5     2.5
     425     453
Pier Skew, UpSta & Num, DnSta & Num=  ,8610, 2 ,8610, 2 , 0 , 0 , 0 ,,
     2.5     2.5
     425     453
     2.5     2.5
     425     453
Pier Skew, UpSta & Num, DnSta & Num=  ,8690, 2 ,8690, 2 , 0 , 0 , 0 ,,
     2.5     2.5
     425     452
     2.5     2.5
     425     452
Pier Skew, UpSta & Num, DnSta & Num=  ,8770, 2 ,8770, 2 , 0 , 0 , 0 ,,
       3       3
     425     452
       3       3
     425     452
Pier Skew, UpSta & Num, DnSta & Num=  ,8890, 2 ,8890, 2 , 0 , 0 , 0 ,,
       3       3
     425     452
       3       3
     425     452
Pier Skew, UpSta & Num, DnSta & Num=  ,9010, 2 ,9010, 2 , 0 , 0 , 0 ,,
       3       3
     425     452
       3       3
     425     452
BR Coef= 1 , 0 , 0 ,1.05, 0 ,,,0.8,-1,0.5,1,
WSPro=,,,, 1 ,,,, 0 ,,,, 0 ,,,,-1 ,-1 ,-1 , 0 , 0 , 0 , 0 , 0
BC Design=,, 0 ,, 0 ,,,,,,
BC Use User HTab Curves=0
BC User HTab FreeFlow(D)= 0