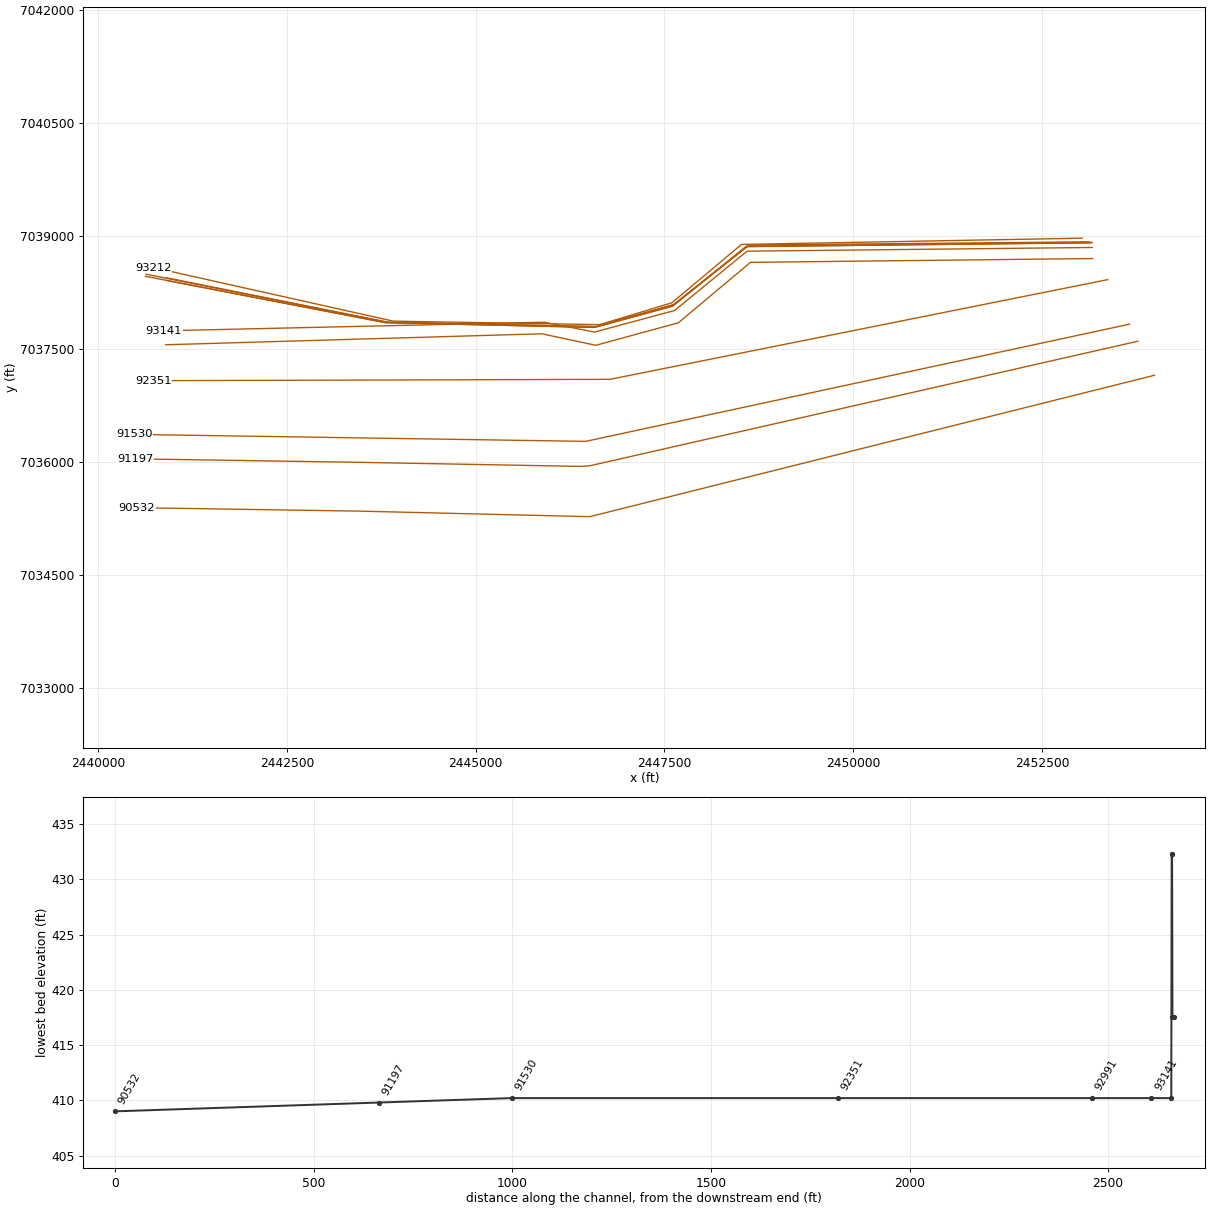
HEC-RAS study CDC_Consolidated_Model.prj: Upper Trinity CDC Consolidated Model

--- CDC_Consolidated_Model.g12 (geometry) --- (continued)

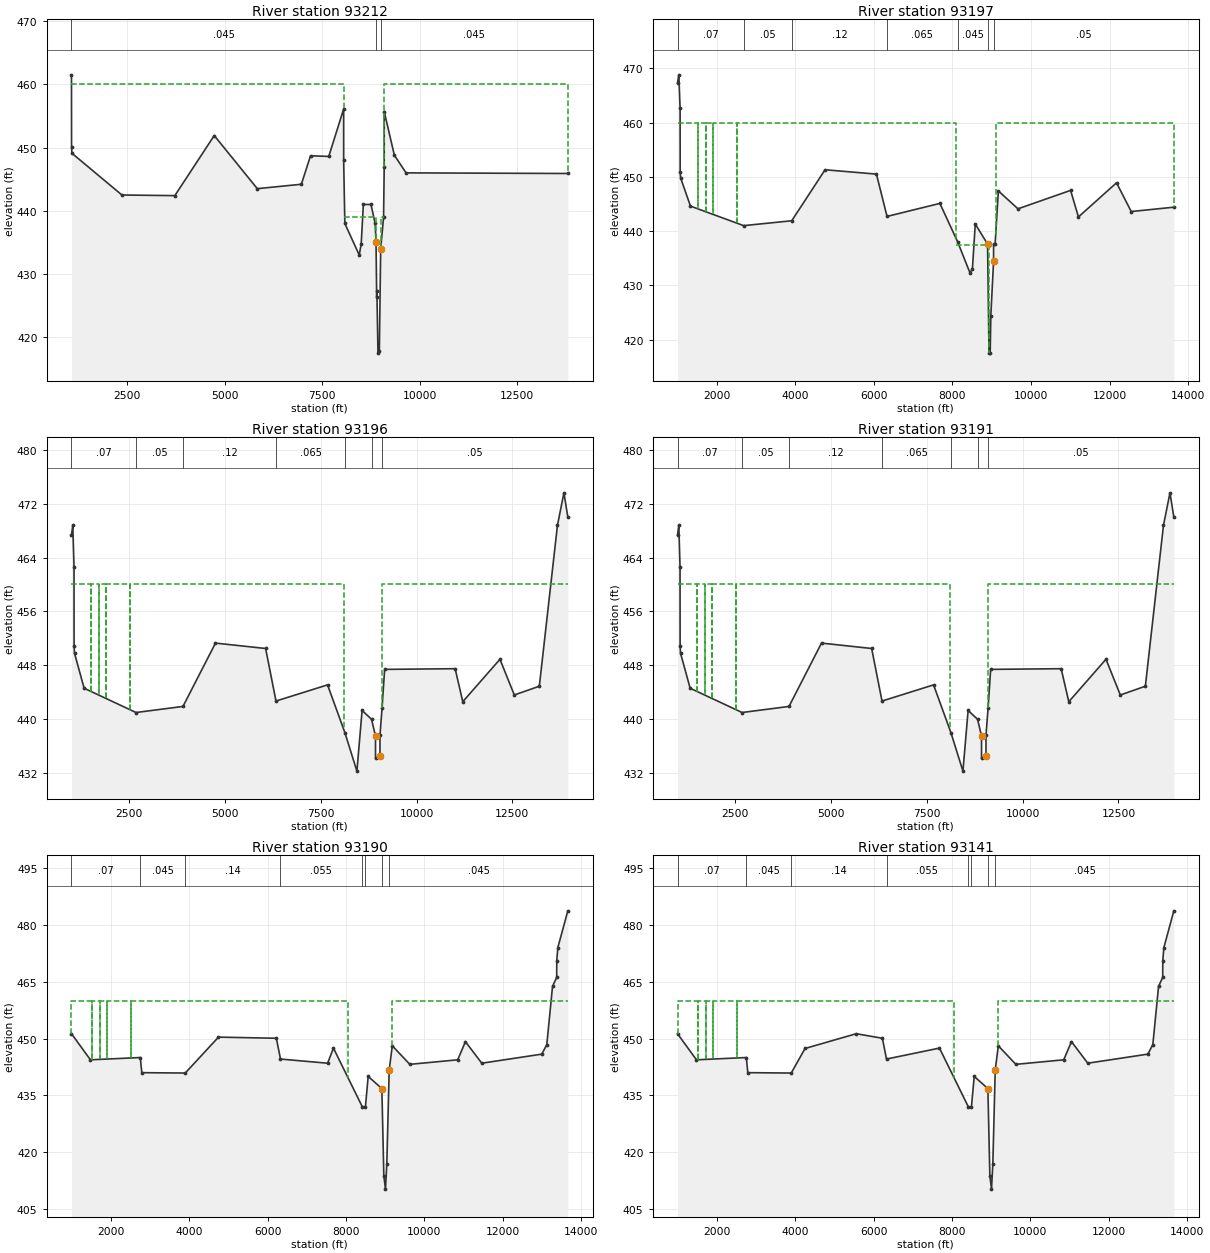
Type RM Length L Ch R = 1 ,93212   ,2,3,4
BEGIN DESCRIPTION:
This cross section corresponds to cross section 93212 of the non-georeferenced CDC model which was the source of this model.
Downstream bounding cross-section for Sandy Lake Road bridge
END DESCRIPTION:
XS GIS Cut Line= 6
2453032.140556017038966.992687632448520.069527697038883.64377296
2447597.799390587038109.242434642446642.141196947037819.29157096
2443907.252637837037866.266214552440736.861069247038575.79107872
#Sta/Elev= 30
    1068   461.5    1070   450.1    1079   449.1    2362   442.5    3719   442.4
    4730   451.9    5835   443.5    6965   444.2    7200   448.7    7668   448.6
    8050   456.1    8050     448    8080     438    8450     433    8500   434.8
    8555     441    8750     441    8858     438    8880     435    8897   426.3
    8902   427.4    8930   417.5    8965   417.8    9000     434    9074     439
    9090     447    9090   455.7    9350   448.8    9650     446   13800   445.9
#Mann= 3 ,0,0
    1068    .045       0    8880     .05       0    9000    .045       0
#XS Ineff= 4 ,-1
    1068    8050     460    8050    8880     439    9000    9090     439
    9090   13800     460
Permanent Ineff=
       F       F       F       F
Bank Sta=8880,9000
XS Rating Curve= 0 ,0
Exp/Cntr=0.3,0.1

Type RM Length L Ch R = 1 ,93197   ,1,1,1
BEGIN DESCRIPTION:
This cross section corresponds to cross section 93197 of the non-georeferenced CDC model which was the source of this model.
One-foot upstream of Carrollton Dam.  Duplication of previous cross-section (93191) with existing channel.
Channel data from NDM Elm Fork channel survey.
END DESCRIPTION:
XS GIS Cut Line= 6
2453120.484211337038918.043638542448624.117547937038876.03912938
2447622.075260677038085.549240542446594.051726167037793.92941697
2443835.875484027037852.248854132440907.53535428 7038441.0544172
#Sta/Elev= 30
    1000   467.3    1034   468.8    1066   462.6    1068   450.8    1079   449.8
    1330   444.6    2684     441    3908   441.9    4756   451.3    6064   450.5
    6334   442.7    7679   445.1    8132     438    8445   432.3    8507     433
    8580   441.3    8893   437.6    8930   417.5    8960   417.5    8976   424.4
    9046   434.5    9046   437.6    9086   437.7    9168   447.4    9667   444.1
   11007   447.5   11206   442.6   12176   448.9   12550   443.6   13635   444.4
#Mann= 7 ,-1,0
    1000     .07       0    2684     .05       0    3908     .12       0
    6334    .065       0    8132    .045       0    8893     .05       0
    9046     .05       0
#XS Ineff= 8 ,-1
    1000    1520     460    1520    1730     460    1730    1900     460
    1900    2520     460    2520    8100     460    8100    8930   437.5
    9046    9100   434.5    9100   13635     460
Permanent Ineff=
       F       T       F       T       F       F       F       F
Bank Sta=8893,9046
XS Rating Curve= 0 ,0
Exp/Cntr=0.3,0.1

Type RM Length L Ch R = 1 ,93196   ,1,1,1
BEGIN DESCRIPTION:
This cross section corresponds to cross section 93196 of the non-georeferenced CDC model which was the source of this model.
Carrollton Dam
Upstream face of dam.
END DESCRIPTION:
XS GIS Cut Line= 6
2453161.383407747038911.607299722448592.968660097038861.20648189
2447619.803611677038082.320244392446590.514987837037792.19451229
2443830.769195027037851.319065972440636.833981847038488.36241131
#Sta/Elev= 30
    1000   467.3    1034   468.8    1066   462.6    1068   450.8    1079   449.8
    1330   444.6    2684     441    3908   441.9    4756   451.3    6064   450.5
    6334   442.7    7679   445.1    8132     438    8445   432.3    8580   441.3
    8826     440    8930   437.5    8930   434.2    9046   434.5    9046   437.6
    9100   441.6    9168   447.4   11007   447.5   11206   442.6   12176   448.9
   12550   443.6   13203   444.9   13676   468.8   13845   473.6   13946     470
#Mann= 7 ,-1,0
    1000     .07       0    2684     .05       0    3908     .12       0
    6334    .065       0    8132    .045       0    8826     .02       0
    9100     .05       0
#XS Ineff= 8 ,-1
    1000    1520     460    1520    1730     460    1730    1900     460
    1900    2520     460    2520    8100     460    8100    8930   437.5
    9046    9100   434.5    9100   13946     460
Permanent Ineff=
       F       T       F       T       F       F       F       F
Bank Sta=8930,9046
XS Rating Curve= 0 ,0
Exp/Cntr=0.3,0.1

Type RM Length L Ch R = 1 ,93191   ,1,1,1
BEGIN DESCRIPTION:
This cross section corresponds to cross section 93191 of the non-georeferenced CDC model which was the source of this model.
Carrollton Dam
Weir crest length approx. 106 feet, minimum weir crest elev. 433.70.  Weir data from surveyed cross-section of structure.  Ground points from cross-section EF118.  Effective flow limit set at sta 8100 in LOB at sta 9100 in ROB. Carrollton Landfill in LOB, Riverchase project in ROB.
END DESCRIPTION:
XS GIS Cut Line= 6
2453153.701992667038906.782834312448582.513956587038855.67696539
2447608.631061857038066.236943222446572.952030847037783.50916222
2443805.37685734 7037846.64322232440628.477043187038460.56751938
#Sta/Elev= 30
    1000   467.3    1034   468.8    1066   462.6    1068   450.8    1079   449.8
    1330   444.6    2684     441    3908   441.9    4756   451.3    6064   450.5
    6334   442.7    7679   445.1    8132     438    8445   432.3    8580   441.3
    8826     440    8930   437.5    8930   434.2    9046   434.5    9046   437.6
    9100   441.6    9168   447.4   11007   447.5   11206   442.6   12176   448.9
   12550   443.6   13203   444.9   13676   468.8   13845   473.6   13946     470
#Mann= 7 ,-1,0
    1000     .07       0    2684     .05       0    3908     .12       0
    6334    .065       0    8132    .045       0    8826     .02       0
    9100     .05       0
#XS Ineff= 8 ,-1
    1000    1520     460    1520    1730     460    1730    1900     460
    1900    2520     460    2520    8100     460    8100    8930     432
    9046    9100   434.5    9100   13946     460
Permanent Ineff=
       F       T       F       T       F       F       F       F
Bank Sta=8930,9046
XS Rating Curve= 0 ,0
Exp/Cntr=0.3,0.1

Type RM Length L Ch R = 1 ,93190   ,50,50,50
BEGIN DESCRIPTION:
This cross section corresponds to cross section 93190 of the non-georeferenced CDC model which was the source of this model.
END DESCRIPTION:
XS GIS Cut Line= 6
      2453153.74      7038905.78     2448582.553     7038854.674
      2447608.67     7038065.234     2446572.991     7037782.506
     2443805.416     7037845.641   2440912.26527   7038404.73134
#Sta/Elev= 30
    1000   451.3    1483   444.4    2755     445    2793     441    3901   440.9
    4749   450.4    6224   450.1    6330   444.6    7532   443.5    7680   447.5
    8415     432    8496     432    8566     440    8915   436.8    8965   413.7
    9007   410.2    9041   416.8    9102   441.7    9181   448.1    9628   443.2
   10849   444.4   11046   449.2   11463   443.5   12993   445.9   13121   448.4
   13267   463.8   13373   466.2   13375   470.6   13403   474.1   13657   483.8
#Mann= 8 ,-1,0
    1000     .07       0    2755    .045       0    3901     .14       0
    6330    .055       0    8415    .035       0    8496     .12       0
    8915     .05       0    9102    .045       0
#XS Ineff= 8 ,-1
    1000    1520     460    1520    1730     460    1730    1900     460
    1900    2520     460    2520    8050     460    8050    8915   436.8
    9102    9181   441.7    9181   13657     460
Permanent Ineff=
       F       T       F       T       F       F       F       F
Bank Sta=8915,9102
XS Rating Curve= 0 ,0
Exp/Cntr=0.3,0.1

Type RM Length L Ch R = 1 ,93141   ,150,150,150
BEGIN DESCRIPTION:
93141
END DESCRIPTION:
XS GIS Cut Line= 6
2453165.058925337038843.361045142448594.03788367 7038794.2240043
2447632.440069357038006.71606489  2446574.4408737037721.01223996
2445907.796865087037851.960140792440871.561530777037738.01909572
#Sta/Elev= 30
    1000   451.3    1483   444.4    2755     445    2793     441    3901   440.9
    4252   447.4    5558   451.3    6224   450.1    6330   444.6    7680   447.5
    8415     432    8496     432    8566     440    8915   436.8    8965   413.7
    9007   410.2    9041   416.8    9102   441.7    9181   448.1    9628   443.2
   10849   444.4   11046   449.2   11463   443.5   12993   445.9   13121   448.4
   13267   463.8   13373   466.2   13375   470.6   13403   474.1   13657   483.8
#Mann= 8 ,-1,0
    1000     .07       0    2755    .045       0    3901     .14       0
    6330    .055       0    8415    .035       0    8496     .12       0
    8915     .05       0    9102    .045       0
#XS Ineff= 8 ,-1
    1000    1520     460    1520    1730     460    1730    1900     460
    1900    2520     460    2520    8050     460    8050    8915   436.8
    9102    9181   441.7    9181   13657     460
Permanent Ineff=
       F       T       F       T       F       F       F       F
Bank Sta=8915,9102
XS Rating Curve= 0 ,0
Exp/Cntr=0.3,0.1

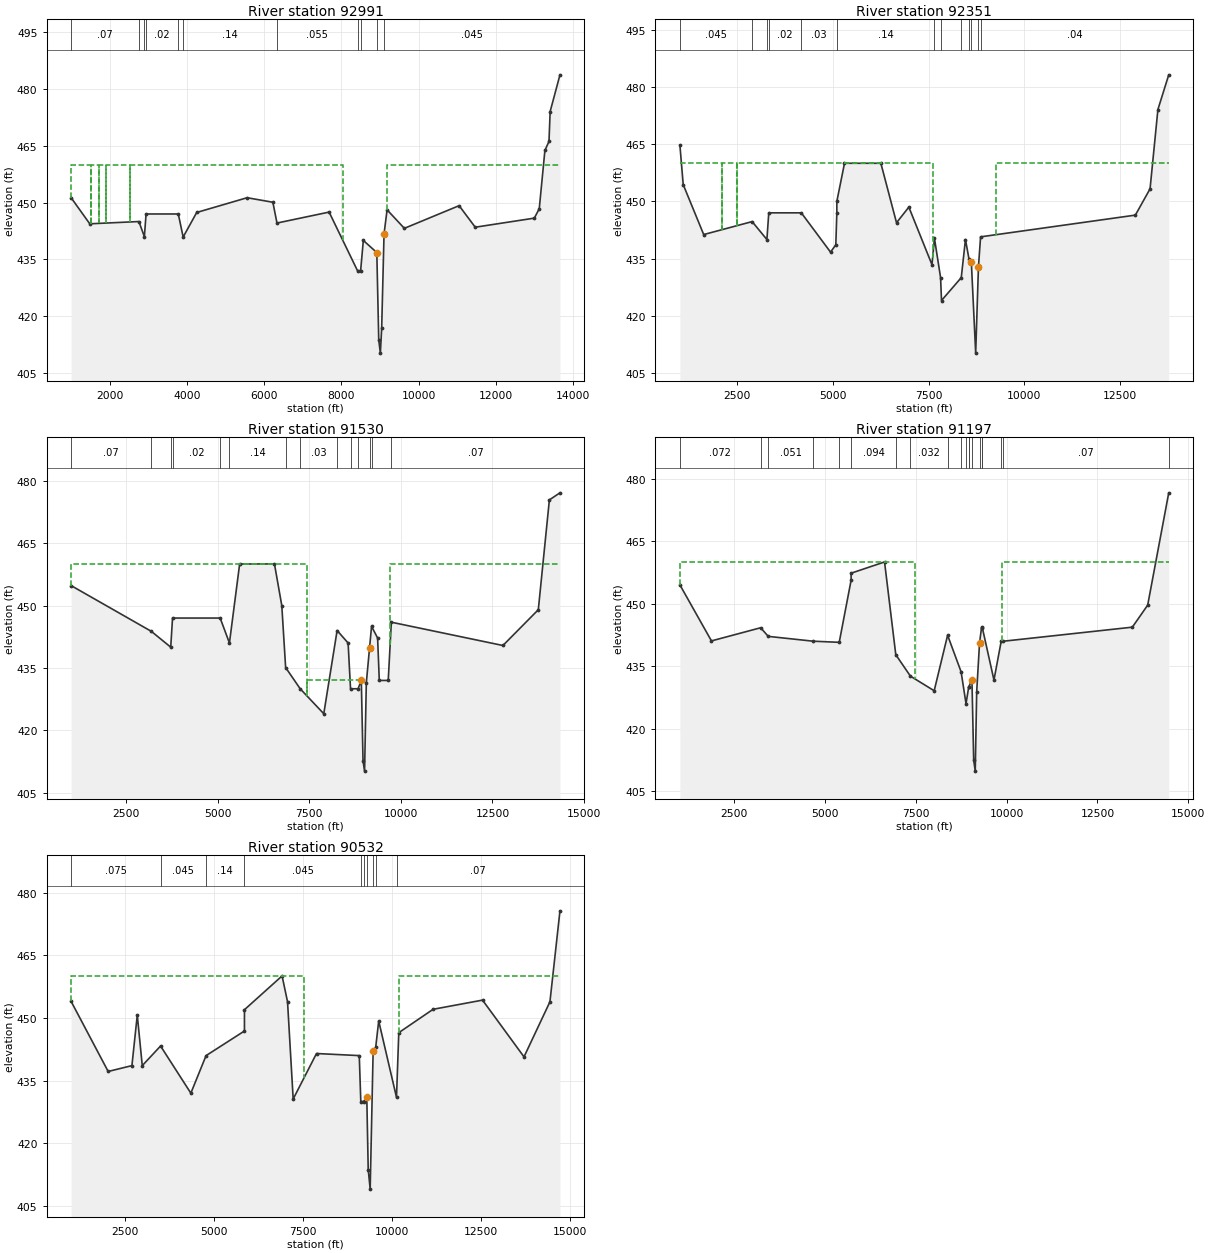
Type RM Length L Ch R = 1 ,92991   ,610,640,590
BEGIN DESCRIPTION:
92991
END DESCRIPTION:
XS GIS Cut Line= 6
  2453168.5703397038696.458968132448639.056450697038646.11174589
2447684.195339537037844.028412572446590.445339537037545.41730146
 2445876.90367297037698.19507922  2440897.0877737037552.57875979
#Sta/Elev= 30
    1000   451.3    1483   444.4    2755     445    2897     441    2941     447
    3775     447    3901   440.9    4252   447.4    5558   451.3    6224   450.1
    6330   444.6    7680   447.5    8415     432    8496     432    8566     440
    8915   436.8    8965   413.7    9007   410.2    9041   416.8    9102   441.7
    9181   448.1    9628   443.2   11046   449.2   11463   443.5   12993   445.9
   13121   448.4   13267   463.8   13373   466.2   13403   474.1   13657   483.8
#Mann= 11 ,-1,0
    1000     .07       0    2755    .045       0    2897     .03       0
    2941     .02       0    3775     .03       0    3901     .14       0
    6330    .055       0    8415    .035       0    8496     .12       0
    8915     .05       0    9102    .045       0
#XS Ineff= 8 ,-1
    1000    1520     460    1520    1730     460    1730    1900     460
    1900    2520     460    2520    8050     460    8050    8915   436.8
    9102    9181   441.7    9181   13657     460
Permanent Ineff=
       F       T       F       T       F       F       F       F
Bank Sta=8915,9102
XS Rating Curve= 0 ,0
Exp/Cntr=0.3,0.1

Type RM Length L Ch R = 1 ,92351   ,820,821,820
BEGIN DESCRIPTION:
92351
END DESCRIPTION:
XS GIS Cut Line= 3
2453370.468947597038416.698184552446778.237053337037093.70312713
2440731.940090847037076.10801797
#Sta/Elev= 30
    1000   464.8    1087   454.4    1622   441.3    2887   444.7    3273     440
    3322     447    4172     447    4935   436.7    5073   438.6    5100     447
    5100     450    5300     460    6250     460    6659   444.4    6981   448.5
    7585   433.4    7650   440.3    7810     430    7834     424    8350     430
    8460     440    8550     435    8613   434.2    8727   410.2    8799   432.8
    8855   440.7   12898   446.4   13282   453.3   13487   474.1   13770   483.2
#Mann= 13 ,-1,0
    1000    .045       0    2887    .045       0    3273     .03       0
    3322     .02       0    4172     .03       0    5100     .14       0
    7650     .05       0    7810     .03       0    8350     .05       0
    8550     .14       0    8613     .05       0    8799     .14       0
    8855     .04       0
#XS Ineff= 6 ,-1
    1000    2100     460    2100    2500     460    2500    7600     460
    7600    8613   434.2    8799    9270   432.8    9270   13770     460
Permanent Ineff=
       F       T       F       F       F       F
Bank Sta=8613,8799
XS Rating Curve= 0 ,0
Exp/Cntr=0.3,0.1

Type RM Length L Ch R = 1 ,91530   ,333.67,333,333.67
BEGIN DESCRIPTION:
CDC CAR 092120-1 Western Extrusions
91530
END DESCRIPTION:
XS GIS Cut Line= 3
  2453657.147836 7037825.5189207 2446457.1701102 7036270.7431589
 2440481.8169034 7036362.9293262
#Sta/Elev= 30
    1000   454.8    3190   443.8    3719     440    3768     447    5068     447
    5321     441    5600     460    6550     460    6750     450    6855   435.1
    7252     430    7896     424    8260     444    8560     441    8626     430
    8832     430    8920     432    8967   412.7    9009   410.2    9057   431.4
    9145   439.8    9200     445    9365   442.2    9411     432    9655     432
    9740     446   12785   440.4   13751     449   14053   475.4   14342   477.1
#Mann= 14 ,-1,0
    1000     .07       0    3190    .045       0    3719     .03       0
    3768     .02       0    5068     .03       0    5321     .14       0
    6855    .035       0    7252     .03       0    8260    .045       0
    8626     .03       0    8832     .05       0    9145     .14       0
    9200    .035       0    9740     .07       0
#XS Ineff= 4 ,-1
    1000    7450     460    7450    8920     432    9145    9706   439.8
    9706   14342     460
Permanent Ineff=
       F       F       F       F
Bank Sta=8920,9145
XS Rating Curve= 0 ,0
Exp/Cntr=0.3,0.1

Type RM Length L Ch R = 1 ,91197   ,666.33,665,666.33
BEGIN DESCRIPTION:
CDC CAR 092120-1 Western Extrusions
Added cross-section.
END DESCRIPTION:
XS GIS Cut Line= 5
  2453767.438232 7037599.3004438 2446520.9501075 7035948.8174417
 2446383.4797542 7035938.7495328 2443386.8610975 7035993.8023071
 2440492.7906828 7036038.5007509
#Sta/Elev= 30
    1000  454.53  1869.4  441.07 3224.14  444.23 3433.41  442.16 4671.46     441
 5388.36  440.73 5715.46  455.63 5715.46  457.33 6636.51  460.03 6946.27  437.75
 7349.46  432.61 8003.49   429.1 8373.17  442.43 8744.87  433.65 8880.45     426
 8954.08  429.99 8954.19  430.01 9043.46  431.67 9091.51  412.44 9134.46   409.8
 9174.16  428.82 9252.77  440.57 9307.92  444.26  9324.4  444.44 9649.69  431.67
 9849.34  440.99 9904.36  440.9913460.71  444.37 13883.5  449.6614463.46  476.63
#Mann= 20 ,-1,0
    1000    .072       0 3224.14    .046       0 3433.41    .051       0
 4671.46    .119       0 5388.36    .118       0 5715.46    .094       0
 6946.27    .036       0 7349.46    .032       0 8373.17    .041       0
 8744.87     .03       0 8880.45    .039       0 8954.08    .048       0
 8954.19    .048       0 9043.46     .11       0 9252.77     .14       0
 9307.92    .043       0  9324.4    .036       0 9849.34    .069       0
 9904.36     .07       014463.46     .07       0
#XS Ineff= 2 , 0
            7477     460    9866             460
Permanent Ineff=
       F       F
Bank Sta=9043.46,9252.77
XS Rating Curve= 0 ,0
Exp/Cntr=0.3,0.1

Type RM Length L Ch R = 1 ,90532   ,650,838,950
BEGIN DESCRIPTION:
90532
END DESCRIPTION:
XS GIS Cut Line= 4
2453987.691138337037147.536024722446511.170002167035271.50893688
2443460.91166702 7035345.00649332440514.705617167035390.60810813
#Sta/Elev= 30
    1000     454    2039   437.2    2705   438.6    2855   450.7    2995   438.6
    3508   443.3    4357     432    4784     441    5860   446.9    5860     452
    6915   460.1    7068   453.9    7226   430.6    7880   441.5    9079     441
    9122     430    9198     430    9290     431    9330   413.7    9385     409
    9468   442.1    9540     443    9624   449.3   10123     431   10187   446.5
   11149   452.1   12535   454.3   13698   440.7   14425   453.9   14706   475.7
#Mann= 10 ,-1,0
    1000    .075       0    3508    .045       0    4784     .14       0
    5860    .045       0    9122     .03       0    9198    .045       0
    9290     .05       0    9468     .14       0    9540    .035       0
   10123     .07       0
#XS Ineff= 4 ,-1
    1000    7530     460    7530    9290     431    9468   10187   442.1
   10187   14706     460
Permanent Ineff=
       F       F       F       F
Bank Sta=9290,9468
XS Rating Curve= 0 ,0
Exp/Cntr=0.3,0.1