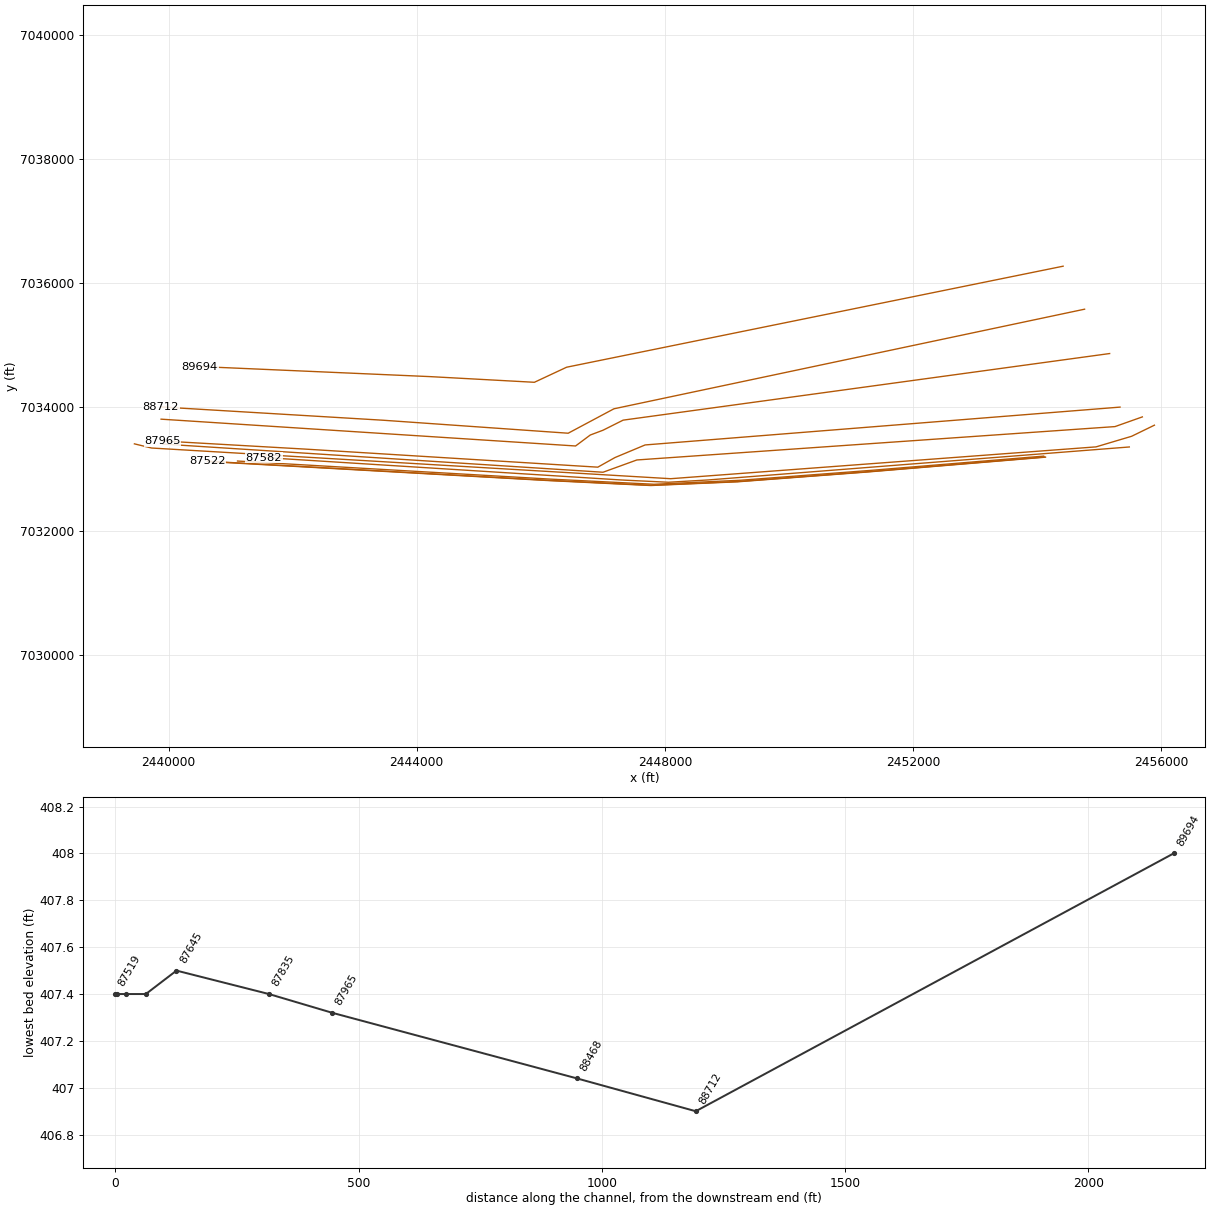
HEC-RAS study CDC_Consolidated_Model.prj: Upper Trinity CDC Consolidated Model

--- CDC_Consolidated_Model.g12 (geometry) --- (continued)

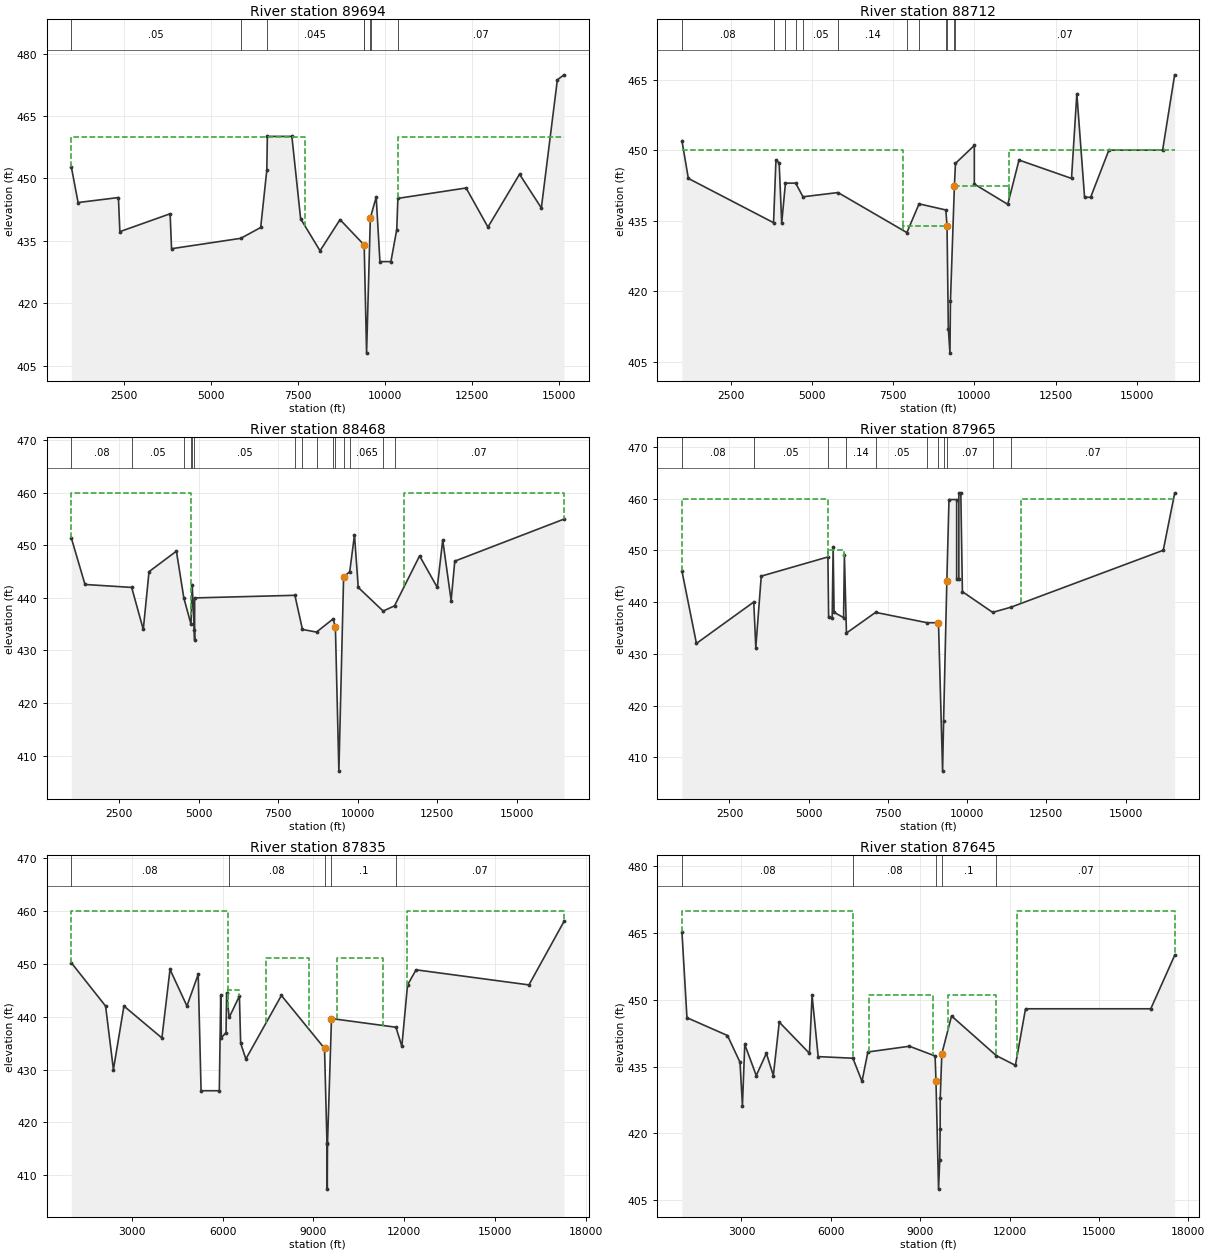
Type RM Length L Ch R = 1 ,89694   ,800,982,1000
BEGIN DESCRIPTION:
89694
---------------------------------------------------------------------
CDC CAR040507-1 Western Extrusions
Cross-section 89694-91530
Located in LOB within ineffective flow area.
---------------------------------------------------------------------
CDC 041718-01 Elm Fork WTP Improvements
Cross-section 89694 - 93141
Modification to LOB.
Revision of CDC CAR081214-01
---------------------------------------------------------------------
END DESCRIPTION:
XS GIS Cut Line= 5
2454416.018037597036265.561082632446415.268947247034636.62405179
2445895.703057267034393.601243882444214.567311917034485.10959105
2440505.224665027034647.44227163
#Sta/Elev= 30
    1000   452.8    1195   444.2    2352   445.4    2393   437.2    3835   441.5
    3876   433.1    5863   435.6    6433   438.2    6609     452    6624   460.1
    7328   460.1    7579   440.3    8136   432.6    8710   440.1    9390   434.1
    9402   434.1    9471     408    9579   440.5    9592   440.9    9747   445.5
    9854     430   10169     430   10337   437.7   10369   445.2   12326   447.7
   12953   438.3   13859     451   14485   442.9   14944   473.7   15135   474.9
#Mann= 8 ,-1,0
    1000     .05       0    5863     .14       0    6609    .045       0
    9390     .14       0    9402     .05       0    9579     .14       0
    9592     .05       0   10369     .07       0
#XS Ineff= 4 ,-1
    1000    7700     460    7700    9402   434.1    9579   10369   440.5
   10369   15135     460
Permanent Ineff=
       F       F       F       F
Bank Sta=9402,9579
XS Rating Curve= 0 ,0
Exp/Cntr=0.3,0.1

Type RM Length L Ch R = 1 ,88712   ,245,244,243
BEGIN DESCRIPTION:
88712
Includes CDC Elm Fork Water Treatment Plant Improvements project (CDC #: CAR 041718-01) from Station 93141 to 88712 (in LOB).
END DESCRIPTION:
XS GIS Cut Line= 5
2454761.838868267035572.279004632447177.857973257033966.21692805
2446440.408988837033572.352230222443455.711218097033782.00502613
 2439876.38143457033996.23688114
#Sta/Elev= 30
    1000     452 1197.54     444    3820   434.6    3894   447.9  3992.5   447.3
    4071   434.5  4185.7     443 4500.86     443    4726   440.1    5804     441
    7924   432.5    8299   438.6    9123   437.3    9160   433.9    9200   412.1
    9250   406.9    9265   417.9    9386   442.3    9420   447.2   10000     451
   10000   442.8   11029   438.5   11376   447.9 12991.8     444 13155.5     462
 13393.5     440 13580.5     440 14141.1     450   15796     450   16166     466
#Mann= 12 ,-1,0
    1000     .08       0    3820     .08       0  4185.7     .02       0
 4500.86     .08       0    4726     .05       0    5804     .14       0
    7924     .07       0    8299     .05       0    9123     .12       0
    9160     .05       0    9386     .12       0    9420     .07       0
#XS Ineff= 4 ,-1
    1000    7800     450    7800    9160   433.9    9386   11077   442.3
   11077   16166     450
Permanent Ineff=
       F       F       F       F
Bank Sta=9160,9386
XS Rating Curve= 0 ,0
Exp/Cntr=0.3,0.1

Type RM Length L Ch R = 1 ,88468   ,513,503,502
BEGIN DESCRIPTION:
88468
END DESCRIPTION:
XS GIS Cut Line= 6
  2455165.712732 7034857.1610123 2447326.1893695 7033783.3226088
 2447001.0978281 7033620.3491815 2446796.7258615 7033543.5494663
 2446559.5229238 7033366.6557912 2439880.4060327 7033799.0171312
#Sta/Elev= 30
    1000  451.43 1430.51  442.56 2896.97     442  3262.1     434  3442.8     445
    4303   448.9 4536.31     440  4761.2     435 4798.89  442.54 4865.54  433.91
 4875.44     432  4876.3     440 8026.34   440.5 8264.74     434 8705.74   433.5
 9226.49     436 9299.29   434.5    9409  407.04 9557.74     444 9750.17     445
 9899.17     45210017.17     44210800.17   437.511158.17   438.511945.17     448
12501.17     44212672.17     45112937.17   439.513051.17     44716484.09     455
#Mann= 15 ,-1,0
    1000     .08       0 2896.97     .05       0 4536.31     .02       0
  4761.2     .02       0 4798.89     .02       0 4865.54     .05       0
 8026.34     .14       0 8264.74     .07       0 8705.74    .045       0
 9226.49     .12       0 9299.29     .05       0 9557.74     .12       0
 9750.17    .065       010800.17     .14       011158.17     .07       0
#XS Ineff= 2 , 0
         4770.19     460   11470             460
Permanent Ineff=
       F       F
Bank Sta=9299.29,9557.74
XS Rating Curve= 0 ,0
Exp/Cntr=0.3,0.1

Type RM Length L Ch R = 1 ,87965   ,152,130,107
BEGIN DESCRIPTION:
87965
END DESCRIPTION:
XS GIS Cut Line= 6
  2455333.454851  7033993.496073  2447680.355984 7033383.3224246
 2447194.2834653 7033179.9117421 2446917.8561967 7033024.9891517
 2442202.4866904 7033316.2995927 2439902.7662243 7033447.3866009
#Sta/Elev= 30
    1000     446 1457.52     432 3266.29     440    3331   431.2 3502.81     445
  5607.2  448.71  5629.3  437.01  5741.6     437  5771.7  450.58  5801.8     438
  6101.7  436.99  6126.7     449 6192.09     434 7111.79     438 8736.46     436
 9096.46     436 9225.91  407.32 9257.76   417.1 9359.66     444 9427.92   459.8
 9669.67   459.8 9669.67   444.5 9738.86   444.5 9738.86   461.1 9800.81   461.1
 9851.41     44210805.41     43811383.01     43916189.79     450   16549     461
#Mann= 11 ,-1,0
    1000     .08       0 3266.29     .05       0  5607.2     .08       0
 6192.09     .14       0 7111.79     .05       0 8736.46     .12       0
 9096.46     .05       0 9257.76     .12       0 9359.66     .07       0
10805.41     .14       011383.01     .07       0
#XS Ineff= 3 ,-1
    1000    5596     460    5596    6130     450   11700   17000     460
Permanent Ineff=
       F       F       F
Bank Sta=9096.46,9359.66
XS Rating Curve= 0 ,0
Exp/Cntr=0.3,0.1

Type RM Length L Ch R = 1 ,87835   ,222,190,156
BEGIN DESCRIPTION:
Cross-Section added as part of CDC project CAR 122118 -01 (project extends from XS 88468 - 87645)
END DESCRIPTION:
XS GIS Cut Line= 5
  2455692.7971537033835.536125562455251.824931297033679.28612556
2447546.963820167033141.091681112447001.824931297032943.17501444
2439904.602709057033398.03612556
#Sta/Elev= 30
    1000  450.19  2132.7     442  2391.3     430  2738.9     442  3993.1  435.97
  4260.9  448.92    4820  442.01  5191.9     448  5287.1     426  5889.5     426
  5935.6     444  5958.7     436    6111  436.99  6131.1  444.46  6215.3  439.84
  6553.1   443.9  6594.2  434.98  6766.6     432  7940.6     444    9365     434
  9445.6  416.12    9455   407.4  9463.1     416    9595  439.64 11724.4     438
   11919   434.4 12107.6     446   12389  448.85 16117.6     446 17276.1     458
#Mann= 5 ,-1,0
    1000     .08       0  6215.3     .08       0    9365     .05       0
    9595      .1       0 11724.4     .07       0
#XS Ineff= 5 ,-1
    1000    6183     460    6183  6553.1     445    7423    8856     451
    9776   11305     451   12104   18000     460
Permanent Ineff=
       F       F       F       F       F
Bank Sta=9365,9595
XS Rating Curve= 0 ,0
Exp/Cntr=0.3,0.1

Type RM Length L Ch R = 1 ,87645   ,60.5,63,58
BEGIN DESCRIPTION:
87645
Luna Road Extension USACE Permit Number 199300443
Cross-section 87645 - 90532
Located in LOB.
---------------------------------------------------------------------
CDC CAR171221-01 Valwood Crossing
In LOB between cross-sections 87541 - 88712.
This project supercedes previous two CDC projects listed below.
CDC PROJECTS: CAR032511-1 AND CAR032511-2 PROPOSED LUNA ROAD LP and #2 LP
---------------------------------------------------------------------
END DESCRIPTION:
XS GIS Cut Line= 6
  2455887.095147 7033701.9940313 2455520.1280341  7033523.189927
  2454945.872949 7033352.1361352 2448091.4749124 7032838.9721353
 2439726.6963664 7033333.7142561 2439450.7848448 7033400.9532948
#Sta/Elev= 30
    1000  465.29 1168.59     446 2528.56     442 2949.73     436 3031.52  426.22
 3109.47     440 3496.07     433  3834.8     438  4069.4     433  4268.4     445
 5281.31     438  5370.2     451 5575.21  437.26    6740   436.9    7047   431.7
    7243   438.3 8639.04  439.59    9501   437.4    9531   431.7    9617   407.5
    9657     414    9671   421.1    9673   427.9    9727   437.910053.13  446.39
11552.79   437.5   12198   435.312537.56     448 16743.4     448 17544.8     460
#Mann= 5 ,-1,0
    1000     .08       0    6740     .08       0    9531     .05       0
    9727      .1       011552.79     .07       0
#XS Ineff= 4 ,-1
    1000 6740.01     470    7280    9420     451    9920   11560     451
 12249.9 17544.8     470
Permanent Ineff=
       F       F       F       F
Bank Sta=9531,9727
XS Rating Curve= 0 ,0
Exp/Cntr=0.3,0.1

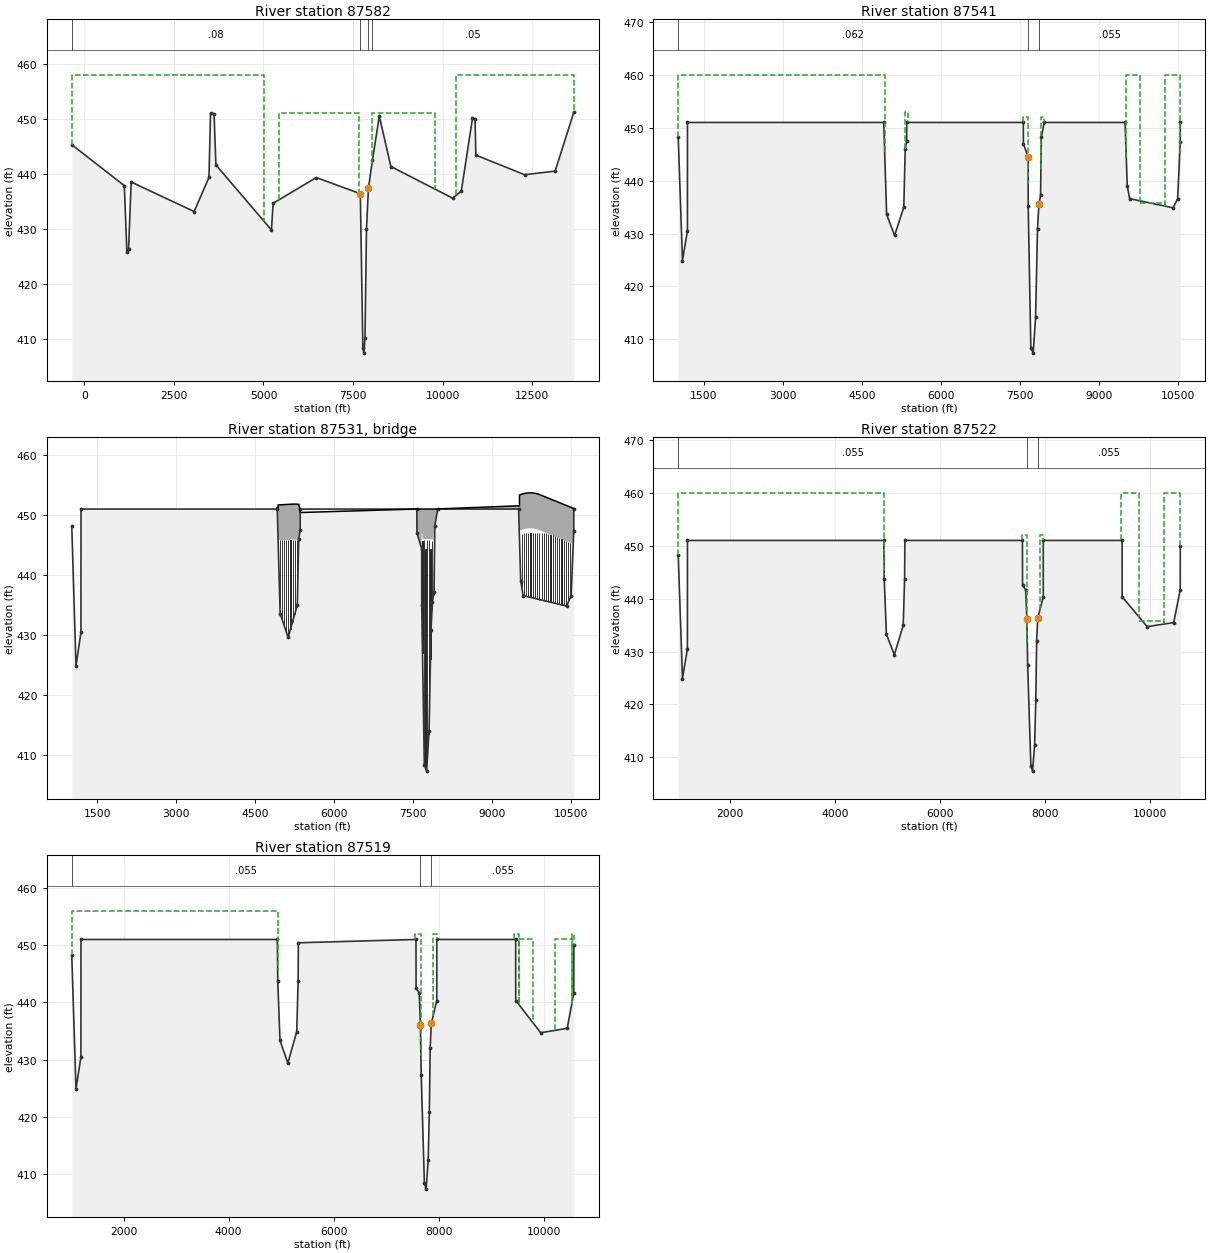
Type RM Length L Ch R = 1 ,87582   ,22,41,46
BEGIN DESCRIPTION:
New section at North ROW line
END DESCRIPTION:
XS GIS Cut Line= 6
  2455482.5050187033350.636150962448691.098768237032818.63383612
2448056.853976587032781.767516692447360.757861057032814.92204182
2447253.946713847032821.158431052441533.773826097033180.81554911
#Sta/Elev= 30
  -349.5   445.3  1116.9  437.85  1188.1  425.85 1234.69  426.28  1308.6  438.51
 3065.48  433.14 3478.73  439.35 3522.16     451 3621.33  450.95 3671.78  441.63
 5222.44  429.79 5267.85  434.64 6472.87  439.32 7702.19  436.39    7773   408.4
    7801   407.4    7833  410.15  7874.2  430.01    7929  437.38 8039.65  442.46
 8232.07  450.48 8554.92  441.3310277.71  435.5810519.14  436.8310832.48   450.1
10904.37  450.0310925.14  443.4112286.15  439.84 13138.5  440.4913660.51  451.23
#Mann= 4 ,-1,0
  -349.5     .08       0 7702.19     .05       0    7929     .06       0
 8039.65     .05       0
#XS Ineff= 4 ,-1
  -349.5  5016.5     458  5423.2  7675.1     451  8023.2  9794.4     451
 10378.813660.51     458
Permanent Ineff=
       T       T       T       T
Bank Sta=7702.19,7929
XS Rating Curve= 0 ,0
Exp/Cntr=0.5,0.3

Type RM Length L Ch R = 1 ,87541   ,19,19,19
BEGIN DESCRIPTION:
87541
H&B Trail added to Staion 5060 to 5074
---------------------------------------------------------------------
CDC CAR171221-01 Valwood Crossing
In LOB between cross-sections 87541 - 88712.
This project supercedes previous two CDC projects listed below.
CDC PROJECTS: CAR032511-1 AND CAR032511-2 PROPOSED LUNA ROAD LP and #2 LP
---------------------------------------------------------------------
END DESCRIPTION:
XS GIS Cut Line= 6
2454102.120371437033203.139057892451323.501912927032973.65756147
2449224.330586347032814.517131722447823.491196427032749.33812821
 2446156.59164317032832.145377292441112.34216543 7033123.6423869
#Sta/Elev= 30
  1015.6   448.2    1096   424.9    1190   430.5    1191     451    4916     451
    4971  433.61 5122.55  429.64 5296.85     435 5323.26     446 5351.51   447.5
    5352     451    7566     451    7567     447 7657.76  444.39 7658.21  435.12
    7708   408.4    7752   407.4 7798.15  414.14 7834.56  430.95 7861.47   435.5
 7892.34  437.21 7907.13  448.23    7962     451    9497     451 9537.45  439.05
 9584.03  436.59 10407.7  434.8710493.88  436.5510544.74  447.38   10545     451
#Mann= 3 ,0,0
  1015.6    .062       0 7657.76     .05       0 7861.47    .055       0
#XS Ineff= 10 ,-1
    1000    4935     460    4935    5324     439    5324    5380     453
    5380    7560     439    7560    7658     452    7899    7965     452
    7965    9520   435.8    9520  9783.1     460  9783.1 10255.6   435.8
 10255.6   10533     460
Permanent Ineff=
       F       F       F       F       T       T       F       T       F       T
Bank Sta=7657.76,7861.47
XS Rating Curve= 0 ,0
Exp/Cntr=0.5,0.3

Type RM Length L Ch R = 3 ,87531   ,,,
BEGIN DESCRIPTION:
Southern Pacific Railroad
END DESCRIPTION:
Node Name=SP Railroad
Bridge Culvert--1,0,-1,-1, 0
Deck Dist Width WeirC Skew NumUp NumDn MinLoCord MaxHiCord MaxSubmerge Is_Ogee
0.5,18,2.6,0, 71, 71, , , 0.95, 0, ,,,
    4915    4929 4931.49  4931.5  4967.5  5007.5  5047.5  5087.5  5127.5  5167.5
  5207.5  5216.5  5241.5  5247.5    5250  5287.5  5327.5 5327.51  5352.1    7550
    7550    7659 7659.01  7672.2 7672.21    7703  7731.8 7731.81  7734.2 7734.21
    7763    7820  7822.8 7822.81  7825.2  7825.2    7828  7853.5  7884.5 7884.51
    7898 7898.01    9514 9514.01    9556    9605    9640    9655    9705  9715.8
    9755    9805    9855    9892    9905    9910    9934    9976   10018   10060
   10102   10144   10186   10228   10270   10354   10438   10522   10533   10546
10546.01
  451.21  451.21  451.21  451.68 451.698 451.718 451.738 451.758 451.778 451.798
 451.818  451.82  451.83  451.83  451.83  451.82  451.78  451.78  450.42     451
     451     451     451     451     451     451     451     451     451     451
     451     451     451     451     451     451     451     451     451     451
     451     451 451.545  453.33  453.47  453.59 453.646  453.67   453.7   453.7
  453.69  453.63  453.53 453.417  453.38  453.36 453.267 453.118 452.968 452.819
 452.669 452.519  452.37  452.22 452.071 451.771 451.472  451.17  451.13  451.09
  451.09
                         445.763 445.781 445.801 445.821 445.841 445.861 445.881
 445.901 445.903 445.913 445.913 445.913 445.903 445.863                     451
     444     444  447.02  446.87  446.04  446.04     446   444.4   444.4     446
     446     446     446   444.4   444.4     446     446  445.98  445.95  446.93
  446.88     443         447.413 447.553 447.673 447.729 447.753 447.783 447.783
 447.773 447.713 447.613   447.5 447.463 447.443  447.35 447.201 447.051 446.902
 446.752 446.602 446.453 446.303 446.154 445.854 445.555  445.26  445.22  445.18
    4927    4929 4931.49  4931.5  4967.5  5007.5  5047.5  5087.5  5127.5  5167.5
  5207.5  5216.5  5241.5  5247.5    5250  5287.5  5327.5 5327.51  5352.1    7550
    7550    7659 7659.01  7672.2 7672.21    7703  7731.8 7731.81  7734.2 7734.21
    7763    7820  7822.8 7822.81  7825.2  7825.2    7828  7853.5  7884.5 7884.51
    7898 7898.01    9514 9514.01    9556    9605    9640    9655    9705  9715.8
    9755    9805    9855    9892    9905    9910    9934    9976   10018   10060
   10102   10144   10186   10228   10270   10354   10438   10522   10533   10575
10575.01
  451.21  451.21  451.21  451.68 451.698 451.718 451.738 451.758 451.778 451.798
 451.818  451.82  451.83  451.83  451.83  451.82  451.78  451.78  450.42     451
     451     451     451     451     451     451     451     451     451     451
     451     451     451     451     451     451     451     451     451     451
     451     451 451.545  453.33  453.47  453.59 453.646  453.67   453.7   453.7
  453.69  453.63  453.53 453.417  453.38  453.36 453.267 453.118 452.968 452.819
 452.669 452.519  452.37  452.22 452.071 451.771 451.472  451.17  451.13     451
     451
                         445.763 445.781 445.801 445.821 445.841 445.861 445.881
 445.901 445.903 445.913 445.913 445.913 445.903 445.863
                  446.97  447.05  445.95  446.04     446   444.4   444.4     446
     446     446     446   444.4   444.4     446     446  445.93  446.02  446.98
  446.92                 447.413 447.553 447.673 447.729 447.753 447.783 447.783
 447.773 447.713 447.613   447.5 447.463 447.443  447.35 447.201 447.051 446.902
 446.752 446.602 446.453 446.303 446.154 445.854 445.555  445.26  445.22  445.09
Pier Skew, UpSta & Num, DnSta & Num=  ,4967.5, 6 ,4967.5, 6 , 5 , 5 , 0 ,,
       2       2   1.167   1.167       3       3
     420  436.72  436.72 442.719 442.719     447
       2       2   1.167   1.167       3       3
     420  436.72  436.72 442.719 442.719     447
Pier Skew, UpSta & Num, DnSta & Num=  ,5007.5, 6 ,5007.5, 6 , 5 , 5 , 0 ,,
       2       2   1.167   1.167       3       3
     420  433.74  433.74 442.739 442.739     447
       2       2   1.167   1.167       3       3
     420  433.74  433.74 442.739 442.739     447
Pier Skew, UpSta & Num, DnSta & Num=  ,5047.5, 6 ,5047.5, 6 , 5 , 5 , 0 ,,
       2       2   1.167   1.167       3       3
     420  432.26  432.26 442.759 442.759     447
       2       2   1.167   1.167       3       3
     420  432.26  432.26 442.759 442.759     447
Pier Skew, UpSta & Num, DnSta & Num=  ,5087.5, 6 ,5087.5, 6 , 5 , 5 , 0 ,,
       2       2   1.167   1.167       3       3
     420  431.78  431.78 442.779 442.779     447
       2       2   1.167   1.167       3       3
     420  431.78  431.78 442.779 442.779     447
Pier Skew, UpSta & Num, DnSta & Num=  ,5127.5, 6 ,5127.5, 6 , 5 , 5 , 0 ,,
       2       2   1.167   1.167       3       3
     420   431.3   431.3 442.799 442.799     447
       2       2   1.167   1.167       3       3
     420   431.3   431.3 442.799 442.799     447
Pier Skew, UpSta & Num, DnSta & Num=  ,5167.5, 6 ,5167.5, 6 , 5 , 5 , 0 ,,
       2       2   1.167   1.167       3       3
     420  432.32  432.32 442.819 442.819     447
       2       2   1.167   1.167       3       3
     420  432.32  432.32 442.819 442.819     447
Pier Skew, UpSta & Num, DnSta & Num=  ,5207.5, 6 ,5207.5, 6 , 5 , 5 , 0 ,,
       2       2   1.167   1.167       3       3
     420  432.84  432.84 442.839 442.839     447
       2       2   1.167   1.167       3       3
     420  432.84  432.84 442.839 442.839     447
Pier Skew, UpSta & Num, DnSta & Num=  ,5247.5, 6 ,5247.5, 6 , 5 , 5 , 0 ,,
       2       2   1.167   1.167       3       3
     420  434.85  434.85 442.851 442.851     447
       2       2   1.167   1.167       3       3
     420  434.85  434.85 442.851 442.851     447
Pier Skew, UpSta & Num, DnSta & Num=  ,5287.5, 6 ,5287.5, 6 , 5 , 5 , 0 ,,
       2       2   1.167   1.167       3       3
     420  435.84  435.84 442.841 442.841     447
       2       2   1.167   1.167       3       3
     420  435.84  435.84 442.841 442.841     447
Pier Skew, UpSta & Num, DnSta & Num=  ,7673.1, 4 ,7673.1, 4 , 3 , 3 , 0 ,,
     1.5     1.5       3       3
     415  443.39  443.39   445.7
     1.5     1.5       3       3
     415  443.33  443.33  445.75
Pier Skew, UpSta & Num, DnSta & Num=  ,7703, 4 ,7703, 4 , 3 , 3 , 0 ,,
     1.5     1.5     2.5     2.5
     415  443.22  443.22   445.8
     1.5     1.5     2.5     2.5
     415  443.33  443.33  445.83
Pier Skew, UpSta & Num, DnSta & Num=  ,7733, 2 ,7733, 2 , 0 , 0 , 0 ,,
       8     5.8
     420   444.4
       8     5.8
     420   444.4
Pier Skew, UpSta & Num, DnSta & Num=  ,7763, 4 ,7763, 4 , 3 , 3 , 0 ,,
     1.5     1.5     2.5     2.5
     415  443.28  443.28  445.84
     1.5     1.5     2.5     2.5
     415  443.28  443.28  445.78
Pier Skew, UpSta & Num, DnSta & Num=  ,7793, 4 ,7793, 4 , 3 , 3 , 0 ,,
     1.5     1.5     2.5     2.5
     415  443.28  443.28  445.84
     1.5     1.5     2.5     2.5
     415  443.28  443.28  445.78
Pier Skew, UpSta & Num, DnSta & Num=  ,7824, 2 ,7824, 2 , 0 , 0 , 0 ,,
       8     5.8
     420   444.4
       8     5.8
     420   444.4
Pier Skew, UpSta & Num, DnSta & Num=  ,7853.5, 4 ,7853.5, 4 , 3 , 3 , 0 ,,
     1.5     1.5     2.5     2.5
     415   443.2   443.2  445.76
     1.5     1.5     2.5     2.5
     415   443.2   443.2  445.75
Pier Skew, UpSta & Num, DnSta & Num=  ,7883.5, 4 ,7883.5, 4 , 3 , 3 , 0 ,,
     1.5     1.5     2.5     2.5
     415   443.2   443.2  445.76
     1.5     1.5     2.5     2.5
     415   443.2   443.2  445.75
Pier Skew, UpSta & Num, DnSta & Num=  ,9556, 6 ,9556, 6 , 5 , 5 , 0 ,,
       2       2   1.167   1.167       3       3
     420  440.62  440.62 444.491 444.491 446.849
       2       2   1.167   1.167       3       3
     420  440.62  440.62 444.491 444.491 446.849
Pier Skew, UpSta & Num, DnSta & Num=  ,9598, 6 ,9598, 6 , 5 , 5 , 0 ,,
       2       2   1.167   1.167       3       3
     420  438.67  438.67 444.594 444.594     447
       2       2   1.167   1.167       3       3
     420  438.67  438.67 444.594 444.594     447
Pier Skew, UpSta & Num, DnSta & Num=  ,9640, 6 ,9640, 6 , 5 , 5 , 0 ,,
       2       2   1.167   1.167       3       3
     420  437.73  437.73 444.667 444.667     447
       2       2   1.167   1.167       3       3
     420  437.73  437.73 444.667 444.667     447
Pier Skew, UpSta & Num, DnSta & Num=  ,9682, 6 ,9682, 6 , 5 , 5 , 0 ,,
       2       2   1.167   1.167       3       3
     420  438.78  438.78 444.711 444.711     447
       2       2   1.167   1.167       3       3
     420  438.78  438.78 444.711 444.711     447
Pier Skew, UpSta & Num, DnSta & Num=  ,9724, 6 ,9724, 6 , 5 , 5 , 0 ,,
       2       2   1.167   1.167       3       3
     420  438.89  438.89 444.721 444.721     447
       2       2   1.167   1.167       3       3
     420  438.89  438.89 444.721 444.721     447
Pier Skew, UpSta & Num, DnSta & Num=  ,9766, 6 ,9766, 6 , 5 , 5 , 0 ,,
       2       2   1.167   1.167       3       3
     420  438.94  438.94 444.698 444.698     447
       2       2   1.167   1.167       3       3
     420  438.94  438.94 444.698 444.698     447
Pier Skew, UpSta & Num, DnSta & Num=  ,9808, 6 ,9808, 6 , 5 , 5 , 0 ,,
       2       2   1.167   1.167       3       3
     420  436.99  436.99 444.641 444.641     447
       2       2   1.167   1.167       3       3
     420  436.99  436.99 444.641 444.641     447
Pier Skew, UpSta & Num, DnSta & Num=  ,9850, 6 ,9850, 6 , 5 , 5 , 0 ,,
       2       2   1.167   1.167       3       3
     420  437.05  437.05 444.561 444.561     447
       2       2   1.167   1.167       3       3
     420  437.05  437.05 444.561 444.561     447
Pier Skew, UpSta & Num, DnSta & Num=  ,9892, 6 ,9892, 6 , 5 , 5 , 0 ,,
       2       2   1.167   1.167       3       3
     420  436.94  436.94 444.438 444.438     447
       2       2   1.167   1.167       3       3
     420  436.94  436.94 444.438 444.438     447
Pier Skew, UpSta & Num, DnSta & Num=  ,9934, 6 ,9934, 6 , 5 , 5 , 0 ,,
       2       2   1.167   1.167       3       3
     420  436.29  436.29 444.288 444.288     447
       2       2   1.167   1.167       3       3
     420  436.29  436.29 444.288 444.288     447
Pier Skew, UpSta & Num, DnSta & Num=  ,9976, 6 ,9976, 6 , 5 , 5 , 0 ,,
       2       2   1.167   1.167       3       3
     420  436.64  436.64 444.138 444.138     447
       2       2   1.167   1.167       3       3
     420  436.64  436.64 444.138 444.138     447
Pier Skew, UpSta & Num, DnSta & Num=  ,10018, 6 ,10018, 6 , 5 , 5 , 0 ,,
       2       2   1.167   1.167       3       3
     420  436.49  436.49 443.989 443.989     447
       2       2   1.167   1.167       3       3
     420  436.49  436.49 443.989 443.989     447
Pier Skew, UpSta & Num, DnSta & Num=  ,10060, 6 ,10060, 6 , 5 , 5 , 0 ,,
       2       2   1.167   1.167       3       3
     420  436.84  436.84 443.839 443.839     447
       2       2   1.167   1.167       3       3
     420  436.84  436.84 443.839 443.839     447
Pier Skew, UpSta & Num, DnSta & Num=  ,10102, 6 ,10102, 6 , 5 , 5 , 0 ,,
       2       2   1.167   1.167       3       3
     420  436.69  436.69  443.69  443.69     447
       2       2   1.167   1.167       3       3
     420  436.69  436.69  443.69  443.69     447
Pier Skew, UpSta & Num, DnSta & Num=  ,10144, 6 ,10144, 6 , 5 , 5 , 0 ,,
       2       2   1.167   1.167       3       3
     420  436.54  436.54  443.54  443.54     447
       2       2   1.167   1.167       3       3
     420  436.54  436.54  443.54  443.54     447
Pier Skew, UpSta & Num, DnSta & Num=  ,10186, 6 ,10186, 6 , 5 , 5 , 0 ,,
       2       2   1.167   1.167       3       3
     420  436.39  436.39  443.39  443.39     447
       2       2   1.167   1.167       3       3
     420  436.39  436.39  443.39  443.39     447
Pier Skew, UpSta & Num, DnSta & Num=  ,10228, 6 ,10228, 6 , 5 , 5 , 0 ,,
       2       2   1.167   1.167       3       3
     420  436.74  436.74 443.241 443.241     447
       2       2   1.167   1.167       3       3
     420  436.74  436.74 443.241 443.241     447
Pier Skew, UpSta & Num, DnSta & Num=  ,10270, 6 ,10270, 6 , 5 , 5 , 0 ,,
       2       2   1.167   1.167       3       3
     420  437.73  437.73 443.091 443.091     447
       2       2   1.167   1.167       3       3
     420  437.73  437.73 443.091 443.091     447
Pier Skew, UpSta & Num, DnSta & Num=  ,10312, 6 ,10312, 6 , 5 , 5 , 0 ,,
       2       2   1.167   1.167       3       3
     420  438.66  438.66 442.942 442.942     447
       2       2   1.167   1.167       3       3
     420  438.66  438.66 442.942 442.942     447
Pier Skew, UpSta & Num, DnSta & Num=  ,10352, 6 ,10352, 6 , 5 , 5 , 0 ,,
       2       2   1.167   1.167       3       3
     420  438.58  438.58 442.792 442.792     447
       2       2   1.167   1.167       3       3
     420  438.58  438.58 442.792 442.792     447
Pier Skew, UpSta & Num, DnSta & Num=  ,10396, 6 ,10396, 6 , 5 , 5 , 0 ,,
       2       2   1.167   1.167       3       3
     420   437.5   437.5 442.642 442.642     447
       2       2   1.167   1.167       3       3
     420   437.5   437.5 442.642 442.642     447
Pier Skew, UpSta & Num, DnSta & Num=  ,10438, 6 ,10438, 6 , 5 , 5 , 0 ,,
       2       2   1.167   1.167       3       3
     420  437.35  437.35 442.493 442.493     447
       2       2   1.167   1.167       3       3
     420  437.35  437.35 442.493 442.493     447
Pier Skew, UpSta & Num, DnSta & Num=  ,10480, 6 ,10480, 6 , 5 , 5 , 0 ,,
       2       2   1.167   1.167       3       3
     420  438.27  438.27 442.343 442.343     447
       2       2   1.167   1.167       3       3
     420  438.27  438.27 442.343 442.343     447
Abutment Skew #Up #Dn= , 4 , 4
    4928 4935.75 4935.75 4959.75
     446     446   443.7   435.7
    4928 4935.75 4935.75 4959.75
     446     446   443.7   435.7
Abutment Skew #Up #Dn= , 4 , 4
 5293.25 5323.25 5323.25    5330
   433.8   443.8     446     446
 5293.25 5323.25 5323.25    5330
   433.8   443.8     446     446
Abutment Skew #Up #Dn= , 3 , 5
    7656  7660.5  7663.6
  444.61  444.36  431.29
    7620    7656  7660.5  7663.8  7664.8
  444.17  444.17  444.09  429.79  426.29
Abutment Skew #Up #Dn= , 4 , 5
  7894.5  7895.5  7896.5  7899.7
     433  438.03  444.42  444.53
  7894.6  7895.6  7896.5  7899.7    7964
   434.7   439.7  444.38  444.48  444.48
Abutment Skew #Up #Dn= , 4 , 4
    9513 9515.49  9515.5  9545.5
   447.8   447.8   445.9   435.9
    9513 9515.49  9515.5  9545.5
   447.8   447.8   445.9   435.9
Abutment Skew #Up #Dn= , 4 , 4
 10502.5 10520.510520.51   10540
  437.75  443.75   445.5   445.5
 10502.5 10520.510520.51   10576
  437.75  443.75   445.5   445.5
BR Coef= 1 , 0 , 0 ,1.05, 0 ,,,0.8,-1,0.5,1,
WSPro=,,,, 1 ,,,, 0 ,,,, 0 ,,,,-1 ,-1 ,-1 , 0 , 0 , 0 , 0 , 0
BR U #Sta/Elev= 247
  1015.6   448.2    1016   445.7    1037   439.5  1054.5  437.17  1063.5  435.15
    1082   426.6    1096   424.9  1098.5   424.9  1107.5   424.9    1127   424.9
  1142.5   427.1  1151.5  427.29    1171   427.6    1190   430.5    1191   448.2
    1191     451    4916     451 4916.01   448.2 4916.57  439.63 4923.95 439.706
 4930.89 440.055 4935.81 439.731 4947.02 438.847 4955.06  436.55  4963.5  436.01
    4965  435.61    4971  433.61 4973.39  433.56  4984.6  433.23 4995.45  432.93
    4998  432.89 5006.56  432.83    5011  431.35  5039.5  431.02  5075.5   430.6
  5111.5   430.2 5116.93 430.097 5122.55 429.641 5129.63 429.908 5133.65 430.107
 5135.97  430.48 5139.11  430.75  5147.5  430.77 5149.76 431.228 5152.02  431.22
  5173.3 431.464 5177.27  431.17  5183.5  430.84 5186.13 430.645 5200.58 430.934
  5219.5  431.09 5221.63 431.046 5224.97 430.935 5227.17 431.156 5231.32 431.669
 5245.97 433.142 5249.52 433.148  5255.5   433.8 5273.71  434.23  5291.5   434.8
 5296.85     435 5318.03 435.872 5322.05 435.986 5325.21 436.038 5347.66 436.703
 5351.51 437.197  5351.9   448.2    5352     451    7566     451    7567     447
 7567.94 447.523  7581.6 447.539 7582.23 447.541 7586.28 447.393 7602.55 447.119
 7608.87 447.148 7611.57 447.038 7625.42 446.953 7629.12 446.892 7633.28 446.687
 7642.31 446.646 7648.27 446.917 7650.65 447.397 7651.03 445.966 7652.18 445.821
 7654.57 445.739 7654.83 446.275 7655.16 446.612 7656.25 446.567 7656.82 446.487
 7657.34 443.126 7657.76 444.387 7658.21 435.118 7660.61 433.495 7669.19 429.428
 7672.14 427.807 7676.86 423.918 7677.97 423.391 7678.29 423.105  7679.8 422.371
 7682.01 421.133 7683.96 419.975 7686.71 418.424 7687.43 418.074 7689.71  417.04
 7692.27 415.622 7693.12  415.39 7696.45 414.584 7697.37 413.884 7698.03 413.505
    7703   411.2    7708   408.4    7752   407.4    7775   409.3    7790   412.4
  7795.2 413.577 7798.15 414.135 7798.62 414.288 7799.24 414.597 7802.24 416.074
 7804.39 416.953 7811.12 420.398 7811.92 420.606 7820.09 423.483 7822.96 424.767
 7832.27 429.331 7834.56  430.95 7838.43 431.534 7848.02  433.08 7854.73 434.232
 7861.47 435.503 7871.49 435.629 7872.89 435.653 7873.52 435.683 7880.66 435.998
 7883.47   436.2 7883.76 436.243 7892.34 437.207 7892.56 437.277 7893.38 437.544
 7897.84 438.951 7898.41 442.692  7898.8 443.661 7899.62 445.869 7901.26 446.151
 7902.35 446.497 7906.53 447.151 7906.93 447.798 7907.13  448.23 7907.99 448.029
 7909.82 447.959  7911.2 447.417 7915.76 447.514 7923.86   447.4 7930.13 447.875
 7940.53 447.951 7946.08 448.051 7961.94 448.136    7962     451    9497     451
    9497   448.2 9497.69  447.65 9503.88 447.355 9515.22 447.536    9520 447.474
  9520.3 447.069  9520.6 444.995 9522.59 444.505  9529.8 441.907 9537.45 439.049
 9548.52 437.755  9550.5 437.513 9573.09 436.797 9580.57  436.67 9584.03 436.591
 9605.49 436.244 9615.63 436.362 9619.53 436.371 9637.76 436.591 9646.12 436.673
  9679.1 436.761 9686.73 436.827    9694  436.24    9730  436.11    9766  435.97
 9786.69   435.9    9802  435.84    9838  435.71    9874  435.57    9910  435.44
 9916.03 435.543 9924.82 435.239 9930.34 435.134    9946  435.01 9952.16 435.019
 9964.54 435.031 9972.74  434.89 9979.36 434.998 9987.96 434.936 9993.33 434.934
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BR U #Mann= 5
  1015.6    .072    7566    .055 7657.76     .04 7861.47    .055    9497    .075
BR D #Sta/Elev= 228
  1015.6   448.2    1016   445.7    1037   439.5  1054.5  437.17  1063.5  435.15
    1082   426.6    1096   424.9  1098.5   424.9  1107.5   424.9    1127   424.9
  1142.5   427.1  1151.5  427.29    1171   427.6    1190   430.5    1191   448.2
    1191     451    4927     451    4928   448.2 4928.87  447.32  4929.7  446.92
 4930.41   445.9 4930.69  444.93 4936.46  441.94 4939.02  441.24 4940.81  440.62
 4953.45  436.55  4955.5  435.86  4966.5  435.64  4967.5  435.62  4970.2  435.57
  4977.1  433.27 4979.37  433.24 4989.54  433.01 4999.67  432.81 5001.67  432.77
 5006.85  432.69    5011  431.29  5039.5  430.98  5075.5  430.59  5111.5  430.23
 5114.87 430.172  5124.9  429.54 5127.86  429.41 5128.48  429.48  5138.6  430.48
  5147.5  430.82 5154.51  431.01 5168.85  431.22 5186.18  431.24 5196.77  431.06
 5200.51  431.03 5216.28  432.21 5235.22  433.21  5241.2  433.51  5255.5  433.81
  5291.5  434.79 5302.43  435.11 5303.03  435.31 5322.03  441.53 5323.33     442
 5326.55  443.55 5327.42  446.37 5327.49  447.28  5327.5  450.42    5328   448.2
 5328.01     451    7566     451    7567     447 7567.96 442.503 7574.74 442.437
 7581.58 442.264 7596.12 442.165 7604.14 441.848  7606.9 442.031 7625.67 441.741
 7627.83 441.692 7644.12 438.821 7645.81 438.698 7646.54 438.145  7649.7 436.093
 7665.58 427.395 7669.53 426.421 7673.46 425.623 7675.42 424.953 7678.06 424.327
 7682.06 423.445 7690.31 421.169 7693.72 420.063 7695.73 419.491  7698.8 418.547
 7703.82 417.164 7710.74 414.784 7711.99 414.323 7712.87 414.065 7713.72 413.732
    7720   411.2    7726   408.4    7758   407.4    7787   409.3    7798   412.4
 7801.02 413.766 7801.95 414.426 7803.22 414.936 7810.84 419.308  7814.4 419.852
 7820.02 420.851 7821.12  421.46 7827.31 424.705 7829.31  425.79 7829.84 426.197
 7835.95 432.043 7839.86  432.73 7846.01 434.125 7857.61 436.332  7876.9 436.175
 7886.24 436.806  7897.3 437.103 7904.52 438.428 7910.18 438.966 7927.49 439.174
 7935.01 440.183 7939.65 440.213 7942.19 440.376 7958.75 440.387 7961.96 440.328
    7962     451    9463     451 9463.62 440.342 9476.81 440.065 9479.04 440.099
 9490.07  440.33 9504.79 440.548 9511.66 440.512 9528.17 439.927 9532.35 439.494
  9543.7 438.895  9547.1 438.435 9549.55 438.174 9557.94 437.668 9572.01 437.294
 9579.77 437.293 9582.01 437.227 9585.78 437.074 9592.73 436.929 9594.94 436.934
 9609.67 436.894 9615.95 436.912 9623.22 436.888 9631.08 437.023 9634.22 437.041
  9642.3 437.185 9662.65 437.341 9672.07 437.609 9682.26   437.2 9692.05  436.91
    9694  436.24    9730   436.1    9766  435.97    9802  435.85    9838  435.72
    9874  435.59    9910  435.47 9914.16 435.121  9916.9 435.032 9919.06 435.019
 9936.71 434.718 9939.43 434.714 9952.42 434.996 9962.38 434.996 9971.66 435.385
 9982.56 435.195 9986.53 435.41410001.97 435.26810012.93 435.304   10018  435.26
10022.75 435.464   10054  435.1510065.48 435.61210074.05 434.817 10082.7 434.817
 10089.2 435.56410096.52 435.55910101.33 435.58410105.51 435.534 10119.3 435.579
10124.05  435.6210128.43 435.397 10136.6 435.41310141.13  435.46   10162  435.08
   10198  434.84   10234  435.38   10270  435.29 10274.5  435.45   10306  435.58
   10342  435.7110343.75 437.28610349.97 437.34710353.78 437.19810359.38 437.112
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BR D #Mann= 5
  1015.6    .071    7566    .055  7649.7     .04 7857.61    .055    9463    .075
BC Design=,, 0 ,, 0 ,,,,,,
BC Use User HTab Curves=0
BC User HTab FreeFlow(D)= 0

Type RM Length L Ch R = 1 ,87522   ,3,3,3
BEGIN DESCRIPTION:
87522
H&B Trail added to Staion 5060 to 5074
END DESCRIPTION:
XS GIS Cut Line= 6
2454120.089167517033189.222747132451256.687085937032950.51850013
2449170.19257125 7032792.92695182447774.69765884 7032732.9585678
2446114.146846097032813.27960138 2440630.59999147033120.73640699
#Sta/Elev= 30
  1015.6   448.2    1096   424.9    1190   430.5    1191     451    4928     451
 4935.75   443.7  4977.1  433.28 5127.86  429.41 5296.67  434.94 5323.25   443.8
 5328.01     451    7566     451 7567.96   442.5 7627.83  441.69  7649.7  436.09
 7665.58  427.39    7726   408.4    7758   407.4    7798   412.4 7820.02  420.85
 7835.95  432.04 7857.61  436.33 7961.96  440.33    7962     451    9463     451
 9463.62  440.34 9939.43  434.71 10444.1  435.4810568.62  441.68   10570     450
#Mann= 3 ,0,0
  1015.6    .055       0  7649.7     .05       0 7857.61    .055       0
#XS Ineff= 8 ,-1
    1000    4935     460    4935    7550     439    7550    7658     452
    7899    7965     452    7965    9440   435.8    9440  9783.1     460
  9783.1 10255.6   435.8 10255.6   10575     460
Permanent Ineff=
       F       F       F       F       F       F       F       F
Bank Sta=7649.7,7857.61
XS Rating Curve= 0 ,0
Exp/Cntr=0.5,0.3

Type RM Length L Ch R = 1 ,87519   ,19,19,22
BEGIN DESCRIPTION:
Upstream of Cotton Belt Regional Rail
H&B Trail added to Staion 5060 to 5074
END DESCRIPTION:
XS GIS Cut Line= 6
  2454132.5263497033186.369790082451253.680951287032946.33074022
2449167.53497759 7032788.79661832447772.113828587032729.09369979
2446111.757705277032809.290540592440627.044655917033116.31562477
#Sta/Elev= 30
  1015.6   448.2    1096   424.9    1190   430.5    1191     451    4928     451
 4935.75   443.7  4977.9  433.37 5127.86  429.41 5296.56  434.91 5323.25   443.8
  5327.5  450.42    7566     451 7567.96   442.5 7627.83  441.69  7649.7  436.09
 7665.58   427.4    7726   408.4    7758   407.4    7798   412.4 7820.02  420.85
 7835.95  432.04 7857.61  436.33 7961.96  440.33    7962     451    9463     451
 9463.62  440.34 9939.43  434.71 10444.1  435.4810568.62  441.68   10570     450
#Mann= 3 ,0,0
  1015.6    .055       0  7649.7     .05       0 7857.61    .055       0
#XS Ineff= 9 ,-1
    1000 4933.66     456 4933.66    7550     439    7550 7659.66     452
    7892    7965     452    7965    9440   435.8    9440    9522     452
    9522  9793.4     451 10220.4   10530     451   10530   10575     452
Permanent Ineff=
       F       F       F       F       F       T       T       T       T
Bank Sta=7649.7,7857.61
XS Rating Curve= 0 ,0
Exp/Cntr=0.5,0.3