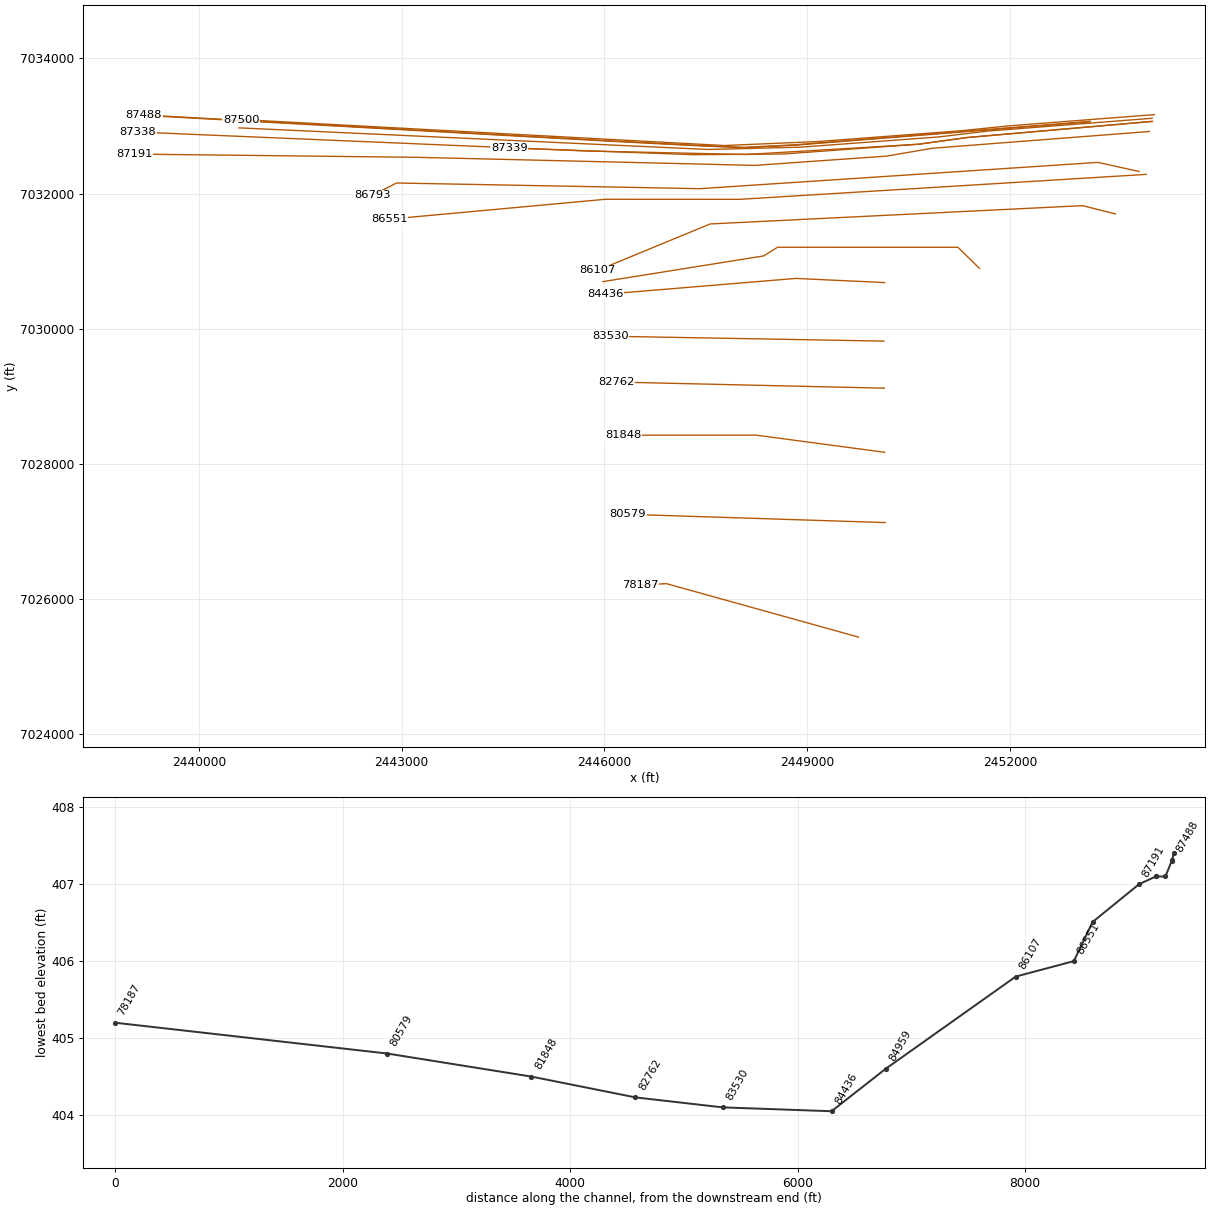
HEC-RAS study CDC_Consolidated_Model.prj: Upper Trinity CDC Consolidated Model

--- CDC_Consolidated_Model.g12 (geometry) --- (continued)

Type RM Length L Ch R = 3 ,87510   ,,,
BEGIN DESCRIPTION:
Cotton Belt Regional Rail
END DESCRIPTION:
Bridge Culvert--1,0,-1,-1, 0
Deck Dist Width WeirC Skew NumUp NumDn MinLoCord MaxHiCord MaxSubmerge Is_Ogee
2.5,14,2.6,0, 63, 63, , , 0.95, 0, ,,,
    4927 4931.49  4931.5  4967.5  5007.5  5047.5  5087.5  5127.5  5167.5  5207.5
  5216.5  5241.5  5247.5    5250  5287.5  5327.5 5327.51    7562 7562.01    7637
    7656    7662    7705    7712    7754    7762    7803    7812    7847    7852
    7901    7909    7963 7963.01    9462 9462.01    9514    9556    9605    9640
    9655    9705  9715.8    9755    9805    9855    9905    9910    9934    9976
   10018   10060   10102   10144   10186   10228   10270   10354   10438   10522
   10533   1057510575.01
  451.68  451.68  451.68 451.698 451.718 451.738 451.758 451.778 451.798 451.818
  451.82  451.83  451.83  451.83  451.82  451.78  451.78  451.96  451.96  451.71
  451.74  451.74 451.766  451.77 451.745  451.74 451.683  451.67   451.6 451.548
  451.46  451.44 451.159 451.159 451.545 451.795 453.336  453.47  453.59 453.646
  453.67   453.7   453.7  453.69  453.63  453.53  453.38  453.36 453.267 453.118
 452.968 452.819 452.669 452.519  452.37  452.22 452.071 451.771 451.472  451.17
  451.13     451     451
          446.21 445.763 445.781 445.801 445.821 445.841 445.861 445.881 445.901
 445.903 445.913 445.913 445.913 445.903 445.863                 444.957 445.457
 445.823 445.823 445.849 445.853 445.828 445.823 445.766 445.753 445.683 445.631
 445.543 445.492 444.992                         447.419 447.553 447.673 447.729
 447.753 447.783 447.783 447.773 447.713 447.613 447.463 447.443  447.35 447.201
 447.051 446.902 446.752 446.602 446.453 446.303 446.154 445.854 445.555  445.26
  445.22  445.09
    4927 4931.49  4931.5  4967.5  5007.5  5047.5  5087.5  5127.5  5167.5  5207.5
  5216.5  5241.5  5247.5    5250  5287.5  5327.5 5327.51    7562 7562.01    7637
    7656    7662    7705    7712    7754    7762    7803    7812    7847    7852
    7901    7907    7963 7963.01    9462 9462.01    9514    9556    9605    9640
    9655    9705  9715.8    9755    9805    9855    9905    9910    9934    9976
   10018   10060   10102   10144   10186   10228   10270   10354   10438   10522
   10533   1057510575.01
  451.68  451.68  451.68 451.698 451.718 451.738 451.758 451.778 451.798 451.818
  451.82  451.83  451.83  451.83  451.82  451.78  451.78  451.96  451.96  451.71
  451.74  451.74 451.766  451.77 451.745  451.74 451.683  451.67   451.6 451.548
  451.46  451.44 451.159 451.159 451.545 451.795 453.336  453.47  453.59 453.646
  453.67   453.7   453.7  453.69  453.63  453.53  453.38  453.36 453.267 453.118
 452.968 452.819 452.669 452.519  452.37  452.22 452.071 451.771 451.472  451.17
  451.13     451     451
          446.21 445.763 445.781 445.801 445.821 445.841 445.861 445.881 445.901
 445.903 445.913 445.913 445.913 445.903 445.863                 444.957 445.457
 445.823 445.823 445.849 445.853 445.828 445.823 445.766 445.753 445.683 445.631
 445.543 445.492 444.992                         447.419 447.553 447.673 447.729
 447.753 447.783 447.783 447.773 447.713 447.613 447.463 447.443  447.35 447.201
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Pier Skew, UpSta & Num, DnSta & Num=  ,4967.5, 6 ,4967.5, 6 , 5 , 5 , 0 ,,
       2       2   1.167   1.167       3       3
     420 437.719 437.719 442.719 442.719     447
       2       2   1.167   1.167       3       3
     420 437.719 437.719 442.719 442.719     447
Pier Skew, UpSta & Num, DnSta & Num=  ,5007.5, 6 ,5007.5, 6 , 5 , 5 , 0 ,,
       2       2   1.167   1.167       3       3
     420 434.739 434.739 442.739 442.739     447
       2       2   1.167   1.167       3       3
     420 434.739 434.739 442.739 442.739     447
Pier Skew, UpSta & Num, DnSta & Num=  ,5047.5, 6 ,5047.5, 6 , 5 , 5 , 0 ,,
       2       2   1.167   1.167       3       3
     420  431.97  431.97 442.759 442.759     447
       2       2   1.167   1.167       3       3
     420  431.97  431.97 442.759 442.759     447
Pier Skew, UpSta & Num, DnSta & Num=  ,5087.5, 6 ,5087.5, 6 , 5 , 5 , 0 ,,
       2       2   1.167   1.167       3       3
     420  431.58  431.58 442.779 442.779     447
       2       2   1.167   1.167       3       3
     420  431.58  431.58 442.779 442.779     447
Pier Skew, UpSta & Num, DnSta & Num=  ,5127.5, 6 ,5127.5, 6 , 5 , 5 , 0 ,,
       2       2   1.167   1.167       3       3
     420  430.75  430.75 442.799 442.799     447
       2       2   1.167   1.167       3       3
     420  430.75  430.75 442.799 442.799     447
Pier Skew, UpSta & Num, DnSta & Num=  ,5167.5, 6 ,5167.5, 6 , 5 , 5 , 0 ,,
       2       2   1.167   1.167       3       3
     420  432.36  432.36 442.819 442.819     447
       2       2   1.167   1.167       3       3
     420  432.36  432.36 442.819 442.819     447
Pier Skew, UpSta & Num, DnSta & Num=  ,5207.5, 6 ,5207.5, 6 , 5 , 5 , 0 ,,
       2       2   1.167   1.167       3       3
     420  432.84  432.84 442.839 442.839     447
       2       2   1.167   1.167       3       3
     420  432.84  432.84 442.839 442.839     447
Pier Skew, UpSta & Num, DnSta & Num=  ,5247.5, 6 ,5247.5, 6 , 5 , 5 , 0 ,,
       2       2   1.167   1.167       3       3
     420 434.851 434.851 442.851 442.851     447
       2       2   1.167   1.167       3       3
     420 434.851 434.851 442.851 442.851     447
Pier Skew, UpSta & Num, DnSta & Num=  ,5287.5, 6 ,5287.5, 6 , 5 , 5 , 0 ,,
       2       2   1.167   1.167       3       3
     420 435.841 435.841 442.841 442.841     447
       2       2   1.167   1.167       3       3
     420 435.841 435.841 442.841 442.841     447
Pier Skew, UpSta & Num, DnSta & Num=  ,7705, 4 ,7705, 4 , 3 , 3 , 0 ,,
       4       4     4.5     4.5
     420 442.787 442.787     450
       4       4     4.5     4.5
     420 442.787 442.787     450
Pier Skew, UpSta & Num, DnSta & Num=  ,7754, 4 ,7754, 4 , 3 , 3 , 0 ,,
       4       4     4.5     4.5
     420 442.766 442.766     450
       4       4     4.5     4.5
     420 442.766 442.766     450
Pier Skew, UpSta & Num, DnSta & Num=  ,7803, 4 ,7803, 4 , 3 , 3 , 0 ,,
       4       4     4.5     4.5
     420 442.704 442.704     450
       4       4     4.5     4.5
     420 442.704 442.704     450
Pier Skew, UpSta & Num, DnSta & Num=  ,7852, 4 ,7852, 4 , 3 , 3 , 0 ,,
       4       4     4.5     4.5
     420 442.569 442.569     450
       4       4     4.5     4.5
     420 442.569 442.569     450
Pier Skew, UpSta & Num, DnSta & Num=  ,9556, 6 ,9556, 6 , 5 , 5 , 0 ,,
       2       2   1.167   1.167       3       3
     420  440.62  440.62 444.491 444.491 446.849
       2       2   1.167   1.167       3       3
     420  440.62  440.62 444.491 444.491 446.849
Pier Skew, UpSta & Num, DnSta & Num=  ,9598, 6 ,9598, 6 , 5 , 5 , 0 ,,
       2       2   1.167   1.167       3       3
     420  438.67  438.67 444.594 444.594     447
       2       2   1.167   1.167       3       3
     420  438.67  438.67 444.594 444.594     447
Pier Skew, UpSta & Num, DnSta & Num=  ,9640, 6 ,9640, 6 , 5 , 5 , 0 ,,
       2       2   1.167   1.167       3       3
     420  437.73  437.73 444.667 444.667     447
       2       2   1.167   1.167       3       3
     420  437.73  437.73 444.667 444.667     447
Pier Skew, UpSta & Num, DnSta & Num=  ,9682, 6 ,9682, 6 , 5 , 5 , 0 ,,
       2       2   1.167   1.167       3       3
     420  438.78  438.78 444.711 444.711     447
       2       2   1.167   1.167       3       3
     420  438.78  438.78 444.711 444.711     447
Pier Skew, UpSta & Num, DnSta & Num=  ,9724, 6 ,9724, 6 , 5 , 5 , 0 ,,
       2       2   1.167   1.167       3       3
     420  438.89  438.89 444.721 444.721     447
       2       2   1.167   1.167       3       3
     420  438.89  438.89 444.721 444.721     447
Pier Skew, UpSta & Num, DnSta & Num=  ,9766, 6 ,9766, 6 , 5 , 5 , 0 ,,
       2       2   1.167   1.167       3       3
     420  438.94  438.94 444.698 444.698     447
       2       2   1.167   1.167       3       3
     420  438.94  438.94 444.698 444.698     447
Pier Skew, UpSta & Num, DnSta & Num=  ,9808, 6 ,9808, 6 , 5 , 5 , 0 ,,
       2       2   1.167   1.167       3       3
     420  436.99  436.99 444.641 444.641     447
       2       2   1.167   1.167       3       3
     420  436.99  436.99 444.641 444.641     447
Pier Skew, UpSta & Num, DnSta & Num=  ,9850, 6 ,9850, 6 , 5 , 5 , 0 ,,
       2       2   1.167   1.167       3       3
     420  437.05  437.05 444.561 444.561     447
       2       2   1.167   1.167       3       3
     420  437.05  437.05 444.561 444.561     447
Pier Skew, UpSta & Num, DnSta & Num=  ,9892, 6 ,9892, 6 , 5 , 5 , 0 ,,
       2       2   1.167   1.167       3       3
     420   437.1   437.1 444.441 444.441     447
       2       2   1.167   1.167       3       3
     420   437.1   437.1 444.441 444.441     447
Pier Skew, UpSta & Num, DnSta & Num=  ,9934, 6 ,9934, 6 , 5 , 5 , 0 ,,
       2       2   1.167   1.167       3       3
     420  436.29  436.29 444.288 444.288     447
       2       2   1.167   1.167       3       3
     420  436.29  436.29 444.288 444.288     447
Pier Skew, UpSta & Num, DnSta & Num=  ,9976, 6 ,9976, 6 , 5 , 5 , 0 ,,
       2       2   1.167   1.167       3       3
     420  436.64  436.64 444.138 444.138     447
       2       2   1.167   1.167       3       3
     420  436.64  436.64 444.138 444.138     447
Pier Skew, UpSta & Num, DnSta & Num=  ,10018, 6 ,10018, 6 , 5 , 5 , 0 ,,
       2       2   1.167   1.167       3       3
     420  436.49  436.49 443.989 443.989     447
       2       2   1.167   1.167       3       3
     420  436.49  436.49 443.989 443.989     447
Pier Skew, UpSta & Num, DnSta & Num=  ,10060, 6 ,10060, 6 , 5 , 5 , 0 ,,
       2       2   1.167   1.167       3       3
     420  436.84  436.84 443.839 443.839     447
       2       2   1.167   1.167       3       3
     420  436.84  436.84 443.839 443.839     447
Pier Skew, UpSta & Num, DnSta & Num=  ,10102, 6 ,10102, 6 , 5 , 5 , 0 ,,
       2       2   1.167   1.167       3       3
     420  436.09  436.09  443.69  443.69     447
       2       2   1.167   1.167       3       3
     420  436.09  436.09  443.69  443.69     447
Pier Skew, UpSta & Num, DnSta & Num=  ,10144, 6 ,10144, 6 , 5 , 5 , 0 ,,
       2       2   1.167   1.167       3       3
     420  436.04  436.04  443.54  443.54     447
       2       2   1.167   1.167       3       3
     420  436.04  436.04  443.54  443.54     447
Pier Skew, UpSta & Num, DnSta & Num=  ,10186, 6 ,10186, 6 , 5 , 5 , 0 ,,
       2       2   1.167   1.167       3       3
     420  436.89  436.89  443.39  443.39     447
       2       2   1.167   1.167       3       3
     420  436.89  436.89  443.39  443.39     447
Pier Skew, UpSta & Num, DnSta & Num=  ,10228, 6 ,10228, 6 , 5 , 5 , 0 ,,
       2       2   1.167   1.167       3       3
     420  436.81  436.81 443.241 443.241     447
       2       2   1.167   1.167       3       3
     420  436.81  436.81 443.241 443.241     447
Pier Skew, UpSta & Num, DnSta & Num=  ,10270, 6 ,10270, 6 , 5 , 5 , 0 ,,
       2       2   1.167   1.167       3       3
     420  437.73  437.73 443.091 443.091     447
       2       2   1.167   1.167       3       3
     420  437.73  437.73 443.091 443.091     447
Pier Skew, UpSta & Num, DnSta & Num=  ,10312, 6 ,10312, 6 , 5 , 5 , 0 ,,
       2       2   1.167   1.167       3       3
     420  438.66  438.66 442.942 442.942     447
       2       2   1.167   1.167       3       3
     420  438.66  438.66 442.942 442.942     447
Pier Skew, UpSta & Num, DnSta & Num=  ,10352, 6 ,10352, 6 , 5 , 5 , 0 ,,
       2       2   1.167   1.167       3       3
     420  438.58  438.58 442.792 442.792     447
       2       2   1.167   1.167       3       3
     420  438.58  438.58 442.792 442.792     447
Pier Skew, UpSta & Num, DnSta & Num=  ,10396, 6 ,10396, 6 , 5 , 5 , 0 ,,
       2       2   1.167   1.167       3       3
     420   437.5   437.5 442.642 442.642     447
       2       2   1.167   1.167       3       3
     420   437.5   437.5 442.642 442.642     447
Pier Skew, UpSta & Num, DnSta & Num=  ,10438, 6 ,10438, 6 , 5 , 5 , 0 ,,
       2       2   1.167   1.167       3       3
     420  437.35  437.35 442.493 442.493     447
       2       2   1.167   1.167       3       3
     420  437.35  437.35 442.493 442.493     447
Pier Skew, UpSta & Num, DnSta & Num=  ,10480, 6 ,10480, 6 , 5 , 5 , 0 ,,
       2       2   1.167   1.167       3       3
     420  438.27  438.27 442.343 442.343     447
       2       2   1.167   1.167       3       3
     420  438.27  438.27 442.343 442.343     447
Abutment Skew #Up #Dn= , 4 , 4
    4928 4935.75 4935.75 4959.75
     446     446   443.7   435.7
    4928 4935.75 4935.75 4959.75
     446     446   443.7   435.7
Abutment Skew #Up #Dn= , 4 , 4
 5293.25 5323.25 5323.25    5330
   433.8   443.8     446     446
 5293.25 5323.25 5323.25    5330
   433.8   443.8     446     446
Abutment Skew #Up #Dn= , 4 , 4
    7566    76127659.6667659.666
   446.3   446.3   446.3  428.34
    7566    76127659.6667659.666
   446.3   446.3   446.3  428.34
Abutment Skew #Up #Dn= , 4 , 4
 7874.837897.3337897.333    7963
  435.19  438.95  446.17  446.17
 7874.837897.3337897.333    7963
  435.19  438.95  446.17  446.17
Abutment Skew #Up #Dn= , 4 , 4
    9513 9515.49  9515.5  9545.5
   447.8   447.8   445.9   435.9
    9513 9515.49  9515.5  9545.5
   447.8   447.8   445.9   435.9
Abutment Skew #Up #Dn= , 4 , 4
 10502.5 10520.510520.51   10576
  437.75  443.75   445.5   445.5
 10502.5 10520.510520.51   10576
  437.75  443.75   445.5   445.5
BR Coef= 1 , 0 , 0 ,1.05, 0 ,,,0.8,-1,0.5,1,
WSPro=,,,, 1 ,,,, 0 ,,,, 0 ,,,,-1 ,-1 ,-1 , 0 , 0 , 0 , 0 , 0
BR U #Sta/Elev= 225
  1015.6   448.2    1016   445.7    1037   439.5  1054.5  437.17  1063.5  435.15
    1082   426.6    1096   424.9  1098.5   424.9  1107.5   424.9    1127   424.9
  1142.5   427.1  1151.5  427.29    1171   427.6    1190   430.5    1191   448.2
    1191     451    4928     451 4928.01   448.2 4928.87  447.32  4929.7  446.92
 4930.41   445.9 4930.69  444.93 4936.46  441.94 4938.02  441.24 4939.81  440.62
  4952.5   436.9  4955.5  436.84  4967.5   436.6  4968.3  436.57  4977.9  433.37
 4980.03  433.32  4990.1  433.04 5000.15  432.86  5002.3  432.82  5006.5   432.8
    5011   431.3  5039.5  430.96  5075.5  430.58  5111.5  430.22 5114.87  430.17
  5124.9  429.54 5127.86  429.41 5128.48  429.48  5138.6  430.48  5147.5  430.82
 5154.51  431.01 5168.85 431.222  5183.5  430.93 5186.18  431.24 5196.77  431.06
 5200.51  431.03 5216.28 432.214 5235.22 433.206  5241.2  433.52  5255.5  433.82
  5291.5  434.78  5303.6  435.07  5305.1  435.57 5322.03  441.53 5323.33     442
 5327.05  443.55 5327.42  446.37 5328.31  447.28  5328.5  450.42    7566     451
    7567     447 7567.96   442.5 7574.74  442.44 7581.58  442.26 7596.12  442.17
 7604.14  441.85  7606.9  442.03 7625.67  441.74 7627.83  441.69 7644.12  438.82
 7645.81   438.7 7646.54  438.15  7649.7  436.09 7665.58   427.4 7669.53  426.42
 7673.46  425.62 7675.42  424.95 7678.06  424.33 7682.06  423.45 7690.31  421.17
 7693.72  420.06 7695.73  419.49  7698.8  418.55 7703.82  417.16 7710.74  414.78
 7711.99  414.32 7712.87  414.07 7713.72  413.73    7720   411.2    7726   408.4
    7758   407.4    7787   409.3    7798   412.4 7801.02  413.77 7801.95  414.43
 7803.22  414.94 7810.84  419.31  7814.4  419.85 7820.02  420.85 7821.12  421.46
 7827.31  424.71 7829.31  425.79 7829.84   426.2 7835.95  432.04 7839.86  432.73
 7846.01  434.13 7857.61  436.33  7876.9  436.18 7886.24  436.81  7897.3   437.1
 7904.52  438.43 7910.18  438.97 7927.49  439.17 7935.01  440.18 7939.65  440.21
 7942.19  440.38 7958.75  440.39 7961.96  440.33    7962     451    9463     451
 9463.62  440.34 9476.81  440.07 9479.04   440.1 9490.07  440.33 9504.79  440.55
 9511.66  440.51 9528.17  439.93 9532.35  439.49  9543.7   438.9  9547.1  438.44
 9549.55  438.17 9557.94  437.67 9572.01  437.29 9579.77  437.29 9582.01  437.23
 9585.78  437.07 9592.73  436.93 9594.94  436.93 9609.67  436.89 9615.95  436.91
 9623.22  436.89 9631.08  437.02 9634.22  437.04  9642.3  437.19 9662.65  437.34
 9672.07  437.61 9682.26   437.2 9692.05  436.91    9694  436.23    9730   436.1
    9766  435.98    9802  435.85    9838  435.73    9874  435.61    9910  435.48
 9914.16  435.12  9916.9  435.03 9919.06  435.02 9936.71  434.72 9939.43  434.71
 9952.42     435 9962.38     435 9971.66 435.385    9982  435.68 9986.53 435.414
10001.97 435.26810012.93 435.304   10018  435.2410022.75  435.46   10054  435.15
10065.48  435.6110074.05 434.817 10082.7 434.817 10089.2  435.5610096.52  435.56
10101.33  435.5810105.51  435.53 10119.3  435.5810124.05  435.6210128.43   435.4
 10136.6  435.4110141.13  435.46   10162  435.08   10198  435.55   10234  435.99
   10270  435.46 10274.5  435.48   10306   435.6   10342  435.7210349.97  437.35
10353.78   437.210359.38  437.1110363.63  436.9810372.68   436.510383.86  436.39
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BR U #Mann= 6
  1015.6    .065    7566    .055  7649.7    .047 7857.61     .05 7961.96    .055
    9463     .06
BR D #Sta/Elev= 216
  1015.6   448.2    1016   445.7    1037   439.5  1054.5  437.17  1063.5  435.15
    1082   426.6    1096   424.9  1098.5   424.9  1107.5   424.9    1127   424.9
  1142.5   427.1  1151.5  427.29    1171   427.6    1190   430.5    1191   448.2
    1191     451    4928     451 4928.01   448.2 4928.87  447.32  4929.7  446.92
 4930.41   445.9 4930.69  444.93 4936.46  441.94 4938.02  441.24 4939.81  440.62
  4953.5  436.81  4955.5  436.77  4967.5  436.53 4969.42   436.5  4977.7  433.74
 4979.84  433.69 4989.85  433.43 4999.94  433.18  5002.1  433.13 5005.45  433.05
    5011 431.205  5039.5  430.92  5075.5  430.56  5111.5  430.29 5114.87  430.17
  5124.9  429.54 5127.86  429.41 5128.48  429.48  5138.6  430.48  5147.5  430.85
 5154.51  431.01 5168.85 431.222  5183.5  431.14 5186.18  431.24 5196.77  431.06
 5200.51  431.03 5216.28 432.214 5235.22 433.206  5241.2  433.53  5255.5  433.83
  5291.5  434.76 5303.18  435.03 5304.68  435.53 5322.03  441.53 5323.33     442
  5327.1  443.55  5327.2  446.37 5327.31  447.28  5327.5  450.42    7566     451
    7567     447 7567.96   442.5 7574.74  442.44 7581.58  442.26 7596.12  442.17
 7604.14  441.85  7606.9  442.03 7625.67  441.74 7627.83  441.69 7644.12  438.82
 7645.81   438.7 7646.54  438.15  7649.7  436.09 7665.58   427.4 7669.53  426.42
 7673.46  425.62 7675.42  424.95 7678.06  424.33 7682.06  423.45 7690.31  421.17
 7693.72  420.06 7695.73  419.49  7698.8  418.55 7703.82  417.16 7710.74  414.78
 7711.99  414.32 7712.87  414.07 7713.72  413.73    7720   411.2    7726   408.4
    7758   407.4    7787   409.3    7798   412.4 7801.02  413.77 7801.95  414.43
 7803.22  414.94 7810.84  419.31  7814.4  419.85 7820.02  420.85 7821.12  421.46
 7827.31  424.71 7829.31  425.79 7829.84   426.2 7835.95  432.04 7839.86  432.73
 7846.01  434.13 7857.61  436.33  7876.9  436.18 7886.24  436.81  7897.3   437.1
 7904.52  438.43 7910.18  438.97 7927.49  439.17 7935.01  440.18 7939.65  440.21
 7942.19  440.38 7958.75  440.39 7961.96  440.33    7962     451    9463     451
 9463.62  440.34 9476.81  440.07 9479.04   440.1 9490.07  440.33 9504.79  440.55
 9511.66  440.51 9528.17  439.93 9532.35  439.49  9543.7   438.9  9547.1  438.44
 9549.55  438.17 9557.94  437.67 9572.01  437.29 9579.77  437.29 9582.01  437.23
 9585.78  437.07 9592.73  436.93 9594.94  436.93 9609.67  436.89 9615.95  436.91
 9623.22  436.89 9631.08  437.02 9634.22  437.04  9642.3  437.19 9662.65  437.34
 9672.07  437.61 9682.26   437.2 9692.05  436.91    9694  436.22    9730   436.1
    9766  435.98    9802  435.86    9838  435.74    9874  435.62    9910  435.51
 9914.16  435.12  9916.9  435.03 9919.06  435.02 9936.71  434.72 9939.43  434.71
 9952.42     435 9962.38     435 9971.66  435.39 9982.56   435.2 9986.53  435.41
10001.97  435.2710012.93   435.3   10054  435.0310071.55  435.0510074.05  434.82
 10082.7  434.8210084.72  435.05   10090  435.06   10126  435.03   10162  435.15
   10198  435.27   10234  435.39   10270  435.51   10306  435.63   10342  435.75
10349.97  437.3510353.78   437.210359.38  437.1110363.63  436.9810372.68   436.5
10383.86  436.39 10394.9  435.9810408.99  435.63 10412.8  435.5110423.46  435.31
10433.91   435.4 10444.1  435.4810453.61  435.8110463.72  436.0510480.42  436.74
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BR D #Mann= 6
  1015.6    .065    7566    .055  7649.7    .047 7857.61     .05 7961.96    .055
    9463     .06
BC Design=,, 0 ,, 0 ,,,,,,
BC Use User HTab Curves=0
BC User HTab FreeFlow(D)= 0

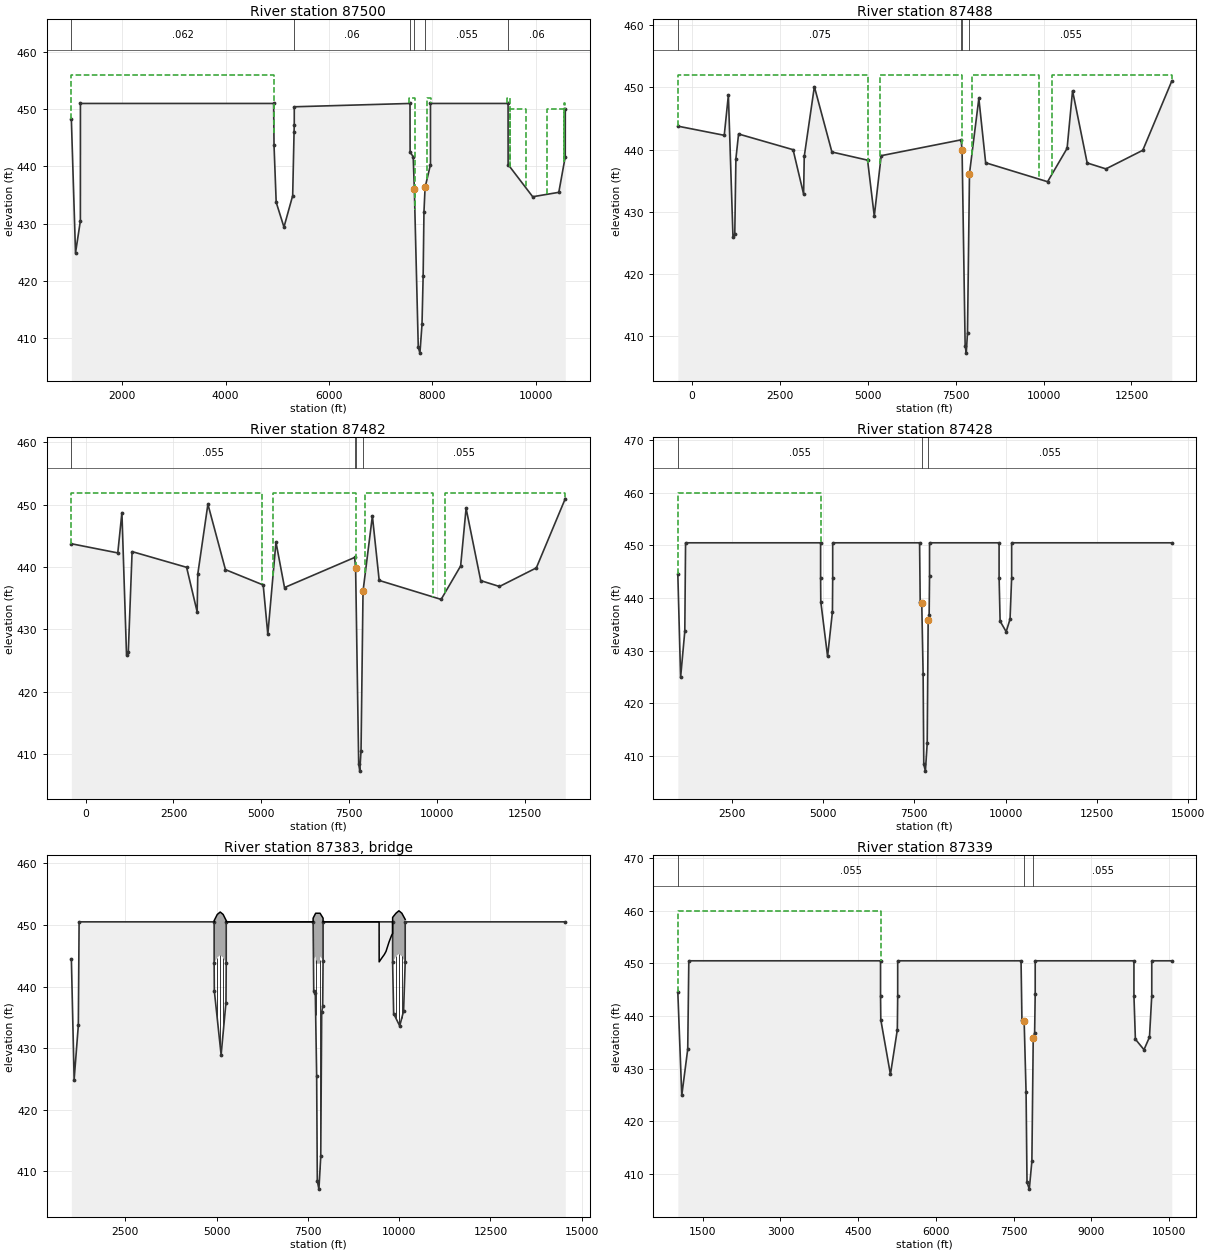
Type RM Length L Ch R = 1 ,87500   ,39,12,12
BEGIN DESCRIPTION:
Downstream of Cotton Belt Regional Rail
---------------------------------------------------------------------
CDC CAR102120-01 Cotton Belt Regional Rail
---------------------------------------------------------------------
CDC CAR 080723-1 Veloweb Hike and Bike Trail
Cross-section 87500 - 87541
-H&B Trail added to Staion 5060 to 5074
---------------------------------------------------------------------
END DESCRIPTION:
XS GIS Cut Line= 6
  2454133.9904257033167.426282472451992.096328237033001.88692711
2451255.352140167032927.402843032449168.739385317032769.83347242
2447772.004677537032710.076821462440625.933082287033094.29720436
#Sta/Elev= 30
  1015.6   448.2    1096   424.9    1190   430.5    1191     451    4928     451
 4935.75   443.7  4977.7  433.74 5127.86  429.41 5296.56   434.9 5323.26     446
 5327.31  447.28  5327.5  450.42    7566     451 7567.96   442.5 7627.83  441.69
  7649.7  436.09    7726   408.4    7758   407.4    7798   412.4 7820.02  420.85
 7835.95  432.04 7857.61  436.33 7961.96  440.33    7962     451    9463     451
 9463.62  440.34 9939.43  434.71 10444.1  435.4810568.62  441.68   10570     450
#Mann= 6 ,-1,0
  1015.6    .062       0 5323.26     .06       0    7566    .055       0
  7649.7     .05       0 7857.61    .055       0    9463     .06       0
#XS Ineff= 9 ,-1
    1000 4933.66     456 4933.66    7550     439    7550 7659.66     452
 7897.34    7965     452    7965    9440   435.8    9440  9503.4     452
  9503.4    9813     450   10212 10549.9     450 10549.9   10575     451
Permanent Ineff=
       F       F       F       F       F       T       T       T       T
Bank Sta=7649.7,7857.61
XS Rating Curve= 0 ,0
Exp/Cntr=0.5,0.3

Type RM Length L Ch R = 1 ,87488   ,44,6,6
XS GIS Cut Line= 6
  2453181.8816557033067.143992542448824.018516937032721.47703637
 2448060.12962777032683.282591922447442.795643067032709.73477653
2446110.127749477032778.333250432439188.095480447033162.13820554
#Sta/Elev= 30
    -405  443.76915.8301  442.29 1033.38  448.75 1164.13  426.01 1215.47  426.47
 1247.42  438.54 1323.15   442.5 2874.36  439.98 3173.99  432.84 3191.91  438.89
 3479.86   450.13978.979  439.614993.601   438.3 5184.62  429.32 5381.33  439.02
 7653.96  441.56 7682.52  439.94    7770  408.52    7801  407.32    7837  410.62
 7893.54  436.15  8159.7  448.21 8353.57  437.88 10115.5  434.8410670.89   440.2
10826.01  449.4411242.05  437.8511775.75   436.912824.51  439.8913648.95     451
#Mann= 4 ,-1,0
    -405    .075       0 7653.96    .055       0 7682.52     .05       0
 7893.54    .055       0
#XS Ineff= 4 ,-1
    -405  5010.7     452    5355    7680     452  7957.7  9865.4     452
 10232.713648.95     452
Permanent Ineff=
       T       T       T       T
Bank Sta=7682.52,7893.54
XS Rating Curve= 0 ,0
Exp/Cntr=0.5,0.3

Type RM Length L Ch R = 1 ,87482   ,36.5,54,28
XS GIS Cut Line= 6
  2453182.3537627033061.16259513 2448824.41280567032715.48925549
2448060.151057297032677.276168082447442.502490937032703.74183222
 2446109.80806337032772.341755792439187.764697747033156.14733058
#Sta/Elev= 30
    -405  443.74  915.83  442.27 1033.38  448.73 1164.13  425.99 1215.47  426.45
 1323.15  442.48 2874.36  439.96 3173.99  432.82 3191.91  438.87 3479.86  450.08
 3978.98  439.59 5053.47  437.13 5184.62  429.22  5416.5     444 5659.58  436.72
 7653.96  441.54 7682.52  439.92    7770   408.5    7801   407.3    7837   410.6
 7893.54  436.13  8159.7  448.19 8353.57  437.86 10115.5  434.8210670.89  440.18
10826.01  449.4211242.05  437.8311775.75  436.8912824.51  439.8713648.95  450.98
#Mann= 4 ,-1,0
    -405    .055       0 7653.96    .055       0 7682.52     .05       0
 7893.54    .055       0
#XS Ineff= 4 ,-1
    -405  5007.7   451.9  5330.9    7680   451.9  7957.7  9871.5   451.9
 10224.213648.95   451.9
Permanent Ineff=
       T       T       T       T
Bank Sta=7682.52,7893.54
XS Rating Curve= 0 ,0
Exp/Cntr=0.5,0.3

Type RM Length L Ch R = 1 ,87428   ,85,85,85
BEGIN DESCRIPTION:
This cross section corresponds to cross section 87428 of the non-georeferenced CDC model which was the source of this model.
END DESCRIPTION:
XS GIS Cut Line= 6
  2454099.7762167033113.246849212451670.286324357032924.21146613
2450948.477072427032837.734276882448898.740358267032685.89796638
2447533.458640017032651.919687882440595.786211237032971.39049108
#Sta/Elev= 30
    1020   444.5    1096   424.9    1211   433.7    1232   450.5    4931   450.5
    4931  443.78    4936   439.3    5122   428.9    5255   437.4    5262  443.78
    5262   450.5    7642   450.5    7659   439.3    7702     439    7739   425.5
    7757   408.4    7801   407.1    7851   412.4    7877   435.8    7904   436.8
    7915  444.18    7915   450.5    9820   450.5    9820   443.9    9848   435.6
   10014   433.6   10120     436   10164   443.9   10164   450.5   14550   450.5
#Mann= 3 ,0,0
    1020    .055       0    7702     .05       0    7877    .055       0
#XS Ineff= 3 ,-1
    1020    4931     460    4931    7702     439    7877   10550   435.8
Permanent Ineff=
       F       F       F
Bank Sta=7702,7877
XS Rating Curve= 0 ,0
Exp/Cntr=0.5,0.3

Type RM Length L Ch R = 3 ,87383   ,,,
BEGIN DESCRIPTION:
Belt Line Road
END DESCRIPTION:
Node Name=Belt Line Road
Bridge Culvert--1,0,-1,-1, 0
Deck Dist Width WeirC Skew NumUp NumDn MinLoCord MaxHiCord MaxSubmerge Is_Ogee
0.5,84,2.6,0, 38, 38, , , 0.95, 0, ,,,
    4931    4931  5015.8  5018.3  5095.8  5098.3  5175.8  5178.3    5262    5262
    5369    7520    7642    7642  7710.8  7713.3  7830.8  7833.3    7915    7915
    8024    9450    9451    9508    9593    9639    9720    9791    9820    9820
    9830  9910.8  9913.3  9990.8  9993.3 10070.8 10073.3   10164
   450.5   450.7  451.69  451.71  452.09  452.09  451.71  451.69   450.7   450.5
   450.5   450.5   450.5   451.1  451.89   451.9   451.9  451.89   451.1   450.5
   450.5   450.5     444   444.5   445.2   445.7   447.2   448.3   448.6   451.2
   451.3  451.89  451.91  452.29  452.29  451.91  451.89   450.9
   450.5  443.78  444.69  444.71  445.09  445.09  444.71  444.69  443.78   450.5
   450.5   450.5   450.5  444.29  444.89   443.7   443.7  444.89  444.29   450.5
   450.5   450.5     444   444.5   445.2   445.7   447.2   448.3   448.6   443.9
     444  444.89  444.91  445.29  445.29  444.91  444.89   443.9
    4931    4931  5015.8  5018.3  5095.8  5098.3  5175.8  5178.3    5262    5262
    5369    7520    7642    7642  7710.8  7713.3  7830.8  7833.3    7915    7915
    8024    9450    9451    9508    9593    9639    9720    9791    9820    9820
    9830  9910.8  9913.3  9990.8  9993.3 10070.8 10073.3   10164
   450.5   450.7  451.69  451.71  452.09  452.09  451.71  451.69   450.7   450.5
   450.5   450.5   450.5   451.1  451.89   451.9   451.9  451.89   451.1   450.5
   450.5   450.5     444   444.5   445.2   445.7   447.2   448.3   448.6   451.2
   451.3  451.89  451.91  452.29  452.29  451.91  451.89   450.9
   450.5  443.78  444.69  444.71  445.09  445.09  444.71  444.69  443.78   450.5
   450.5   450.5   450.5  444.29  444.89   443.7   443.7  444.89  444.29   450.5
   450.5   450.5     444   444.5   445.2   445.7   447.2   448.3   448.6   443.9
     444  444.89  444.91  445.29  445.29  444.91  444.89   443.9
Pier Skew, UpSta & Num, DnSta & Num=  ,5017.05, 2 ,5017.05, 2 , 0 , 0 , 0 ,,
     2.5     2.5
     430     450
     2.5     2.5
     430     450
Pier Skew, UpSta & Num, DnSta & Num=  ,5097.05, 2 ,5097.05, 2 , 0 , 0 , 0 ,,
     2.5     2.5
     430     450
     2.5     2.5
     430     450
Pier Skew, UpSta & Num, DnSta & Num=  ,5177.05, 2 ,5177.05, 2 , 0 , 0 , 0 ,,
     2.5     2.5
     430     450
     2.5     2.5
     430     450
Pier Skew, UpSta & Num, DnSta & Num=  ,7712.05, 2 ,7712.05, 2 , 0 , 0 , 0 ,,
     2.5     2.5
     410     450
     2.5     2.5
     410     450
Pier Skew, UpSta & Num, DnSta & Num=  ,7832.05, 2 ,7832.05, 2 , 0 , 0 , 0 ,,
     2.5     2.5
     410     450
     2.5     2.5
     410     450
Pier Skew, UpSta & Num, DnSta & Num=  ,9912.05, 2 ,9912.05, 2 , 0 , 0 , 0 ,,
     2.5     2.5
     410     450
     2.5     2.5
     410     450
Pier Skew, UpSta & Num, DnSta & Num=  ,9992.05, 2 ,9992.05, 2 , 0 , 0 , 0 ,,
     2.5     2.5
     410     450
     2.5     2.5
     410     450
Pier Skew, UpSta & Num, DnSta & Num=  ,10072.05, 2 ,10072.05, 2 , 0 , 0 , 0 ,,
     2.5     2.5
     410     450
     2.5     2.5
     410     450
BR Coef= 1 , 0 , 0 ,1.05, 0 ,,,0.8,-1,0.5,1,
WSPro=,,,, 1 ,,,, 0 ,,,, 0 ,,,,-1 ,-1 ,-1 , 0 , 0 , 0 , 0 , 0
BC Design=,, 0 ,, 0 ,,,,,,
BC Use User HTab Curves=0
BC User HTab FreeFlow(D)= 0

Type RM Length L Ch R = 1 ,87339   ,1,1,1
BEGIN DESCRIPTION:
This cross section corresponds to cross section 87339 of the non-georeferenced CDC model which was the source of this model.
END DESCRIPTION:
XS GIS Cut Line= 6
2454096.437968087033066.68066938 2451360.00446467032828.53350788
2450655.638419247032730.874910552448644.077809847032584.72428422
2447305.792756777032575.173778382444591.557699687032674.81465521
#Sta/Elev= 30
    1020   444.5    1096   424.9    1211   433.7    1232   450.5    4931   450.5
    4931  443.78    4936   439.3    5122   428.9    5255   437.4    5262  443.78
    5262   450.5    7642   450.5    7659   439.3    7702     439    7739   425.5
    7757   408.4    7801   407.1    7851   412.4    7877   435.8    7904   436.8
    7915  444.18    7915   450.5    9820   450.5    9820   443.9    9848   435.6
   10014   433.6   10120     436   10164   443.9   10164   450.5   10550   450.5
#Mann= 3 ,0,0
    1020    .055       0    7702     .05       0    7877    .055       0
#XS Ineff= 3 ,-1
    1020    4931     460    4931    7702     439    7877   10550   435.8
Permanent Ineff=
       F       F       F
Bank Sta=7702,7877
XS Rating Curve= 0 ,0
Exp/Cntr=0.5,0.3

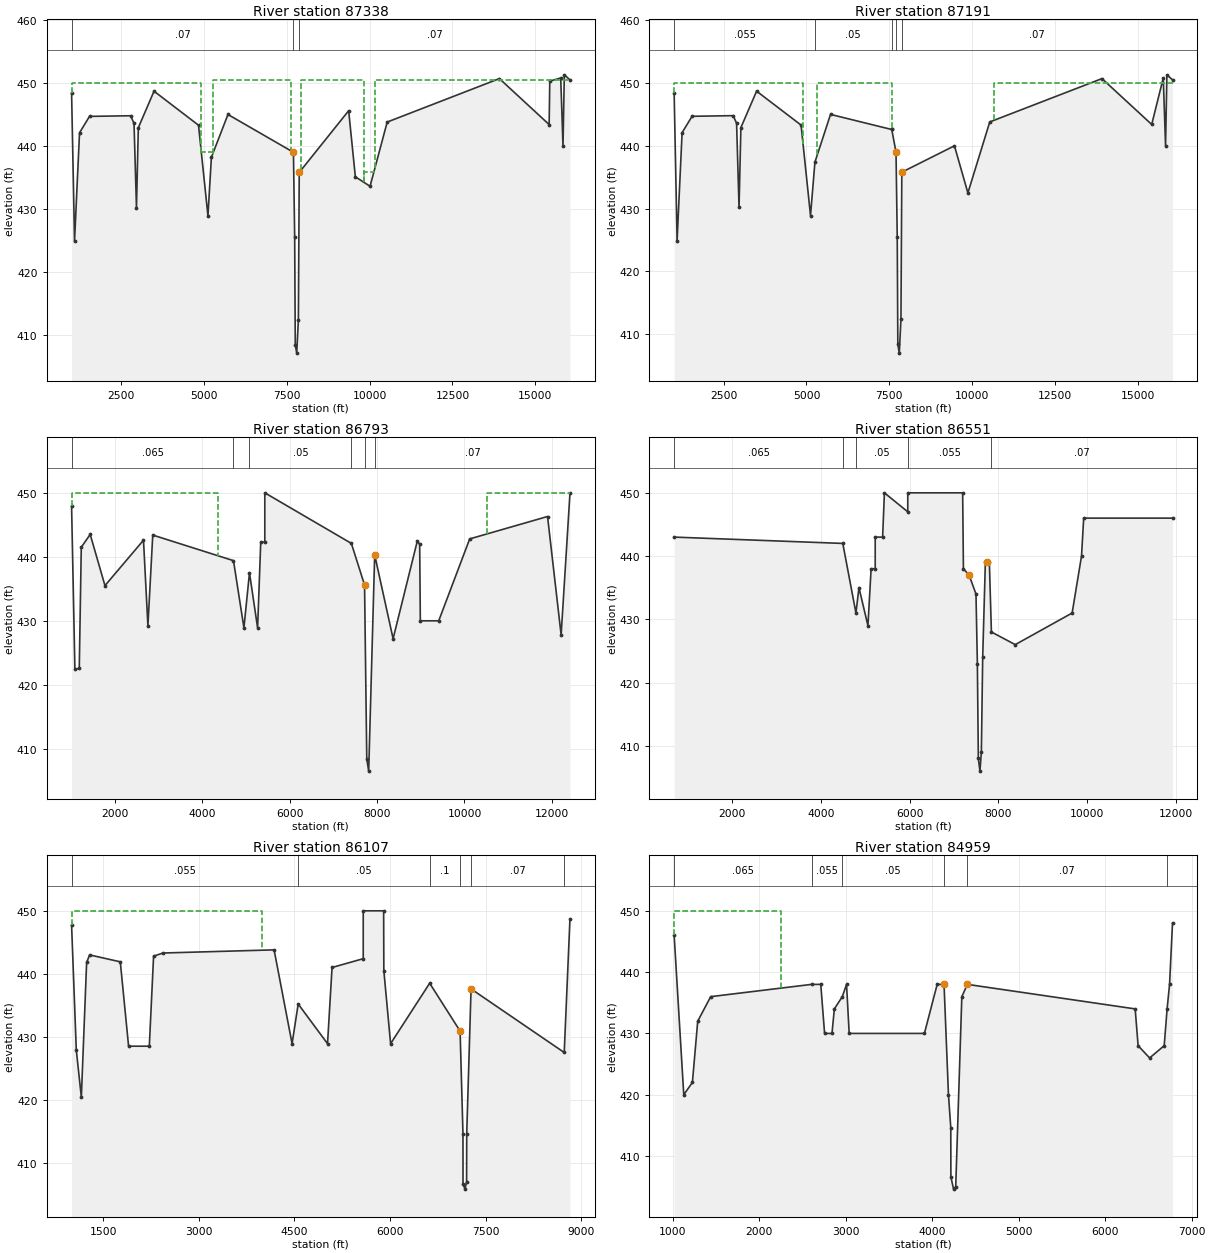
Type RM Length L Ch R = 1 ,87338   ,99,146,258
BEGIN DESCRIPTION:
This cross section corresponds to cross section 87338 of the non-georeferenced CDC model which was the source of this model.
END DESCRIPTION:
XS GIS Cut Line= 6
2454105.186966337033067.315182552451356.589773277032827.46494047
2450652.393018937032729.678718722448100.939460437032577.65474455
2445703.858952767032630.561462882439097.106090167032909.77547139
#Sta/Elev= 30
    1007   448.4    1096   424.9    1247   442.1    1548   444.7    2787   444.8
    2891   443.6    2965   430.2    3021   442.9    3495   448.7    4837   443.3
    5122   428.9    5226   438.2    5726     445    7702     439    7739   425.5
    7757   408.4    7801   407.1    7851   412.4    7877   435.8    9368   445.6
    9570   435.1   10014   433.6   10531   443.8   13917   450.7   15418   443.4
   15437   450.3   15767   450.8   15836     440   15876   451.3   16046   450.5
#Mann= 3 ,0,0
    1007     .07       0    7702    .055       0    7877     .07       0
#XS Ineff= 6 ,-1
    1007    4925     450    4925    5270     439    5270    7620   450.5
    7924    9820   450.5    9820   10164   435.8   10164   16046   450.5
Permanent Ineff=
       F       F       T       T       F       T
Bank Sta=7702,7877
XS Rating Curve= 0 ,0
Exp/Cntr=0.3,0.1

Type RM Length L Ch R = 1 ,87191   ,308,408,390
BEGIN DESCRIPTION:
This cross section corresponds to cross section 87191 of the non-georeferenced CDC model which was the source of this model.
---------------------------------------------------------------------
UPSTREAM END OF CDC COP082301-1 DEVELOPMENT AT 1550 E. BELT LINE ROAD.
CROSS-SECTION 86107 - 87191
---------------------------------------------------------------------
END DESCRIPTION:
XS GIS Cut Line= 6
2454060.747750767032917.900455132450850.105878087032670.02595088
2450173.568845337032553.538979132448224.031077747032416.58813755
2443228.375058597032535.863161462439047.861109917032583.44180647
#Sta/Elev= 30
    1007   448.4    1096   424.9    1247   442.1    1548   444.7    2787   444.8
    2891   443.6    2965   430.2    3021   442.9    3495   448.7    4837   443.3
    5122   428.9    5255   437.4    5726     445    7570   442.6    7570   442.7
    7702     439    7739   425.5    7757   408.4    7801     407    7851   412.4
    7877   435.8    9465     440    9871   432.5   10531   443.8   13917   450.7
   15418   443.4   15767   450.8   15836     440   15876   451.3   16046   450.5
#Mann= 5 ,-1,0
    1007    .055       0    5255     .05       0    7570      .1       0
    7702    .055       0    7877     .07       0
#XS Ineff= 5 ,-1
    1007    4900     450    4900    5330   435.8    5330    7570     450
    7877   10650   435.8   10650   16046     450
Permanent Ineff=
       F       F       T       F       F
Bank Sta=7702,7877
XS Rating Curve= 0 ,0
Exp/Cntr=0.3,0.1

Type RM Length L Ch R = 1 ,86793   ,140,166,166
BEGIN DESCRIPTION:
This cross section corresponds to cross section 86793 of the non-georeferenced CDC model which was the source of this model.
XS 86799 to 87207 retored to 1991 topo to remove project COP 082310-01
END DESCRIPTION:
XS GIS Cut Line= 5
2453906.375684177032326.389827132453299.809968177032460.72912538
2447409.058954427032071.975965892442924.895022517032155.90001063
 2442570.11620457031975.03324638
#Sta/Elev= 30
    1007   447.9    1083   422.4    1183   422.6    1229   441.5    1433   443.5
    1771   435.5    2653   442.6    2754   429.2    2865   443.4    4713   439.4
    4952   428.9    5079   437.5    5265   428.9    5337   442.3    5430   442.3
    5430     450    7411   442.1    7713   435.6    7764   408.4    7808  406.51
    7945   440.3  8366.6   427.2  8918.4   442.4  8974.8     442    8990     430
    9411     430   10120   442.8   11902   446.3   12213   427.8   12415   449.9
#Mann= 6 ,-1,0
    1007    .065       0    4713    .055       0    5079     .05       0
    7411      .1       0    7713    .055       0    7945     .07       0
#XS Ineff= 4 ,-1
    1007    4362     450    4362    7713   435.6    7945   10520   435.6
   10520   12415     450
Permanent Ineff=
       F       F       F       T
Bank Sta=7713,7945
XS Rating Curve= 0 ,0
Exp/Cntr=0.3,0.1

Type RM Length L Ch R = 1 ,86551   ,431,510,1114
BEGIN DESCRIPTION:
This cross section corresponds to cross section 86551 of the non-georeferenced CDC model which was the source of this model.
END DESCRIPTION:
XS GIS Cut Line= 6
2454012.779178877032283.428838422450357.663293427032058.99206796
2448004.311044757031914.488091892446014.163122187031915.05370755
 2444808.19440557031804.091002972442816.607098677031620.84253979
#Sta/Elev= 30
     700     443    4497     442    4793     431    4861     435    5063     429
    5135     438    5227     438    5227     443    5394     443    5434     450
    5960     447    5960     450    7196     450    7213     438    7340     437
    7496     434    7527     423    7549     408    7585     406    7617     409
    7647     424    7707     439    7737     439    7797     439    7843     428
    8380     426    9661     431    9872     440    9921     446   11921     446
#Mann= 5 ,-1,0
     700    .065       0    4497    .055       0    4793     .05       0
    5960    .055       0    7843     .07       0
Bank Sta=7340,7737
XS Rating Curve= 0 ,0
Exp/Cntr=0.3,0.1

Type RM Length L Ch R = 1 ,86107   ,479,1145,299
BEGIN DESCRIPTION:
This cross section corresponds to cross section 86107 of the non-georeferenced CDC model which was the source of this model.
---------------------------------------------------------------------
DOWNSTREAM END OF CDC COP082301-1 DEVELOPMENT AT 1550 E. BELT LINE ROAD.
CROSS-SECTION 86107 - 87191
---------------------------------------------------------------------
END DESCRIPTION:
XS GIS Cut Line= 4
2453555.21398494 7031698.60040032453070.766134927031820.77404046
2447563.644931357031550.248990972445897.360862347030862.53908031
#Sta/Elev= 30
    1006   447.7    1080   427.9    1159   420.4    1242   441.8    1289     443
    1770   441.9    1900   428.5    2225   428.5    2292   442.8    2440   443.3
    4182   443.8    4464   428.9    4560   435.2    5020   428.9    5091     441
    5580   442.4    5580     450    5900     450    5903   440.5    6009   428.9
    6622   438.5    7099   430.9    7144   414.6    7145   406.6    7176   405.8
    7201     407    7203   414.6    7271   437.6    8732   427.5    8822   448.7
#Mann= 6 ,-1,0
    1006    .055       0    4560     .05       0    6622      .1       0
    7099     .05       0    7271     .07       0    8732     .03       0
#XS Ineff= 3 ,-1
    1006    4000     450    4000    7099   430.9    7271    8822   437.6
Permanent Ineff=
       F       F       F
Bank Sta=7099,7271
XS Rating Curve= 0 ,0
Exp/Cntr=0.3,0.1

Type RM Length L Ch R = 1 ,84959   ,512,475,221
BEGIN DESCRIPTION:
This cross section corresponds to cross section 84959 of the non-georeferenced CDC model which was the source of this model.
END DESCRIPTION:
XS GIS Cut Line= 5
 2451546.38565357030892.684361222451228.805908087031204.77297588
  2448559.7479267031205.354995712448354.105948847031077.09901863
  2445978.1664757030697.18212755
#Sta/Elev= 30
  1016.1     446  1127.3     420  1227.1     422  1288.7     432  1438.9     436
  2605.3     438  2711.4     438  2755.8     430  2841.1     430  2868.6     434
  2960.7     436  3009.5     438    3040     430    3910     430  4057.5     438
  4136.9     438  4188.1     420    4215   414.6    4216   406.6    4247   404.6
    4272     405  4342.6     436  4407.1     438  6347.1     434    6381     428
  6514.3     426  6682.7     428  6716.3     434  6744.6     438  6778.9     448
#Mann= 6 ,-1,0
  1016.1    .065       0  2605.3    .055       0  2960.7     .05       0
  4136.9    .055       0  4407.1     .07       0  6716.3     .03       0
#XS Ineff= 3 ,-1
  1016.1    2250     450    2250  4136.9   435.9  4407.1  6778.9   435.9
Permanent Ineff=
       F       F       F
Bank Sta=4136.9,4407.1
XS Rating Curve= 0 ,0
Exp/Cntr=0.3,0.1

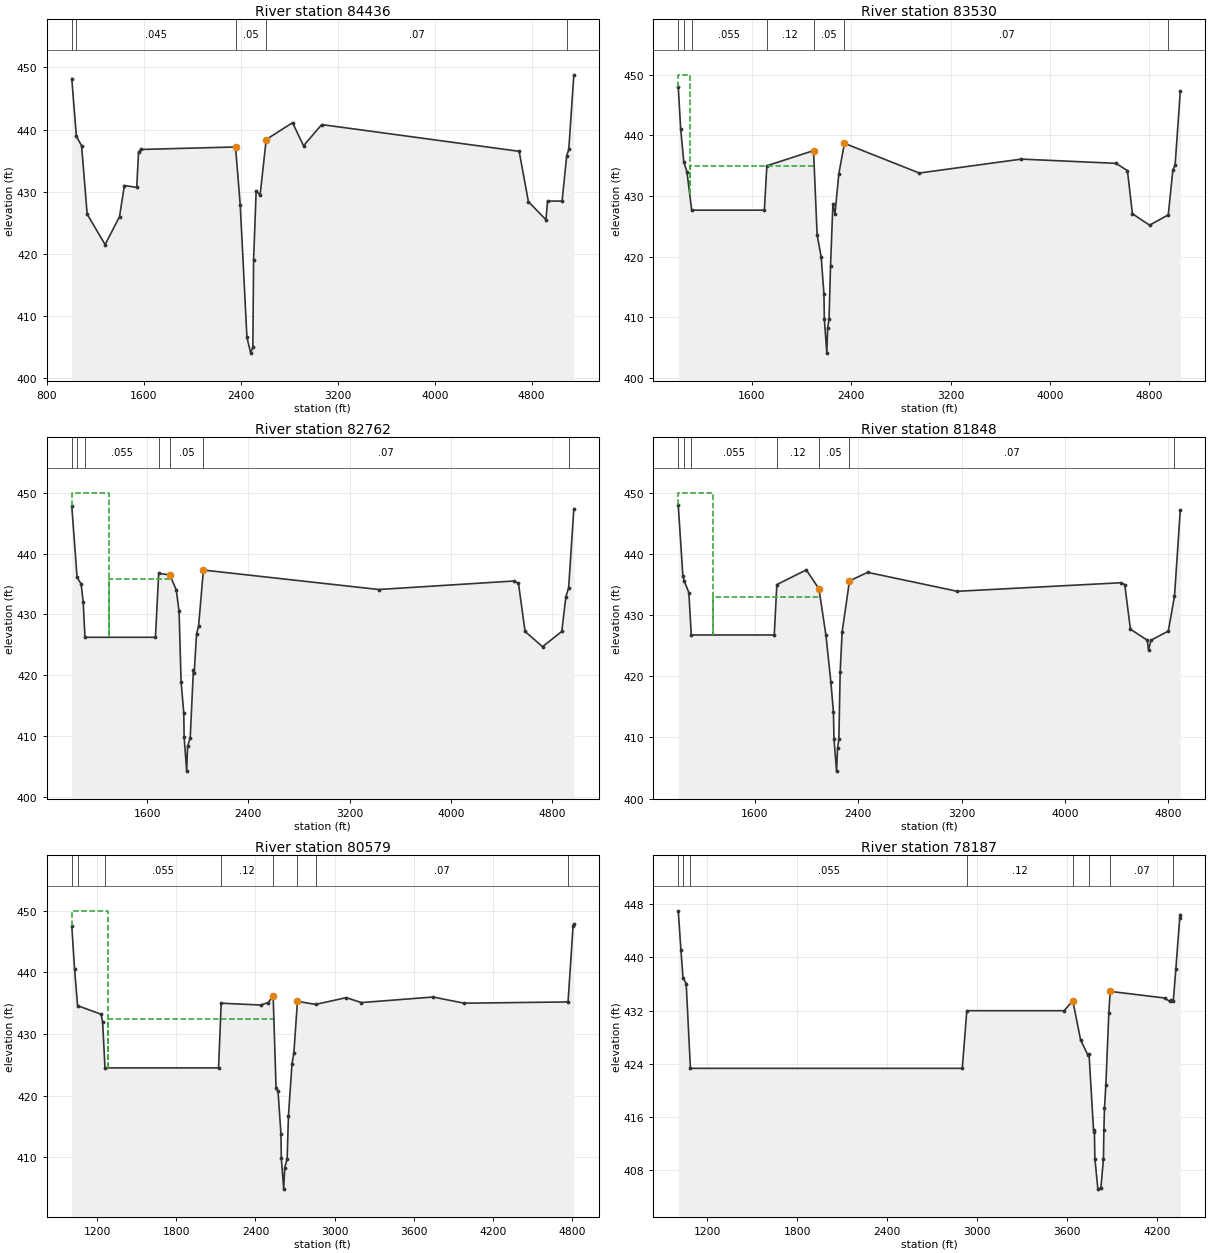
Type RM Length L Ch R = 1 ,84436   ,900,956,650
BEGIN DESCRIPTION:
This cross section corresponds to cross section 84436 of the non-georeferenced CDC model which was the source of this model.
END DESCRIPTION:
XS GIS Cut Line= 3
2450143.405519847030683.264832562448828.647978757030744.41595696
2446012.520736997030510.55126722
#Sta/Elev= 30
    1006   448.2    1044   438.9    1087   437.4    1133   426.4    1281   421.5
    1400     426    1440     431    1542   430.7    1557   436.4    1576   436.8
    2357   437.2    2396   427.8    2451   406.6    2482  404.05    2500     405
    2506     419    2527   430.1    2560   429.5    2610   438.4    2827   441.1
    2918   437.4    3068   440.8    4697   436.5    4773   428.4    4918   425.5
    4931   428.5    5051   428.5    5089   435.8    5106   436.8    5148   448.8
#Mann= 5 ,-1,0
    1006     .03       0    1044    .045       0    2357     .05       0
    2610     .07       0    5089     .03       0
#XS Ineff= 2 , 0
            2357   435.9    2610           435.9
Permanent Ineff=
       F       F
Bank Sta=2357,2610
XS Rating Curve= 0 ,0
Exp/Cntr=0.3,0.1

Type RM Length L Ch R = 1 ,83530   ,700,768,690
BEGIN DESCRIPTION:
This cross section corresponds to cross section 83530 of the non-georeferenced CDC model which was the source of this model.
END DESCRIPTION:
XS GIS Cut Line= 2
2450134.949828097029817.165514892446090.594727847029889.38584289
#Sta/Elev= 30
    1006     448    1026     441    1051   435.6    1076     434  1114.4  427.68
    1700  427.68    1720     435    2096   437.5    2125   423.6    2158   419.9
    2180   413.8    2183   409.8    2203   404.1    2210   408.3    2221   409.7
    2233   418.5    2252   428.7    2269   427.1    2300   433.7    2345   438.7
    2948   433.8    3770   436.1    4533   435.4    4625   434.2    4665   427.1
    4803   425.2    4954   426.9    4991   434.3    5009   435.1    5051   447.3
#Mann= 7 ,-1,0
    1006     .03       0    1051    .045       0  1114.4    .055       0
    1720     .12       0    2096     .05       0    2345     .07       0
    4954     .03       0
#XS Ineff= 3 ,-1
    1006    1098     450    1098    2096     435    2345    5051     435
Permanent Ineff=
       F       F       F
Bank Sta=2096,2345
XS Rating Curve= 0 ,0
Exp/Cntr=0.3,0.1

Type RM Length L Ch R = 1 ,82762   ,920,914,780
BEGIN DESCRIPTION:
This cross section corresponds to cross section 82762 of the non-georeferenced CDC model which was the source of this model.
END DESCRIPTION:
XS GIS Cut Line= 2
2450139.973768177029120.920844382446178.006298427029211.37670022
#Sta/Elev= 30
    1006   447.8    1048   436.1    1080     435    1096   432.1 1110.11  426.24
 1666.53  426.24    1692  436.75    1781   436.5    1831     434    1853   430.5
    1869   418.9    1890   413.8    1893   409.8    1913  404.23    1920   408.3
    1941   409.7    1966   420.9    1972   420.3    1991   426.8    2007   428.1
    2045   437.3    3429   434.1    4496   435.5    4532   435.1    4584   427.2
    4722   424.7    4874   427.2    4906   432.9    4928   434.4    4969   447.4
#Mann= 7 ,-1,0
    1006     .03       0    1048    .045       0 1110.11    .055       0
    1692     .12       0    1781     .05       0    2045     .07       0
    4928     .03       0
#XS Ineff= 3 ,-1
    1006    1298     450    1298    1781   435.8    2045    4969     435
Permanent Ineff=
       F       F       F
Bank Sta=1781,2045
XS Rating Curve= 0 ,0
Exp/Cntr=0.3,0.1

Type RM Length L Ch R = 1 ,81848   ,1090,1269,1200
BEGIN DESCRIPTION:
This cross section corresponds to cross section 81848 of the non-georeferenced CDC model which was the source of this model.
END DESCRIPTION:
XS GIS Cut Line= 3
2450144.67126533 7028172.55627132448247.31088683 7028425.5380488
2446276.46246633 7028425.5380488
#Sta/Elev= 30
    1007     448    1043   436.4    1053   435.6    1089   433.7  1107.8  426.76
    1750  426.76    1770     435    1998   437.4    2096   434.3    2150   426.7
    2188   419.1    2208   414.1    2212   409.8    2232   404.5    2240   408.3
    2250   409.7    2260   420.7    2275   427.2    2332   435.6    2473     437
    3166   433.9    4432   435.3    4462     435    4506   427.7    4637   425.9
    4646   424.3    4665   425.9    4799   427.4    4847   433.1    4892   447.2
#Mann= 7 ,-1,0
    1007     .03       0    1053    .045       0  1107.8    .055       0
    1770     .12       0    2096     .05       0    2332     .07       0
    4847     .03       0
#XS Ineff= 3 ,-1
    1007    1274     450    1274    2096     433    2332    4892     433
Permanent Ineff=
       F       F       F
Bank Sta=2096,2332
XS Rating Curve= 0 ,0
Exp/Cntr=0.3,0.1

Type RM Length L Ch R = 1 ,80579   ,1599,2391,1030
BEGIN DESCRIPTION:
This cross section corresponds to cross section 80579 of the non-georeferenced CDC model which was the source of this model.
END DESCRIPTION:
XS GIS Cut Line= 2
2450151.002617517027133.076722962446345.963639687027255.25626864
#Sta/Elev= 30
    1007   447.6    1028   440.6    1051   434.6    1230   433.2    1241   431.9
    1259  424.49    2120  424.49    2140     435    2439   434.7    2497   435.1
    2534   436.2    2556   421.2    2571   420.7    2593   413.8    2596   409.8
    2614   404.8    2622   408.3    2640   409.7    2650   416.7    2677   425.2
    2691   426.9    2718   435.3    2856   434.8    3088   435.9    3203   435.1
    3747     436    3981     435    4770   435.2    4808   447.5    4814   447.8
#Mann= 8 ,-1,0
    1007     .03       0    1051    .045       0    1259    .055       0
    2140     .12       0    2534    .055       0    2718     .12       0
    2856     .07       0    4770     .03       0
#XS Ineff= 3 ,-1
    1007    1279     450    1279    2534   432.5    2718    4814   432.5
Permanent Ineff=
       F       F       F
Bank Sta=2534,2718
XS Rating Curve= 0 ,0
Exp/Cntr=0.3,0.1

Type RM Length L Ch R = 1 ,78187   ,800,1712,1380
BEGIN DESCRIPTION:
This cross section corresponds to cross section 78187 of the non-georeferenced CDC model which was the source of this model.
END DESCRIPTION:
XS GIS Cut Line= 3
2449757.539821747025438.934770052446916.428049927026229.58115463
2446522.145373917026207.05101597
#Sta/Elev= 30
    1008     447    1026   441.1    1040   436.9    1061  436.07 1089.14  423.34
    2900  423.34    2930     432    3578     432    3636   433.5    3688   427.6
    3735   425.4    3744   425.5    3774   414.1    3780   413.8    3783   409.8
    3803   405.2    3823   405.4    3840   409.7    3843   414.1    3847   417.4
    3856   420.8    3876   431.7    3885   434.9    4250   433.9    4280   433.4
    4289   433.6    4305   433.4    4322   438.2    4348   445.9    4352   446.4
#Mann= 8 ,-1,0
    1008     .03       0    1040    .045       0 1089.14    .055       0
    2930     .12       0    3636     .12       0    3744    .055       0
    3885     .07       0    4305     .03       0
#XS Ineff= 2 , 0
            3636     432    3885             432
Permanent Ineff=
       F       F
Bank Sta=3636,3885
XS Rating Curve= 0 ,0
Exp/Cntr=0.3,0.1