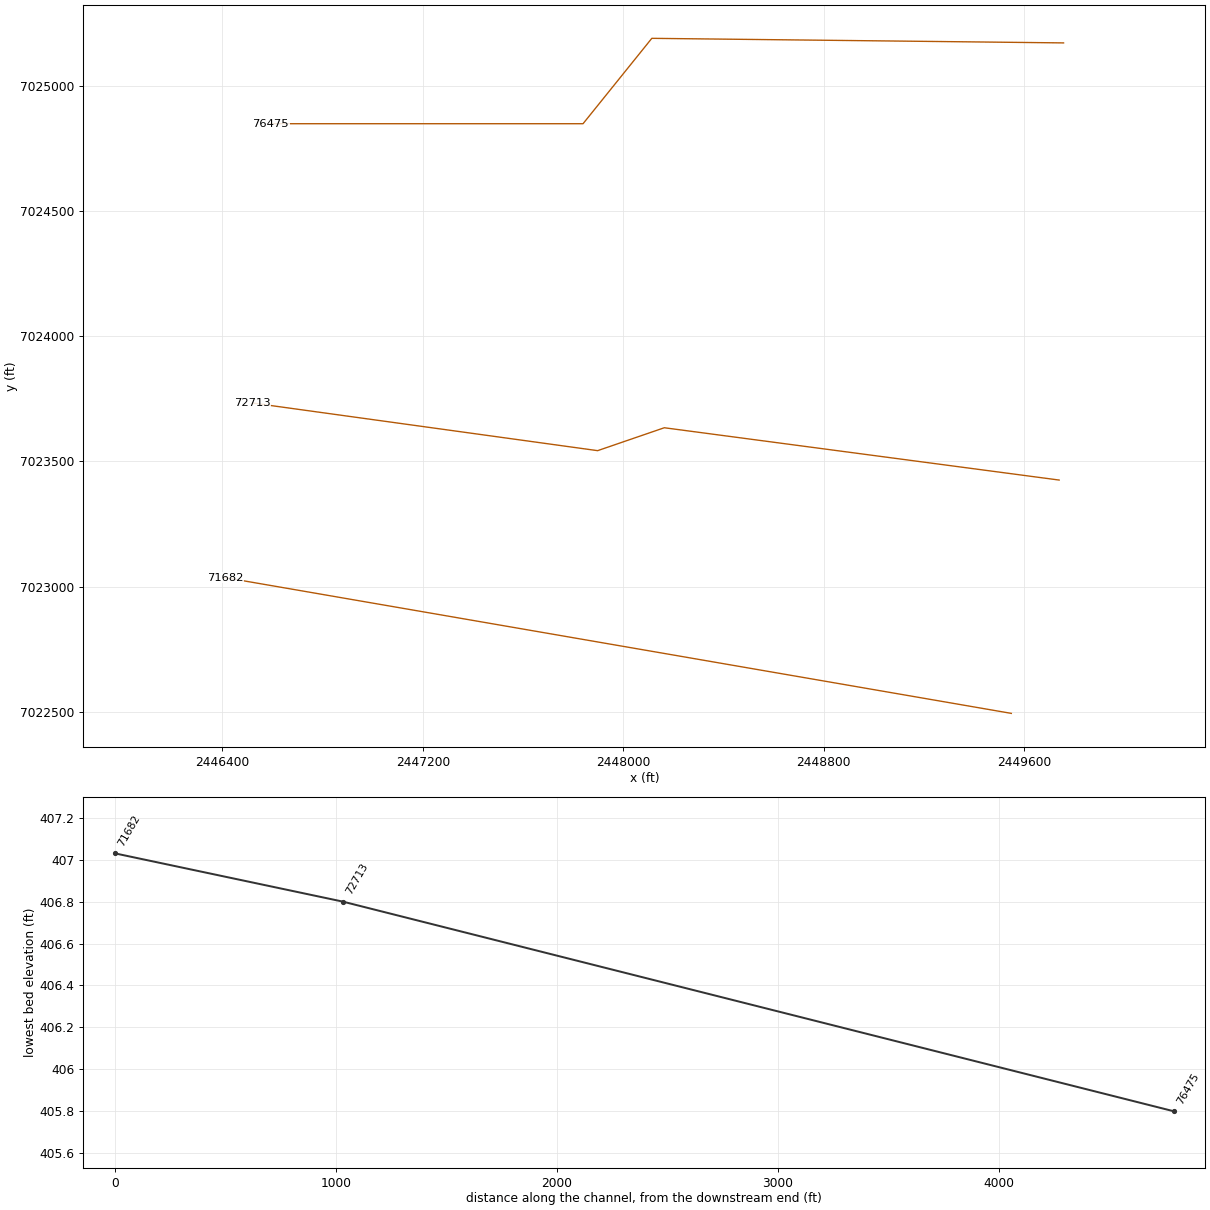
HEC-RAS study CDC_Consolidated_Model.prj: Upper Trinity CDC Consolidated Model

--- CDC_Consolidated_Model.g12 (geometry) --- (continued)

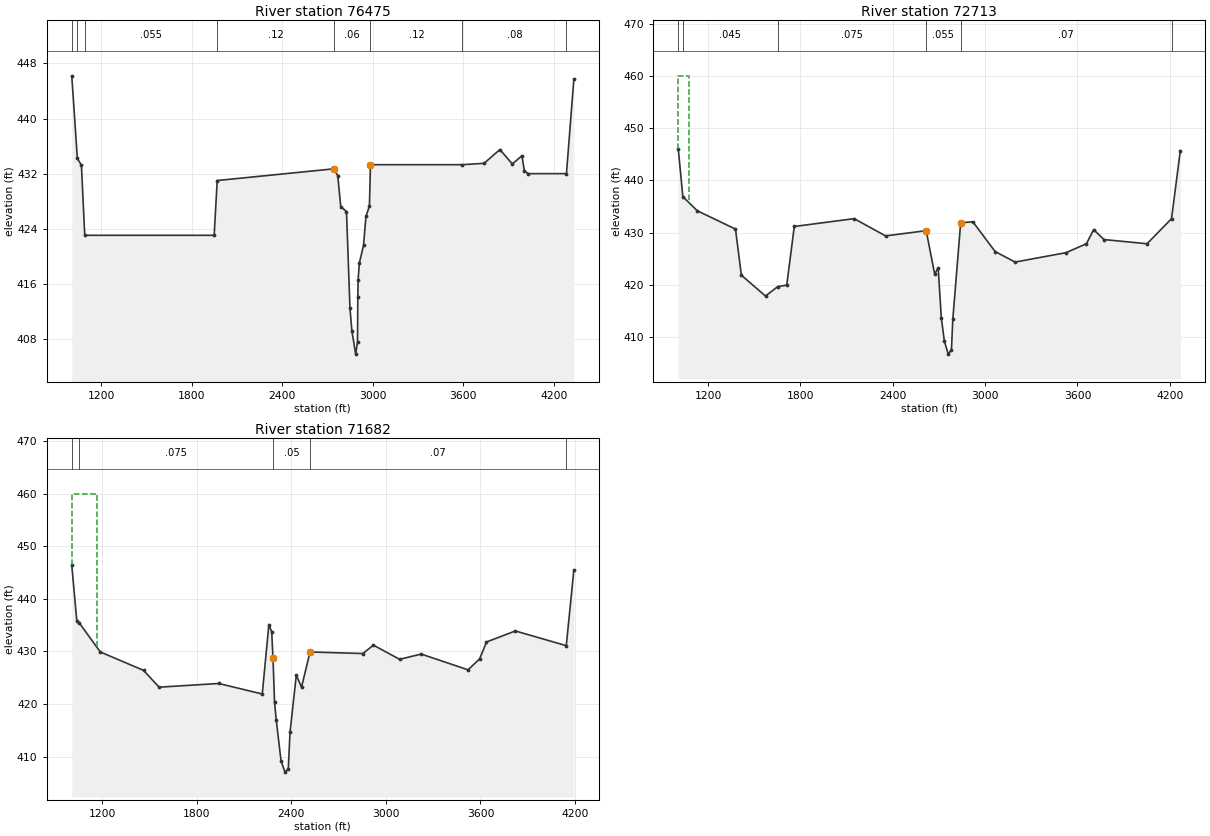
Type RM Length L Ch R = 1 ,76475   ,1740,3762,1200
BEGIN DESCRIPTION:
This cross section corresponds to cross section 76475 of the non-georeferenced CDC model which was the source of this model.
END DESCRIPTION:
XS GIS Cut Line= 4
2449757.729453927025171.567522632448114.222898427025189.82896905
2447839.728040587024848.789952962446593.120297587024848.78995296
#Sta/Elev= 30
    1006   446.2    1043   434.2    1070  433.24 1091.99  423.05    1950  423.05
    1970     431    2743   432.7    2769   431.7    2789   427.2    2827   426.5
    2850   412.5    2863   409.1    2888   405.8    2900   407.6    2902   414.1
    2904   416.5    2912     419    2940   421.6    2956   425.8    2979   427.3
    2986   433.3    3595   433.3    3739   433.5    3844   435.5    3926   433.4
    3990   434.6    4006   432.4    4032     432    4285     432    4334   445.7
#Mann= 8 ,-1,0
    1006     .03       0    1043    .045       0 1091.99    .055       0
    1970     .12       0    2743     .06       0    2986     .12       0
    3595     .08       0    4285     .03       0
#XS Ineff= 2 , 0
            2743     432    2986             432
Permanent Ineff=
       F       F
Bank Sta=2743,2986
XS Rating Curve= 0 ,0
Exp/Cntr=0.3,0.1

Type RM Length L Ch R = 1 ,72713   ,940,1031,740
BEGIN DESCRIPTION:
This cross section corresponds to cross section 72713 of the non-georeferenced CDC model which was the source of this model.
END DESCRIPTION:
XS GIS Cut Line= 4
2449740.069056187023425.39581813 2448164.13093517023634.35898288
2447897.953974017023542.861134382446520.236257027023733.20392954
#Sta/Elev= 30
    1006   446.1    1036   436.9    1130   434.2    1378   430.7    1416   421.9
    1573   417.9    1652   419.7    1711     420    1760   431.2    2149   432.7
    2353   429.4    2617   430.4    2672   422.1    2695   423.3    2715   413.8
    2735   409.3    2760   406.8    2781   407.6    2790   413.5    2841   431.9
    2920   432.1    3065   426.4    3195   424.4    3526   426.2    3658   427.9
    3705   430.6    3772   428.7    4052   427.9    4211   432.7    4268   445.7
#Mann= 6 ,-1,0
    1006     .03       0    1036    .045       0    1652    .075       0
    2617    .055       0    2841     .07       0    4211     .03       0
#XS Ineff= 3 ,-1
    1000    1077     460    1077    2617     429    2841    4268     429
Permanent Ineff=
       F       F       F
Bank Sta=2617,2841
XS Rating Curve= 0 ,0
Exp/Cntr=0.3,0.1

Type RM Length L Ch R = 1 ,71682   ,850,1089,920
BEGIN DESCRIPTION:
This cross section corresponds to cross section 71682 of the non-georeferenced CDC model which was the source of this model.
END DESCRIPTION:
XS GIS Cut Line= 2
  2449549.1829557022493.442301472446411.683324527023035.61608589
#Sta/Elev= 30
    1008   446.4    1040   435.8    1054   435.5    1189   429.9    1463   426.4
    1562   423.2    1940   423.9    2216   421.9    2258   435.1    2276   433.7
    2284   428.8    2294   420.3    2305   416.9    2335   409.2    2360  407.03
    2381   407.6    2392   414.6    2432   425.5    2465   423.2    2519   429.9
    2854   429.6    2921   431.2    3087   428.5    3224   429.5    3521   426.5
    3595   428.6    3638   431.8    3821   433.9    4144   431.1    4192   445.5
#Mann= 5 ,-1,0
    1008     .03       0    1054    .075       0    2284     .05       0
    2519     .07       0    4144     .03       0
#XS Ineff= 3 ,-1
    1008    1171     460    1171    2284   428.8    2519    4192     429
Permanent Ineff=
       F       F       F
Bank Sta=2284,2519
XS Rating Curve= 0 ,0
Exp/Cntr=0.3,0.1