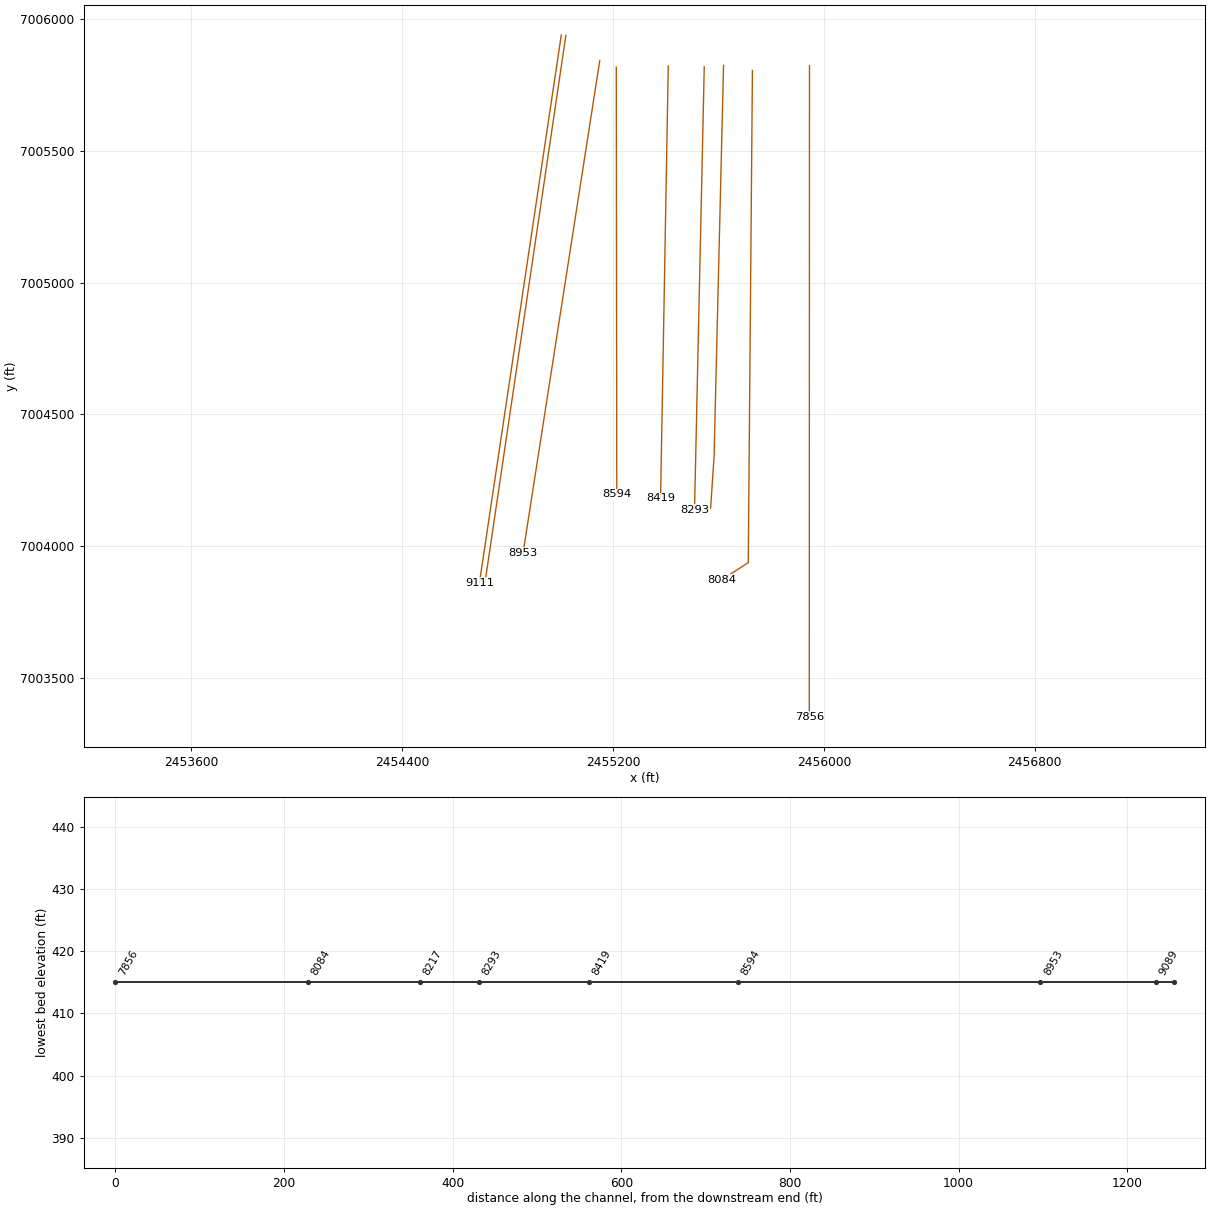
HEC-RAS study CDC_Consolidated_Model.prj: Upper Trinity CDC Consolidated Model

--- CDC_Consolidated_Model.g12 (geometry) --- (continued)

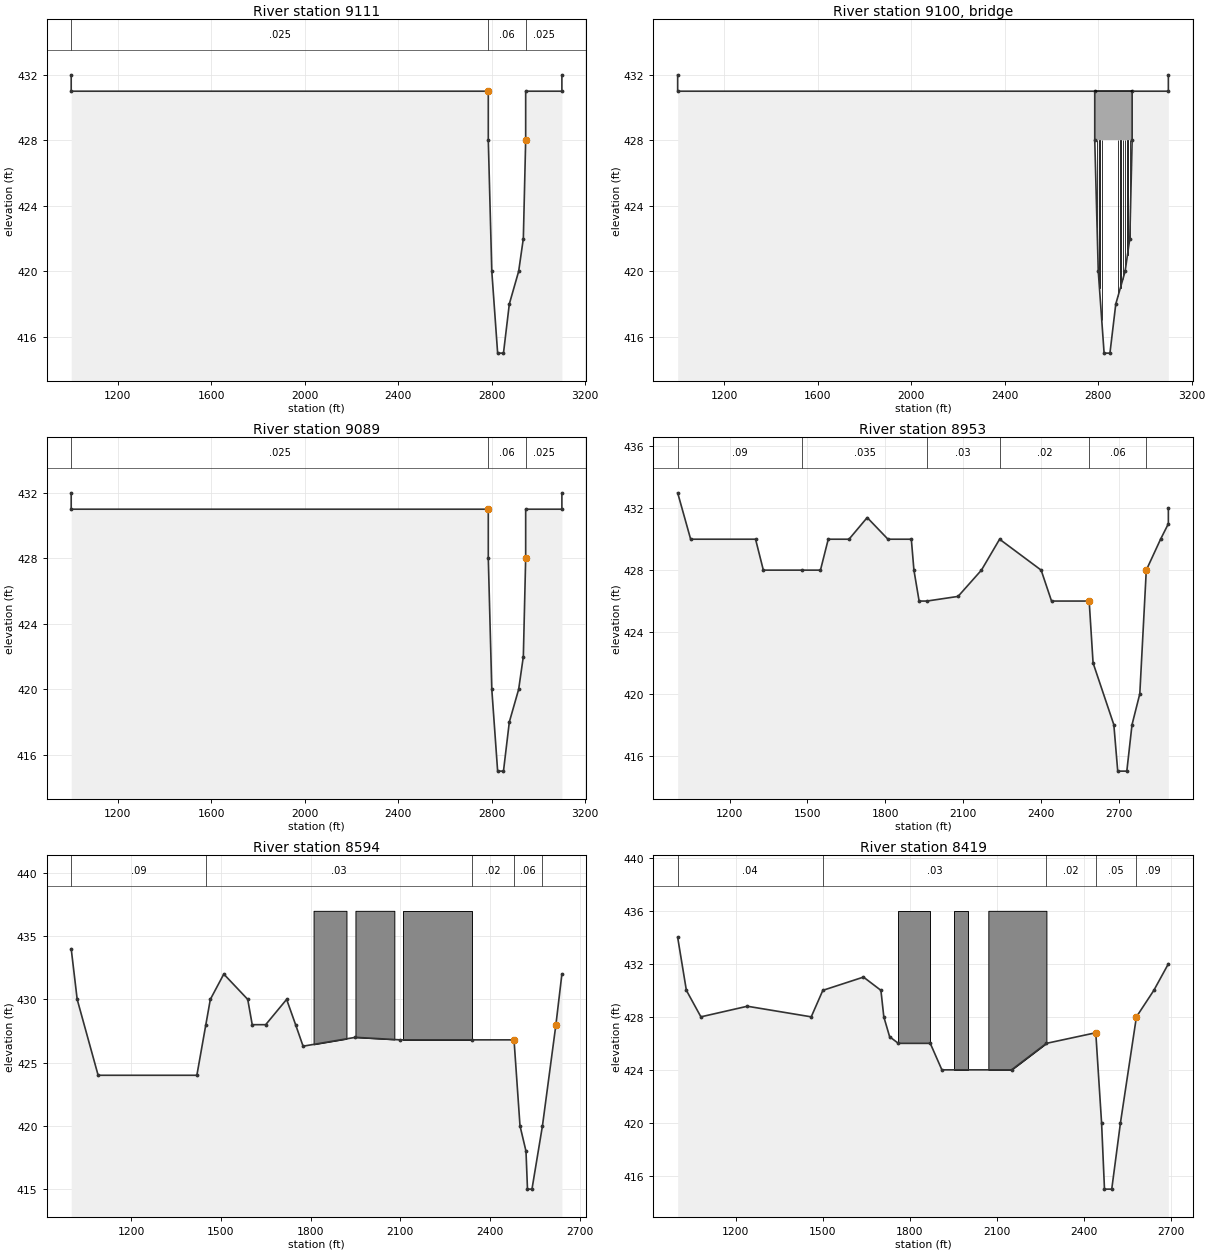
Type RM Length L Ch R = 1 ,9111    ,21,21,21
BEGIN DESCRIPTION:
This cross section corresponds to cross section 9111 of the non-georeferenced CDC model which was the source of this model.
Upstream bounding cross section for Burlington Northern RR bridge
END DESCRIPTION:
XS GIS Cut Line= 2
2455004.091664587005938.998704392454693.73172101 7003862.0596168
#Sta/Elev= 14
    1000     432    1000     431    2785     431    2785     428    2800     420
    2825     415    2850     415    2875     418    2915     420    2935     422
    2945     428    2945     431    3100     431    3100     432
#Mann= 3 ,-1,0
    1000    .025       0    2785     .06       0    2945    .025       0
Bank Sta=2785,2945
XS Rating Curve= 0 ,0
Exp/Cntr=0.3,0.1

Type RM Length L Ch R = 3 ,9100    ,,,
BEGIN DESCRIPTION:
Burlington Northern Railroad
END DESCRIPTION:
Node Name=BN Railroad
Bridge Culvert--1,0,-1,-1, 0
Deck Dist Width WeirC Skew NumUp NumDn MinLoCord MaxHiCord MaxSubmerge Is_Ogee
1,19,2.6,0, 2, 2, , , 0.95, 0, 0,0,,
    2785    2945
     431     431
     428     428
    2785    2945
     431     431
     428     428
Pier Skew, UpSta & Num, DnSta & Num=  ,2795, 2 ,2795, 2 , 0 , 0 , 0 ,,
       1       1
     400     430
       1       1
     400     430
Pier Skew, UpSta & Num, DnSta & Num=  ,2805, 2 ,2805, 2 , 0 , 0 , 0 ,,
       1       1
     400     430
       1       1
     400     430
Pier Skew, UpSta & Num, DnSta & Num=  ,2815, 2 ,2815, 2 , 0 , 0 , 0 ,,
       1       1
     400     430
       1       1
     400     430
Pier Skew, UpSta & Num, DnSta & Num=  ,2885, 2 ,2885, 2 , 0 , 0 , 0 ,,
       1       1
     400     430
       1       1
     400     430
Pier Skew, UpSta & Num, DnSta & Num=  ,2895, 2 ,2895, 2 , 0 , 0 , 0 ,,
       1       1
     400     430
       1       1
     400     430
Pier Skew, UpSta & Num, DnSta & Num=  ,2905, 2 ,2905, 2 , 0 , 0 , 0 ,,
       1       1
     400     430
       1       1
     400     430
Pier Skew, UpSta & Num, DnSta & Num=  ,2915, 2 ,2915, 2 , 0 , 0 , 0 ,,
       1       1
     400     430
       1       1
     400     430
Pier Skew, UpSta & Num, DnSta & Num=  ,2925, 2 ,2925, 2 , 0 , 0 , 0 ,,
       1       1
     400     430
       1       1
     400     430
Pier Skew, UpSta & Num, DnSta & Num=  ,2935, 2 ,2935, 2 , 0 , 0 , 0 ,,
       1       1
     400     430
       1       1
     400     430
BR Coef=-1 , 0 , 0 ,, 0 ,,,0.8,0,,0,
WSPro=,,,, 1 ,,,, 0 ,,,, 0 ,,,,-1 ,-1 ,-1 , 0 , 0 , 0 , 0 , 0
BC Design=,, 0 ,, 0 ,,,,,,
BC HTab HWMax=432
BC Use User HTab Curves=0
BC User HTab FreeFlow(D)= 0

Type RM Length L Ch R = 1 ,9089    ,137,137,137
BEGIN DESCRIPTION:
This cross section corresponds to cross section 9089 of the non-georeferenced CDC model which was the source of this model.
Downstream bounding cross section for Burlington Northern RR bridge
END DESCRIPTION:
XS GIS Cut Line= 2
2455021.354097257005936.887488132454714.29664052 7003859.4572598
#Sta/Elev= 14
    1000     432    1000     431    2785     431    2785     428    2800     420
    2825     415    2850     415    2875     418    2915     420    2935     422
    2945     428    2945     431    3100     431    3100     432
#Mann= 3 ,-1,0
    1000    .025       0    2785     .06       0    2945    .025       0
Bank Sta=2785,2945
XS Rating Curve= 0 ,0
Exp/Cntr=0.3,0.1

Type RM Length L Ch R = 1 ,8953    ,160,359,350
BEGIN DESCRIPTION:
This cross section corresponds to cross section 8953 of the non-georeferenced CDC model which was the source of this model.
END DESCRIPTION:
XS GIS Cut Line= 2
2455150.116963097005842.398831962454859.196613167003974.92323622
#Sta/Elev= 30
    1000     433    1050     430    1300     430    1330     428    1480     428
    1550     428    1580     430    1660     430    1730   431.4    1810     430
    1900     430    1910     428    1930     426    1960     426    2080   426.3
    2170     428    2240     430    2400     428    2440     426    2585     426
    2600     422    2680     418    2695     415    2730     415    2750     418
    2780     420    2805     428    2860     430    2890     431    2890     432
#Mann= 6 ,-1,0
    1000     .09       0    1480    .035       0    1960     .03       0
    2240     .02       0    2585     .06       0    2805     .08       0
Bank Sta=2585,2805
XS Rating Curve= 0 ,0
Exp/Cntr=0.3,0.1

Type RM Length L Ch R = 1 ,8594    ,211,176,181
BEGIN DESCRIPTION:
This cross section corresponds to cross section 8594 of the non-georeferenced CDC model which was the source of this model.
END DESCRIPTION:
XS GIS Cut Line= 2
2455212.663425927005817.151179052455214.561059927004197.15212247
#Sta/Elev= 24
    1000     434    1020     430    1090     424    1420     424    1450     428
    1465     430    1510     432    1590     430    1605     428    1650     428
    1720     430    1750     428    1775   426.3    1950     427    2100   426.8
    2340   426.8    2480   426.8    2500     420    2520     418    2525     415
    2540     415    2575     420    2620     428    2640     432
#Mann= 5 ,-1,0
    1000     .09       0    1450     .03       0    2340     .02       0
    2480     .06       0    2575     .08       0
#Block Obstruct= 3 ,-1
    1810    1920     437    1950    2080     437    2110    2340     437
Bank Sta=2480,2620
XS Rating Curve= 0 ,0
Exp/Cntr=0.3,0.1

Type RM Length L Ch R = 1 ,8419    ,131,131,131
BEGIN DESCRIPTION:
This cross section corresponds to cross section 8419 of the non-georeferenced CDC model which was the source of this model.
END DESCRIPTION:
XS GIS Cut Line= 2
2455409.864147017005821.679713292455380.70803735 7004181.9388983
#Sta/Elev= 23
    1000     434    1030     430    1080     428    1240   428.8    1460     428
    1500     430    1640     431    1700     430    1710     428    1730   426.5
    1760     426    1870     426    1910     424    2150     424    2270     426
    2440   426.8    2460     420    2470     415    2495     415    2525     420
    2580     428    2640     430    2690     432
#Mann= 5 ,-1,0
    1000     .04       0    1500     .03       0    2270     .02       0
    2440     .05       0    2580     .09       0
#Block Obstruct= 3 ,-1
    1760    1870     436    1950    2000     436    2070    2270     436
Bank Sta=2440,2580
XS Rating Curve= 0 ,0
Exp/Cntr=0.3,0.1

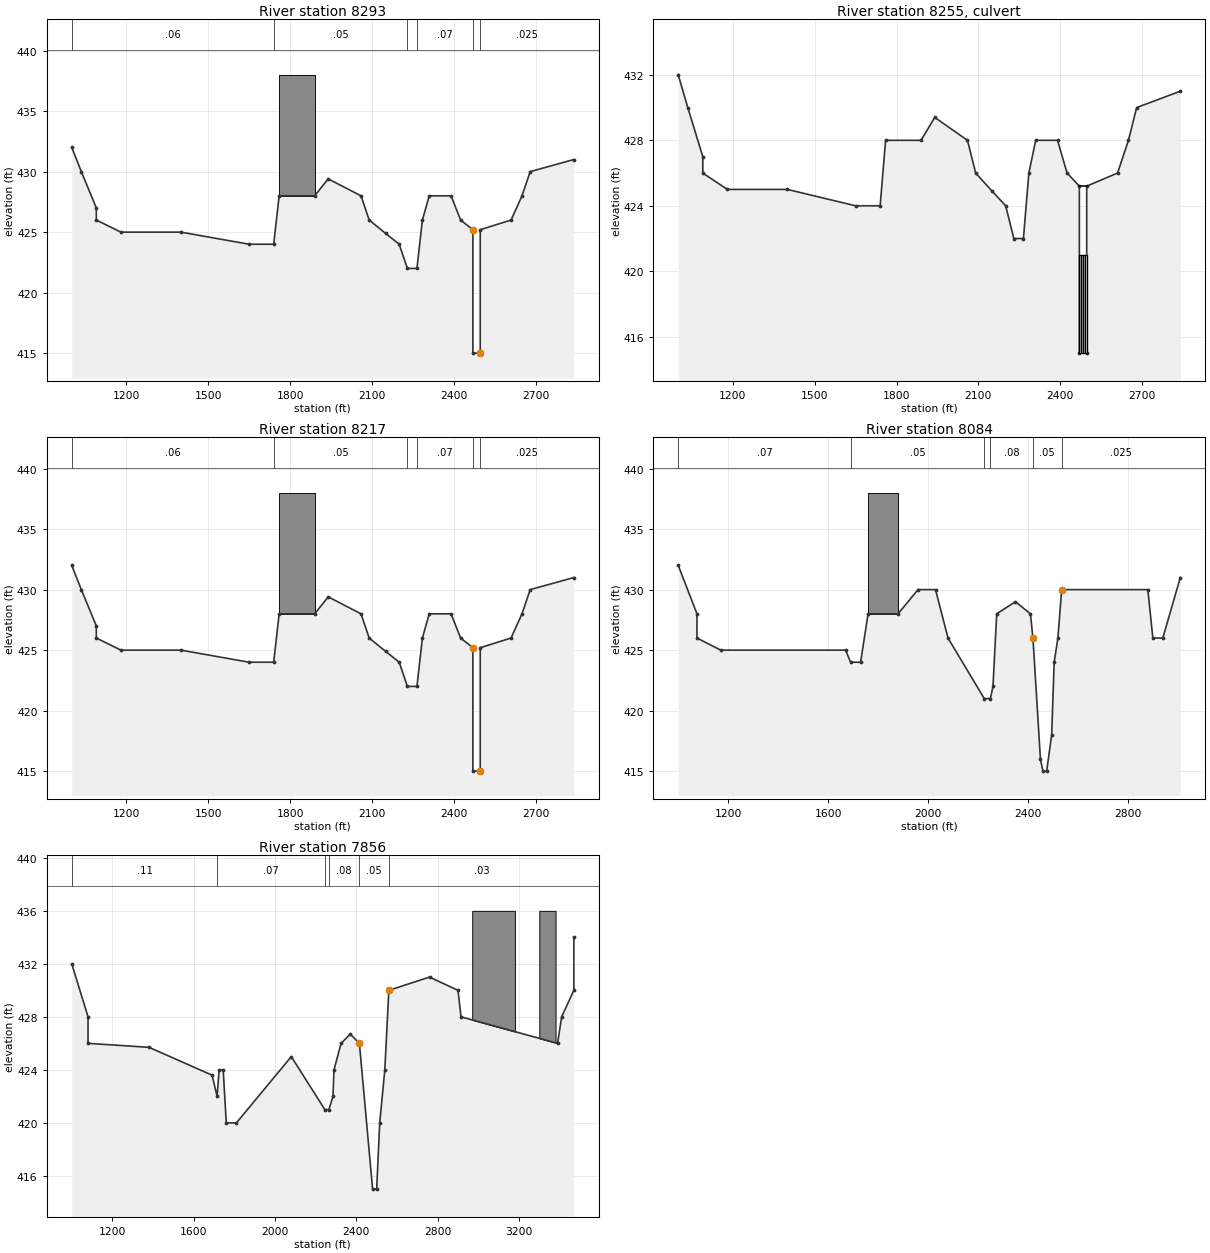
Type RM Length L Ch R = 1 ,8293    ,70,70,70
BEGIN DESCRIPTION:
This cross section corresponds to cross section 8293 of the non-georeferenced CDC model which was the source of this model.
Upstream bounding cross section for the Spangler Road bridge
END DESCRIPTION:
XS GIS Cut Line= 2
2455546.387167937005818.321124212455509.511257417004138.72605821
#Sta/Elev= 29
    1000     432    1035     430    1090     427    1090     426    1180     425
    1400     425    1650     424    1740     424    1760     428    1890     428
    1940   429.4    2060     428    2090     426    2150   424.9    2200     424
    2230     422    2265     422    2285     426    2310     428    2390     428
    2425     426    2470   425.2    2470     415    2497     415    2497   425.2
    2610     426    2650     428    2680     430    2840     431
#Mann= 6 ,-1,0
    1000     .06       0    1740     .05       0    2230     .02       0
    2265     .07       0    2470     .05       0    2497    .025       0
#Block Obstruct= 1 ,-1
    1760    1890     438
Bank Sta=2470,2497
XS Rating Curve= 0 ,0
Exp/Cntr=0.3,0.1

Type RM Length L Ch R = 2 ,8255    ,,,
BEGIN DESCRIPTION:
Spangler Road
END DESCRIPTION:
Node Name=Spangler Road
Bridge Culvert--1,0,-1,-1, 0
Deck Dist Width WeirC Skew NumUp NumDn MinLoCord MaxHiCord MaxSubmerge Is_Ogee
1,68,2.6,0, 2, 2, , , 0.95, 0, 0,0,,
    2470    2497
   425.2   425.2
    2470    2497
   425.2   425.2
BR Coef=-1 , 0 , 0 ,, 0 ,,,0.8,-1,,0,
WSPro=,,,, 1 ,,,, 0 ,,,, 0 ,,,,-1 ,-1 ,-1 , 0 , 0 , 0 , 0 , 0
Multiple Barrel Culv=2,6,6,68,0.16,0.5,1,10,1,415,415, 4,Culvert #1  , 0 ,1
    2473    2473    2480    2480    2487    2487    2494    2494
BC Culvert Barrel=1,Barrel #1,0
BC Culvert Barrel=2,Barrel #2,0
BC Culvert Barrel=3,Barrel #3,0
BC Culvert Barrel=4,Barrel #4,0
Culvert Bottom n=0.16
BC Design=,, 0 ,, 0 ,,,,,,
BC HTab HWMax=432
BC Use User HTab Curves=0
BC User HTab FreeFlow(D)= 0

Type RM Length L Ch R = 1 ,8217    ,125,133,140
BEGIN DESCRIPTION:
This cross section corresponds to cross section 8217 of the non-georeferenced CDC model which was the source of this model.
Downstream bounding cross section for the Spangler Road bridge
END DESCRIPTION:
XS GIS Cut Line= 3
2455619.579934927005824.043225632455583.656122277004341.81292239
2455570.661069517004144.90682013
#Sta/Elev= 29
    1000     432    1035     430    1090     427    1090     426    1180     425
    1400     425    1650     424    1740     424    1760     428    1890     428
    1940   429.4    2060     428    2090     426    2150   424.9    2200     424
    2230     422    2265     422    2285     426    2310     428    2390     428
    2425     426    2470   425.2    2470     415    2497     415    2497   425.2
    2610     426    2650     428    2680     430    2840     431
#Mann= 6 ,-1,0
    1000     .06       0    1740     .05       0    2230     .02       0
    2265     .07       0    2470     .05       0    2497    .025       0
#Block Obstruct= 1 ,-1
    1760    1890     438
Bank Sta=2470,2497
XS Rating Curve= 0 ,0
Exp/Cntr=0.3,0.1

Type RM Length L Ch R = 1 ,8084    ,228,228,228
BEGIN DESCRIPTION:
This cross section corresponds to cross section 8084 of the non-georeferenced CDC model which was the source of this model.
END DESCRIPTION:
XS GIS Cut Line= 3
2455729.113508497005804.651532132455713.315967927003937.66215588
  2455614.3637387003873.48118189
#Sta/Elev= 30
    1000     432    1075     428    1075     426    1170     425    1670     425
    1690     424    1730     424    1760     428    1880     428    1960     430
    2030     430    2080     426    2225     421    2250     421    2260     422
    2275     428    2350     429    2410     428    2420     426    2450     416
    2460     415    2475     415    2495     418    2505     424    2520     426
    2535     430    2880     430    2900     426    2940     426    3010     431
#Mann= 6 ,-1,0
    1000     .07       0    1690     .05       0    2225     .02       0
    2250     .08       0    2420     .05       0    2535    .025       0
#Block Obstruct= 1 ,-1
    1760    1880     438
Bank Sta=2420,2535
XS Rating Curve= 0 ,0
Exp/Cntr=0.3,0.1

Type RM Length L Ch R = 1 ,7856    ,216,216,216
BEGIN DESCRIPTION:
This cross section corresponds to cross section 7856 of the non-georeferenced CDC model which was the source of this model.
END DESCRIPTION:
XS GIS Cut Line= 2
2455945.542865667005823.038962542455944.75546569 7003353.0389813
#Sta/Elev= 30
    1000     432    1080     428    1080     426    1380   425.7    1690   423.6
    1715     422    1725     424    1745     424    1760     420    1810     420
    2080     425    2245     421    2265     421    2285     422    2290     424
    2325     426    2370   426.7    2415     426    2480     415    2500     415
    2515     420    2540     424    2560     430    2760     431    2900     430
    2915     428    3390     426    3410     428    3470     430    3470     434
#Mann= 6 ,-1,0
    1000     .11       0    1715     .07       0    2245     .02       0
    2265     .08       0    2415     .05       0    2560     .03       0
#Block Obstruct= 2 ,-1
    2970    3180     436    3300    3380     436
Bank Sta=2415,2560
XS Rating Curve= 0 ,0
Exp/Cntr=0.3,0.1