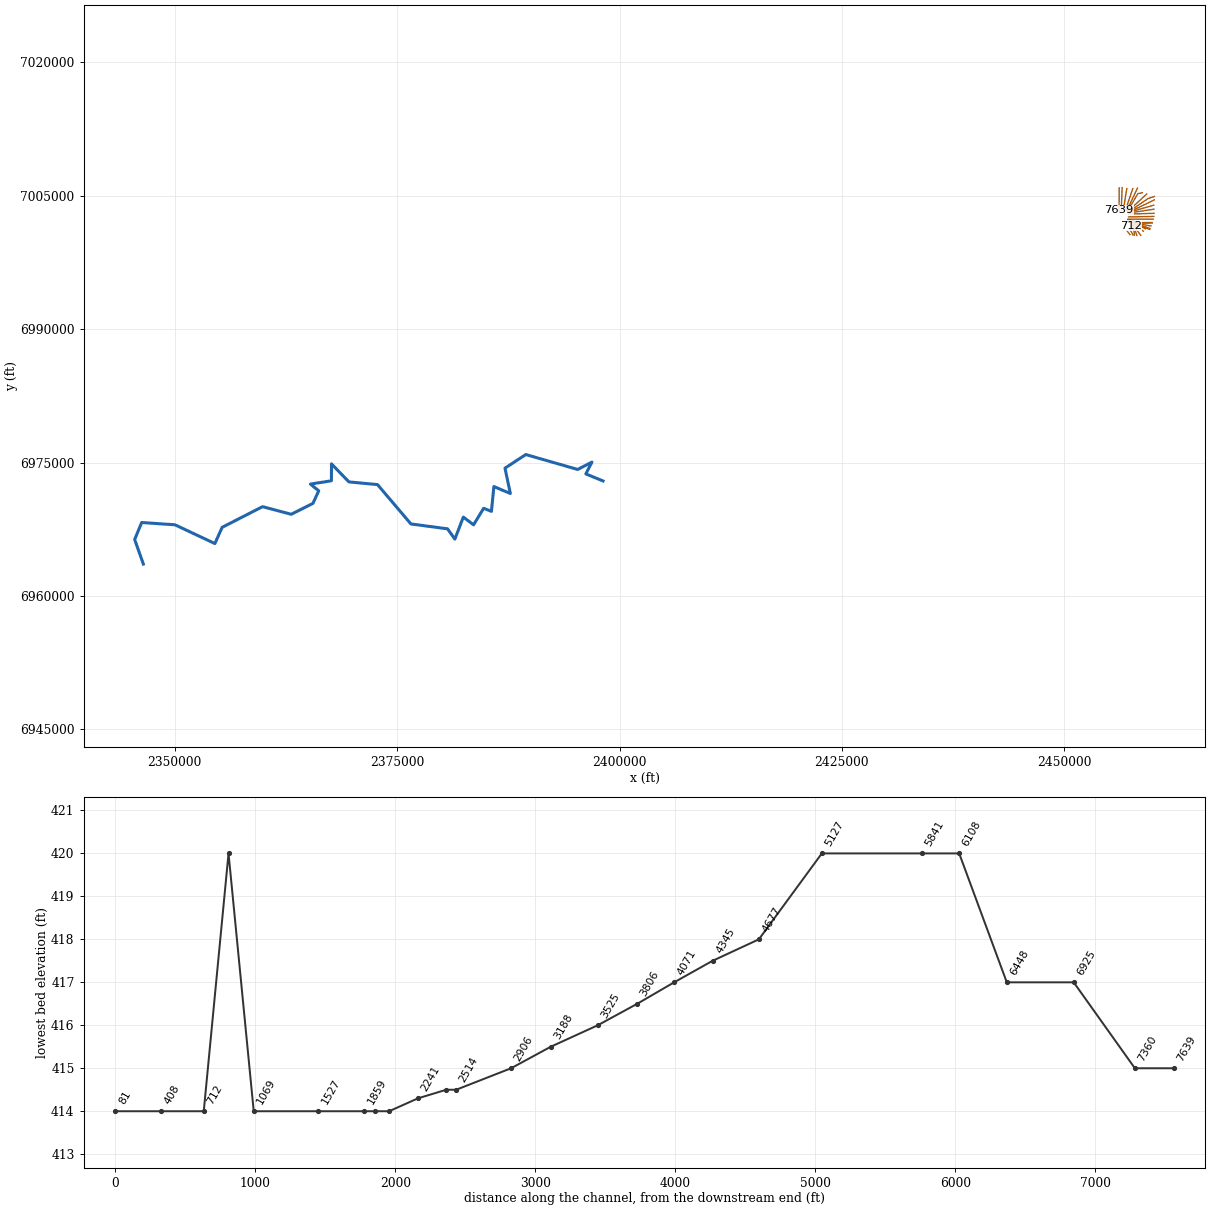
HEC-RAS study CDC_Consolidated_Model.prj: Upper Trinity CDC Consolidated Model

--- CDC_Consolidated_Model.g12 (geometry) --- (continued)

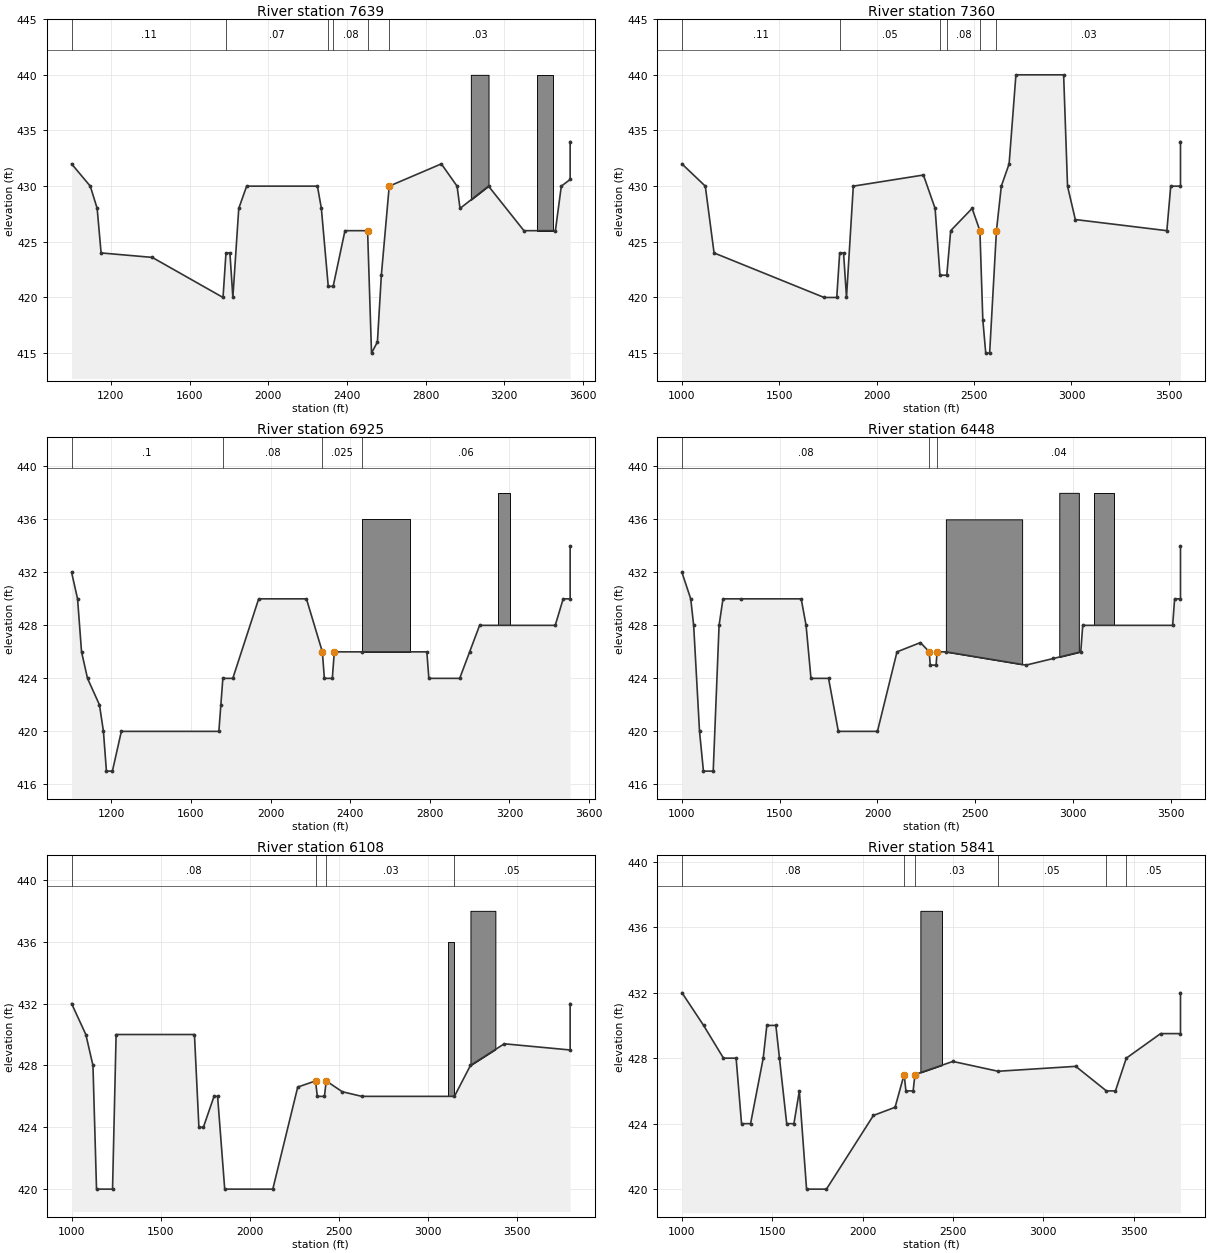
Type RM Length L Ch R = 1 ,7639    ,298,277,259
BEGIN DESCRIPTION:
This cross section corresponds to cross section 7639 of the non-georeferenced CDC model which was the source of this model.
END DESCRIPTION:
XS GIS Cut Line= 2
2456175.122787097005880.597574472456152.28260967 7003345.7004133
#Sta/Elev= 30
    1000     432    1095     430    1130     428    1150     424    1410   423.6
    1770     420    1785     424    1805     424    1820     420    1850     428
    1890     430    2250     430    2270     428    2305     421    2330     421
    2390     426    2505     426    2525     415    2555     416    2575     422
    2615     430    2880     432    2960     430    2975     428    3120     430
    3300     426    3460     426    3490     430    3535   430.6    3535     434
#Mann= 6 ,-1,0
    1000     .11       0    1785     .07       0    2305     .02       0
    2330     .08       0    2505     .05       0    2615     .03       0
#Block Obstruct= 2 ,-1
    3030    3120     440    3365    3450     440
Bank Sta=2505,2615
XS Rating Curve= 0 ,0
Exp/Cntr=0.3,0.1

Type RM Length L Ch R = 1 ,7360    ,452,437,311
BEGIN DESCRIPTION:
This cross section corresponds to cross section 7360 of the non-georeferenced CDC model which was the source of this model.
END DESCRIPTION:
XS GIS Cut Line= 2
2456505.616876757005908.161167642456396.289995677003350.49666356
#Sta/Elev= 30
    1000     432    1120     430    1165     424    1730     420    1795     420
    1810     424    1830     424    1845     420    1880     430    2240     431
    2300     428    2325     422    2360     422    2380     426    2490     428
    2530     426    2545     418    2560     415    2580     415    2615     426
    2640     430    2680     432    2715     440    2960     440    2980     430
    3020     427    3490     426    3510     430    3560     430    3560     434
#Mann= 6 ,-1,0
    1000     .11       0    1810     .05       0    2325     .02       0
    2360     .08       0    2530     .05       0    2615     .03       0
Bank Sta=2530,2615
XS Rating Curve= 0 ,0
Exp/Cntr=0.3,0.1

Type RM Length L Ch R = 1 ,6925    ,561,478,350
BEGIN DESCRIPTION:
This cross section corresponds to cross section 6925 of the non-georeferenced CDC model which was the source of this model.
END DESCRIPTION:
XS GIS Cut Line= 2
2457025.548579667005791.406479882456630.352847767003317.77658464
#Sta/Elev= 29
    1000     432    1030     430    1050     426    1080     424    1140     422
    1160     420    1175     417    1205     417    1250     420    1740     420
    1750     422    1760     424    1810     424    1940     430    2180     430
    2260     426    2270     424    2310     424    2320     426    2460     426
    2785     426    2795     424    2950     424    3000     426    3050     428
    3430     428    3470     430    3505     430    3505     434
#Mann= 4 ,-1,0
    1000      .1       0    1760     .08       0    2260    .025       0
    2460     .06       0
#Block Obstruct= 2 ,-1
    2460    2700     436    3140    3205     438
Bank Sta=2260,2320
XS Rating Curve= 0 ,0
Exp/Cntr=0.3,0.1

Type RM Length L Ch R = 1 ,6448    ,400,340,250
BEGIN DESCRIPTION:
This cross section corresponds to cross section 6448 of the non-georeferenced CDC model which was the source of this model.
END DESCRIPTION:
XS GIS Cut Line= 2
2457697.747038427005798.583958972456877.258521917003384.18983763
#Sta/Elev= 30
    1000     432    1045     430    1060     428    1090     420    1110     417
    1160     417    1190     428    1210     430    1300     430    1610     430
    1635     428    1660     424    1750     424    1800     420    2000     420
    2100     426    2220   426.7    2265     426    2270     425    2300     425
    2305     426    2350     426    2760     425    2900   425.5    3040     426
    3050     428    3510     428    3520     430    3550     430    3550     434
#Mann= 3 ,-1,0
    1000     .08       0    2265     .02       0    2305     .04       0
#Block Obstruct= 3 ,-1
    2350    2740     436    2930    3030     438    3110    3210     438
Bank Sta=2265,2305
XS Rating Curve= 0 ,0
Exp/Cntr=0.3,0.1

Type RM Length L Ch R = 1 ,6108    ,289,266,190
BEGIN DESCRIPTION:
This cross section corresponds to cross section 6108 of the non-georeferenced CDC model which was the source of this model.
END DESCRIPTION:
XS GIS Cut Line= 2
2458228.105885837005844.132096222457018.314670267003318.97769772
#Sta/Elev= 25
    1000     432    1080     430    1120     428    1140     420    1230     420
    1250     430    1690     430    1715     424    1740     424    1800     426
    1820     426    1860     420    2130     420    2270   426.6    2370     427
    2380     426    2420     426    2430     427    2520   426.3    2630     426
    3150     426    3240     428    3430   429.4    3800     429    3800     432
#Mann= 4 ,-1,0
    1000     .08       0    2370     .02       0    2430     .03       0
    3150     .05       0
#Block Obstruct= 2 ,-1
    3115    3150     436    3240    3380     438
Bank Sta=2370,2430
XS Rating Curve= 0 ,0
Exp/Cntr=0.3,0.1

Type RM Length L Ch R = 1 ,5841    ,751,715,400
BEGIN DESCRIPTION:
This cross section corresponds to cross section 5841 of the non-georeferenced CDC model which was the source of this model.
END DESCRIPTION:
XS GIS Cut Line= 3
2458772.544101427005332.150180552458276.446996517005232.09395021
2457119.936186167003297.51153331
#Sta/Elev= 30
    1000     432    1120     430    1230     428    1300     428    1330     424
    1380     424    1450     428    1470     430    1520     430    1540     428
    1580     424    1620     424    1650     426    1690     420    1800     420
    2060   424.5    2180     425    2230     427    2240     426    2280     426
    2290     427    2500   427.8    2750   427.2    3180   427.5    3350     426
    3400     426    3460     428    3650   429.5    3760   429.5    3760     432
#Mann= 6 ,-1,0
    1000     .08       0    2230     .02       0    2290     .03       0
    2750     .05       0    3350     .02       0    3460     .05       0
#Block Obstruct= 1 ,-1
    2320    2440     437
Bank Sta=2230,2290
XS Rating Curve= 0 ,0
Exp/Cntr=0.3,0.1

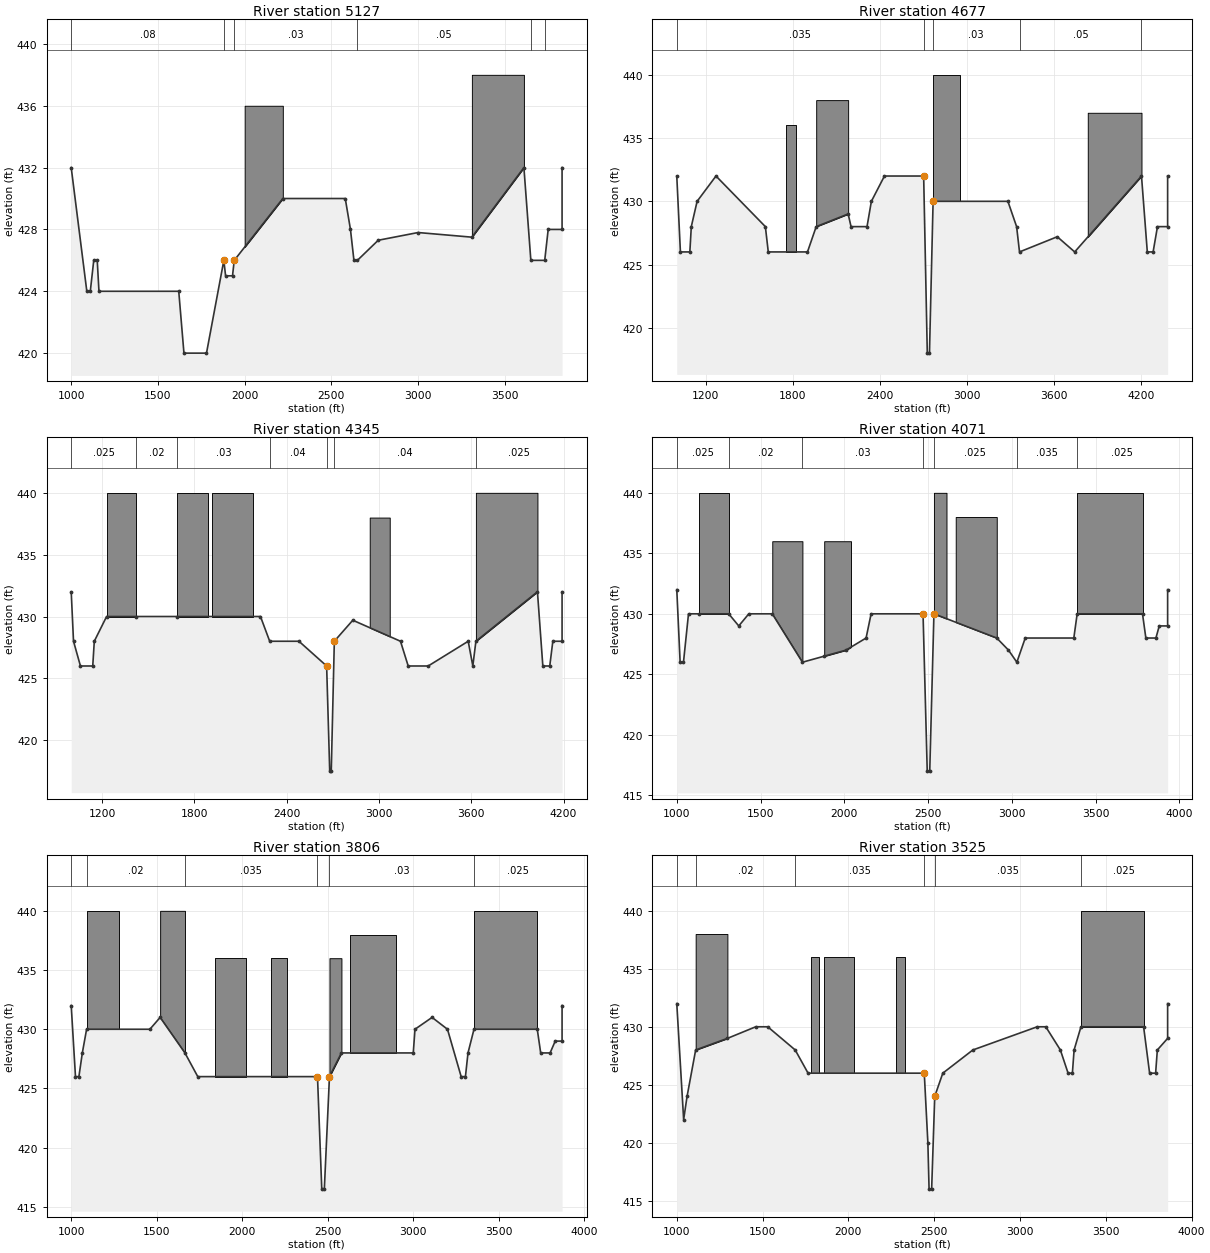
Type RM Length L Ch R = 1 ,5127    ,440,450,240
BEGIN DESCRIPTION:
This cross section corresponds to cross section 5127 of the non-georeferenced CDC model which was the source of this model.
END DESCRIPTION:
XS GIS Cut Line= 2
2459271.896777247005197.728205292457195.246403017003275.11951771
#Sta/Elev= 27
    1000     432    1090     424    1110     424    1130     426    1150     426
    1160     424    1620     424    1650     420    1780     420    1880     426
    1890     425    1930     425    1940     426    2220     430    2580     430
    2610     428    2630     426    2650     426    2770   427.3    3000   427.8
    3310   427.5    3610     432    3650     426    3730     426    3750     428
    3830     428    3830     432
#Mann= 6 ,-1,0
    1000     .08       0    1880    .025       0    1940     .03       0
    2650     .05       0    3650     .02       0    3730     .04       0
#Block Obstruct= 2 ,-1
    2000    2220     436    3310    3610     438
Bank Sta=1880,1940
XS Rating Curve= 0 ,0
Exp/Cntr=0.3,0.1

Type RM Length L Ch R = 1 ,4677    ,349,331,190
BEGIN DESCRIPTION:
This cross section corresponds to cross section 4677 of the non-georeferenced CDC model which was the source of this model.
END DESCRIPTION:
XS GIS Cut Line= 5
2460132.002668597004910.78324114 2459424.57888667004682.24006306
2458600.146152267004123.669001712457523.919958267003389.42998463
2457203.595467697003281.85014731
#Sta/Elev= 30
    1000     432    1025     426    1090     426    1100     428    1140     430
    1270     432    1610     428    1630     426    1900     426    1960     428
    2180     429    2200     428    2310     428    2340     430    2430     432
    2700     432    2725     418    2740     418    2765     430    3280     430
    3340     428    3360     426    3620   427.2    3740     426    4200     432
    4240     426    4280     426    4310     428    4380     428    4380     432
#Mann= 5 ,-1,0
    1000    .035       0    2700    .025       0    2765     .03       0
    3360     .05       0    4200    .025       0
#Block Obstruct= 4 ,-1
    1750    1820     436    1960    2180     438    2765    2950     440
    3830    4200     437
Bank Sta=2700,2765
XS Rating Curve= 0 ,0
Exp/Cntr=0.3,0.1

Type RM Length L Ch R = 1 ,4345    ,330,274,170
BEGIN DESCRIPTION:
This cross section corresponds to cross section 4345 of the non-georeferenced CDC model which was the source of this model.
END DESCRIPTION:
XS GIS Cut Line= 4
2460121.269094267004527.358483052458599.089067767003790.60995655
2457748.655073087003384.786949312457210.331674677003243.34070988
#Sta/Elev= 28
    1000     432    1015     428    1060     426    1140     426    1150     428
    1230     430    1420     430    1690     430    2230     430    2290     428
    2480     428    2660     426    2680   417.5    2690   417.5    2710     428
    2830   429.7    3140     428    3190     426    3320     426    3580     428
    3610     426    3630     428    4030     432    4065     426    4110     426
    4130     428    4190     428    4190     432
#Mann= 7 ,-1,0
    1000    .025       0    1420     .02       0    1690     .03       0
    2290     .04       0    2660    .025       0    2710     .04       0
    3630    .025       0
#Block Obstruct= 5 ,-1
    1230    1420     440    1690    1890     440    1915    2180     440
    2940    3070     438    3630    4030     440
Bank Sta=2660,2710
XS Rating Curve= 0 ,0
Exp/Cntr=0.3,0.1

Type RM Length L Ch R = 1 ,4071    ,338,264,189
BEGIN DESCRIPTION:
This cross section corresponds to cross section 4071 of the non-georeferenced CDC model which was the source of this model.
END DESCRIPTION:
XS GIS Cut Line= 3
 2460052.31582017003932.686444042457750.880134257003277.21597022
2457224.037683997003173.04819955
#Sta/Elev= 30
    1000     432    1020     426    1040     426    1070     430    1130     430
    1310     430    1370     429    1430     430    1570     430    1750     426
    1880   426.5    2010     427    2130     428    2160     430    2470     430
    2495     417    2510     417    2535     430    2910     428    2980     427
    3030     426    3080     428    3370     428    3390     430    3780     430
    3800     428    3860     428    3880     429    3930     429    3930     432
#Mann= 7 ,-1,0
    1000    .025       0    1310     .02       0    1750     .03       0
    2470    .025       0    2535    .025       0    3030    .035       0
    3390    .025       0
#Block Obstruct= 6 ,-1
    1130    1310     440    1570    1750     436    1880    2040     436
    2535    2610     440    2665    2910     438    3390    3780     440
Bank Sta=2470,2535
XS Rating Curve= 0 ,0
Exp/Cntr=0.3,0.1

Type RM Length L Ch R = 1 ,3806    ,371,282,221
BEGIN DESCRIPTION:
This cross section corresponds to cross section 3806 of the non-georeferenced CDC model which was the source of this model.
END DESCRIPTION:
XS GIS Cut Line= 3
2460060.824005197003478.478034882457730.219086357003124.53222047
2457219.985526747003074.59760904
#Sta/Elev= 28
    1000     432    1025     426    1045     426    1065     428    1090     430
    1460     430    1520     431    1665     428    1740     426    2440     426
    2465   416.5    2480   416.5    2510     426    2580     428    3000     428
    3010     430    3110     431    3200     430    3280     426    3305     426
    3320     428    3355     430    3725     430    3745     428    3800     428
    3830     429    3870     429    3870     432
#Mann= 6 ,-1,0
    1000    .025       0    1090     .02       0    1665    .035       0
    2440    .025       0    2510     .03       0    3355    .025       0
#Block Obstruct= 7 ,-1
    1090    1280     440    1520    1665     440    1840    2020     436
    2170    2260     436    2510    2580     436    2630    2900     438
    3355    3725     440
Bank Sta=2440,2510
XS Rating Curve= 0 ,0
Exp/Cntr=0.3,0.1

Type RM Length L Ch R = 1 ,3525    ,339,336,324
BEGIN DESCRIPTION:
This cross section corresponds to cross section 3525 of the non-georeferenced CDC model which was the source of this model.
END DESCRIPTION:
XS GIS Cut Line= 3
 2460081.37284867003017.559009212458610.531958257002975.42195438
2457222.637424357002932.57394296
#Sta/Elev= 29
    1000     432    1040     422    1060     424    1110     428    1295     429
    1460     430    1530     430    1690     428    1765     426    2442     426
    2463     420    2470     416    2485     416    2503     424    2550     426
    2725     428    3100     430    3150     430    3235     428    3280     426
    3305     426    3315     428    3355     430    3720     430    3755     426
    3790     426    3800     428    3860     429    3860     432
#Mann= 6 ,-1,0
    1000    .025       0    1110     .02       0    1690    .035       0
    2442    .025       0    2503    .035       0    3355    .025       0
#Block Obstruct= 5 ,-1
    1110    1295     438    1780    1830     436    1855    2035     436
    2280    2330     436    3355    3720     440
Bank Sta=2442,2503
XS Rating Curve= 0 ,0
Exp/Cntr=0.3,0.1

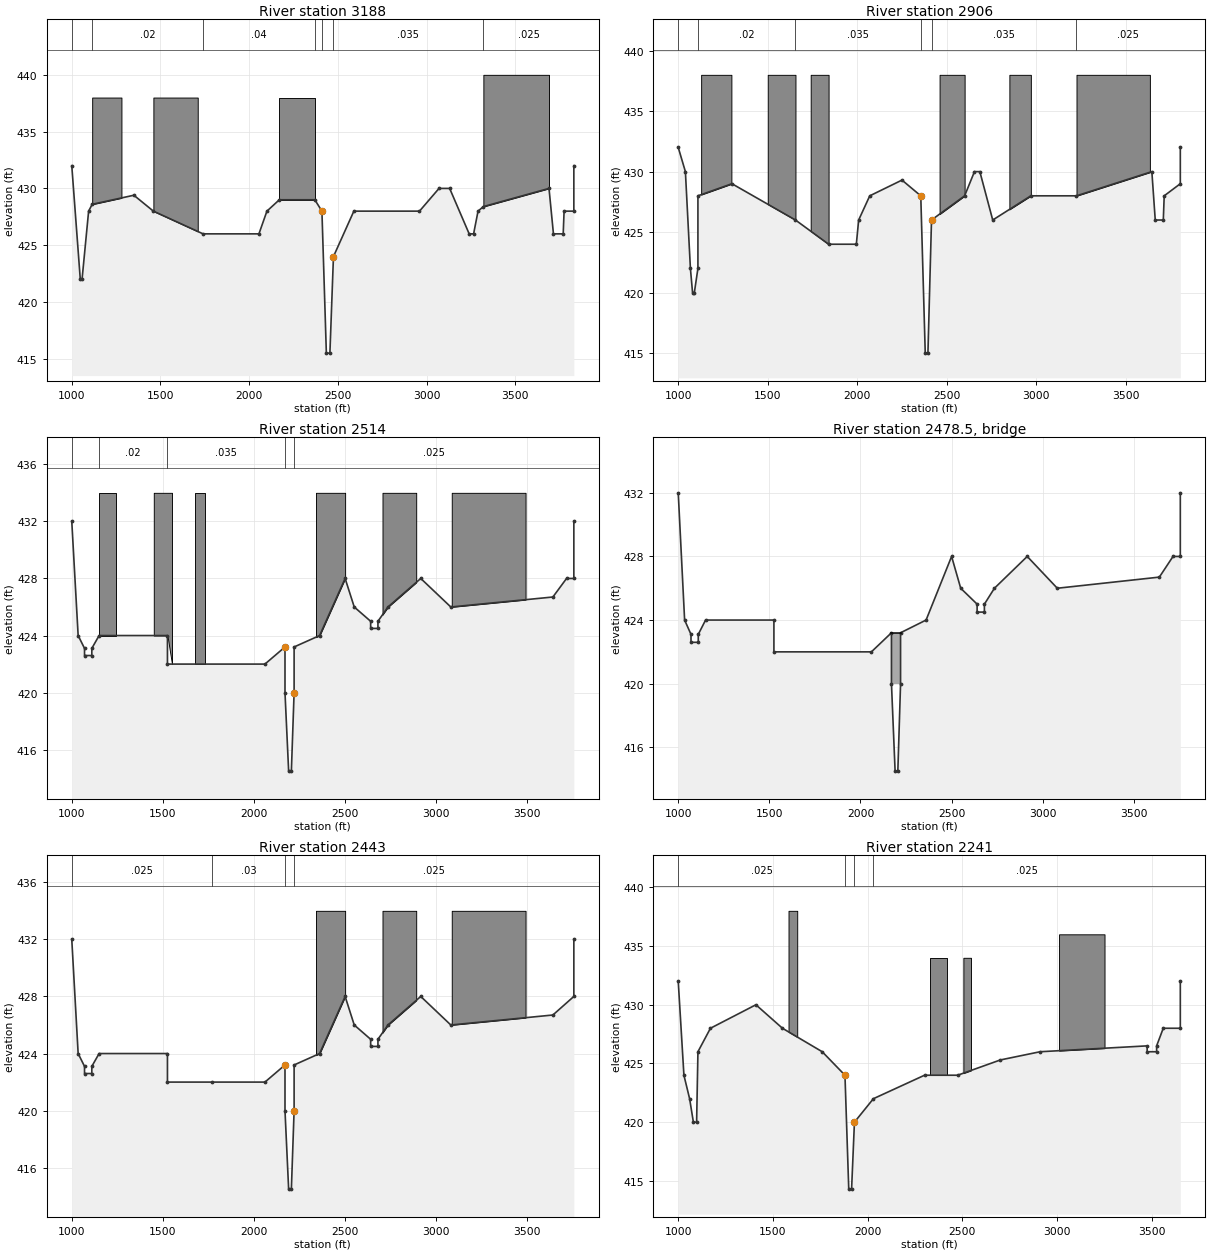
Type RM Length L Ch R = 1 ,3188    ,291,283,271
BEGIN DESCRIPTION:
This cross section corresponds to cross section 3188 of the non-georeferenced CDC model which was the source of this model.
END DESCRIPTION:
XS GIS Cut Line= 3
2460056.792845257002668.427817722458681.387131517002640.37898929
2457227.311955667002614.34032747
#Sta/Elev= 30
    1000     432    1048     422    1058     422    1095     428    1115   428.6
    1350   429.4    1460     428    1740     426    2055     426    2100     428
    2170     429    2370     429    2410     428    2435   415.5    2455   415.5
    2475     424    2590     428    2960     428    3070     430    3130     430
    3240     426    3265     426    3290     428    3320   428.4    3690     430
    3715     426    3770     426    3775     428    3830     428    3830     432
#Mann= 7 ,-1,0
    1000    .025       0    1115     .02       0    1740     .04       0
    2370     .03       0    2410    .025       0    2475    .035       0
    3320    .025       0
#Block Obstruct= 4 ,-1
    1115    1280     438    1460    1710     438    2170    2370     438
    3320    3690     440
Bank Sta=2410,2475
XS Rating Curve= 0 ,0
Exp/Cntr=0.3,0.1

Type RM Length L Ch R = 1 ,2906    ,370,392,330
BEGIN DESCRIPTION:
This cross section corresponds to cross section 2906 of the non-georeferenced CDC model which was the source of this model.
END DESCRIPTION:
XS GIS Cut Line= 2
2459994.546906777002351.267034712457189.563999687002361.02587347
#Sta/Elev= 30
    1000     432    1040     430    1068     422    1080     420    1090     420
    1110     422    1110     428    1300     429    1655     426    1840     424
    1995     424    2008     426    2070     428    2250   429.3    2355     428
    2380     415    2395     415    2415     426    2600     428    2655     430
    2685     430    2757     426    2970     428    3225     428    3646     430
    3665     426    3710     426    3715     428    3805     429    3805     432
#Mann= 6 ,-1,0
    1000    .025       0    1110     .02       0    1655    .035       0
    2355    .025       0    2415    .035       0    3225    .025       0
#Block Obstruct= 6 ,-1
    1128    1297     438    1500    1655     438    1740    1840     438
    2460    2600     438    2850    2970     438    3225    3635     438
Bank Sta=2355,2415
XS Rating Curve= 0 ,0
Exp/Cntr=0.3,0.1

Type RM Length L Ch R = 1 ,2514    ,71,71,71
BEGIN DESCRIPTION:
This cross section corresponds to cross section 2514 of the non-georeferenced CDC model which was the source of this model.
Upstream bounding cross section for Lombardy Lane bridge
END DESCRIPTION:
XS GIS Cut Line= 4
2459850.826393667001987.409166632458632.215970017001973.51713406
  2457152.7228667002317.915723472457135.911219847002321.82910147
#Sta/Elev= 30
    1000     432    1035     424    1070   423.1    1070   422.6    1110   422.6
    1110   423.1    1150     424    1525     424    1525     422    2060     422
    2170   423.2    2170     420    2190   414.5    2205   414.5    2220     420
    2220   423.2    2360     424    2500     428    2550     426    2640     425
    2640   424.5    2680   424.5    2680     425    2735     426    2915     428
    3080     426    3640   426.7    3715     428    3755     428    3755     432
#Mann= 5 ,-1,0
    1000    .025       0    1150     .02       0    1525    .035       0
    2170    .025       0    2220    .025       0
#Block Obstruct= 6 ,-1
    1150    1240     434    1450    1550     434    1675    1730     434
    2340    2500     434    2705    2890     434    3085    3490     434
Bank Sta=2170,2220
XS Rating Curve= 0 ,0
Exp/Cntr=0.3,0.1

Type RM Length L Ch R = 3 ,2478.5  ,,,
BEGIN DESCRIPTION:
Lombardy Lane
END DESCRIPTION:
Node Name=Lombardy Lane
Bridge Culvert--1,0,-1,-1, 0
Deck Dist Width WeirC Skew NumUp NumDn MinLoCord MaxHiCord MaxSubmerge Is_Ogee
1,69,2.6,0, 2, 2, , , 0.95, 0, 0,0,,
    2170    2220
   423.2   423.2
     420     420
    2170    2220
   423.2   423.2
     420     420
BR Coef=-1 , 0 , 0 ,, 0 ,,,0.8,-1,,0,
WSPro=,,,, 1 ,,,, 0 ,,,, 0 ,,,,-1 ,-1 ,-1 , 0 , 0 , 0 , 0 , 0
BC Design=,, 0 ,, 0 ,,,,,,
BC HTab HWMax=432
BC Use User HTab Curves=0
BC User HTab FreeFlow(D)= 0

Type RM Length L Ch R = 1 ,2443    ,239,202,140
BEGIN DESCRIPTION:
This cross section corresponds to cross section 2243 of the non-georeferenced CDC model which was the source of this model.
Downstream bounding cross section for Lombardy Lane bridge
END DESCRIPTION:
XS GIS Cut Line= 5
2459889.651119177001926.708172542458668.732957337001912.19704671
2458166.184749847002033.626265792458166.170642267002033.62889047
2457177.647684937002272.48438388
#Sta/Elev= 30
    1000     432    1035     424    1070   423.1    1070   422.6    1110   422.6
    1110   423.1    1150     424    1525     424    1525     422    1770     422
    2060     422    2170   423.2    2170     420    2190   414.5    2205   414.5
    2220     420    2220   423.2    2360     424    2500     428    2550     426
    2640     425    2640   424.5    2680   424.5    2680     425    2735     426
    2915     428    3080     426    3640   426.7    3755     428    3755     432
#Mann= 4 ,-1,0
    1000    .025       0    1770     .03       0    2170    .035       0
    2220    .025       0
#Block Obstruct= 3 ,-1
    2340    2500     434    2705    2890     434    3085    3490     434
Bank Sta=2170,2220
XS Rating Curve= 0 ,0
Exp/Cntr=0.3,0.1

Type RM Length L Ch R = 1 ,2241    ,210,206,120
BEGIN DESCRIPTION:
This cross section corresponds to cross section 2241 of the non-georeferenced CDC model which was the source of this model.
END DESCRIPTION:
XS GIS Cut Line= 5
2459736.78397083 7001594.50903382458410.805979767001831.38421622
2458247.243970937001876.353942542457711.441892927002016.01868947
2457150.49288359 7002162.2382133
#Sta/Elev= 26
    1000     432    1030     424    1060     422    1080     420    1097     420
    1104     426    1170     428    1410     430    1550     428    1760     426
    1880     424    1900   414.3    1915   414.3    1930     420    2030     422
    2300     424    2475     424    2700   425.3    2910     426    3475   426.5
    3475     426    3525     426    3525   426.5    3560     428    3650     428
    3650     432
#Mann= 4 ,-1,0
    1000    .025       0    1880     .04       0    1930     .07       0
    2030    .025       0
#Block Obstruct= 4 ,-1
    1582    1628     438    2330    2420     434    2505    2545     434
    3010    3250     436
Bank Sta=1880,1930
XS Rating Curve= 0 ,0
Exp/Cntr=0.3,0.1

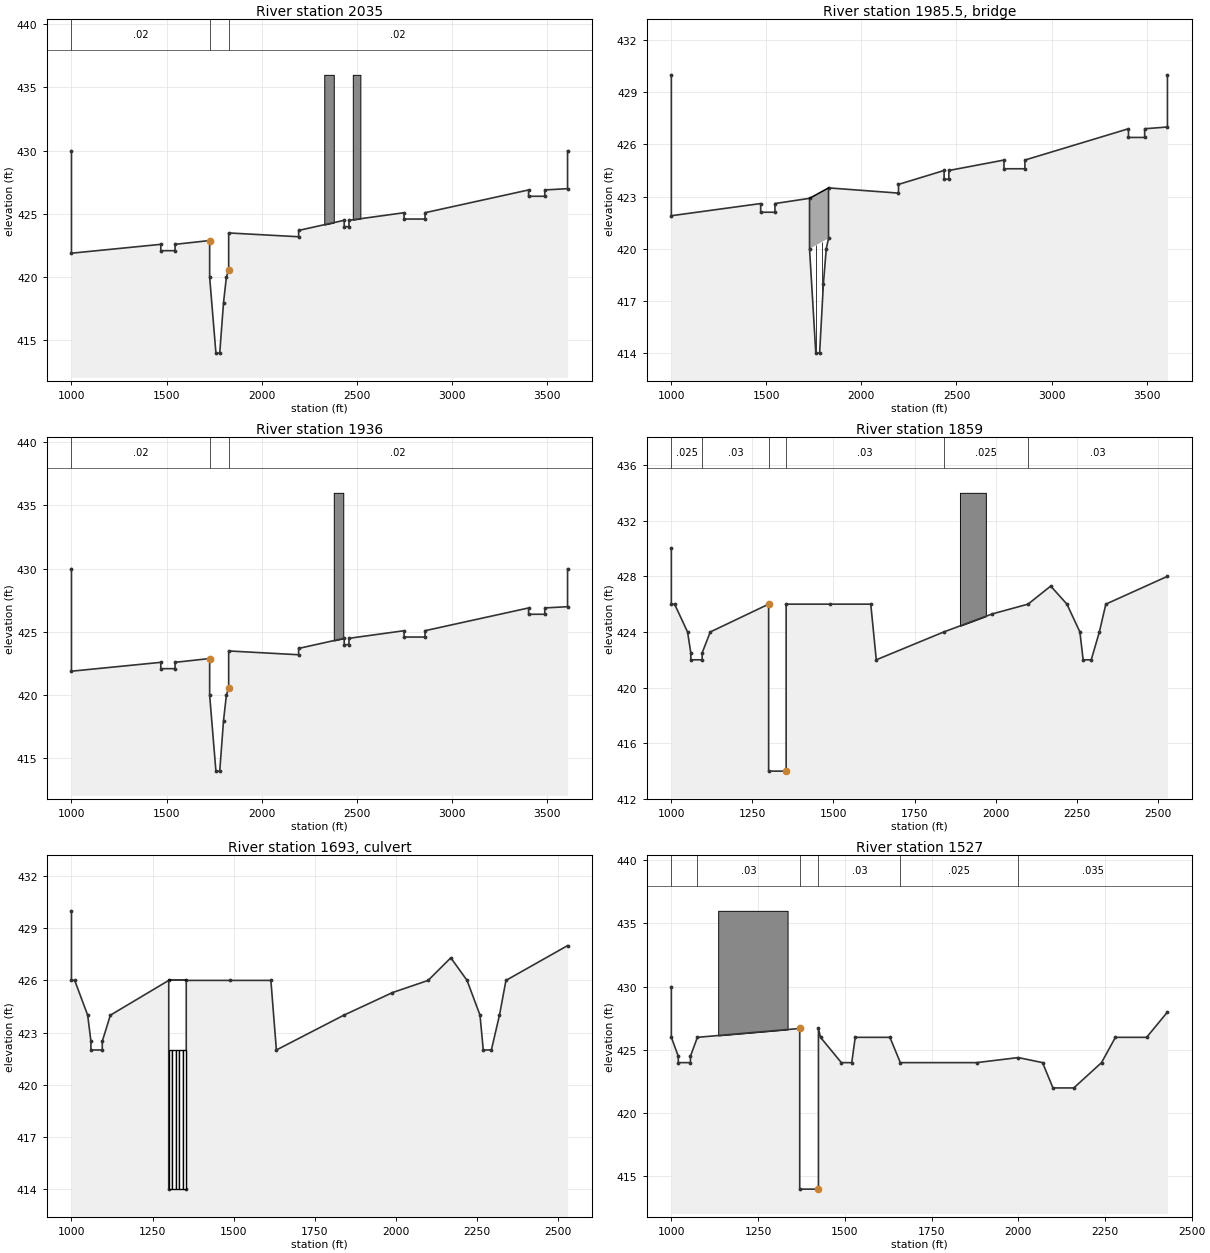
Type RM Length L Ch R = 1 ,2035    ,100,100,100
BEGIN DESCRIPTION:
This cross section corresponds to cross section 2035 of the non-georeferenced CDC model which was the source of this model.
Upstream bounding cross section for SH 348/Northwest Highway bridge
END DESCRIPTION:
XS GIS Cut Line= 6
2459627.049938357001305.04307731 2459145.04007567001483.89606605
 2459002.6738905 7001533.13317232458456.552935517001741.61208604
2458229.431998677001822.451163222457146.04833868 7002104.7540763
#Sta/Elev= 30
    1000     430    1000   421.9    1470   422.6    1470   422.1    1545   422.1
    1545   422.6    1727   422.9    1727     420    1760     414    1780     414
    1800     418    1815     420    1827   420.6    1827   423.5    2195   423.2
    2195   423.7    2435   424.5    2435     424    2460     424    2460   424.5
    2750   425.1    2750   424.6    2860   424.6    2860   425.1    3405   426.9
    3405   426.4    3490   426.4    3490   426.9    3610     427    3610     430
#Mann= 3 ,-1,0
    1000     .02       0    1727     .03       0    1827     .02       0
#Block Obstruct= 2 ,-1
    2330    2380     436    2480    2520     436
Bank Sta=1727,1827
XS Rating Curve= 0 ,0
Exp/Cntr=0.3,0.1

Type RM Length L Ch R = 3 ,1985.5  ,,,
BEGIN DESCRIPTION:
State Highway 348/Northwest Highway
END DESCRIPTION:
Node Name=Northwest Highwa
Bridge Culvert--1,0,-1,-1, 0
Deck Dist Width WeirC Skew NumUp NumDn MinLoCord MaxHiCord MaxSubmerge Is_Ogee
2,96,2.6,0, 2, 2, , , 0.95, 0, 0,0,,
    1727    1827
   422.9   423.5
     420   420.6
    1727    1827
   422.9   423.5
     420   420.6
Pier Skew, UpSta & Num, DnSta & Num=  ,1760, 2 ,1760, 2 , 0 , 0 , 0 ,,
       2       2
     400     422
       2       2
     400     422
Pier Skew, UpSta & Num, DnSta & Num=  ,1794, 2 ,1794, 2 , 0 , 0 , 0 ,,
       2       2
     400     422
       2       2
     400     422
BR Coef=-1 , 0 , 0 ,, 0 ,,,0.8,-1,,0,
WSPro=,,,, 1 ,,,, 0 ,,,, 0 ,,,,-1 ,-1 ,-1 , 0 , 0 , 0 , 0 , 0
BC Design=,, 0 ,, 0 ,,,,,,
BC HTab HWMax=430
BC Use User HTab Curves=0
BC User HTab FreeFlow(D)= 0

Type RM Length L Ch R = 1 ,1936    ,76,76,76
BEGIN DESCRIPTION:
This cross section corresponds to cross section 1936 of the non-georeferenced CDC model which was the source of this model.
Downstream bounding cross section for SH 348/Northwest Highway bridge
END DESCRIPTION:
XS GIS Cut Line= 6
2459590.126127667001210.093135972459106.108066837001389.72597881
2458490.092894677001624.34821297 2458202.66007067001735.66196671
 2457663.98595117001939.199945462457128.039188337002064.76170221
#Sta/Elev= 30
    1000     430    1000   421.9    1470   422.6    1470   422.1    1545   422.1
    1545   422.6    1727   422.9    1727     420    1760     414    1780     414
    1800     418    1815     420    1827   420.6    1827   423.5    2195   423.2
    2195   423.7    2435   424.5    2435     424    2460     424    2460   424.5
    2750   425.1    2750   424.6    2860   424.6    2860   425.1    3405   426.9
    3405   426.4    3490   426.4    3490   426.9    3610     427    3610     430
#Mann= 3 ,-1,0
    1000     .02       0    1727     .03       0    1827     .02       0
#Block Obstruct= 1 ,-1
    2380    2430     436
Bank Sta=1727,1827
XS Rating Curve= 0 ,0
Exp/Cntr=0.3,0.1

Type RM Length L Ch R = 1 ,1859    ,331,333,220
BEGIN DESCRIPTION:
This cross section corresponds to cross section 1859 of the non-georeferenced CDC model which was the source of this model.
Upstream end of 5 cell box culvert (8'W x 10'H )
END DESCRIPTION:
XS GIS Cut Line= 3
2459109.734043847001282.172060042458792.49583316 7001441.2081593
2457854.378286847001741.46969788
#Sta/Elev= 27
    1000     430    1000     426    1010     426    1050     424    1060   422.5
    1060     422    1095     422    1095   422.5    1120     424    1300     426
    1300     414    1354     414    1354     426    1490     426    1615     426
    1632     422    1840     424    1990   425.3    2100     426    2170   427.3
    2220     426    2260     424    2270     422    2295     422    2320     424
    2340     426    2530     428
#Mann= 6 ,-1,0
    1000    .025       0    1095     .03       0    1300    .025       0
    1354     .03       0    1840    .025       0    2100     .03       0
#Block Obstruct= 1 ,-1
    1890    1970     434
Bank Sta=1300,1354
XS Rating Curve= 0 ,0
Exp/Cntr=0.3,0.1

Type RM Length L Ch R = 2 ,1693    ,,,
BEGIN DESCRIPTION:
5 cell concrete box culvert (5-8'hx10'w )
END DESCRIPTION:
Node Name=culvert
Bridge Culvert--1,0,-1,-1, 0
Deck Dist Width WeirC Skew NumUp NumDn MinLoCord MaxHiCord MaxSubmerge Is_Ogee
1,330,2.6,0, 2, 2, , , 0.95, 0, 0,0,,
    1300    1354
     426     426
    1370    1424
   426.7   426.7
Multiple Barrel Culv=2,8,10,328,0.016,0.5,1,11,3,414,414, 5,Culvert #1  , 0 ,1
    1305    1375    1316    1386    1327    1397    1338    1408    1349    1419
BC Culvert Barrel=1,Barrel #1,0
BC Culvert Barrel=2,Barrel #2,0
BC Culvert Barrel=3,Barrel #3,0
BC Culvert Barrel=4,Barrel #4,0
BC Culvert Barrel=5,Barrel #5,0
Culvert Bottom n=0.016
BC Design=,, 0 ,, 0 ,,,,,,
BC HTab HWMax=430
BC Use User HTab Curves=0
BC User HTab FreeFlow(D)= 0

Type RM Length L Ch R = 1 ,1527    ,400,458,300
BEGIN DESCRIPTION:
This cross section corresponds to cross section 1510 of the non-georeferenced CDC model which was the source of this model.
Downstream end of 5 cell box culvert (8'H x 10'W)
END DESCRIPTION:
XS GIS Cut Line= 3
2458889.712830337001010.939006722458541.642988417001247.25021388
2457716.17022991 7001716.0245388
#Sta/Elev= 26
    1000     430    1000     426    1020   424.5    1020     424    1055     424
    1055   424.5    1075     426    1370   426.7    1370     414    1424     414
    1424   426.7    1430     426    1490     424    1520     424    1530     426
    1630     426    1660     424    1880     424    2000   424.4    2070     424
    2100     422    2160     422    2240     424    2280     426    2370     426
    2430     428
#Mann= 6 ,-1,0
    1000    .025       0    1075     .03       0    1370     .02       0
    1424     .03       0    1660    .025       0    2000    .035       0
#Block Obstruct= 1 ,-1
    1135    1335     436
Bank Sta=1370,1424
XS Rating Curve= 0 ,0
Exp/Cntr=0.3,0.1

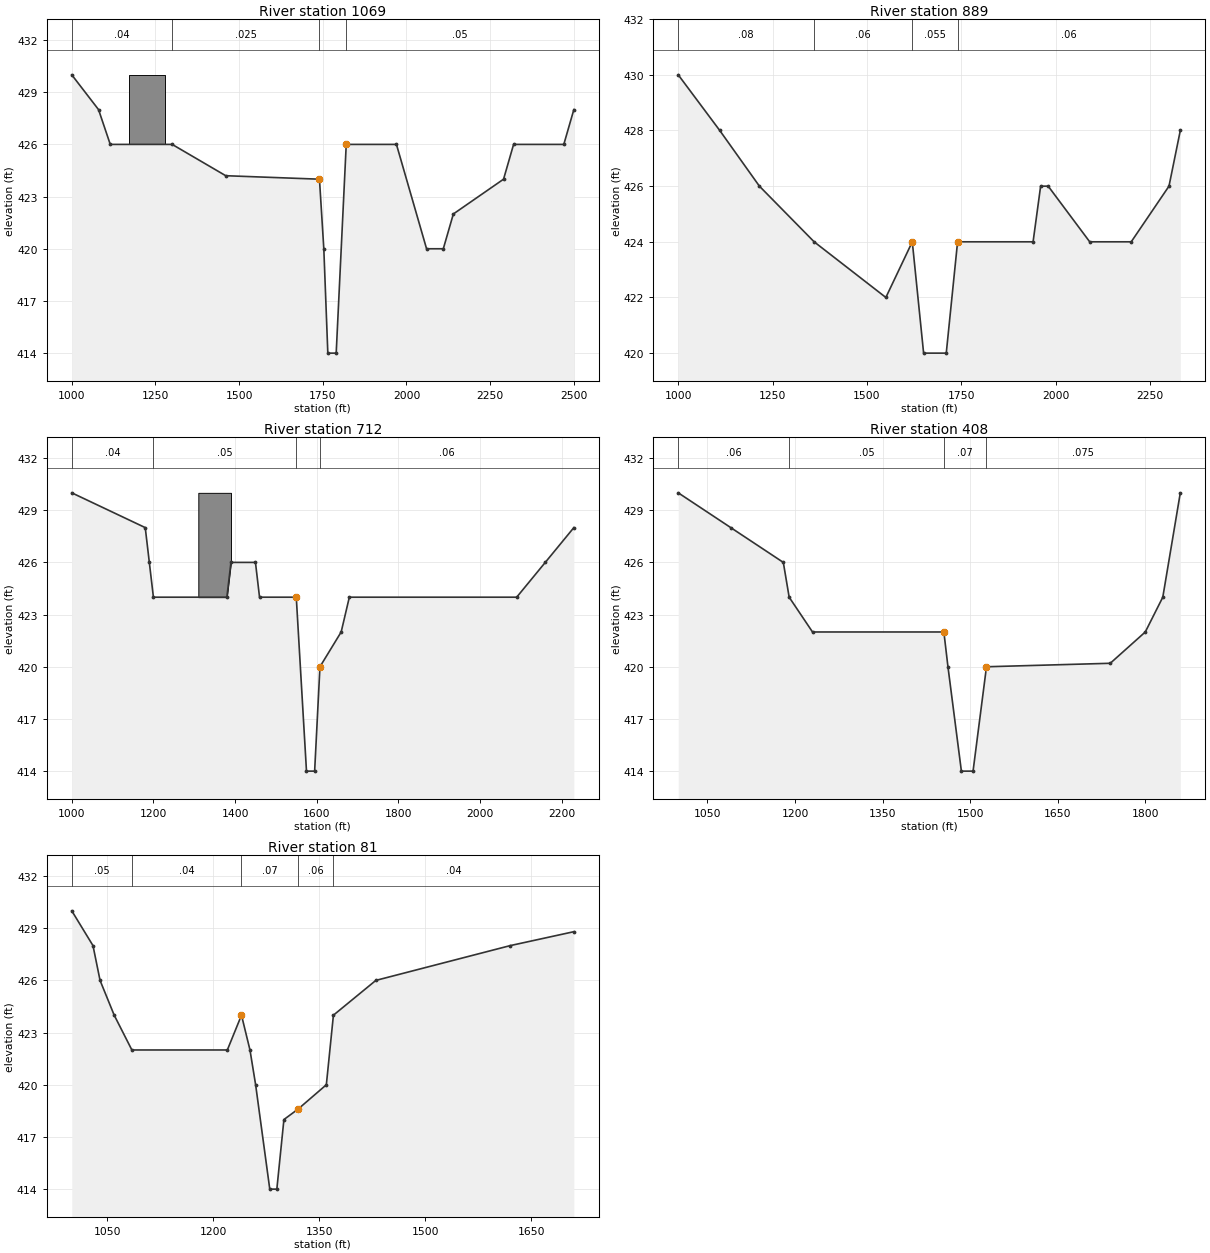
Type RM Length L Ch R = 1 ,1069    ,260,180,110
BEGIN DESCRIPTION:
This cross section corresponds to cross section 1069 of the non-georeferenced CDC model which was the source of this model.
END DESCRIPTION:
XS GIS Cut Line= 2
2458594.765913677000559.849029632457690.085636447001718.49205355
#Sta/Elev= 18
    1000     430    1080     428    1115     426    1300     426    1460   424.2
    1740     424    1753     420    1765     414    1790     414    1820     426
    1970     426    2060     420    2110     420    2140     422    2290     424
    2320     426    2470     426    2500     428
#Mann= 4 ,-1,0
    1000     .04       0    1300    .025       0    1740     .04       0
    1820     .05       0
#Block Obstruct= 1 ,-1
    1170    1280     430
Bank Sta=1740,1820
XS Rating Curve= 0 ,0
Exp/Cntr=0.3,0.1

Type RM Length L Ch R = 1 ,889     ,177,177,177
BEGIN DESCRIPTION:
This cross section corresponds to cross section 889 of the non-georeferenced CDC model which was the source of this model.
END DESCRIPTION:
XS GIS Cut Line= 3
2458161.806149667000531.314965962457929.777086177001175.21918997
  2457618.6904387001706.39365254
#Sta/Elev= 16
    1000     430    1110     428    1215     426    1360     424    1550     422
    1620     424    1650     420    1710     420    1740     424    1940     424
    1960     426    1980     426    2090     424    2200     424    2300     426
    2330     428
#Mann= 4 ,-1,0
    1000     .08       0    1360     .06       0    1620    .055       0
    1740     .06       0
Bank Sta=1620,1740
XS Rating Curve= 0 ,0
Exp/Cntr=0.3,0.1

Type RM Length L Ch R = 1 ,712     ,280,304,290
BEGIN DESCRIPTION:
This cross section corresponds to cross section 712 of the non-georeferenced CDC model which was the source of this model.
END DESCRIPTION:
XS GIS Cut Line= 3
2457885.36411726 7000567.13707282457838.728055697001008.64898504
2457457.022454267001614.45650047
#Sta/Elev= 17
    1000     430    1180     428    1190     426    1200     424    1380     424
    1390     426    1450     426    1460     424    1550     424    1575     414
    1595     414    1608     420    1660     422    1680     424    2090     424
    2160     426    2230     428
#Mann= 4 ,-1,0
    1000     .04       0    1200     .05       0    1550    .065       0
    1608     .06       0
#Block Obstruct= 1 ,-1
    1310    1390     430
Bank Sta=1550,1608
XS Rating Curve= 0 ,0
Exp/Cntr=0.3,0.1

Type RM Length L Ch R = 1 ,408     ,300,327,350
BEGIN DESCRIPTION:
This cross section corresponds to cross section 408 of the non-georeferenced CDC model which was the source of this model.
END DESCRIPTION:
XS GIS Cut Line= 2
2457724.418901097000584.181986212457317.52076477 7001307.6001588
#Sta/Elev= 14
    1000     430    1090     428    1180     426    1190     424    1230     422
    1455     422    1462     420    1485     414    1505     414    1528     420
    1740   420.2    1800     422    1830     424    1860     430
#Mann= 4 ,-1,0
    1000     .06       0    1190     .05       0    1455     .07       0
    1528    .075       0
Bank Sta=1455,1528
XS Rating Curve= 0 ,0
Exp/Cntr=0.3,0.1

Type RM Length L Ch R = 1 ,81      ,0,0,0
BEGIN DESCRIPTION:
This cross section corresponds to cross section 81 of the non-georeferenced CDC model which was the source of this model.
END DESCRIPTION:
XS GIS Cut Line= 2
2457383.519976597000616.041174472457006.568630757001108.28887764
#Sta/Elev= 18
    1000     430    1030     428    1040     426    1060     424    1085     422
    1220     422    1240     424    1252     422    1260     420    1280     414
    1290     414    1300     418    1320   418.6    1360     420    1370     424
    1430     426    1620     428    1710   428.8
#Mann= 5 ,-1,0
    1000     .05       0    1085     .04       0    1240     .07       0
    1320     .06       0    1370     .04       0
Bank Sta=1240,1320
XS Rating Curve= 0 ,0
Exp/Cntr=0.3,0.1

River Reach=West Fork       ,wf3
Reach XY= 30
       2346473.9        6963584.      2345494.34      6966352.98
      2346286.59      6968259.29      2350023.34      6968003.69
       2354512.4      6965894.36      2355330.74      6967716.62
      2359871.65      6970041.49      2363096.49      6969184.51
      2365532.14      6970407.58      2366189.04      6971823.97
      2365252.88      6972579.18      2367613.99      6972950.01
      2367619.48       6974853.9      2369582.09      6972823.37
      2372792.67      6972522.24      2376551.53      6968098.36
      2380668.89      6967549.98      2381491.36      6966391.92
      2382440.84      6968870.18       2383593.3      6968002.34
      2384725.84      6969858.66       2385600.2      6969508.62
      2385877.69      6972305.46      2387730.11       6971519.9
      2387123.85      6974369.92      2389461.82      6975900.01
      2395299.96      6974224.43      2396899.94      6975052.14
      2396212.76      6973722.55      2398149.68       6972930.3