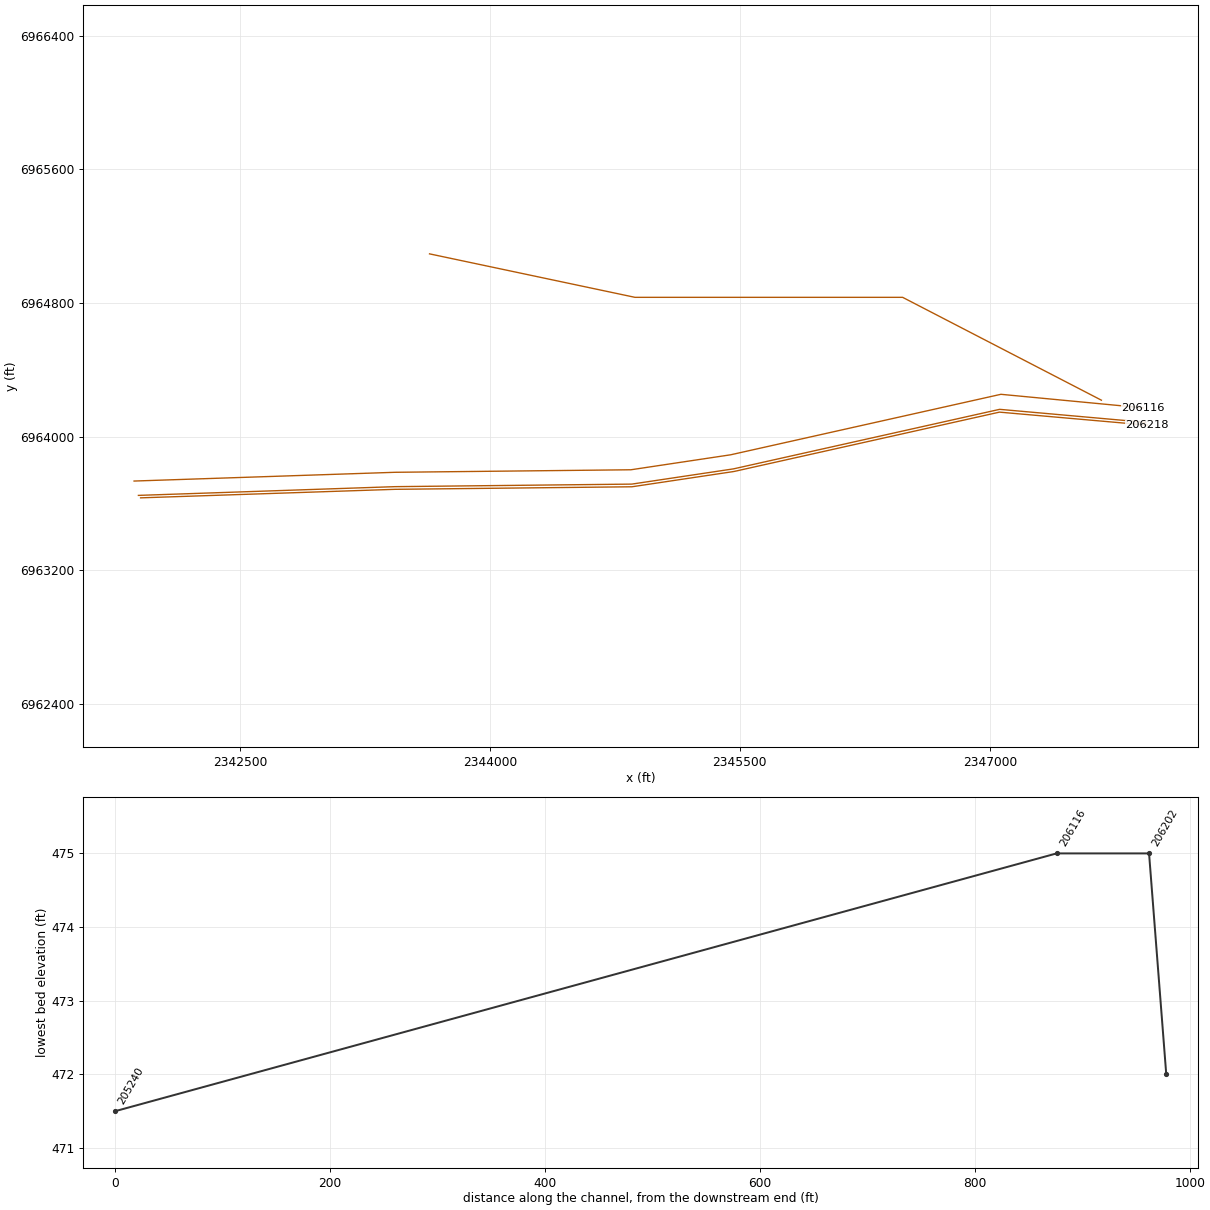
HEC-RAS study CDC_Consolidated_Model.prj: Upper Trinity CDC Consolidated Model

--- CDC_Consolidated_Model.g12 (geometry) --- (continued)

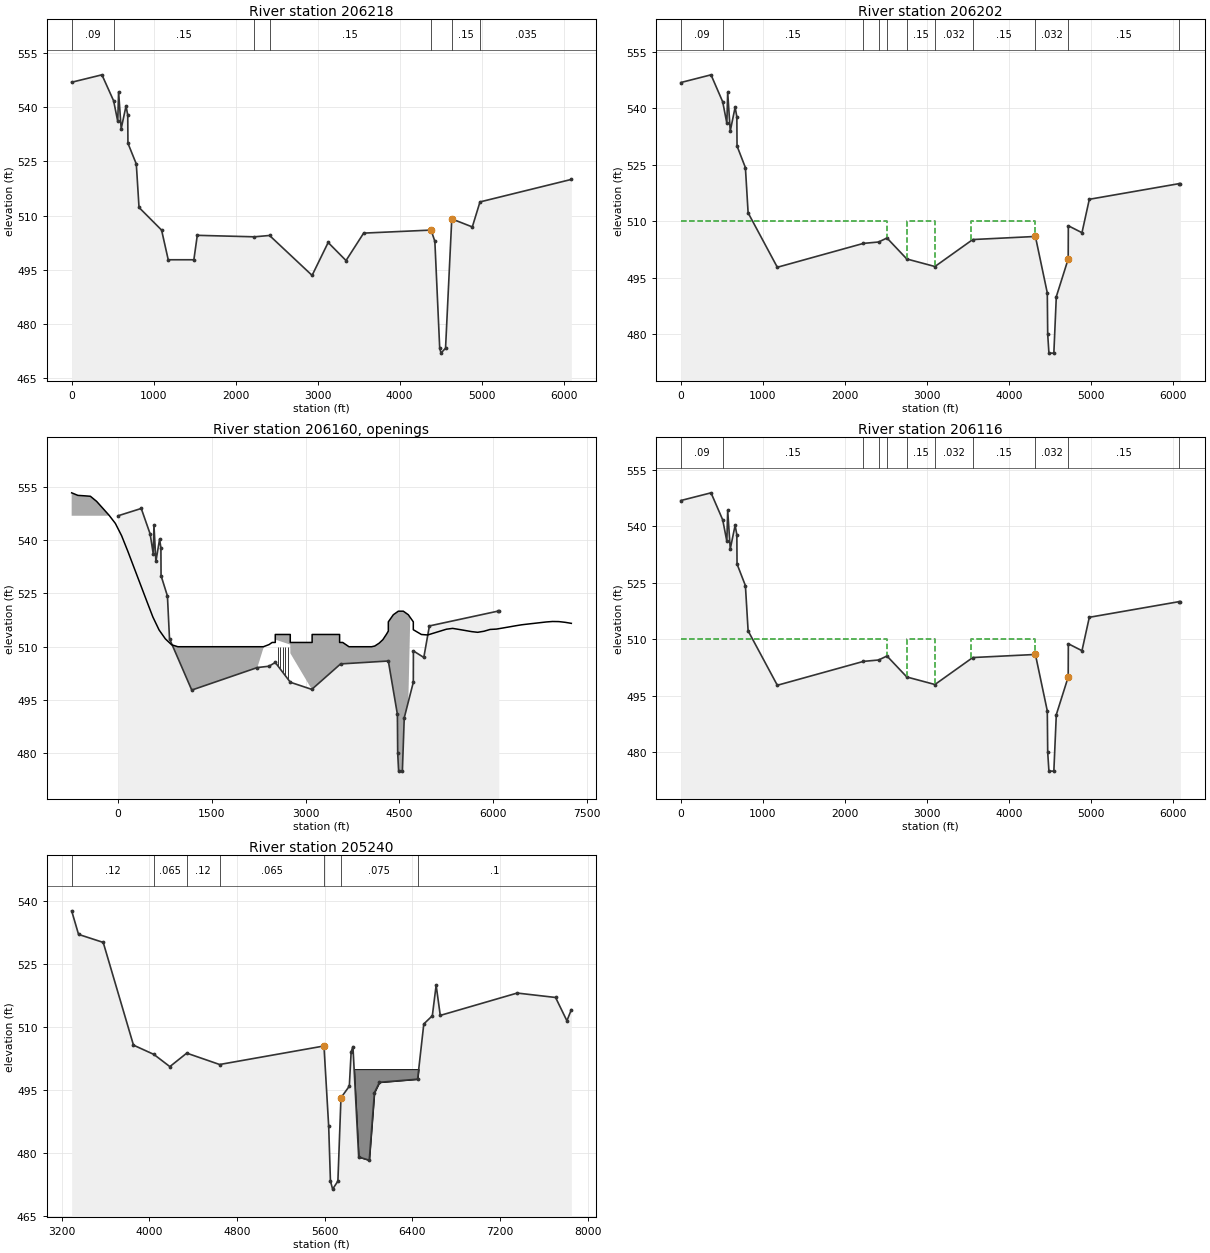
Type RM Length L Ch R = 1 ,206218  ,16,16,16
BEGIN DESCRIPTION:
This cross section corresponds to cross section 206218 of the non-georeferenced CDC model which was the source of this model.
Downstream of East 1st Street.
END DESCRIPTION:
XS GIS Cut Line= 6
  2341904.095961 6963632.5437376   2343430.68391   6963683.60684
     2344852.789   6963698.88109   2345465.41508   6963790.52001
   2347058.22685   6964146.11608      2347944.51      6964068.28
#Sta/Elev= 30
       0  546.85  369.23   548.9  512.04  541.71  562.18  536.03  572.53  544.23
  603.81  533.98  663.08  540.28  684.12  537.77  686.41     530  788.51  524.26
  821.63  512.25 1096.67     506  1177.8   497.8 1490.48   497.8  1532.1  504.55
 2227.97  504.14 2413.28  504.51 2932.16  493.48 3128.06  502.57 3345.99  497.58
 3560.99  505.16 4383.29     506 4429.29  502.89 4488.22  473.47 4503.96     472
 4559.71  473.37 4635.51  509.09 4886.06  506.87 4979.55  513.78 6093.63     520
#Mann= 7 ,-1,0
       0     .09       0  512.04     .15       0 2227.97     .06       0
 2413.28     .15       0 4383.29    .066       0 4635.51     .15       0
 4979.55    .035       0
Bank Sta=4383.29,4635.51
XS Rating Curve= 0 ,0
Exp/Cntr=0.3,0.1

Type RM Length L Ch R = 1 ,206202  ,86,86,86
BEGIN DESCRIPTION:
Upstream bounding cross-section East 1st Street.
206202
END DESCRIPTION:
XS GIS Cut Line= 6
  2341891.061142 6963647.26742262343430.498883846963699.60684003
2344851.808137246963714.866671252345462.208898196963806.19742592
2347059.594346796964162.870387292347935.861851846964084.92095993
#Sta/Elev= 30
       0  546.85  369.23   548.9  512.04  541.71  562.18  536.03  572.53  544.23
  603.81  533.98  663.08  540.28  684.12  537.77  686.41     530  788.51  524.26
  821.63  512.25  1177.8   497.8 2227.97  504.14 2413.28  504.51    2515  505.57
 2756.74     500  3099.7     498 3560.99  505.16    4325  505.98    4470     491
    4475     480    4490     475    4550     475    4580     490    4725     500
 4726.55  508.82 4892.94  506.98 4982.56  515.85 6076.14     520 6093.63     520
#Mann= 11 ,-1,0
       0     .09       0  512.04     .15       0 2227.97     .06       0
 2413.28     .15       0    2515    .032       0 2756.74     .15       0
  3099.7    .032       0 3560.99     .15       0    4325    .032       0
 4726.55     .15       0 6076.14    .035       0
#XS Ineff= 3 ,-1
       0    2515     510    2755    3105     510    3545    4325     510
Permanent Ineff=
       F       F       F
Bank Sta=4325,4725
XS Rating Curve= 0 ,0
Exp/Cntr=0.3,0.1

Type RM Length L Ch R = 4 ,206160  ,,,
BEGIN DESCRIPTION:
East 1st Street
END DESCRIPTION:
Bridge Culvert--1,0,-1,-1, 0
Deck Dist Width WeirC Skew NumUp NumDn MinLoCord MaxHiCord MaxSubmerge Is_Ogee
5,74,2.6,0, 70, 70, , , 0.98, 0, 0,0,,
    -745    -645    -545    -445    -345    -245    -145     -45      55     155
     255     355     455     555     655     755     855     955    2325    2415
    2465    2515    2515    2755    2755    3105    3105    3545    3545    3595
    3645    3695    4058    4108    4178    4238    4298    4325    4325    4405
    4485    4565    4645    4725    4725    4855    4955    5055    5155    5255
    5355    5455    5555    5655    5755    5855    5955    6055    6155    6255
    6355    6455    6555    6655    6755    6855    6955    7055    7155    7255
   553.3  552.58  552.47  552.33  550.89  548.93  546.97  544.69  541.23  536.83
   532.2  527.58  522.95  518.38  514.71  512.22  510.56     510     510   510.6
   511.2   511.2  513.45  513.45   511.2   511.2  513.45  513.45   511.2   511.2
   510.6     510     510   510.2     511     512   513.6  514.41     517     519
     520     520     519     517  514.78  513.44  513.31  513.85  514.39  514.93
  515.16  514.87  514.57  514.26  514.06  514.35  514.86  514.96  515.26  515.56
  515.87  516.16  516.37  516.57  516.77  516.97   517.1  517.07  516.87  516.58
                  508.92  508.92       0       0  508.92  508.92       0
                                                                   509.6     512
     513     513     512   510.6
    -745    -645    -545    -445    -345    -245    -145     -45      55     155
     255     355     455     555     655     755     855     955    2325    2415
    2465    2515    2515    2755    2755    3105    3105    3545    3545    3595
    3645    3695    4058    4108    4178    4238    4298    4325    4325    4405
    4485    4565    4645    4725    4725    4855    4955    5055    5155    5255
    5355    5455    5555    5655    5755    5855    5955    6055    6155    6255
    6355    6455    6555    6655    6755    6855    6955    7055    7155    7255
   553.3  552.58  552.47  552.33  550.89  548.93  546.97  544.69  541.23  536.83
   532.2  527.58  522.95  518.38  514.71  512.22  510.56     510     510   510.6
   511.2   511.2  513.45  513.45   511.2   511.2  513.45  513.45   511.2   511.2
   510.6     510     510   510.2     511     512   513.6  514.41     517     519
     520     520     519     517  514.78  513.44  513.31  513.85  514.39  514.93
  515.16  514.87  514.57  514.26  514.06  514.35  514.86  514.96  515.26  515.56
  515.87  516.16  516.37  516.57  516.77  516.97   517.1  517.07  516.87  516.58
                  508.92  508.92       0       0  508.92  508.92       0
                                                                   509.6     512
     513     513     512   510.6
Pier Skew, UpSta & Num, DnSta & Num=  ,2555, 2 ,2555, 2 , 0 , 0 , 0 ,,
       2       2
     400     510
       2       2
     400     510
Pier Skew, UpSta & Num, DnSta & Num=  ,2595, 2 ,2595, 2 , 0 , 0 , 0 ,,
       2       2
     400     510
       2       2
     400     510
Pier Skew, UpSta & Num, DnSta & Num=  ,2635, 2 ,2635, 2 , 0 , 0 , 0 ,,
       2       2
     400     510
       2       2
     400     510
Pier Skew, UpSta & Num, DnSta & Num=  ,2675, 2 ,2675, 2 , 0 , 0 , 0 ,,
       2       2
     400     510
       2       2
     400     510
Pier Skew, UpSta & Num, DnSta & Num=  ,2715, 2 ,2715, 2 , 0 , 0 , 0 ,,
       2       2
     400     510
       2       2
     400     510
Pier Skew, UpSta & Num, DnSta & Num=  ,3145, 2 ,3145, 2 , 0 , 0 , 0 ,,
       2       2
     400     510
       2       2
     400     510
Pier Skew, UpSta & Num, DnSta & Num=  ,3185, 2 ,3185, 2 , 0 , 0 , 0 ,,
       2       2
     400     510
       2       2
     400     510
Pier Skew, UpSta & Num, DnSta & Num=  ,3225, 2 ,3225, 2 , 0 , 0 , 0 ,,
       2       2
     400     510
       2       2
     400     510
Pier Skew, UpSta & Num, DnSta & Num=  ,3265, 2 ,3265, 2 , 0 , 0 , 0 ,,
       2       2
     400     510
       2       2
     400     510
Pier Skew, UpSta & Num, DnSta & Num=  ,3305, 2 ,3305, 2 , 0 , 0 , 0 ,,
       2       2
     400     510
       2       2
     400     510
Pier Skew, UpSta & Num, DnSta & Num=  ,3345, 2 ,3345, 2 , 0 , 0 , 0 ,,
       2       2
     400     510
       2       2
     400     510
Pier Skew, UpSta & Num, DnSta & Num=  ,3385, 2 ,3385, 2 , 0 , 0 , 0 ,,
       2       2
     400     510
       2       2
     400     510
Pier Skew, UpSta & Num, DnSta & Num=  ,3425, 2 ,3425, 2 , 0 , 0 , 0 ,,
       2       2
     400     510
       2       2
     400     510
Pier Skew, UpSta & Num, DnSta & Num=  ,3465, 2 ,3465, 2 , 0 , 0 , 0 ,,
       2       2
     400     510
       2       2
     400     510
Pier Skew, UpSta & Num, DnSta & Num=  ,3505, 2 ,3505, 2 , 0 , 0 , 0 ,,
       2       2
     400     510
       2       2
     400     510
Pier Skew, UpSta & Num, DnSta & Num=  ,4405, 5 ,4405, 5 , 5 , 5 , 0 ,,
     6.5     6.5   4.861   4.167       6
     400     496     496     506     514
     6.5     6.5   4.861   4.167       6
     400     496     496     506     514
Pier Skew, UpSta & Num, DnSta & Num=  ,4485, 5 ,4485, 5 , 5 , 5 , 0 ,,
     6.5     6.5   5.583   4.167       6
     400     482     482     507     514
     6.5     6.5   5.583   4.167       6
     400     482     482     507     514
Pier Skew, UpSta & Num, DnSta & Num=  ,4565, 5 ,4565, 5 , 5 , 5 , 0 ,,
     6.5     6.5   5.583   4.167       6
     400     482     482     507     514
     6.5     6.5   5.583   4.167       6
     400     482     482     507     514
Pier Skew, UpSta & Num, DnSta & Num=  ,4645, 5 ,4645, 5 , 5 , 5 , 0 ,,
     6.5     6.5   4.861   4.167       6
     494     494     494     507     514
     6.5     6.5   4.861   4.167       6
     494     494     494     507     514
BR Coef=-1 , 0 , 0 ,, 0 ,,,0.8,-1,,0,
WSPro=,,,, 1 ,,,, 0 ,,,, 0 ,,,,-1 ,-1 ,-1 , 0 , 0 , 0 , 0 , 0
BC Mult= 3 ,-745,3105,-745,3105
BC Mult= 3 ,2755,4325,2755,4325
BC Mult= 3 ,3545,7255,3545,7255
BR U #Sta/Elev= 222
    -745   553.3    -645  552.58    -545  552.47    -445  552.33    -345  550.89
    -245  548.93    -145  546.97     -45  544.69      55  541.23     155  536.83
     255   532.2     355  527.58     455  522.95     555  518.38     655  514.71
     755  512.22     855  510.56  903.86   510.4  913.95  510.07  926.97  509.66
  952.62  508.87  961.51  508.81  980.36  508.53 1004.29  506.98 1017.47     506
 1031.39  505.13 1035.06  504.86 1059.92  504.82 1091.94     506 1095.45  506.04
 1096.67     506 1121.01  504.75 1132.55     504 1142.13  503.48 1146.45  503.14
 1160.38     502 1163.46  501.79  1172.5  500.62  1177.8   497.8 1177.85     498
 1197.43  497.93 1213.47  497.82 1217.85   497.8 1245.34   497.8 1247.09  497.86
 1251.24  497.88 1258.82   497.8 1271.11   497.8 1272.55     498    1277  499.82
 1278.98  500.99 1280.37     500 1282.03  499.26 1285.11   497.8 1373.43   497.8
 1373.82     498 1375.12  499.34 1382.46  500.01 1386.94  499.35 1391.49  498.19
 1393.16   497.8 1490.48   497.8 1491.04   498.2 1493.17     500    1496     502
  1497.2  502.68 1507.76  502.92 1514.76   503.3 1523.89     504  1532.1  504.55
 1540.22  504.16  1546.9  503.88 1560.95   503.1 1590.46  503.78 1596.65  503.86
 1602.43  504.03 1608.49  504.17 1615.75  504.12 1632.42  504.09 1648.24  504.03
 1679.05  504.05 1691.71  504.07 1705.84  504.15 1713.49  504.18  1729.8  504.12
 1746.88  504.13 1753.65  504.09 1766.12  502.89 1767.74  502.69 1778.08  502.73
 1798.06  501.94 1816.65  502.16 1821.04  502.26 1827.56     502 1838.81  501.58
 1870.85  500.31 1880.12   500.7 1886.68  500.95  1900.8  501.52 1915.48     502
 1933.48   502.6 1947.93  503.07 1953.41  503.27 1976.89     504 1989.02  504.21
 2010.44  504.78 2053.35  504.48 2072.12  504.38 2140.57     504 2142.69  503.96
 2193.52  503.11 2207.59  503.52 2222.17     504 2227.97  504.14 2263.52  504.82
 2312.87  504.89  2339.2  505.22 2342.81  505.22 2390.34  505.68 2405.67  505.49
 2413.28  504.51 2413.84  504.44  2434.4   505.7  2465.2  505.75 2483.41  505.76
    2515  505.57    2515     508    2532     501    2635     499    2737     500
    2755     508    2755  508.92 2756.74     500    2783  500.44 2787.49  497.67
 2794.19  493.48 2932.16  493.48 2939.26  498.34 2947.93     498 3010.48     498
 3017.16  498.06 3022.28     498 3086.29     498 3094.95  497.78  3099.7     498
    3105     508    3125     500    3305     498    3405     498    3525     500
    3545     508 3550.23  504.29  3553.3  504.51 3560.99  505.16 3614.21  505.14
 3622.88  505.15 3626.06  505.13 3634.19  505.14 3694.51  504.94 3706.89  504.93
 3736.47  504.96    3763  505.03 3772.72  505.08 3835.68  504.46 3880.26  504.84
 3883.89  504.84 3922.99  504.38 3964.32     504  4111.7     504 4129.77  505.23
 4137.02  505.34 4140.27  505.33 4153.22  505.45 4162.11  505.47 4169.81  505.53
 4182.93  505.53 4194.26   505.6 4198.49  505.59 4222.14  505.79 4225.37  505.79
 4253.33  506.03 4270.66  506.13 4281.97  506.11 4295.19  505.97    4307  505.94
    4325  505.98    4355     499    4470     491    4475     480    4480     478
    4490     475    4550     475    4560     480    4570     488    4580     490
    4725     500    4725  514.78    4855  513.44    4955  513.31    5055  513.85
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BR U #Mann= 7
    -745     .02    2515    .032    2755     .02    3105    .032    3545     .02
    4325    .032    4725     .02
BR D #Sta/Elev= 222
    -745   553.3    -645  552.58    -545  552.47    -445  552.33    -345  550.89
    -245  548.93    -145  546.97     -45  544.69      55  541.23     155  536.83
     255   532.2     355  527.58     455  522.95     555  518.38     655  514.71
     755  512.22     855  510.56  903.86   510.4  913.95  510.07  926.97  509.66
  952.62  508.87  961.51  508.81  980.36  508.53 1004.29  506.98 1017.47     506
 1031.39  505.13 1035.06  504.86 1059.92  504.82 1091.94     506 1095.45  506.04
 1096.67     506 1121.01  504.75 1132.55     504 1142.13  503.48 1146.45  503.14
 1160.38     502 1163.46  501.79  1172.5  500.62  1177.8   497.8 1177.85     498
 1197.43  497.93 1213.47  497.82 1217.85   497.8 1245.34   497.8 1247.09  497.86
 1251.24  497.88 1258.82   497.8 1271.11   497.8 1272.55     498    1277  499.82
 1278.98  500.99 1280.37     500 1282.03  499.26 1285.11   497.8 1373.43   497.8
 1373.82     498 1375.12  499.34 1382.46  500.01 1386.94  499.35 1391.49  498.19
 1393.16   497.8 1490.48   497.8 1491.04   498.2 1493.17     500    1496     502
  1497.2  502.68 1507.76  502.92 1514.76   503.3 1523.89     504  1532.1  504.55
 1540.22  504.16  1546.9  503.88 1560.95   503.1 1590.46  503.78 1596.65  503.86
 1602.43  504.03 1608.49  504.17 1615.75  504.12 1632.42  504.09 1648.24  504.03
 1679.05  504.05 1691.71  504.07 1705.84  504.15 1713.49  504.18  1729.8  504.12
 1746.88  504.13 1753.65  504.09 1766.12  502.89 1767.74  502.69 1778.08  502.73
 1798.06  501.94 1816.65  502.16 1821.04  502.26 1827.56     502 1838.81  501.58
 1870.85  500.31 1880.12   500.7 1886.68  500.95  1900.8  501.52 1915.48     502
 1933.48   502.6 1947.93  503.07 1953.41  503.27 1976.89     504 1989.02  504.21
 2010.44  504.78 2053.35  504.48 2072.12  504.38 2140.57     504 2142.69  503.96
 2193.52  503.11 2207.59  503.52 2222.17     504 2227.97  504.14 2263.52  504.82
 2312.87  504.89  2339.2  505.22 2342.81  505.22 2390.34  505.68 2405.67  505.49
 2413.28  504.51 2413.84  504.44  2434.4   505.7  2465.2  505.75 2483.41  505.76
    2515  505.57    2515     508    2532     501    2635     499    2737     500
    2755     508    2755  508.92 2756.74     500    2783  500.44 2787.49  497.67
 2794.19  493.48 2932.16  493.48 2939.26  498.34 2947.93     498 3010.48     498
 3017.16  498.06 3022.28     498 3086.29     498 3094.95  497.78  3099.7     498
    3105     508    3125     500    3305     498    3405     498    3525     500
    3545     508 3550.23  504.29  3553.3  504.51 3560.99  505.16 3614.21  505.14
 3622.88  505.15 3626.06  505.13 3634.19  505.14 3694.51  504.94 3706.89  504.93
 3736.47  504.96    3763  505.03 3772.72  505.08 3835.68  504.46 3880.26  504.84
 3883.89  504.84 3922.99  504.38 3964.32     504  4111.7     504 4129.77  505.23
 4137.02  505.34 4140.27  505.33 4153.22  505.45 4162.11  505.47 4169.81  505.53
 4182.93  505.53 4194.26   505.6 4198.49  505.59 4222.14  505.79 4225.37  505.79
 4253.33  506.03 4270.66  506.13 4281.97  506.11 4295.19  505.97    4307  505.94
    4325  505.98    4355     499    4470     491    4475     480    4480     478
    4490     475    4550     475    4560     480    4570     488    4580     490
    4725     500    4725  514.78    4855  513.44    4955  513.31    5055  513.85
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BR D #Mann= 7
    -745     .02    2515    .032    2755     .02    3105    .032    3545     .02
    4325    .032    4725     .02
BC Design=,, 0 ,, 0 ,,,,,,
BC Use User HTab Curves=0
BC User HTab FreeFlow(D)= 0

Type RM Length L Ch R = 1 ,206116  ,780,876,358
BEGIN DESCRIPTION:
Downstream bounding cross-section East 1st Street.
---------------------------------------------------------------------
CDC East 1st Street FW 040113-01
---------------------------------------------------------------------
END DESCRIPTION:
XS GIS Cut Line= 6
  2341865.0194766963733.20492262 2343429.50436816963785.60684001
2344846.53599986 6963800.78917042345444.975670556963890.46353647
2347066.944641866964252.92478897 2347920.67087966964171.72651552
#Sta/Elev= 30
       0  546.85  369.23   548.9  512.04  541.71  562.18  536.03  572.53  544.23
  603.81  533.98  663.08  540.28  684.12  537.77  686.41     530  788.51  524.26
  821.63  512.25  1177.8   497.8 2227.97  504.14 2413.28  504.51    2515  505.57
 2756.74     500  3099.7     498 3560.99  505.16    4325  505.98    4470     491
    4475     480    4490     475    4550     475    4580     490    4725     500
 4726.55  508.82 4892.94  506.98 4982.56  515.85 6076.14     520 6093.63     520
#Mann= 11 ,-1,0
       0     .09       0  512.04     .15       0 2227.97     .06       0
 2413.28     .15       0    2515    .032       0 2756.74     .15       0
  3099.7    .032       0 3560.99     .15       0    4325    .032       0
 4726.55     .15       0 6076.14    .035       0
#XS Ineff= 3 ,-1
       0    2515     510    2755    3105     510    3545    4325     510
Permanent Ineff=
       F       F       F
Bank Sta=4325,4725
XS Rating Curve= 0 ,0
Exp/Cntr=0.3,0.1

Type RM Length L Ch R = 1 ,205240  ,800,904,900
BEGIN DESCRIPTION:
ROB updated with 2009 TNRIS LiDAR
END DESCRIPTION:
XS GIS Cut Line= 6
  2343638.127123 6965094.4051029 2343922.8423688 6965034.2533849
   2344871.03011      6964833.93   2346477.14501      6964833.93
     2347171.557   6964475.169892347670.10784933 6964217.5993346
#Sta/Elev= 30
    3291   537.6    3354     532    3579   530.1    3855   505.7    4041   503.5
    4187   500.6    4341   503.8    4641   501.1    5593   505.5    5636   486.4
    5652   473.4    5672   471.5    5720   473.4    5748   493.2 5824.32  495.96
 5840.89  504.11  5857.3  505.35 5909.68  479.13 6006.13  478.36  6053.3  494.42
  6099.2  496.87 6447.21  497.62 6503.68  510.73 6581.57  512.68 6616.27  519.92
 6653.93  512.76  7355.7  518.07 7705.91  517.02 7809.26  511.48 7849.67  514.11
#Mann= 7 ,-1,0
    3291     .12       0    4041    .065       0    4341     .12       0
    4641    .065       0    5593    .055       0    5748    .075       0
 6447.21      .1       0
#XS Ineff= 2 , 0
            5593   505.5    5748           493.2
Permanent Ineff=
       F       F
#Block Obstruct= 1 ,-1
 5861.35 6480.54     500
Bank Sta=5593,5748
XS Rating Curve= 0 ,0
Exp/Cntr=0.3,0.1