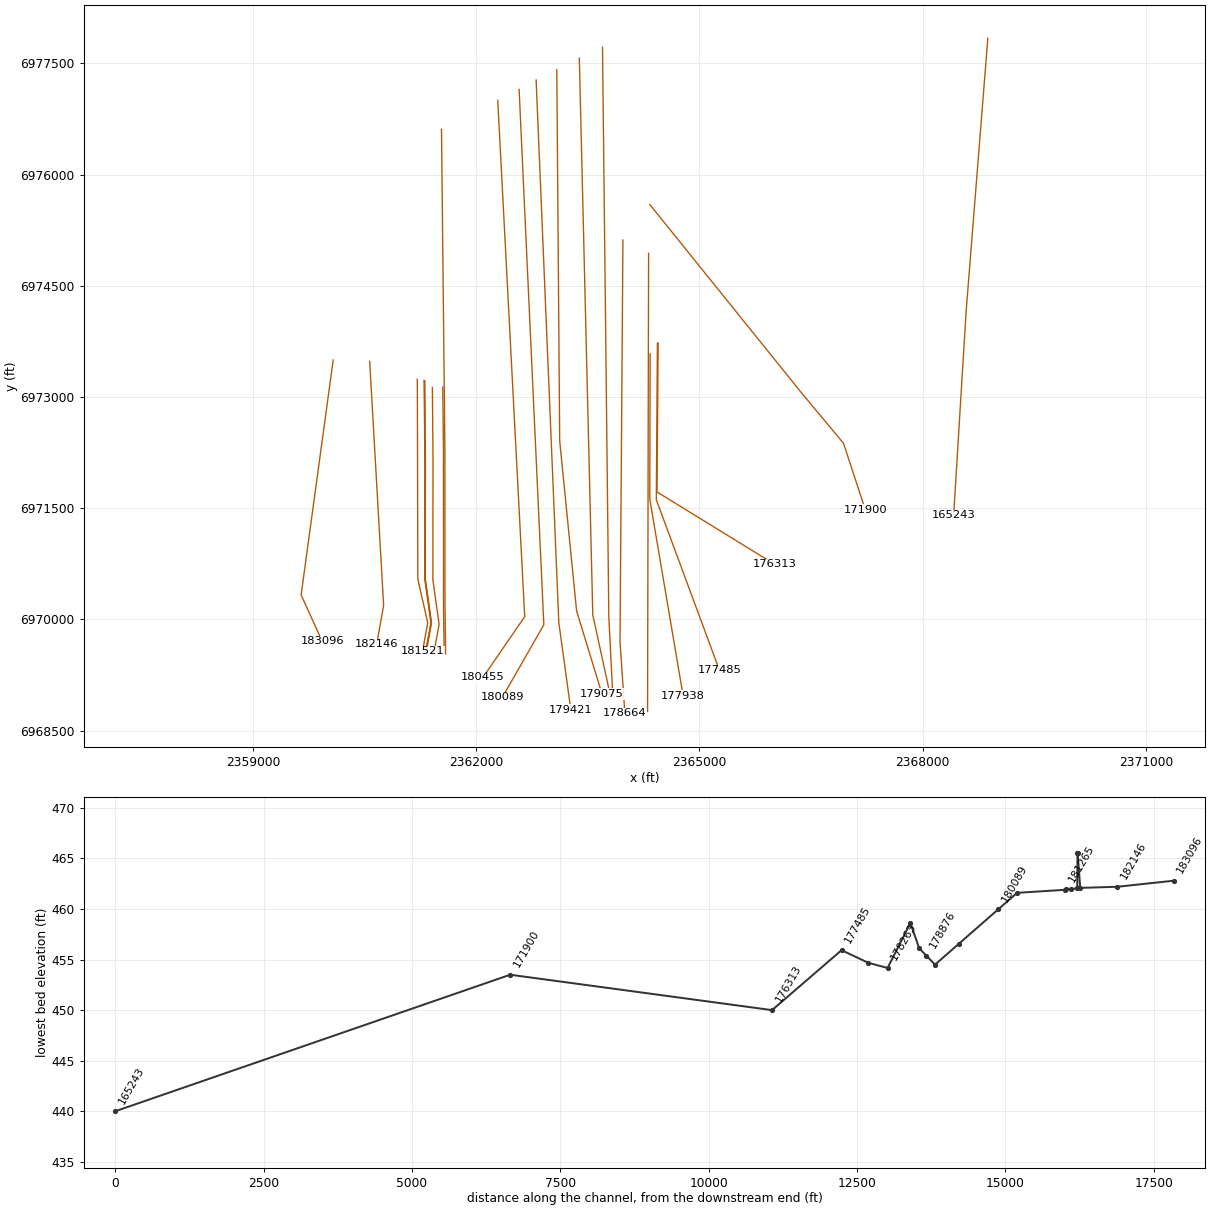
HEC-RAS study CDC_Consolidated_Model.prj: Upper Trinity CDC Consolidated Model

--- CDC_Consolidated_Model.g12 (geometry) --- (continued)

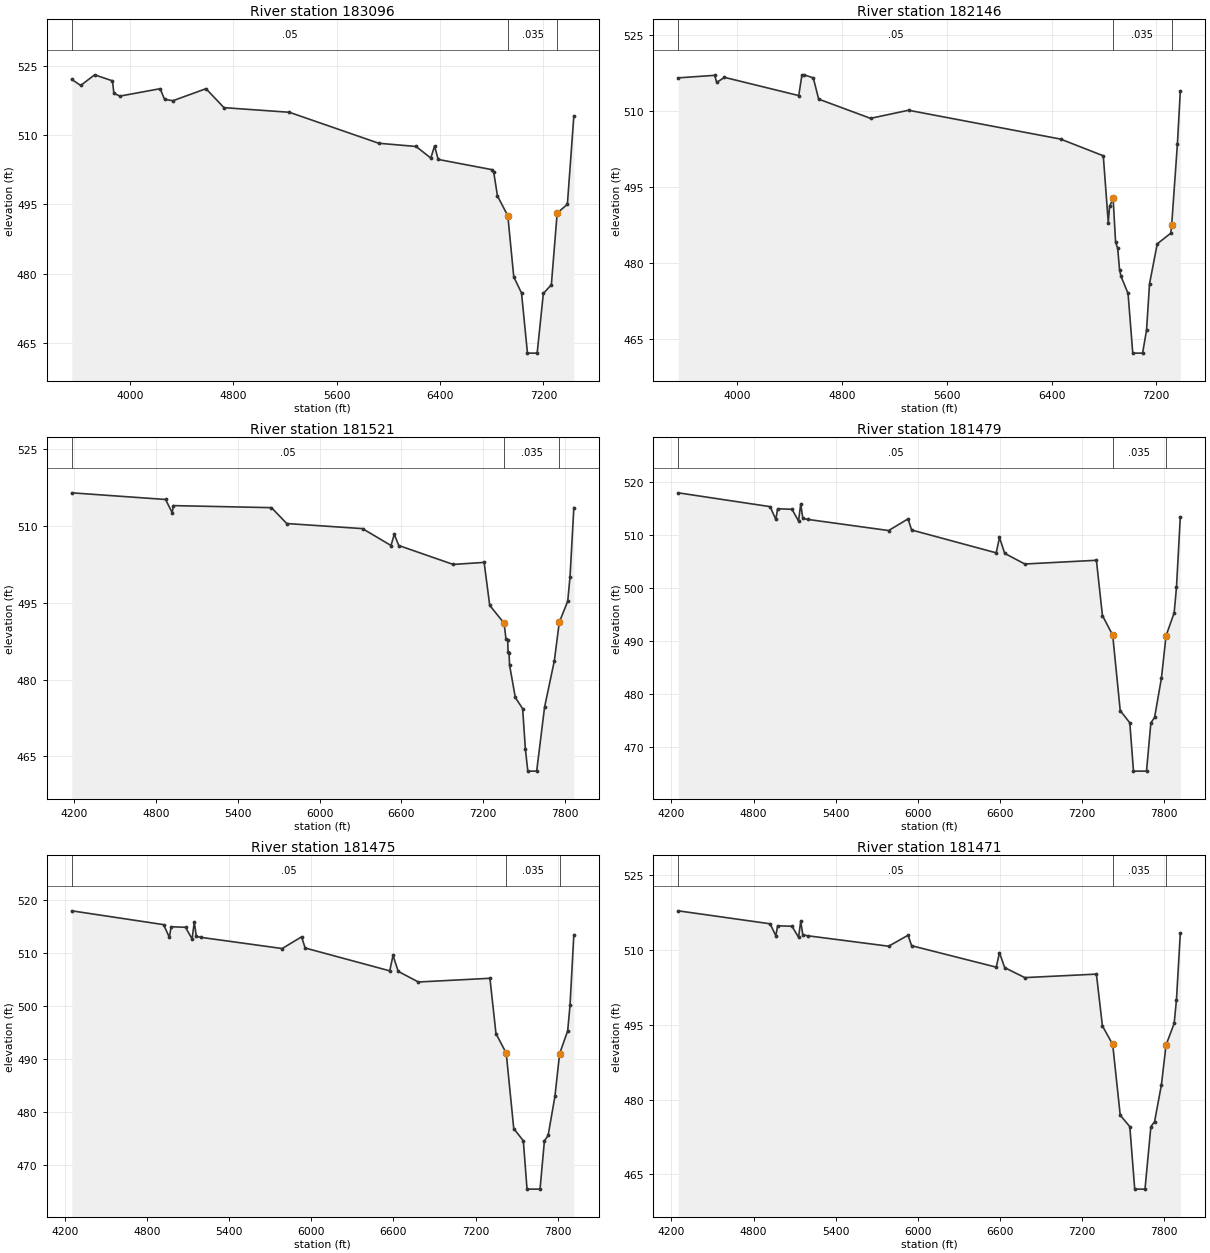
Type RM Length L Ch R = 1 ,183096  ,1050,950,900
BEGIN DESCRIPTION:
This cross section corresponds to cross section 183096 of the non-georeferenced CDC model which was the source of this model.
END DESCRIPTION:
XS GIS Cut Line= 3
  2360080.302205 6973499.7483181   2359649.32404   6970330.62602
   2359932.37499   6969703.87006
#Sta/Elev= 30
    3550     522    3619   520.7    3727     523    3865   521.7    3876     519
    3923   518.4    4234     520    4268   517.7    4333   517.4    4589     520
    4728   515.9    5234   514.9    5926   508.2    6215   507.5    6329     505
    6358   507.6    6386   504.7    6800   502.5    6816   501.9    6845   496.8
    6925   492.5    6971   479.3    7031   475.8    7077   462.8    7152   462.8
    7200   475.7    7262   477.6    7307   493.1    7386     495    7436   514.1
#Mann= 3 ,0,0
    3550     .05       0    6925    .035       0    7307     .05       0
#XS Ineff= 2 , 0
            6925   492.5    7307           493.1
Permanent Ineff=
       F       F
Bank Sta=6925,7307
XS Rating Curve= 0 ,0
Exp/Cntr=0.3,0.1

Type RM Length L Ch R = 1 ,182146  ,610,625,625
BEGIN DESCRIPTION:
This cross section corresponds to cross section 182146 of the non-georeferenced CDC model which was the source of this model.
END DESCRIPTION:
XS GIS Cut Line= 3
   2360570.38532  6973481.139121   2360758.00785   6970189.29297
   2360664.02707   6969661.78812
#Sta/Elev= 30
    3550   516.6    3828   517.1    3844   515.7    3903   516.7    4470   513.1
    4494   517.1    4511   517.2    4581   516.6    4622   512.4    5018   508.6
    5308   510.2    6469   504.5    6795   501.2    6833     488    6843   491.2
    6870   492.8    6889   484.1    6905   482.9    6919   478.7    6930   477.4
    6984     474    7020   462.2    7095   462.2    7125   466.7    7148   475.9
    7207   483.8    7310   485.9    7317   487.5    7361   503.6    7383     514
#Mann= 3 ,0,0
    3550     .05       0    6870    .035       0    7317     .05       0
#XS Ineff= 2 , 0
            6870   492.8    7317           487.5
Permanent Ineff=
       F       F
Bank Sta=6870,7317
XS Rating Curve= 0 ,0
Exp/Cntr=0.3,0.1

Type RM Length L Ch R = 1 ,181521  ,42,42,42
BEGIN DESCRIPTION:
This cross section corresponds to cross section 181521 of the non-georeferenced CDC model which was the source of this model.
END DESCRIPTION:
XS GIS Cut Line= 5
  2361210.029294 6973237.9957154   2361211.53516   6973077.56016
   2361217.59715   6970543.71713   2361350.82294   6969954.61497
   2361281.10589   6969571.17315
#Sta/Elev= 30
    4180   516.5    4869   515.2    4918   512.6    4926     514    5647   513.6
    5759   510.5    6316   509.5    6525   506.2    6549   508.4    6582   506.2
    6982   502.5    7209   502.9    7250   494.5    7356     491    7369     488
    7382   487.8    7385   485.3    7392   485.1    7396   482.8    7438   476.5
    7492   474.3    7512   466.4    7530  462.09    7595  462.09    7653   474.6
    7725   483.7    7761   491.2    7823   495.3    7840   500.1    7868   513.6
#Mann= 3 ,0,0
    4180     .05       0    7356    .035       0    7761     .05       0
#XS Ineff= 2 , 0
            7356     491    7761           491.2
Permanent Ineff=
       F       F
Bank Sta=7356,7761
XS Rating Curve= 0 ,0
Exp/Cntr=0.3,0.1

Type RM Length L Ch R = 1 ,181479  ,4,4,4
BEGIN DESCRIPTION:
This cross section corresponds to cross section 181479 of the non-georeferenced CDC model which was the source of this model.
END DESCRIPTION:
XS GIS Cut Line= 6
  2361302.493278 6973221.8763323 2361302.4932784 6973221.8763323
 2361311.6129613 6972207.4595381 2361309.9459713 6970552.1327981
 2361393.7978313 6969955.0716581 2361323.0847213 6969566.1537981
#Sta/Elev= 30
    4250   517.9    4921   515.3    4963   512.9    4976   514.9    5081   514.8
    5129   512.6    5145   515.8    5160   513.1    5195   512.9    5787   510.8
    5929     513    5955   510.9    6573   506.6    6597   509.5    6635   506.5
    6782   504.5    7305   505.2    7349   494.8    7424   491.1    7479   476.9
    7549   474.6    7576   465.5    7671   465.5    7703   474.6    7730   475.6
    7780     483    7814     491    7873   495.3    7890   500.1    7918   513.4
#Mann= 3 ,0,0
    4250     .05       0    7424    .035       0    7814     .05       0
#XS Ineff= 2 , 0
            7424   491.1    7814             491
Permanent Ineff=
       F       F
Bank Sta=7424,7814
XS Rating Curve= 0 ,0
Exp/Cntr=0.3,0.1

Type RM Length L Ch R = 1 ,181475  ,4,4,4
BEGIN DESCRIPTION:
This cross section corresponds to cross section 181475 of the non-georeferenced CDC model which was the source of this model.
END DESCRIPTION:
XS GIS Cut Line= 5
  2361306.421067 6973221.1185436 2361315.5407504 6972206.7017494
 2361313.8737604 6970551.3750094 2361397.7256204 6969954.3138694
 2361327.0125104 6969565.3960094
#Sta/Elev= 30
    4250   517.9    4921   515.3    4963   512.9    4976   514.9    5081   514.8
    5129   512.6    5145   515.8    5160   513.1    5195   512.9    5787   510.8
    5929     513    5955   510.9    6573   506.6    6597   509.5    6635   506.5
    6782   504.5    7305   505.2    7349   494.8    7424   491.1    7479   476.9
    7549   474.6    7576   465.5    7671   465.5    7703   474.6    7730   475.6
    7780     483    7814     491    7873   495.3    7890   500.1    7918   513.4
#Mann= 3 ,0,0
    4250     .05       0    7424    .035       0    7814     .05       0
#XS Ineff= 2 , 0
            7424   491.1    7814             491
Permanent Ineff=
       F       F
Bank Sta=7424,7814
XS Rating Curve= 0 ,0
Exp/Cntr=0.3,0.1

Type RM Length L Ch R = 1 ,181471  ,104,104,104
BEGIN DESCRIPTION:
This cross section corresponds to cross section 181471 of the non-georeferenced CDC model which was the source of this model.
END DESCRIPTION:
XS GIS Cut Line= 5
  2361310.152467 6973220.3986442   2361319.27215   6972205.98185
   2361317.60516   6970550.65511   2361401.45702   6969953.59397
   2361330.74391   6969564.67611
#Sta/Elev= 30
    4250   517.9    4921   515.3    4963   512.9    4976   514.9    5081   514.8
    5129   512.6    5145   515.8    5160   513.1    5195   512.9    5787   510.8
    5929     513    5955   510.9    6573   506.6    6597   509.5    6635   506.5
    6782   504.5    7305   505.2    7349   494.8    7424   491.1    7479   476.9
    7549   474.6    7585  462.06    7660  462.06    7703   474.6    7730   475.6
    7780     483    7814     491    7873   495.3    7890   500.1    7918   513.4
#Mann= 3 ,0,0
    4250     .05       0    7424    .035       0    7814     .05       0
#XS Ineff= 2 , 0
            7424   491.1    7814             491
Permanent Ineff=
       F       F
Bank Sta=7424,7814
XS Rating Curve= 0 ,0
Exp/Cntr=0.3,0.1

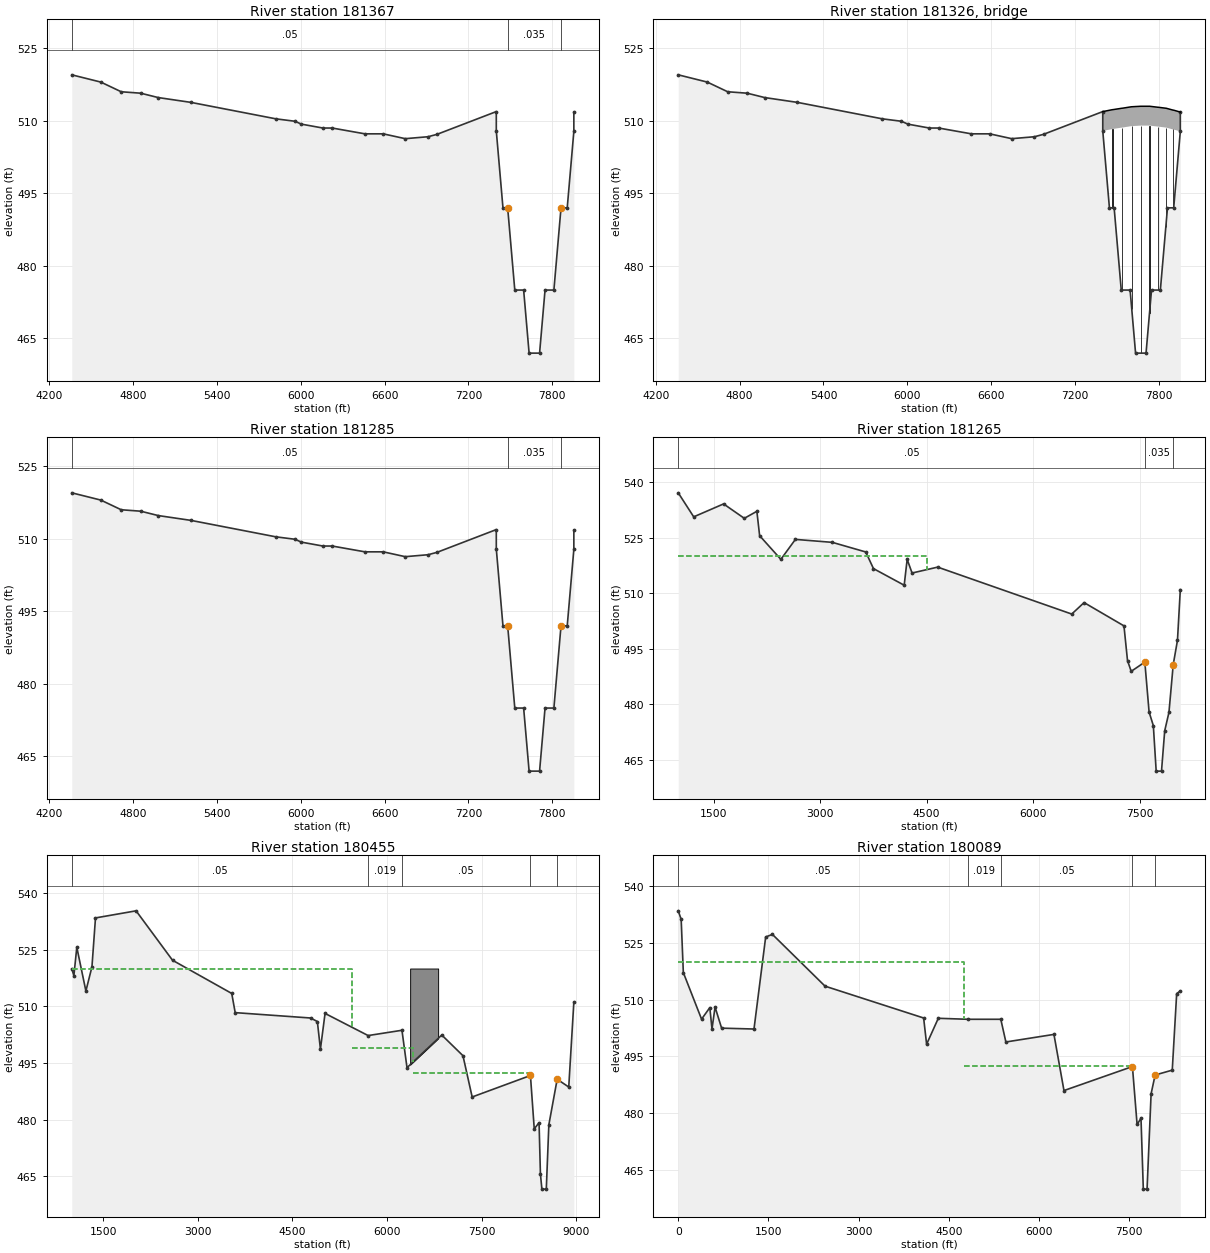
Type RM Length L Ch R = 1 ,181367  ,82,82,82
BEGIN DESCRIPTION:
This cross section corresponds to cross section 181367 of the non-georeferenced CDC model which was the source of this model.
END DESCRIPTION:
XS GIS Cut Line= 5
  2361413.135029 6973127.9692752 2361421.6012506 6972186.2394851
 2361419.9342606 6970530.9127451 2361503.7861206 6969933.8516051
 2361433.0730106 6969544.9337451
#Sta/Elev= 30
    4360   519.5    4568     518    4714     516    4854   515.7    4979   514.8
    5214   513.8    5822   510.4    5958   509.9    6005   509.3    6158   508.5
    6225   508.5    6459   507.3    6590   507.3    6748   506.3    6911   506.7
    6976   507.2    7400   511.9    7400   507.9  7447.7     492 7481.43     492
 7532.43     475 7595.81     475 7634.93  461.96 7709.93  461.96 7749.05     475
 7812.43     475 7863.43     492 7907.91     492 7955.31   507.8 7955.31   511.8
#Mann= 3 ,0,0
    4360     .05       0 7481.43    .035       0 7863.43     .05       0
#XS Ineff= 2 , 0
         7481.43     492 7863.43             492
Permanent Ineff=
       F       F
Bank Sta=7481.43,7863.43
XS Rating Curve= 0 ,0
Exp/Cntr=0.5,0.3

Type RM Length L Ch R = 3 ,181326  ,,,
BEGIN DESCRIPTION:
Handley-Ederville Road
END DESCRIPTION:
Node Name=Handley-Edervill
Bridge Culvert--1,0,-1,-1, 0
Deck Dist Width WeirC Skew NumUp NumDn MinLoCord MaxHiCord MaxSubmerge Is_Ogee
1,80,2.6,0, 18, 18, , , 0.95, 0, ,,,
    7400 7469.53 7472.03 7538.75 7541.25  7606.1  7608.6 7671.18 7673.68  7733.8
  7736.3 7793.67 7796.17 7850.51 7853.01 7903.99 7906.49 7955.31
   511.9   512.3   512.3   512.6   512.6   512.9   512.9     513     513     513
     513   512.8   512.8   512.6   512.6   512.2   512.2   511.8
   507.9   508.3   508.3   508.6   508.6   508.9   508.9     509     509     509
     509   508.8   508.8   508.6   508.6   508.2   508.2   507.8
    7400 7469.53 7472.03 7538.75 7541.25  7606.1  7608.6 7671.18 7673.68  7733.8
  7736.3 7793.67 7796.17 7850.51 7853.01 7903.99 7906.49 7955.31
   511.9   512.3   512.3   512.6   512.6   512.9   512.9     513     513     513
     513   512.8   512.8   512.6   512.6   512.2   512.2   511.8
   507.9   508.3   508.3   508.6   508.6   508.9   508.9     509     509     509
     509   508.8   508.8   508.6   508.6   508.2   508.2   507.8
Pier Skew, UpSta & Num, DnSta & Num=  ,7470.78, 2 ,7470.78, 2 , 0 , 0 , 0 ,,
     2.5     2.5
     450     510
     2.5     2.5
     450     510
Pier Skew, UpSta & Num, DnSta & Num=  ,7540, 2 ,7540, 2 , 0 , 0 , 0 ,,
     2.5     2.5
     450     510
     2.5     2.5
     450     510
Pier Skew, UpSta & Num, DnSta & Num=  ,7607.35, 2 ,7607.35, 2 , 0 , 0 , 0 ,,
     2.5     2.5
     450     510
     2.5     2.5
     450     510
Pier Skew, UpSta & Num, DnSta & Num=  ,7672.43, 2 ,7672.43, 2 , 0 , 0 , 0 ,,
     2.5     2.5
     450     510
     2.5     2.5
     450     510
Pier Skew, UpSta & Num, DnSta & Num=  ,7735.05, 2 ,7735.05, 2 , 0 , 0 , 0 ,,
     2.5     2.5
     450     510
     2.5     2.5
     450     510
Pier Skew, UpSta & Num, DnSta & Num=  ,7794.92, 2 ,7794.92, 2 , 0 , 0 , 0 ,,
     2.5     2.5
     450     510
     2.5     2.5
     450     510
Pier Skew, UpSta & Num, DnSta & Num=  ,7851.76, 2 ,7851.76, 2 , 0 , 0 , 0 ,,
     2.5     2.5
     450     510
     2.5     2.5
     450     510
Pier Skew, UpSta & Num, DnSta & Num=  ,7905.24, 2 ,7905.24, 2 , 0 , 0 , 0 ,,
     2.5     2.5
     450     510
     2.5     2.5
     450     510
BR Coef= 1 , 0 , 0 ,1.05, 0 ,,,0.8,-1,0.5,1,
WSPro=,,,, 1 ,,,, 0 ,,,, 0 ,,,,-1 ,-1 ,-1 , 0 , 0 , 0 , 0 , 0
BC Design=,, 0 ,, 0 ,,,,,,
BC HTab HWMax=519.5
BC Use User HTab Curves=0
BC User HTab FreeFlow(D)= 0

Type RM Length L Ch R = 1 ,181285  ,20,20,20
BEGIN DESCRIPTION:
This cross section corresponds to cross section 181285 of the non-georeferenced CDC model which was the source of this model.
END DESCRIPTION:
XS GIS Cut Line= 5
  2361552.884858 6973134.1526615 2361561.6402378 6972306.8421715
 2361562.8780978 6970179.9373115 2361564.3869478 6970066.7462615
 2361571.1129878 6969538.9422015
#Sta/Elev= 30
    4360   519.5    4568     518    4714     516    4854   515.7    4979   514.8
    5214   513.8    5822   510.4    5958   509.9    6005   509.3    6158   508.5
    6225   508.5    6459   507.3    6590   507.3    6748   506.3    6911   506.7
    6976   507.2    7400   511.9    7400   507.9  7447.7     492 7481.43     492
 7532.43     475 7595.81     475 7634.93  461.96 7709.93  461.96 7749.05     475
 7812.43     475 7863.43     492 7907.91     492 7955.31   507.8 7955.31   511.8
#Mann= 3 ,0,0
    4360     .05       0 7481.43    .035       0 7863.43     .05       0
#XS Ineff= 2 , 0
         7481.43     492 7863.43             492
Permanent Ineff=
       F       F
Bank Sta=7481.43,7863.43
XS Rating Curve= 0 ,0
Exp/Cntr=0.3,0.1

Type RM Length L Ch R = 1 ,181265  ,928,808,728
BEGIN DESCRIPTION:
This cross section corresponds to cross section 181265 of the non-georeferenced CDC model which was the source of this model.
END DESCRIPTION:
XS GIS Cut Line= 6
  2361535.702464 6976609.8584375   2361535.70413   6976609.70107
   2361581.28114   6972303.05285     2361582.519   6970176.14799
   2361584.02785   6970062.95694   2361590.75389   6969535.15288
#Sta/Elev= 30
    1000   537.2    1218   530.7    1639   534.2    1931   530.3    2108   532.2
    2147   525.6    2446   519.2    2651   524.6    3171   523.8    3642   521.2
    3751   516.7    4184   512.2    4226   519.2    4295   515.5    4656   517.1
    6545   504.4    6719   507.5    7281   501.2    7331   491.8    7383   488.9
    7575   491.4    7635   477.9    7695   474.2    7735   461.9    7810   461.9
    7855   472.8    7915   477.8    7975   490.7    8035   497.3    8075     511
#Mann= 3 ,0,0
    1000     .05       0    7575    .035       0    7975     .05       0
#XS Ineff= 2 ,-1
    1000    4500     520    4500    7575   491.4
Permanent Ineff=
       F       F
Bank Sta=7575,7975
XS Rating Curve= 0 ,0
Exp/Cntr=0.3,0.1

Type RM Length L Ch R = 1 ,180455  ,300.06,315.47,330.72
BEGIN DESCRIPTION:
This cross section corresponds to cross section 180455 of the non-georeferenced CDC model which was the source of this model.
END DESCRIPTION:
XS GIS Cut Line= 3
   2362291.77906   6977002.08906   2362653.95485   6970036.21093
 2362095.2733342 6969221.6854017
#Sta/Elev= 30
    1000  519.92 1033.63  518.12  1079.8  525.62    1224  514.05 1320.14  520.45
 1376.21  533.39 2020.01  535.27 2597.92  522.19 3537.24   513.4 3592.04  508.32
 4786.99   506.9 4895.14  505.97 4943.94  498.67 5017.31  508.11 5700.65  502.25
 6237.03  503.65 6317.16  493.75 6868.73  502.39 7204.65  496.92 7350.56  485.99
    8275  491.68 8335.37  477.55 8411.62   479.2  8433.2  465.66 8456.52   461.6
  8526.5   461.6 8566.99  478.64    8699  490.69 8882.49  488.63  8963.4  511.05
#Mann= 5 ,-1,0
    1000     .05       0 5700.65    .019       0 6237.03     .05       0
    8275    .035       0    8699     .08       0
#XS Ineff= 3 ,-1
    1000    5450     520    5450  6407.4     499  6407.4    8275   492.4
Permanent Ineff=
       F       T       F
#Block Obstruct= 1 ,-1
    6367    6811     520
Bank Sta=8275,8699
XS Rating Curve= 0 ,0
Exp/Cntr=0.3,0.1

Type RM Length L Ch R = 1 ,180089  ,533.31,667.85,742.87
XS GIS Cut Line= 3
2362578.692429856977149.360410662362911.099837266969926.95010975
2362354.32321689 6968950.7984894
#Sta/Elev= 30
       0  533.42    48.8  531.17   84.84  517.12  388.03  504.83  525.31  507.88
  561.35  502.23  612.42  508.03  721.44  502.46  1260.1  502.23  1454.3  526.52
 1566.39   527.2 2441.81  513.54 4081.44  505.14 4130.94  498.22 4325.37  505.06
  4815.4   504.8 5364.78   504.8 5449.29  498.81 6248.78  500.81 6415.59  485.99
 7554.04  492.33 7631.58  477.04 7696.53  478.69 7735.19  459.98 7797.58  459.98
  7864.7  485.14 7931.58  490.09 8216.55  491.38    8290  511.58 8350.49  512.27
#Mann= 5 ,-1,0
       0     .05       0  4815.4    .019       0 5364.78     .05       0
 7554.04    .035       0 7931.58     .08       0
#XS Ineff= 2 ,-1
       0    4750     520    4750    7545   492.4
Permanent Ineff=
       F       F
Bank Sta=7554.04,7931.58
XS Rating Curve= 0 ,0
Exp/Cntr(USF)=0,0
Exp/Cntr=0.3,0.1

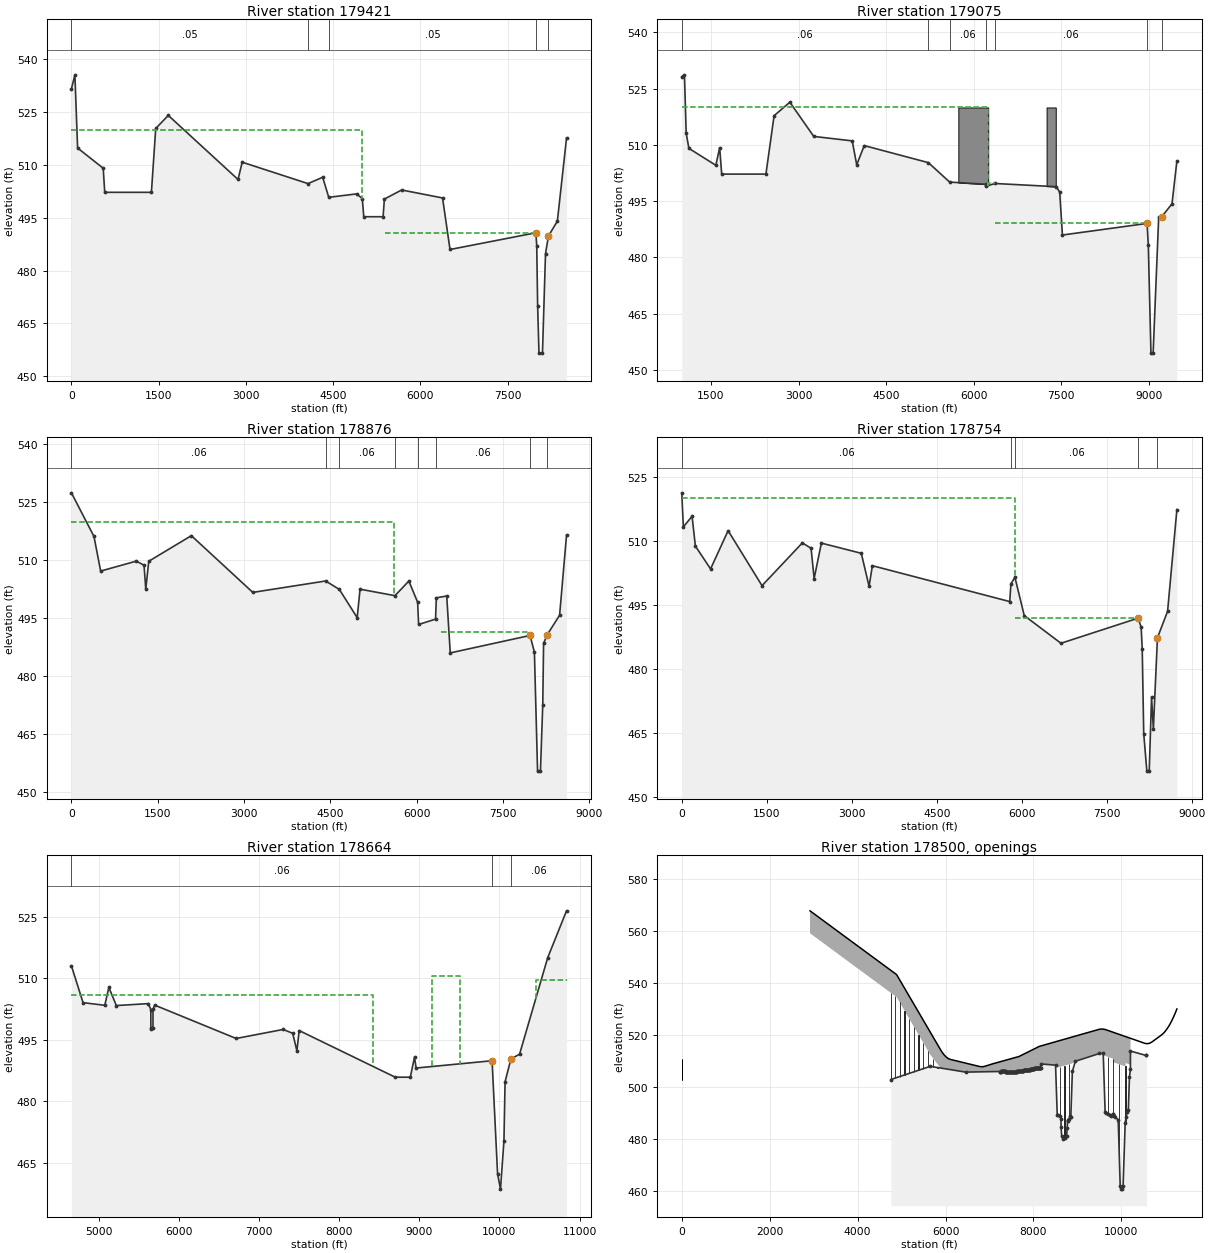
Type RM Length L Ch R = 1 ,179421  ,372.53,399.76,426.49
XS GIS Cut Line= 3
2362807.425068756977275.488882882363112.546596526969954.04791069
2363274.004929856968776.96457735
#Sta/Elev= 30
       0  531.63   59.75  535.61  106.38  514.82  546.77  509.07   572.8  502.23
 1375.52  502.23  1449.7  520.38 1665.79  524.08 2864.87  505.88 2936.94  510.79
 4067.92  504.71 4320.47   506.5  4425.1  500.81 4904.72  501.79 5001.82  500.45
 5027.23   495.3  5359.5   495.3  5381.5  500.31 5678.55   502.9 6381.81  500.63
 6510.17  485.99 7986.83  490.74 8001.56  486.93  8017.1   469.8 8040.03  456.55
 8099.93  456.55 8152.31  484.83 8202.62   489.8 8356.13  494.05 8513.78  517.66
#Mann= 5 ,-1,0
       0     .05       0 4067.92    .019       0  4425.1     .05       0
 7986.83    .035       0 8202.62     .08       0
#XS Ineff= 3 ,-1
       0    5000     520    5000    5383     500    5384    7965   490.8
Permanent Ineff=
       F       T       F
Bank Sta=7986.83,8202.62
XS Rating Curve= 0 ,0
Exp/Cntr(USF)=0,0
Exp/Cntr=0.3,0.1

Type RM Length L Ch R = 1 ,179075  ,155.58,144.92,132.39
BEGIN DESCRIPTION:
This cross section corresponds to cross section 179075 of the non-georeferenced CDC model which was the source of this model.
END DESCRIPTION:
XS GIS Cut Line= 4
   2363085.04585     6977414.061   2363124.02904   6972410.30002
   2363351.58403   6970112.34989 2363692.7487769 6968994.3479177
#Sta/Elev= 30
    1000  528.22 1045.89   528.7 1075.74  513.13 1121.67   509.1 1583.66  504.58
 1649.23  509.28  1683.7  502.23 2441.75  502.23 2581.76  517.81 2851.77   521.4
 3260.78  512.28    3920  511.09 3997.08   504.7 4126.09  509.83 5224.42  505.29
 5589.53   500.1  6204.5  499.53  6204.5  498.96 6366.01  499.73 7419.11  498.87
 7475.21  497.37 7521.33  485.99    8972  489.08 8992.74  483.21 9038.06   454.5
 9075.43   454.5 9170.72  490.78    9219  490.79 9398.65  494.31 9482.36  505.69
#Mann= 7 ,-1,0
    1000     .06       0 5224.42    .019       0 5589.53     .06       0
  6204.5     .05       0 6366.01     .06       0    8972     .05       0
    9219     .08       0
#XS Ineff= 3 ,-1
    1000    6250     520    6250  6365.6  499.75  6365.6    8972   489.3
Permanent Ineff=
       F       T       F
#Block Obstruct= 2 ,-1
    5738    6250     520    7250    7407     520
Bank Sta=8972,9219
XS Rating Curve= 0 ,0
Exp/Cntr=0.3,0.1

Type RM Length L Ch R = 1 ,178876  ,147.67,122.06,99.22
XS GIS Cut Line= 3
2363387.821842476977571.154392112363568.854466896970059.54559583
2363801.695902086968986.77360508
#Sta/Elev= 30
       0  527.44  392.13  516.14  508.17  507.18 1129.07  509.76 1262.42  508.69
 1292.43  502.48 1344.45  509.72 2084.69  516.35 3152.99  501.66 4419.27  504.61
 4657.09  502.44 4967.65  495.12 5017.66  502.49 5624.39  500.81 5865.93   504.6
 6018.31  499.11 6035.57  493.35 6329.76  494.73 6344.11  500.26 6524.17  500.72
 6585.46  485.99 7972.43  490.51 8048.56  486.17 8103.35  455.38 8153.44  455.38
 8193.85   472.6 8208.18  488.48 8272.43  490.72 8486.49  495.75 8606.99  516.48
#Mann= 8 ,-1,0
       0     .06       0 4419.27    .019       0 4657.09     .06       0
 5624.39    .019       0 6018.31     .05       0 6329.76     .06       0
 7972.43     .05       0 8272.43     .08       0
#XS Ineff= 3 ,-1
       0    5600     520    6000 6421.63   496.3 6421.63 7923.68  491.45
Permanent Ineff=
       F       T       F
Bank Sta=7972.43,8272.43
XS Rating Curve= 0 ,0
Exp/Cntr(USF)=0,0
Exp/Cntr=0.3,0.1

Type RM Length L Ch R = 1 ,178754  ,147.4,147.4,147.4
BEGIN DESCRIPTION:
CDC FW 091322-1 Riverbend East
Project located in LOB.
Cross-sections 178754 - 181265
END DESCRIPTION:
XS GIS Cut Line= 4
 2363699.49718976977718.000456932363784.103671186970035.18795692
2363837.141865626968978.677540242363837.14186562 6968977.8094847
#Sta/Elev= 30
       0   521.2   27.81  513.23  181.83  515.71  240.24  508.75  508.21  503.41
  817.88  512.35 1416.18  499.49 2127.99  509.49    2282  508.24 2336.01  501.15
 2464.02  509.44 3168.23  507.06 3306.09  499.33 3363.98  504.16  5788.3  495.77
 5809.54   499.9 5879.83  501.46  6044.4   492.5 6692.39  486.02 8053.21  491.89
 8107.59  489.81 8126.64  484.77  8153.3  464.89 8208.29  456.12  8250.3  456.12
 8291.34  473.42 8323.38  465.99 8395.48  487.31 8574.19  493.48 8738.47  517.27
#Mann= 5 ,-1,0
       0     .06       0 5809.54    .019       0 5879.83     .06       0
 8053.21     .05       0 8395.48     .08       0
#XS Ineff= 2 ,-1
       0    5885     520    5885    8020   491.9
Permanent Ineff=
       F       F
Bank Sta=8053.21,8395.48
XS Rating Curve= 0 ,0
Exp/Cntr(USF)=0,0
Exp/Cntr=0.3,0.1

Type RM Length L Ch R = 1 ,178664  ,385,385,385
BEGIN DESCRIPTION:
178664
U/S of IH 820.
END DESCRIPTION:
XS GIS Cut Line= 3
  2363973.8598046975116.739679742363934.797304816969700.07301305
 2363999.90147156968732.19106862
#Sta/Elev= 30
    4660     513 4805.15  504.04 5076.03  503.39 5127.18  507.74 5220.57  503.33
 5618.07   503.8 5651.06  502.36 5651.27  497.85  5657.6   497.7 5677.57  497.77
 5677.92  502.44 5698.67  503.44 6715.73  495.31 7302.85  497.51 7421.34  496.56
 7473.43   492.3 7501.77  497.24 8700.55  485.88 8888.79  485.88 8941.04  490.77
  8961.3  488.11 9908.97  489.89 9977.44  462.36   10014  458.62   10057  470.38
   10071  484.77   10144  490.32   10252  491.49   10603  514.98   10838   526.4
#Mann= 3 ,0,0
    4660     .06       0 9908.97     .05       0   10144     .06       0
#XS Ineff= 3 ,-1
    4200    8423     506    9165    9508   510.5   10453   11000  509.53
Permanent Ineff=
       F       F       F
Bank Sta=9908.97,10144
XS Rating Curve= 0 ,0
Exp/Cntr=0.3,0.1

Type RM Length L Ch R = 4 ,178500  ,,,
BEGIN DESCRIPTION:
IH 820
END DESCRIPTION:
Node Name=IH 820
Bridge Culvert--1,0,-1,-1, 0
Deck Dist Width WeirC Skew NumUp NumDn MinLoCord MaxHiCord MaxSubmerge Is_Ogee
60,246,2.6,0, 69, 56, , , 0.95, 0, 3,3,,
    2916    4886    5883    5883    5906    5930    5953    5976    5999    6022
    6045    6069    6092    6115    6764    6778    6792    6806    6820    6834
    6847    6861    6875    6889    6903    7066    7668    8131    8131    9473
    9491    9509    9527    9545    9563    9581    9599    9616    9634    9652
    9808    9808   10000   10094   10094   10206   10206   10524   10542   10560
   10578   10596   10613   10631   10649   10667   10685   10703   10904   10940
   10976   11011   11047   11083   11119   11154   11190   11226   11262
  567.93  543.37  514.52  514.52  513.88   513.3  512.77   512.3  511.89  511.54
  511.24     511  510.82   510.7  508.03  507.98  507.95  507.92  507.91  507.91
  507.93  507.96     508  508.06  508.13     509  511.83  515.73  515.73  522.21
  522.29  522.35  522.39   522.4   522.4  522.39  522.35  522.29  522.21  522.12
   521.2   521.2  520.06  519.51  519.51  518.85  518.85  516.96  516.87  516.82
  516.79   516.8  516.84  516.92  517.02  517.16  517.33  517.54  520.03  520.53
  521.14  521.87  522.71  523.66  524.73  525.91   527.2  528.61  530.14
  559.28  534.72  505.87  505.87  505.23  504.65  504.12  503.65  503.24  502.89
  502.59  502.35  502.17  502.05  499.38  499.33   499.3  499.27  499.26  499.26
  499.28  499.31  499.35  499.41  499.48  500.35  503.18          505.56  512.05
  512.12  512.18  512.22  512.24  512.24  512.22  512.18  512.12  512.05  511.95
  511.03   509.7  508.57  508.01  509.34  508.68
    2182    5126    6405    6442    6479    6517    6554    6591    6628    6665
    6702    6739    6776    7133    8223    8223    9516    9534    9552    9570
    9588    9606    9624    9641    9659    9677    9695    9812    9812   10000
   10099   10099   10211   10211   10567   10585   10603   10621   10638   10656
   10674   10692   10710   10728   10746   10947   10983   11018   11054   11090
   11126   11162   11197   11233   11269   11305
   597.1  559.05  513.44  512.19  511.09  510.13  509.32  508.66  508.14  507.77
  507.55  507.47  507.54  508.92  515.96  515.96  522.44  522.51  522.57  522.61
  522.63  522.63  522.61  522.57  522.51  522.44  522.34  521.65  521.65  520.54
  519.95  519.95  519.29  519.29  517.19   517.1  517.04  517.02  517.03  517.07
  517.14  517.25  517.39  517.56  517.76  520.25  520.75  521.36  522.09  522.93
  523.88  524.95  526.13  527.43  528.84  530.36
  588.45   550.4  504.79  503.54  502.44  501.48  500.67  500.01  499.49  499.12
   498.9  498.82  498.89  500.27          505.87  512.35  512.42  512.48  512.52
  512.54  512.54  512.52  512.48  512.42  512.35  512.25  511.56  510.23  509.12
  508.53  509.86   509.2
Pier Skew, UpSta & Num, DnSta & Num=  ,0, 2 ,4815, 2 , 0 , 0 , 0 ,,
       3       3
     440     511
       3       3
     440     555
Pier Skew, UpSta & Num, DnSta & Num=  ,0, 2 ,4910, 2 , 0 , 0 , 0 ,,
       3       3
     440     511
       3       3
     440     555
Pier Skew, UpSta & Num, DnSta & Num=  ,0, 2 ,5016, 2 , 0 , 0 , 0 ,,
       3       3
     440     511
       3       3
     440     555
Pier Skew, UpSta & Num, DnSta & Num=  ,4758, 2 ,5125, 2 , 0 , 0 , 0 ,,
       3       3
     440     540
       3       3
     440     555
Pier Skew, UpSta & Num, DnSta & Num=  ,4850, 2 ,5230, 2 , 0 , 0 , 0 ,,
       3       3
     440     540
       3       3
     440     550
Pier Skew, UpSta & Num, DnSta & Num=  ,4958, 2 ,5337, 2 , 0 , 0 , 0 ,,
       3       3
     440     535
       3       3
     440     545
Pier Skew, UpSta & Num, DnSta & Num=  ,5065, 2 ,5447, 2 , 0 , 0 , 0 ,,
       3       3
     440     531
       3       3
     440     540
Pier Skew, UpSta & Num, DnSta & Num=  ,5176, 2 ,5552, 2 , 0 , 0 , 0 ,,
       3       3
     440     528
       3       3
     440     540
Pier Skew, UpSta & Num, DnSta & Num=  ,5280, 2 ,5659, 2 , 0 , 0 , 0 ,,
       3       3
     440     525
       3       3
     440     535
Pier Skew, UpSta & Num, DnSta & Num=  ,5385, 2 ,5761, 2 , 0 , 0 , 0 ,,
       3       3
     440     525
       3       3
     440     530
Pier Skew, UpSta & Num, DnSta & Num=  ,5493, 2 ,5870, 2 , 0 , 0 , 0 ,,
       3       3
     440     520
       3       3
     440     530
Pier Skew, UpSta & Num, DnSta & Num=  ,5602, 2 ,5980, 2 , 0 , 0 , 0 ,,
       3       3
     440     515
       3       3
     440     525
Pier Skew, UpSta & Num, DnSta & Num=  ,5708, 2 ,6084, 2 , 0 , 0 , 0 ,,
       3       3
     440     515
       3       3
     440     520
Pier Skew, UpSta & Num, DnSta & Num=  ,5815, 2 ,6191, 2 , 0 , 0 , 0 ,,
       3       3
     440     512
       3       3
     440     520
Pier Skew, UpSta & Num, DnSta & Num=  ,8597, 2 ,8616, 2 , 0 , 0 , 0 ,,
       3       3
     440     511
       3       3
     440     511
Pier Skew, UpSta & Num, DnSta & Num=  ,8704, 2 ,8723, 2 , 0 , 0 , 0 ,,
       3       3
     440     511
       3       3
     440     511
Pier Skew, UpSta & Num, DnSta & Num=  ,8812, 2 ,8830, 2 , 0 , 0 , 0 ,,
       3       3
     440     511
       3       3
     440     511
Pier Skew, UpSta & Num, DnSta & Num=  ,9696, 2 ,9702, 2 , 0 , 0 , 0 ,,
       3       3
     440     513
       3       3
     440     513
Pier Skew, UpSta & Num, DnSta & Num=  ,9808, 2 ,9814, 2 , 0 , 0 , 0 ,,
     3.5     3.5
     440     511
     3.5     3.5
     440     511
Pier Skew, UpSta & Num, DnSta & Num=  ,9951, 2 ,9957, 2 , 0 , 0 , 0 ,,
     3.5     3.5
     440     511
     3.5     3.5
     440     511
Pier Skew, UpSta & Num, DnSta & Num=  ,10094, 2 ,10100, 2 , 0 , 0 , 0 ,,
     3.5     3.5
     440     511
     3.5     3.5
     440     511
Abutment Skew #Up #Dn= , 3 , 3
    8515    8538    8598
   502.3  502.07  482.07
 8531.55 8554.55 8614.55
   502.3  502.07  482.07
Abutment Skew #Up #Dn= , 3 , 3
    8794    8854    8877
  482.07  502.07   502.3
  8808.8  8868.8  8891.8
  482.07  502.07   502.3
Abutment Skew #Up #Dn= , 3 , 3
    9605    9628    9688
   502.3  502.07  482.07
  9610.8  9633.8  9693.8
   502.3  502.07  482.07
BR Coef= 1 , 0 , 0 ,1.05, 0 ,,,0.8,0,1.2,1,
WSPro=,,,, 1 ,,,, 0 ,,,, 0 ,,,,-1 ,-1 ,-1 , 0 , 0 , 0 , 0 , 0
BR Coef=-1 , 0 , 0 ,1.05, 0 ,,,0.8,0,1.2,1,
WSPro=,,,, 1 ,,,, 0 ,,,, 0 ,,,,-1 ,-1 ,-1 , 0 , 0 , 0 , 0 , 0
BC Mult= 3 ,4171,9586,4171,9588
BC Mult= 3 ,8951,10909,8960,10999
BR U #Sta/Elev= 150
    4756  502.98    5651  508.06    6456  505.83    7237  506.04    7248  506.05
    7257  506.06    7268  506.08    7270  506.08    7281   506.1    7292  506.12
    7303  506.15    7314  506.16    7318  506.17    7321  506.16    7332  506.15
    7343  506.09    7355  506.08    7365  506.02    7369  506.02    7373  506.01
    7385  505.98    7395  505.98    7408  505.94    7417  505.93    7424  505.91
    7433  505.91    7446  505.91    7455  505.91    7466  505.91    7475   505.9
    7488  505.91    7490  505.91    7500  505.92    7508  505.92    7522  505.92
    7531  505.92    7542  505.92    7551  505.91    7565  505.91    7569   505.9
    7577  505.94    7590  505.93    7596  505.95    7610  506.02    7618  506.04
    7630   506.1    7635  506.11    7650   506.1    7658  506.09    7671  506.08
    7676  506.07    7691  506.15    7698  506.23    7710  506.29    7714  506.34
    7730  506.38    7737  506.39    7741  506.39    7753  506.43    7761  506.45
    7776  506.55    7780  506.56    7795  506.65    7802  506.66    7817  506.68
    7820  506.68    7825  506.69    7832  506.69    7848  506.66    7851  506.66
    7865  506.63    7871  506.66    7874  506.68    7890  506.73    7896  506.73
    7910  506.78    7913  506.78    7929  506.86    7935  506.91    7949  506.97
    7952     507    7958  507.04    7974  507.13    7975  507.13    7992  507.22
    7997  507.22    7999  507.22    8017  507.21    8022  507.25    8037  507.25
    8042  507.25    8059  507.36    8060  507.36    8062  507.36    8080  507.34
    8085  507.34    8096  507.33    8097  507.33    8102  507.35    8120  507.34
    8120  507.35    8135  507.34    8138  507.37    8139  507.37    8158  507.55
    8162  507.55  8177.2  508.97    8502   508.5    8540  489.32    8557  489.26
    8600  488.84    8626  487.79    8627  484.62    8642  481.21    8674  479.91
    8713  480.32    8752  481.18    8767  484.29    8774  487.03    8788  487.56
    8819  487.79    8822  488.78    8849  488.63    8884  506.08    8951     510
    9500     513  9586.2     513  9629.9  490.34    9649  490.07    9684  489.59
    9730  489.43    9759  489.12    9801  489.66    9819  489.65    9822  488.78
    9849  488.63    9927  487.47    9973   461.8   10000  460.78   10006  460.79
   10038  461.84   10086   486.4   10108  488.49   10129  490.59 10157.5  491.23
   10183     504 10204.6  506.87   10206  513.94   10563  512.24   10569   512.3
BR U #Mann= 3
    4756     .06    9927     .05   10086     .06
BR U Banks=9927,10086
BR D #Sta/Elev= 70
    4812  505.62    5693  511.31    6408  508.73 8517.75   508.5  8556.2  489.27
    8591  488.19    8617   487.8    8636  486.86    8643  483.87    8656  480.59
    8694   479.5    8712  479.53    8742  479.58    8770  480.63    8784   483.8
    8792  487.82    8806  488.94    8826  489.24    8853  489.77    8865  488.66
    8901  506.05  8958.2     510  9588.2     513  9633.3  490.21    9659  489.78
    9695  489.99    9730  489.31    9766  489.24    9801  489.24    9824   489.6
    9855  489.95    9887  489.14    9904  488.68    9921  486.34    9962  465.06
    9967  463.36    9979  460.26   10000   459.5   10010  459.56   10036  459.91
   10048  466.92   10079  483.94   10098  486.93   10113  488.33   10132  490.26
   10150   491.2 10158.8  491.43   10184  504.02   10207  505.96   10211  513.65
   10506  513.05   10510  513.03   10525  512.94   10531  512.95   10534  512.94
   10534  512.96   10535  512.95   10535  512.94   10550  513.05   10553  512.99
   10559  511.95   10566  511.85   10577  511.64   10580   511.6   10587  513.29
   10590  513.34   10598  513.56   10606  513.65   10613   513.8   10624  513.91
BR D #Mann= 3
    4812     .13    9921     .05   10098     .08
BR D Banks=9921,10098
BC Design=,, 0 ,, 0 ,,,,,,
BC HTab HWMax=512.6
BC Use User HTab Curves=0
BC User HTab FreeFlow(D)= 0

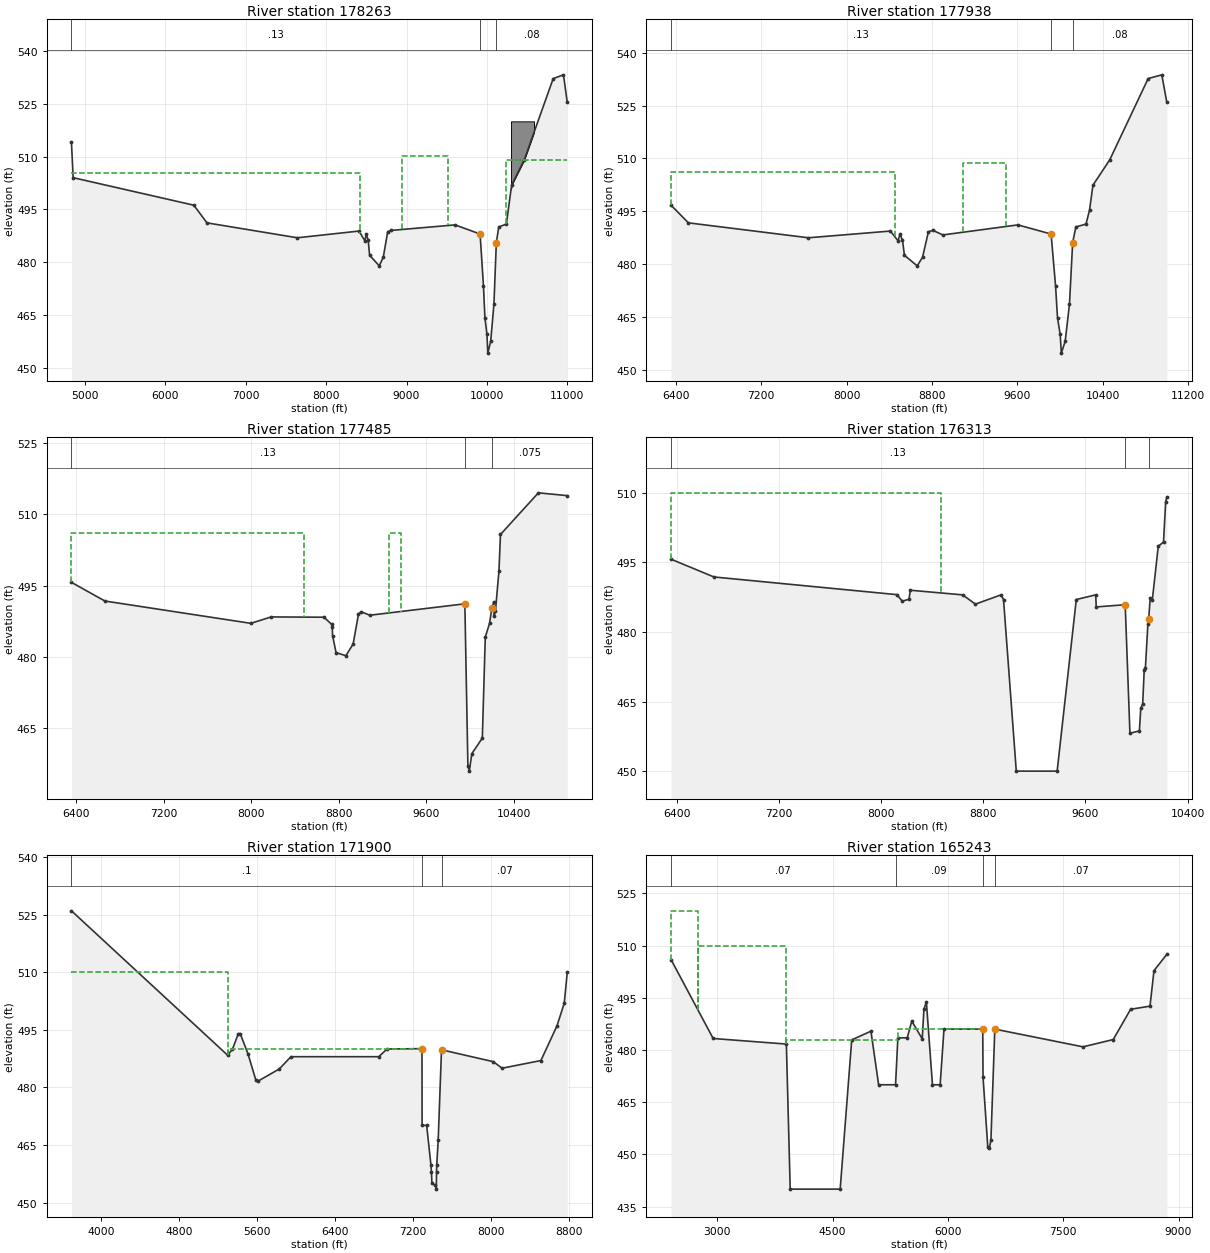
Type RM Length L Ch R = 1 ,178263  ,146,325,343
BEGIN DESCRIPTION:
178263
D/S of IH 820.
---------------------------------------------------------------------
CDC FW 050917-01 IH 820
---------------------------------------------------------------------
END DESCRIPTION:
XS GIS Cut Line= 2
  2364318.8250826974937.616415842364304.936193736968757.06086026
#Sta/Elev= 30
    4833     514    4854     504    6355  496.18    6518  491.17    7642  486.93
    8410  488.84    8482  486.04    8499  487.95    8523  486.29    8541  481.97
    8661  478.95    8711  481.41    8766  488.66    8809  489.02    9604  490.59
    9915  487.99    9957  473.19    9975  464.19   10000  459.49   10011  454.17
   10047  457.56   10087  468.03   10117  485.58   10147     490   10242  490.83
   10307  501.87   10464  509.05   10824  532.14   10952  533.21   10999  525.38
#Mann= 3 ,0,0
    4833     .13       0    9915     .05       0   10117     .08       0
#XS Ineff= 3 ,-1
    4200    8426   505.4    8946    9518  510.25   10241   11000  509.16
Permanent Ineff=
       F       F       F
#Block Obstruct= 1 ,-1
   10300   10585     520
Bank Sta=9915,10117
XS Rating Curve= 0 ,0
Exp/Cntr=0.3,0.1

Type RM Length L Ch R = 1 ,177938  ,92,450,540
XS GIS Cut Line= 3
  2364339.6584156973581.713638072364334.450082636971623.38030472
2364782.366749296968972.33863805
#Sta/Elev= 30
    6355  496.69    6518  491.68    7642  487.44    8410  489.35    8482  486.55
    8499  488.46    8523   486.8    8541  482.48    8661  479.46    8711  481.92
    8766  489.17    8809  489.53    8901  488.25    9604   491.1    9915   488.5
    9957   473.7    9975   464.7   10000     460   10011  454.68   10047  458.07
   10087  468.54   10117  486.09   10147  490.51   10242  491.34   10275  495.28
   10307  502.38   10464  509.56   10824  532.65   10952  533.72   10999  525.89
#Mann= 3 ,0,0
    6355     .13       0    9915     .05       0   10117     .08       0
#XS Ineff= 2 ,-1
    6355    8450     506    9089    9489  508.73
Permanent Ineff=
       F       F
Bank Sta=9915,10117
XS Rating Curve= 0 ,0
Exp/Cntr=0.3,0.1

Type RM Length L Ch R = 1 ,177485  ,700,1172,1250
BEGIN DESCRIPTION:
177485
END DESCRIPTION:
XS GIS Cut Line= 3
   2364436.924046973724.248360262364422.64452705 6971613.6580825
2365271.950082636969310.88030472
#Sta/Elev= 30
    6355  495.69    6661  491.76    7996  487.06    8182  488.41    8665  488.35
    8736  486.84    8741  486.28    8744  484.46    8776  480.88    8866  480.25
    8932  482.71    8981  488.99    9006  489.49    9085  488.77    9954  491.17
    9954  491.18    9982  457.05    9995  455.93   10018  459.61   10114  462.89
   10141  484.14   10180  487.05   10201  490.19   10217   491.5   10223  488.71
   10234  489.67   10266  498.09   10280  505.78   10627  514.55   10891  513.96
#Mann= 3 ,0,0
    6355     .13       0    9954     .05       0   10201    .075       0
#XS Ineff= 2 ,-1
    6000    8487     506    9263    9366     506
Permanent Ineff=
       F       F
Bank Sta=9954,10201
XS Rating Curve= 0 ,0
Exp/Cntr=0.3,0.1

Type RM Length L Ch R = 1 ,176313  ,2500,4413,1800
BEGIN DESCRIPTION:
176313
---------------------------------------------------------------------
CDC IH820 Project FW 050917-01
(from XS 178664 - 176313)
--------------------------------------------------------------------
END DESCRIPTION:
XS GIS Cut Line= 3
  2364447.340707 6973729.4566936 2364431.71570766971719.04002695
 2366009.84070766970745.08169362
#Sta/Elev= 30
    6355  495.69    6691  491.86    8124  488.05    8166  486.64    8219  487.06
    8229     489    8639     488    8739     486    8939     488    8959     487
    9059     450    9379     450    9529     487    9681     488    9685   485.4
    9912  485.88    9949  458.17   10023  458.67   10034  463.57   10049  464.52
   10061  471.87   10070  472.17   10090  481.82   10096  482.86   10108  487.38
   10124  486.82   10171  498.49   10212  499.37   10229  508.09   10238  509.03
#Mann= 3 ,0,0
    6355     .13       0    9912    .065       0   10096    .075       0
#XS Ineff= 4 ,-1
    6355    8469     510    8469    9529     487    9529    9912  485.88
   10124   11000  486.82
Permanent Ineff=
       F       T       F       F
Bank Sta=9912,10096
XS Rating Curve= 0 ,0
Exp/Cntr=0.3,0.1

Type RM Length L Ch R = 1 ,171900  ,3799,6655,1500
BEGIN DESCRIPTION:
This cross section corresponds to cross section 171900 of the non-georeferenced CDC model which was the source of this model.
END DESCRIPTION:
XS GIS Cut Line= 6
  2364335.620421 6975595.7691784   2365304.91116   6974387.82788
   2366385.72986   6973040.89915   2366385.83485   6973040.77185
   2366938.19201   6972375.97791   2367230.55298   6971480.70607
#Sta/Elev= 30
    3700     526    5300   488.4    5350   489.9    5410     494    5430     494
    5510   488.7    5590   481.9    5610   481.6    5830   484.8    5950     488
    6850     488    6935     490    7293   490.1    7294   470.1    7341   470.1
    7385   459.7    7390     458    7395     455    7430   454.5    7440   453.5
    7442     458    7444   459.7    7459   466.2    7493   489.8    8024   486.7
    8114     485    8512     487    8676     496    8751   501.9    8782     510
#Mann= 3 ,0,0
    3700      .1       0    7293    .065       0    7493     .07       0
#XS Ineff= 3 ,-1
    3700    5300     510    5300    7293   490.1    7493    8782   489.8
Permanent Ineff=
       F       F       F
Bank Sta=7293,7493
XS Rating Curve= 0 ,0
Exp/Cntr=0.3,0.1

Type RM Length L Ch R = 1 ,165243  ,2402,2810,1151
BEGIN DESCRIPTION:
This cross section corresponds to cross section 165243 of the non-georeferenced CDC model which was the source of this model.
END DESCRIPTION:
XS GIS Cut Line= 5
 2368877.65286136977838.04796955  2368850.022491 6977489.1402989
  2368841.654436 6977383.4711187   2368586.11687   6974156.62297
 2368418.6193932  6971406.669799
#Sta/Elev= 30
    2400     506    2948   483.3    3900   481.7    3950     440    4600     440
    4750   482.9    5000   485.4    5100     470    5320     470    5350   483.5
    5472   483.5    5531   488.3    5667   483.2    5689   491.7    5721   493.8
    5800     470    5900     470    5950     486    6454     486    6458   472.1
    6520     452    6540   451.8    6560     454    6611     486    7758   480.9
    8151     483    8377   491.7    8629   492.6    8681   502.8    8848   507.5
#Mann= 4 ,-1,0
    2400     .07       0    5320     .09       0    6454    .055       0
    6611     .07       0
#XS Ineff= 5 ,-1
    2400    2750     520    2750    3900     510    3900    5350     483
    5350    6454     486    6611    8848     486
Permanent Ineff=
       F       F       T       F       F
Bank Sta=6454,6611
XS Rating Curve= 0 ,0
Exp/Cntr=0.3,0.1