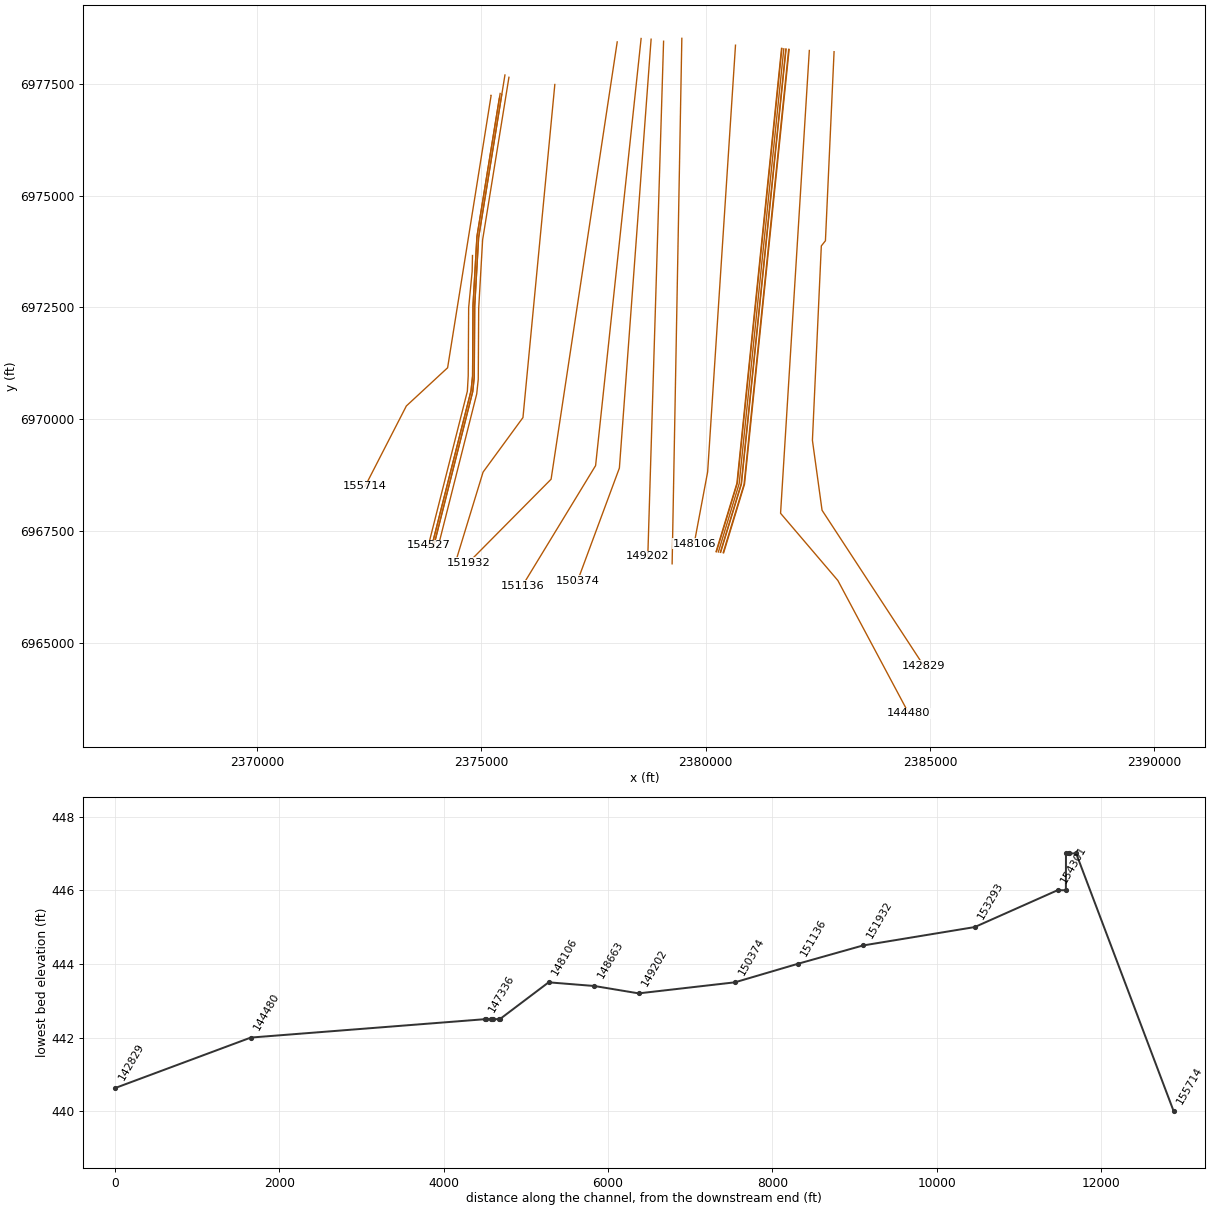
HEC-RAS study CDC_Consolidated_Model.prj: Upper Trinity CDC Consolidated Model

--- CDC_Consolidated_Model.g12 (geometry) --- (continued)

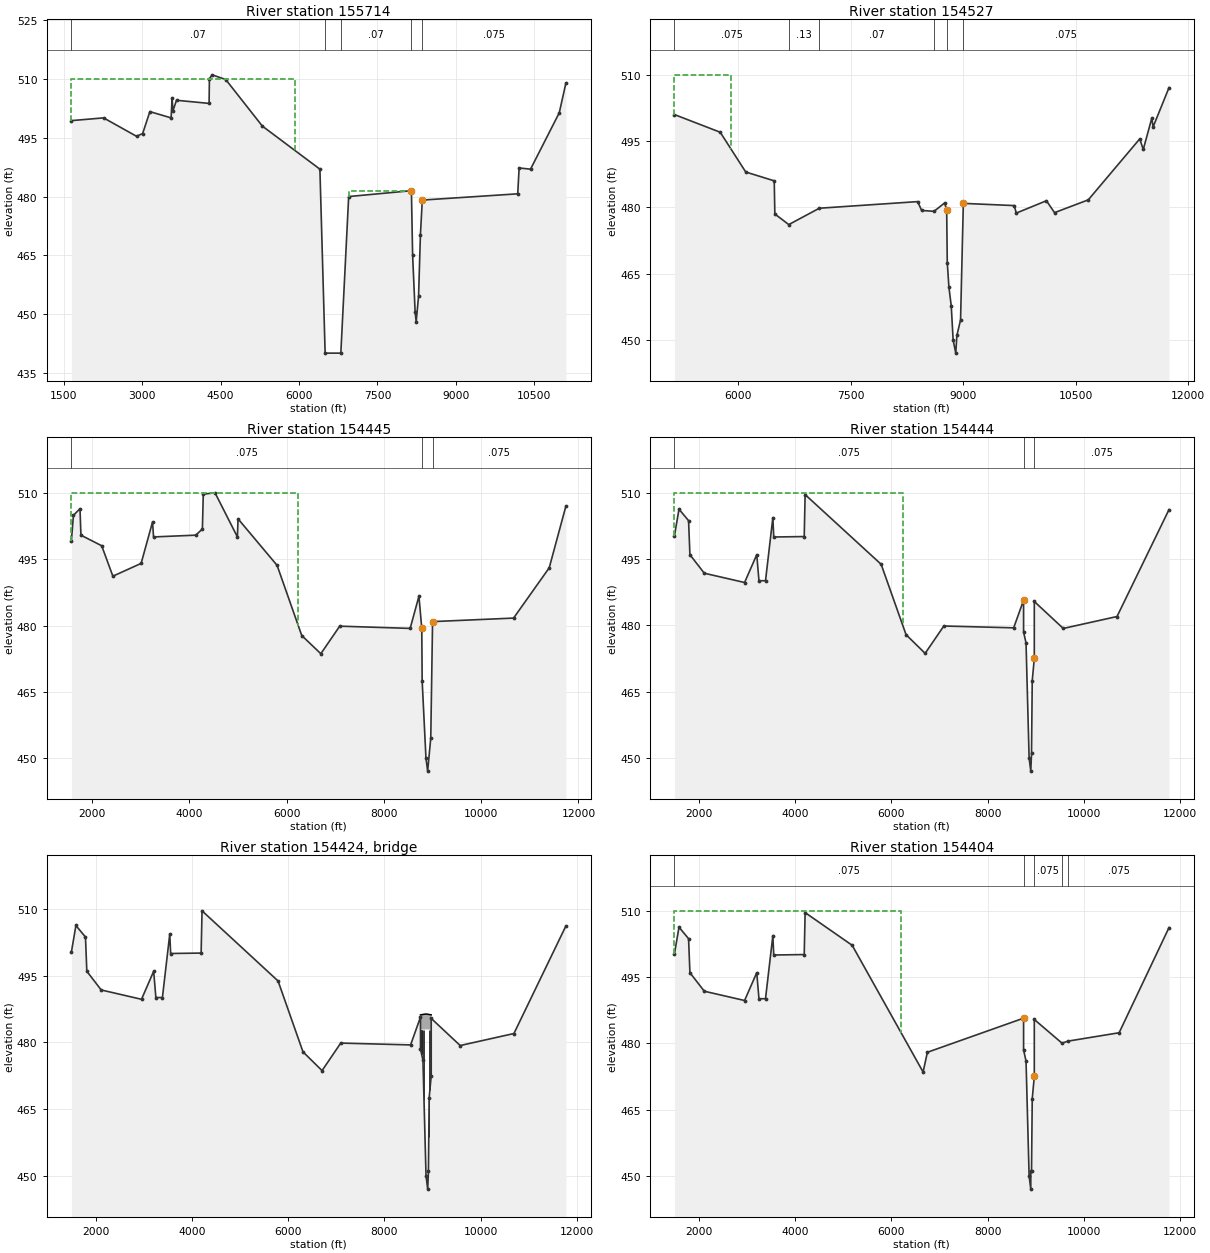
Type RM Length L Ch R = 1 ,155714  ,350,1187,1499
BEGIN DESCRIPTION:
This cross section corresponds to cross section 155714 of the non-georeferenced CDC model which was the source of this model.
END DESCRIPTION:
XS GIS Cut Line= 5
  2375216.900499 6977247.5845485 2375216.9004995 6977247.5845485
   2374246.14885   6971151.04991   2373326.55916   6970296.25897
   2372405.52196   6968494.91907
#Sta/Elev= 30
    1650   499.4    2265   500.1    2895   495.4    3012   496.1    3150   501.7
    3556   500.1    3575   505.1    3591   501.9    3659   504.6    4282   503.8
    4288   510.1    4340   511.1    4600   509.9    5300     498    6400     487
    6500     440    6800     440    6950     480    8149   481.5    8172   465.1
    8220   450.5    8240     448    8286   454.6    8321   470.2    8357   479.1
   10181   480.7   10208   487.3   10426     487   10975   501.4   11102     509
#Mann= 5 ,-1,0
    1650     .07       0    6500     .04       0    6800     .07       0
    8149    .055       0    8357    .075       0
#XS Ineff= 4 ,-1
    1650    5933     510    5933    6950     480    6950    8149   481.5
    8357   11102   479.1
Permanent Ineff=
       F       T       F       F
Bank Sta=8149,8357
XS Rating Curve= 0 ,0
Exp/Cntr=0.3,0.1

Type RM Length L Ch R = 1 ,154527  ,83,83,83
BEGIN DESCRIPTION:
This cross section corresponds to cross section 154527 of the non-georeferenced CDC model which was the source of this model.
END DESCRIPTION:
XS GIS Cut Line= 6
  2374800.699271 6973662.8791966   2374793.20189    6973308.0141
   2374715.41793     6972496.144   2374705.69485   6970969.63393
   2374686.24902   6970624.46796   2373819.26716     6967181.798
#Sta/Elev= 30
    5150     501    5760     497    6100     488    6480     486    6488   478.5
    6674   476.1    7081   479.8    8392   481.3    8445   479.3    8610   479.1
    8752     481    8779   479.4    8787   467.5    8809   461.9    8840   457.7
    8865     450    8900     447    8915     451    8964   454.5    9001   480.9
    9680   480.4    9707   478.7   10109   481.5   10217   478.8   10667   481.7
   11353   495.5   11400   493.1   11514   500.2   11531   498.2   11743   507.1
#Mann= 6 ,-1,0
    5150    .075       0    6674     .13       0    7081     .07       0
    8610     .13       0    8779    .055       0    9001    .075       0
#XS Ineff= 3 ,-1
    5150    5900     510    5900    8779   479.4    9001   11743   480.9
Permanent Ineff=
       F       F       F
Bank Sta=8779,9001
XS Rating Curve= 0 ,0
Exp/Cntr=0.3,0.1

Type RM Length L Ch R = 1 ,154445  ,1,1,1
BEGIN DESCRIPTION:
154445
END DESCRIPTION:
XS GIS Cut Line= 6
  2375398.244882 6977175.2932533 2374899.9057473 6974085.5876751
 2374812.3987045 6972549.3545271 2374802.6756268 6970964.5066469
 2374768.6455112 6970638.7868259 2373893.0406351 6967159.7826291
#Sta/Elev= 30
    1574   499.2    1616     505    1751   506.5    1770   500.5    2197   498.1
    2427   491.2    3008   494.1    3243   503.5    3263   500.1    4131   500.5
    4268   501.9    4286   509.8    4528   510.1    4988   500.1    5001   504.2
 5803.74  493.66 6310.82  477.75 6703.26  473.62 7091.77  479.87 8540.35  479.36
 8720.79  486.66    8779   479.4    8787   467.5    8865     450    8900     447
    8964   454.5    9001   480.9   10667   481.7   11400   493.1   11743   507.1
#Mann= 3 ,0,0
    1574    .075       0    8779    .055       0    9001    .075       0
#XS Ineff= 3 ,-1
    1574    6244     510    6244    8779   479.4    9001   11743   480.9
Permanent Ineff=
       F       F       F
Bank Sta=8779,9001
XS Rating Curve= 0 ,0
Exp/Cntr=0.5,0.3

Type RM Length L Ch R = 1 ,154444  ,40,40,40
BEGIN DESCRIPTION:
154444
END DESCRIPTION:
XS GIS Cut Line= 6
   2375417.43061 6977288.3246735 2374900.7797613 6974085.0863637
 2374813.2727185 6972548.8532157 2374803.5496408 6970964.0053356
 2374769.5195252 6970638.2855146 2373893.9146491 6967159.2813177
#Sta/Elev= 30
    1490   500.3    1584   506.3    1783   503.7    1811     496    2110   491.8
    2948   489.7    3201     496    3247   490.1    3383   490.1    3536   504.4
    3554     500    4188   500.1    4207   509.6  5787.9  493.82 6306.26  477.88
 6702.72  473.66 7091.43  479.85 8544.29  479.44    8750   485.7    8750   478.5
    8801     476    8865     450    8900     447    8915     451    8930   467.5
    8973   472.5    8973   485.4  9575.4   479.3   10693     482   11774   506.2
#Mann= 3 ,0,0
    1490    .075       0    8750    .055       0    8973    .075       0
#XS Ineff= 2 ,-1
    1490    6244     510    6244    8750   477.8
Permanent Ineff=
       F       F
Bank Sta=8750,8973
XS Rating Curve= 0 ,0
Exp/Cntr=0.5,0.3

Type RM Length L Ch R = 3 ,154424  ,,,
BEGIN DESCRIPTION:
Precinct Line Road
END DESCRIPTION:
Node Name=Precinct Line Ro
Bridge Culvert--1,0,-1,-1, 0
Deck Dist Width WeirC Skew NumUp NumDn MinLoCord MaxHiCord MaxSubmerge Is_Ogee
1,38,2.6,0, 3, 3, , , 0.95, 0, ,,,
    8750    8865    8973
   486.2   486.4   486.2
   482.9   482.9   482.9
    8750    8865    8973
   486.2   486.4   486.2
   482.9   482.9   482.9
Pier Skew, UpSta & Num, DnSta & Num=  ,8771, 2 ,8771, 2 , 0 , 0 , 0 ,,
       2       2
     455     485
       2       2
     455     485
Pier Skew, UpSta & Num, DnSta & Num=  ,8799.5, 2 ,8799.5, 2 , 0 , 0 , 0 ,,
       3       3
     455     485
       3       3
     455     485
Pier Skew, UpSta & Num, DnSta & Num=  ,8823, 2 ,8823, 2 , 0 , 0 , 0 ,,
       4       4
     455     485
       4       4
     455     485
Pier Skew, UpSta & Num, DnSta & Num=  ,8922, 2 ,8922, 2 , 0 , 0 , 0 ,,
       4       4
     455     485
       4       4
     455     485
Pier Skew, UpSta & Num, DnSta & Num=  ,8946, 2 ,8946, 2 , 0 , 0 , 0 ,,
       2       2
     455     485
       2       2
     455     485
BR Coef= 1 , 0 , 0 ,1.05, 0 ,,,0.8,-1,0.5,1,
WSPro=,,,, 1 ,,,, 0 ,,,, 0 ,,,,-1 ,-1 ,-1 , 0 , 0 , 0 , 0 , 0
BC Design=,, 0 ,, 0 ,,,,,,
BC HTab HWMax=506.2
BC Use User HTab Curves=0
BC User HTab FreeFlow(D)= 0

Type RM Length L Ch R = 1 ,154404  ,1,1,1
BEGIN DESCRIPTION:
154404
END DESCRIPTION:
XS GIS Cut Line= 6
  2375453.266234 6977267.7661527 2374936.6153862 6974064.5278488
 2374849.1083362 6972528.2946988 2374839.3852662 6970943.4468188
 2374805.3551462 6970617.7269988 2373929.7502662 6967138.7227988
#Sta/Elev= 30
    1490   500.3    1584   506.3    1783   503.7    1811     496    2110   491.8
    2948   489.7    3201     496    3247   490.1    3383   490.1    3536   504.4
    3554     500    4188   500.1    4207   509.6    5185   502.2 6660.43  473.51
 6749.35  477.98    8750   485.7    8750   478.5    8801     476    8865     450
    8900     447    8900     451    8915     451    8930   467.5    8973   472.5
    8973   485.4  9549.5  480.04  9671.8   480.5   10737   482.4   11774   506.2
#Mann= 5 ,-1,0
    1490    .075       0    8750    .055       0    8973    .075       0
  9549.5    .075       0  9671.8    .075       0
#XS Ineff= 2 ,-1
    1490    6202     510    6202    8750   477.8
Permanent Ineff=
       F       F
Bank Sta=8750,8973
XS Rating Curve= 0 ,0
Exp/Cntr=0.5,0.3

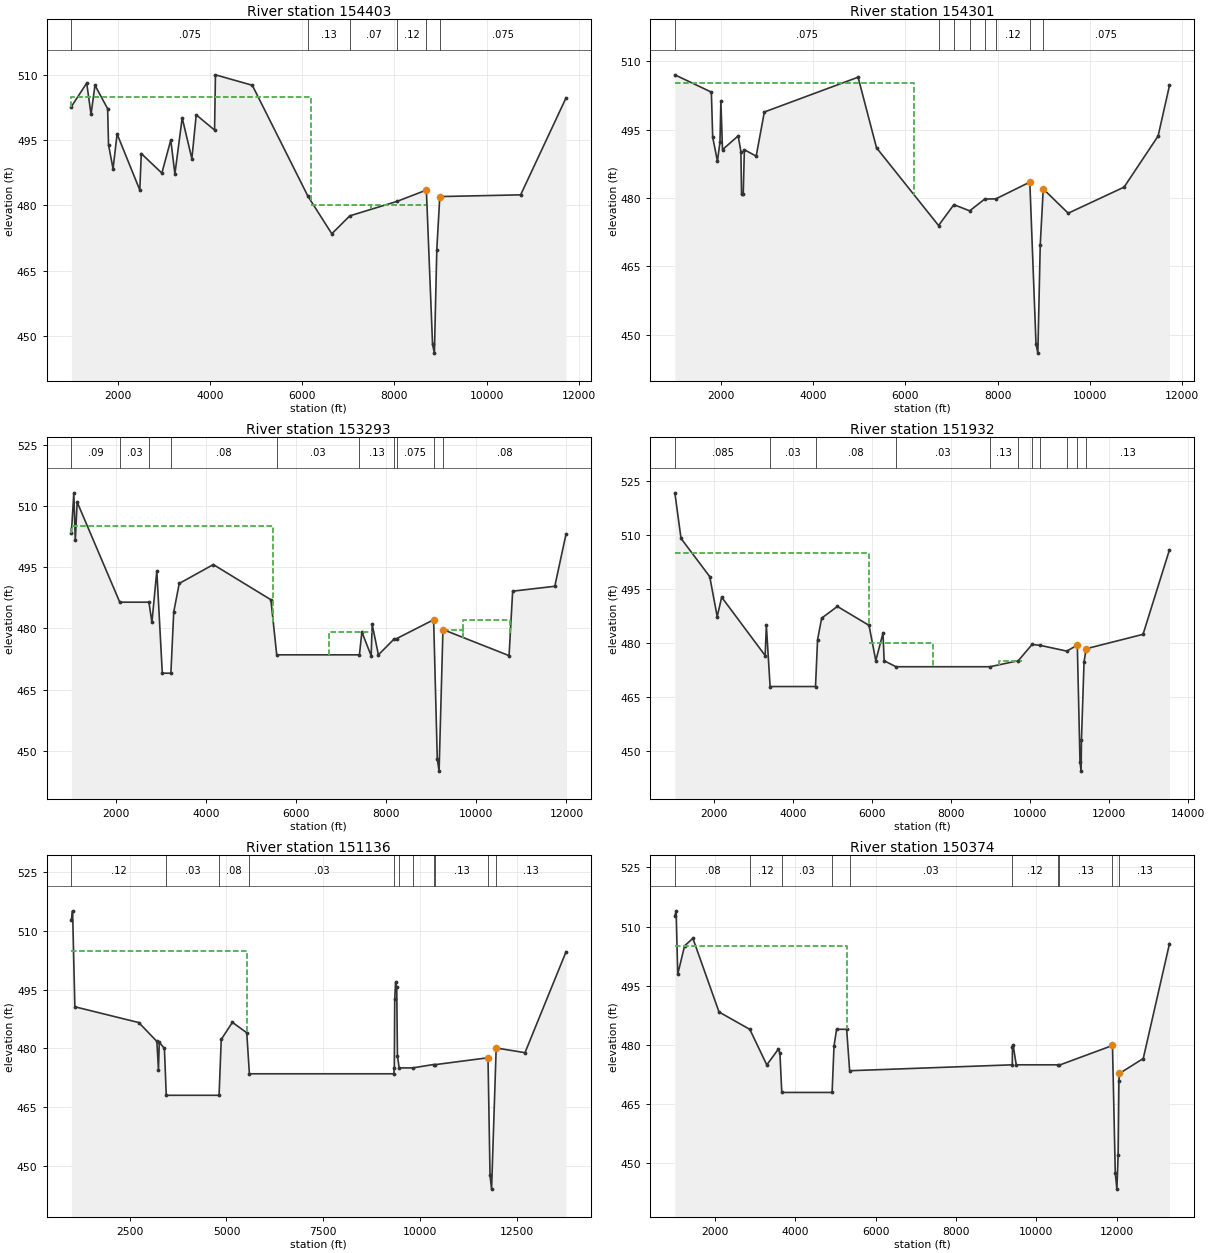
Type RM Length L Ch R = 1 ,154403  ,102,102,102
BEGIN DESCRIPTION:
154403
END DESCRIPTION:
XS GIS Cut Line= 6
    2375524.3271    6977702.0368      2374937.62      6974064.48
      2374850.14      6972528.37      2374840.39      6970943.44
      2374806.35      6970617.86      2373930.66      6967138.23
#Sta/Elev= 30
    1000   502.7    1332   508.1    1426   500.9    1511   507.6    1786   502.2
    1805   493.9    1903   488.4    1991   496.4    2483   483.5    2515   491.9
    2961   487.4    3155     495    3244   487.2    3402   500.1    3612   490.7
    3706   500.8    4104   497.3    4123     510    4922   507.6  6129.9  482.05
 6645.54  473.45 7036.15  477.57 8060.19   480.9    8696   483.5    8830     448
    8870     446    8922   469.8    8987     482   10740   482.4   11724   504.7
#Mann= 6 ,-1,0
    1000    .075       0  6129.9     .13       0 7036.15     .07       0
 8060.19     .12       0    8696    .055       0    8987    .075       0
#XS Ineff= 4 ,-1
    1000    6203     505    6203    7486     480    7486    8696   480.1
    8987   11724     482
Permanent Ineff=
       F       F       F       F
Bank Sta=8696,8987
XS Rating Curve= 0 ,0
Exp/Cntr=0.3,0.1

Type RM Length L Ch R = 1 ,154301  ,1200,1008,600
BEGIN DESCRIPTION:
154301
---------------------------------------------------------------------
CDC FW122816-1 Randol Mill Roundabout
Cross-section 154301 - 154527
Project in ROB.
---------------------------------------------------------------------
END DESCRIPTION:
XS GIS Cut Line= 6
  2375613.267176 6977650.5554074   2375026.55412     6974012.931
   2374939.04707   6972476.69785     2374929.324   6970891.84997
   2374895.29388   6970566.13015     2374019.689   6967087.12595
#Sta/Elev= 30
    1000  507.02 1791.68  503.23 1820.63  493.34 1923.31  488.09 1978.39  492.29
 1997.76  501.28 2033.08  490.61 2373.32  493.64 2431.84  490.19 2446.26  480.81
  2482.4  480.81 2507.19   490.6 2763.25  489.19 2940.48  498.87 4972.34   506.5
 5372.45  491.02 6717.53  473.98 7049.03  478.55 7392.67   477.2 7719.94   479.8
 7957.17  479.81    8696   483.5    8830     448    8870     446    8922   469.8
    8987     482    9528  476.68   10740   482.4   11477   493.6   11724   504.7
#Mann= 8 ,-1,0
    1000    .075       0 6717.53     .13       0 7049.03     .07       0
 7392.67     .12       0 7719.94    .035       0 7957.17     .12       0
    8696    .055       0    8987    .075       0
#XS Ineff= 3 ,-1
    1000    6186 505.147    6186    8696   480.1    8987   11724     482
Permanent Ineff=
       F       F       F
Bank Sta=8696,8987
XS Rating Curve= 0 ,0
Exp/Cntr=0.3,0.1

Type RM Length L Ch R = 1 ,153293  ,860,1361,950
BEGIN DESCRIPTION:
153293
END DESCRIPTION:
XS GIS Cut Line= 6
  2376636.219919 6977489.5995078   2376636.19985   6977489.38894
   2375925.88992   6970036.66008    2375036.4291   6968815.61888
   2374455.51884   6966908.72014 2374455.4571995 6966908.5177987
#Sta/Elev= 30
    1000  503.29  1053.8   513.2 1086.25  501.54 1127.92  510.93 2074.67   486.4
 2723.35   486.4 2789.14  481.44  2897.9  494.07 3019.91     469 3210.66     469
 3273.82     484 3396.12  490.99 4153.62  495.62 5432.74     487 5562.19   473.5
 7400.28   473.5 7454.46  479.11 7660.91  473.27 7683.29  480.95 7821.98   473.5
 8174.38  477.42    8226  477.47    9049   482.1    9130     448    9170     445
    9256   479.7   10725   473.3   10805   489.1   11741   490.3   11991   503.1
#Mann= 10 ,-1,0
    1000     .09       0 2074.67     .03       0 2723.35     .09       0
 3210.66     .08       0 5562.19     .03       0 7400.28     .13       0
 8174.38    .035       0    8226    .075       0    9049    .055       0
    9256     .08       0
#XS Ineff= 5 ,-1
  998.99  5485.7 505.027 6727.62 7683.29     479    7700    8000     475
    9256    9709   479.7    9709   10752     482
Permanent Ineff=
       F       T       T       T       T
Bank Sta=9049,9256
XS Rating Curve= 0 ,0
Exp/Cntr=0.3,0.1

Type RM Length L Ch R = 1 ,151932  ,800,796,1050
BEGIN DESCRIPTION:
151932
END DESCRIPTION:
XS GIS Cut Line= 3
  2378026.881175 6978442.6706785   2376553.11898   6968657.02012
 2374705.7128756 6966785.1333997
#Sta/Elev= 30
    1000  521.81 1156.67  509.14  1883.2  498.54 2072.37  487.43 2186.13  492.82
 3287.28   476.6 3317.09     485 3411.91     468    4562     468 4614.02     481
 4717.86     487 5115.98  490.25 5916.57     485  6088.7  475.19 6270.91  482.84
  6300.3  475.16 6600.01   473.5 8980.05   473.5 9696.97  475.17 10046.2  479.69
10247.23  479.45 10925.6  477.84   11192   479.5   11260     447   11288   444.5
   11297   453.2   11362   474.8   11416   478.5   12856   482.5   13526     506
#Mann= 11 ,-1,0
    1000    .085       0 3411.91     .03       0    4562     .08       0
 6600.01     .03       0 8980.05     .13       0 9696.97     .08       0
 10046.2    .035       010247.23     .08       0 10925.6     .13       0
   11192     .05       0   11416     .13       0
#XS Ineff= 4 ,-1
    1000 5916.57     505 5916.57    7542   480.1    9219    9800     475
   11416   13526   477.5
Permanent Ineff=
       F       T       T       T
Bank Sta=11192,11416
XS Rating Curve= 0 ,0
Exp/Cntr=0.3,0.1

Type RM Length L Ch R = 1 ,151136  ,430,762,900
BEGIN DESCRIPTION:
151136
END DESCRIPTION:
XS GIS Cut Line= 6
  2378559.604136 6978518.6939663 2378062.9548674 6973839.7476156
 2377819.8549599 6971550.0546884 2377544.9998666 6968961.7101276
 2376505.2814736 6967247.5255638 2375911.1061527 6966268.0068536
#Sta/Elev= 30
    1000  512.93 1030.53  515.18 1089.38  490.64 2738.85   486.6 3204.48  481.79
 3246.25  474.55 3266.88  481.56 3399.36     480 3447.52     468 4810.01     468
 4865.82  482.29 5153.86  486.66 5523.96     484 5592.18   473.5 9316.84   473.5
 9330.96     475 9341.08  492.52 9363.65  496.86 9392.74  495.57 9411.64  478.11
 9455.69     475 9800.33     47510342.33  475.8710376.96  475.83   11748   477.6
   11800   447.5   11840     444   11959   480.1   12702   478.9   13761   504.7
#Mann= 11 ,-1,0
    1000     .12       0 3447.52     .03       0 4810.01     .08       0
 5592.18     .03       0 9316.84     .12       0 9455.69     .03       0
 9800.33     .13       010342.33    .035       010376.96     .13       0
   11748     .05       0   11959     .13       0
#XS Ineff= 2 , 0
         5523.96     505   11959           478.9
Permanent Ineff=
       F       T
Bank Sta=11748,11959
XS Rating Curve= 0 ,0
Exp/Cntr=0.3,0.1

Type RM Length L Ch R = 1 ,150374  ,550,1172,1360
BEGIN DESCRIPTION:
150374
END DESCRIPTION:
XS GIS Cut Line= 3
   2378782.41111   6978502.98599   2378075.32886       6968907.1
 2377143.8019386 6966383.4347682
#Sta/Elev= 30
    1000  512.74 1031.92  514.02 1072.04  497.97 1242.49  505.14 1448.45  507.06
 2099.35  488.39 2866.02  483.98 3288.35  474.98 3575.63  478.96 3615.07     478
 3661.57     468 4914.35     468 4961.51  479.76 5025.96     484 5276.48     484
 5350.64   473.5 9398.51     475 9403.62  479.56 9419.09  479.99 9497.61     475
10534.85     47510569.56  474.92   11893   479.9   11963   447.5   12003   443.5
   12034   452.1   12053     471   12066   472.8   12659   476.6   13312   505.7
#Mann= 10 ,-1,0
    1000     .08       0 2866.02     .12       0 3661.57     .03       0
 4914.35     .08       0 5350.64     .03       0 9398.51     .12       0
10534.85    .035       010569.56     .13       0   11893     .05       0
   12066     .13       0
#XS Ineff= 2 , 0
         5276.48  505.16   12066           472.8
Permanent Ineff=
       F       T
Bank Sta=11893,12066
XS Rating Curve= 0 ,0
Exp/Cntr=0.3,0.1

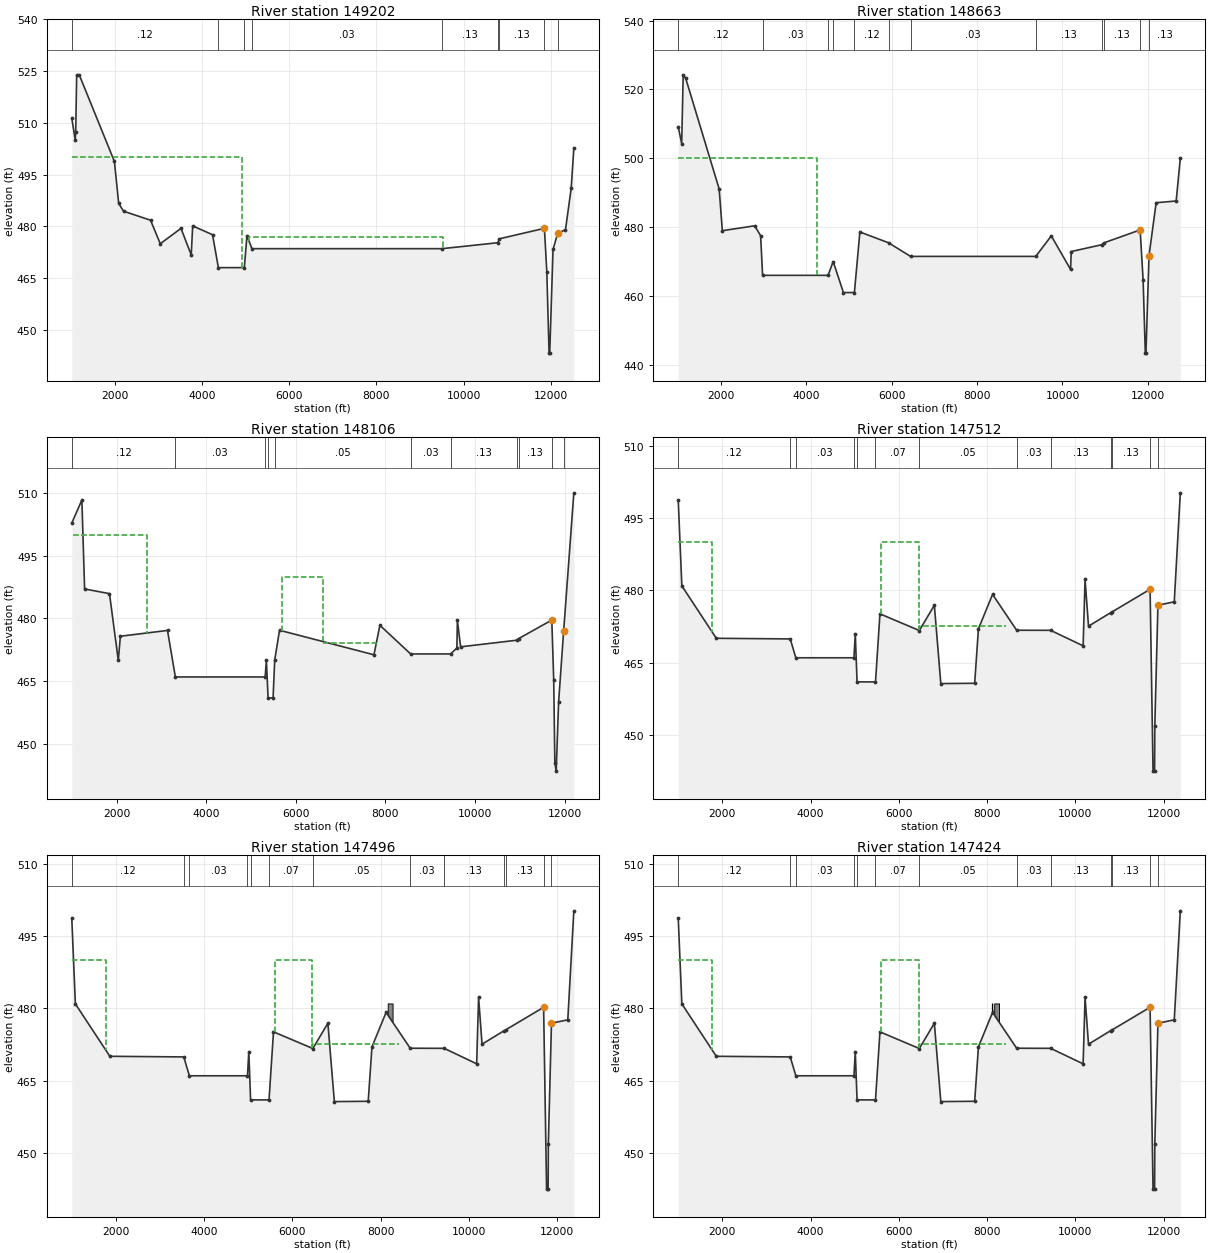
Type RM Length L Ch R = 1 ,149202  ,480,539,550
BEGIN DESCRIPTION:
149202
END DESCRIPTION:
XS GIS Cut Line= 2
  2379060.506912 6978457.0551653   2378708.55692   6966928.42614
#Sta/Elev= 30
    1000  511.34 1078.82  505.06 1090.16  507.29 1112.68   523.8 1171.84  523.92
 1979.36  498.79 2077.72  486.64 2188.49  484.37 2809.62  481.75 3033.37  474.93
 3508.88  479.38 3744.26  471.68 3777.56   480.1 4233.42  477.55 4368.21     468
  4964.2     468 5024.73  477.29 5138.18   473.5 9506.12   473.510787.85  475.22
10822.99  476.36   11858   479.4   11913   466.8   11965   443.2   11980   443.2
   12056   473.3   12165     478   12342     479   12473     491   12534   502.7
#Mann= 9 ,-1,0
    1000     .12       0 4368.21     .03       0  4964.2     .08       0
 5138.18     .03       0 9506.12     .13       010787.85    .035       0
10822.99     .13       0   11858     .05       0   12165     .12       0
#XS Ineff= 3 ,-1
 1000.01    4905     500    5072 9531.43     477   12165   12534   476.5
Permanent Ineff=
       F       T       T
Bank Sta=11858,12165
XS Rating Curve= 0 ,0
Exp/Cntr=0.3,0.1

Type RM Length L Ch R = 1 ,148663  ,900,557,500
BEGIN DESCRIPTION:
148663
END DESCRIPTION:
XS GIS Cut Line= 3
  2379467.410259 6978522.3299658   2379466.17516   6978455.19901
   2379251.08208   6966764.31984
#Sta/Elev= 30
    1000  509.14 1081.18  504.27    1116  524.26 1175.61  523.22  1958.7  491.09
 2033.37  478.97 2791.17   480.4 2929.97   477.5 2975.99     466 4508.78     466
  4629.4     470 4868.83     461 5126.04     461 5254.72   478.6 5925.59  475.46
 6441.95   471.5 9373.76   471.5 9738.36  477.4610188.96  467.7310205.37  472.92
10918.45  474.8910965.12  475.42   11819   479.2   11889   464.6   11940   443.4
   11955   443.4   12027   471.7   12194   487.1   12663   487.6   12760     500
#Mann= 12 ,-1,0
    1000     .12       0 2975.99     .03       0 4508.78     .08       0
  4629.4     .03       0 5126.04     .12       0 5925.59     .05       0
 6441.95     .03       0 9373.76     .13       010918.45    .035       0
10965.12     .13       0   11819     .05       0   12027     .13       0
#XS Ineff= 3 ,-1
    1000    4250     500 9705.1510971.54   472.5   12027   12760   471.7
Permanent Ineff=
       F       T       T
#Block Obstruct= 1 ,-1
 5397.18 5635.78  476.56
Bank Sta=11819,12027
XS Rating Curve= 0 ,0
Exp/Cntr=0.3,0.1

Type RM Length L Ch R = 1 ,148106  ,800,594,550
BEGIN DESCRIPTION:
148106 N-values: Modified to reflect excavation and lakes.
END DESCRIPTION:
XS GIS Cut Line= 3
  2380663.699414 6978369.1204873   2380042.69008   6968821.25011
 2379742.1518695 6967213.1374916
#Sta/Elev= 30
    1000  502.78 1225.65  508.28  1286.3  487.03 1841.53  485.91 2038.43  469.94
  2084.3  475.73 3136.31  477.12  3311.5     466 5315.28     466 5342.69     470
 5380.96     461 5492.36     461 5528.46     470 5636.03  477.16 7743.45   471.3
 7875.89  478.35 8562.28   471.5 9453.28   471.5 9593.68  472.91 9605.09  479.55
 9676.75   473.210930.22  474.7810974.41  475.18   11712   479.6   11755   465.2
   11780   445.5   11810   443.5   11864     460   11976   476.9   12204     510
#Mann= 11 ,-1,0
    1000     .12       0  3311.5     .03       0 5315.28     .08       0
 5380.96     .03       0 5528.46     .05       0 8562.28     .03       0
 9453.28     .13       010930.22    .035       010974.41     .13       0
   11712     .05       0   11976     .13       0
#XS Ineff= 4 ,-1
 1020.45    2670     500    5700    6600     490    6600    7790     474
    842411695.79   472.5
Permanent Ineff=
       F       F       T       T
Bank Sta=11712,11976
XS Rating Curve= 0 ,0
Exp/Cntr=0.3,0.1

Type RM Length L Ch R = 1 ,147512  ,16,16,16
BEGIN DESCRIPTION:
147512 Revised w/ 2014 DAS and 2009 TNRIS
N-values: Modified to reflect excavation and lakes.
END DESCRIPTION:
XS GIS Cut Line= 5
  2381689.690602 6978296.0682551   2381689.67596   6978295.92505
   2380694.93189   6968566.94484   2380231.07586   6967037.73793
  2380231.034075 6967037.6001762
#Sta/Elev= 30
    1000   498.7  1081.7  480.91 1862.86  470.04 3538.38  469.91 3665.17     466
 4981.78     466 5012.12     471 5052.58     461 5470.33     461 5571.45  475.11
 6463.29  471.65 6804.14  476.89 6950.59  460.65 7717.98  460.71 7802.81  471.99
 8123.19  479.14 8669.39  471.71 9439.14  471.6910175.42  468.4810219.33  482.24
10297.78  472.5510798.19  475.3510840.44  475.56   11693   480.2   11760   442.5
   11795   442.5   11800   451.8   11871   476.9   12241   477.6   12378   500.2
#Mann= 13 ,-1,0
    1000     .12       0 3538.38     .05       0 3665.17     .03       0
 4981.78     .08       0 5052.58     .03       0 5470.33     .07       0
 6463.29     .05       0 8669.39     .03       0 9439.14     .13       0
10798.19    .035       010840.44     .13       0   11693    .055       0
   11871     .13       0
#XS Ineff= 5 ,-1
    1000    1770     490    5600    6450     490    6450    8424   472.5
    842411695.79   472.5   11871   12378   476.9
Permanent Ineff=
       F       F       F       T       F
Bank Sta=11693,11871
XS Rating Curve= 0 ,0
Exp/Cntr=0.3,0.1

Type RM Length L Ch R = 1 ,147496  ,72,72,72
BEGIN DESCRIPTION:
147496 Revised w/ 2014 DAS and 2009 TNRIS
THIS SECTION WAS COPIED FROM 1475+12
1) THE 110' BLOCKED OBSTRUCTION MODELS THE BERM THAT THE TANKS WILL BE ELEVATED ON
END DESCRIPTION:
XS GIS Cut Line= 5
  2381698.477657 6978294.5800697  2381698.463016 6978294.4368689
 2380703.7189428  6968565.456655 2380239.8629152 6967036.2497397
 2380239.8211315 6967036.1119901
#Sta/Elev= 30
    1000   498.7  1081.7  480.91 1862.86  470.04 3538.38  469.91 3665.17     466
 4981.78     466 5012.12     471 5052.58     461 5470.33     461 5571.45  475.11
 6463.29  471.65 6804.14  476.89 6950.59  460.65 7717.98  460.71 7802.81  471.99
 8123.19  479.14 8669.39  471.71 9439.14  471.6910175.42  468.4810219.33  482.24
10297.78  472.5510798.19  475.3510840.44  475.56   11693   480.2   11760   442.5
   11795   442.5   11800   451.8   11871   476.9   12241   477.6   12378   500.2
#Mann= 13 ,-1,0
    1000     .12       0 3538.38     .05       0 3665.17     .03       0
 4981.78     .08       0 5052.58     .03       0 5470.33     .07       0
 6463.29     .05       0 8669.39     .03       0 9439.14     .13       0
10798.19    .035       010840.44     .13       0   11693    .055       0
   11871     .13       0
#XS Ineff= 5 ,-1
    1000    1770     490    5600    6450     490    6450    8424   472.5
    842411695.79   472.5   11871   12378   476.9
Permanent Ineff=
       F       F       F       T       F
#Block Obstruct= 1 ,-1
    8160    8270     481
Bank Sta=11693,11871
XS Rating Curve= 0 ,0
Exp/Cntr=0.3,0.1

Type RM Length L Ch R = 1 ,147424  ,10,10,10
BEGIN DESCRIPTION:
147424 Revised w/ 2014 DAS and 2009 TNRIS
THIS SECTION WAS COPIED FROM 1475+12
1) THE 10'  BLOCKED OBSTRUCTION REPRESENTS THE GAS WELL HEAD
2) THE 110' BLOCKED OBSTRUCTION MODELS THE BERM THAT THE TANKS WILL BE ELEVATED ON
END DESCRIPTION:
XS GIS Cut Line= 5
  2381740.376851 6978287.4849395   2381740.36221 6978287.3417387
 2380745.6181372 6968558.3615248 2380281.7621096 6967029.1546095
 2380281.7203258 6967029.0168598
#Sta/Elev= 30
    1000   498.7  1081.7  480.91 1862.86  470.04 3538.38  469.91 3665.17     466
 4981.78     466 5012.12     471 5052.58     461 5470.33     461 5571.45  475.11
 6463.29  471.65 6804.14  476.89 6950.59  460.65 7717.98  460.71 7802.81  471.99
 8123.19  479.14 8669.39  471.71 9439.14  471.6910175.42  468.4810219.33  482.24
10297.78  472.5510798.19  475.3510840.44  475.56   11693   480.2   11760   442.5
   11795   442.5   11800   451.8   11871   476.9   12241   477.6   12378   500.2
#Mann= 13 ,-1,0
    1000     .12       0 3538.38     .05       0 3665.17     .03       0
 4981.78     .08       0 5052.58     .03       0 5470.33     .07       0
 6463.29     .05       0 8669.39     .03       0 9439.14     .13       0
10798.19    .035       010840.44     .13       0   11693    .055       0
   11871     .13       0
#XS Ineff= 5 ,-1
    1000    1770     490    5600    6450     490    6450    8424   472.5
    842411695.79   472.5   11871   12378   476.9
Permanent Ineff=
       F       F       F       T       F
#Block Obstruct= 2 ,-1
    8107    8117     481    8160    8270     481
Bank Sta=11693,11871
XS Rating Curve= 0 ,0
Exp/Cntr=0.3,0.1

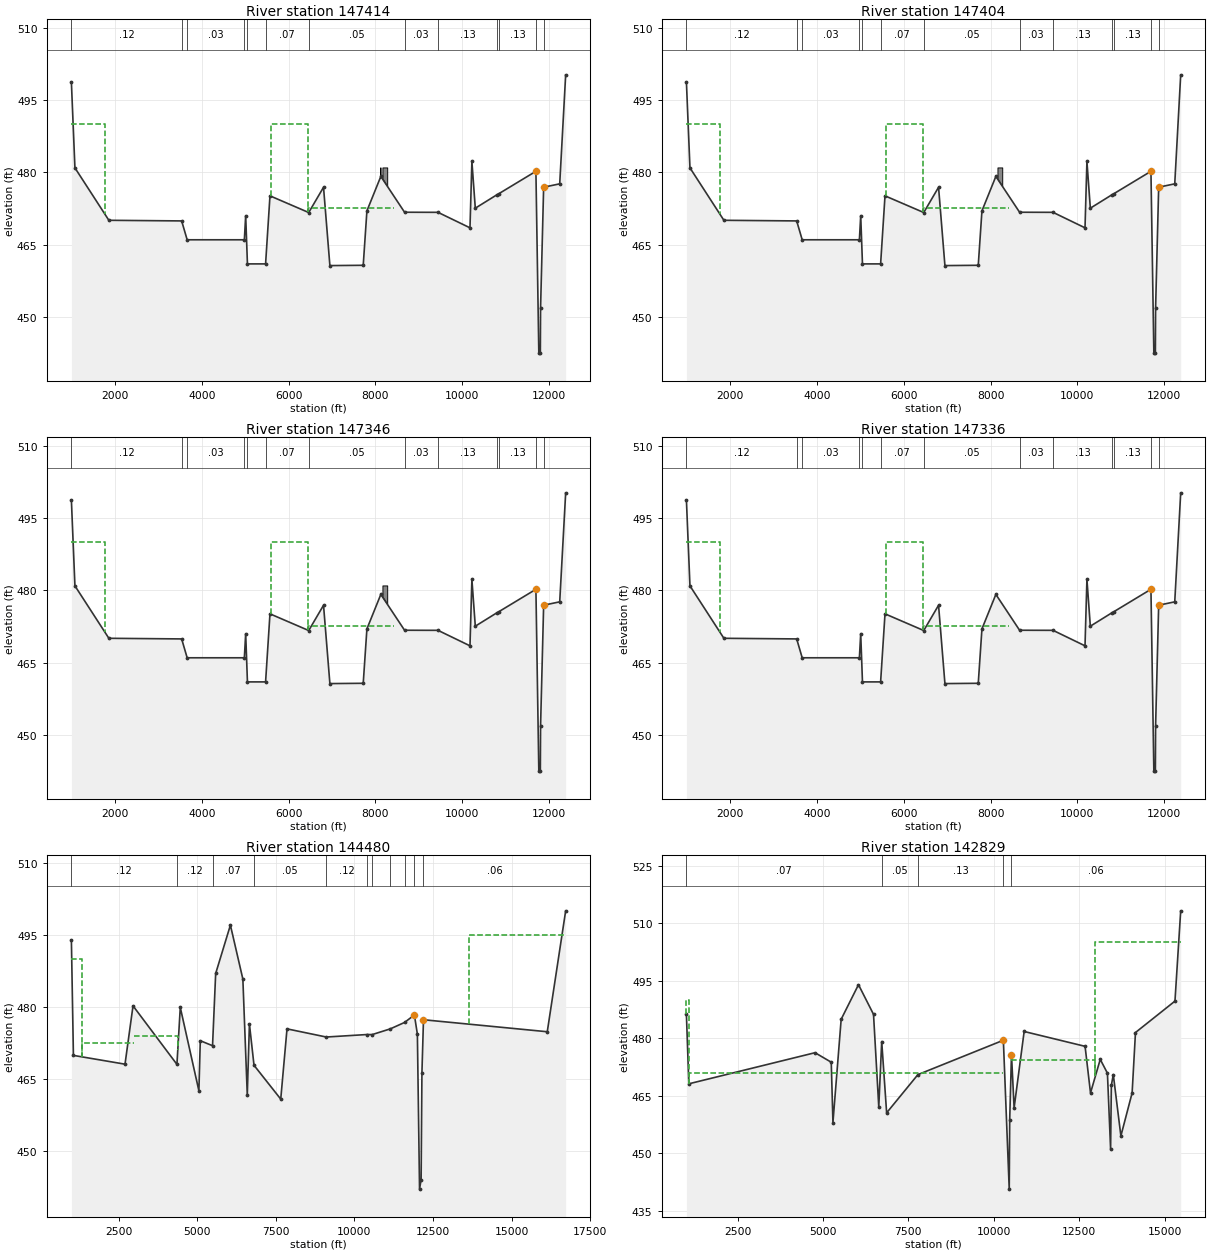
Type RM Length L Ch R = 1 ,147414  ,10,10,10
BEGIN DESCRIPTION:
147414 Revised w/ 2014 DAS and 2009 TNRIS
THIS SECTION WAS COPIED FROM 1475+12
1) THE 10'  BLOCKED OBSTRUCTION REPRESENTS THE GAS WELL HEAD
2) THE 110' BLOCKED OBSTRUCTION MODELS THE BERM THAT THE TANKS WILL BE ELEVATED ON
END DESCRIPTION:
XS GIS Cut Line= 5
   2381785.09625  6978280.588956  2381785.081609 6978280.4457552
  2380790.337536 6968551.4655412 2380326.4815083 6967022.2586259
 2380326.4397246 6967022.1208763
#Sta/Elev= 30
    1000   498.7  1081.7  480.91 1862.86  470.04 3538.38  469.91 3665.17     466
 4981.78     466 5012.12     471 5052.58     461 5470.33     461 5571.45  475.11
 6463.29  471.65 6804.14  476.89 6950.59  460.65 7717.98  460.71 7802.81  471.99
 8123.19  479.14 8669.39  471.71 9439.14  471.6910175.42  468.4810219.33  482.24
10297.78  472.5510798.19  475.3510840.44  475.56   11693   480.2   11760   442.5
   11795   442.5   11800   451.8   11871   476.9   12241   477.6   12378   500.2
#Mann= 13 ,-1,0
    1000     .12       0 3538.38     .05       0 3665.17     .03       0
 4981.78     .08       0 5052.58     .03       0 5470.33     .07       0
 6463.29     .05       0 8669.39     .03       0 9439.14     .13       0
10798.19    .035       010840.44     .13       0   11693    .055       0
   11871     .13       0
#XS Ineff= 5 ,-1
    1000    1770     490    5600    6450     490    6450    8424   472.5
    842411695.79   472.5   11871   12378   476.9
Permanent Ineff=
       F       F       F       T       F
#Block Obstruct= 2 ,-1
    8107    8117     481    8160    8270     481
Bank Sta=11693,11871
XS Rating Curve= 0 ,0
Exp/Cntr=0.3,0.1

Type RM Length L Ch R = 1 ,147404  ,58,58,58
BEGIN DESCRIPTION:
147404 Revised w/ 2014 DAS and 2009 TNRIS
THIS SECTION WAS COPIED FROM 1475+12
1) THE 110' BLOCKED OBSTRUCTION MODELS THE BERM THAT THE TANKS WILL BE ELEVATED ON
END DESCRIPTION:
XS GIS Cut Line= 5
  2381790.800307 6978279.7418448  2381790.785666  6978279.598644
 2380796.0415928 6968550.6184301 2380332.1855652 6967021.4115147
 2380332.1437815 6967021.2737651
#Sta/Elev= 30
    1000   498.7  1081.7  480.91 1862.86  470.04 3538.38  469.91 3665.17     466
 4981.78     466 5012.12     471 5052.58     461 5470.33     461 5571.45  475.11
 6463.29  471.65 6804.14  476.89 6950.59  460.65 7717.98  460.71 7802.81  471.99
 8123.19  479.14 8669.39  471.71 9439.14  471.6910175.42  468.4810219.33  482.24
10297.78  472.5510798.19  475.3510840.44  475.56   11693   480.2   11760   442.5
   11795   442.5   11800   451.8   11871   476.9   12241   477.6   12378   500.2
#Mann= 13 ,-1,0
    1000     .12       0 3538.38     .05       0 3665.17     .03       0
 4981.78     .08       0 5052.58     .03       0 5470.33     .07       0
 6463.29     .05       0 8669.39     .03       0 9439.14     .13       0
10798.19    .035       010840.44     .13       0   11693    .055       0
   11871     .13       0
#XS Ineff= 5 ,-1
    1000    1770     490    5600    6450     490    6450    8424   472.5
    842411695.79   472.5   11871   12378   476.9
Permanent Ineff=
       F       F       F       T       F
#Block Obstruct= 1 ,-1
    8160    8270     481
Bank Sta=11693,11871
XS Rating Curve= 0 ,0
Exp/Cntr=0.3,0.1

Type RM Length L Ch R = 1 ,147346  ,10,10,10
BEGIN DESCRIPTION:
147346 Revised w/ 2014 DAS and 2009 TNRIS
THIS SECTION WAS COPIED FROM 1475+12
1) THE 110' BLOCKED OBSTRUCTION MODELS THE BERM THAT THE TANKS WILL BE ELEVATED ON
END DESCRIPTION:
XS GIS Cut Line= 3
      2381848.81       6978274.3      2380854.37      6968545.83
       2380389.6      6967014.01
#Sta/Elev= 30
    1000   498.7  1081.7  480.91 1862.86  470.04 3538.38  469.91 3665.17     466
 4981.78     466 5012.12     471 5052.58     461 5470.33     461 5571.45  475.11
 6463.29  471.65 6804.14  476.89 6950.59  460.65 7717.98  460.71 7802.81  471.99
 8123.19  479.14 8669.39  471.71 9439.14  471.6910175.42  468.4810219.33  482.24
10297.78  472.5510798.19  475.3510840.44  475.56   11693   480.2   11760   442.5
   11795   442.5   11800   451.8   11871   476.9   12241   477.6   12378   500.2
#Mann= 13 ,-1,0
    1000     .12       0 3538.38     .05       0 3665.17     .03       0
 4981.78     .08       0 5052.58     .03       0 5470.33     .07       0
 6463.29     .05       0 8669.39     .03       0 9439.14     .13       0
10798.19    .035       010840.44     .13       0   11693    .055       0
   11871     .13       0
#XS Ineff= 5 ,-1
    1000    1770     490    5600    6450     490    6450    8424   472.5
    842411695.79   472.5   11871   12378   476.9
Permanent Ineff=
       F       F       F       T       F
#Block Obstruct= 1 ,-1
    8160    8270     481
Bank Sta=11693,11871
XS Rating Curve= 0 ,0
Exp/Cntr=0.3,0.1

Type RM Length L Ch R = 1 ,147336  ,724,2856,2794
BEGIN DESCRIPTION:
147346 Revised w/ 2014 DAS and 2009 TNRIS
THIS SECTION WAS COPIED FROM 1475+12 AND MODELS THE AREA IMMEDIATELY DOWNSTREAM OF THE BLOCKED OBSTRUCTION
---------------------------------------------------------------------
CDC FW122804-01 Gas Well Duck Lake No.1
Located in LOB.
Cross-sections 147336 - 147496
---------------------------------------------------------------------
END DESCRIPTION:
XS GIS Cut Line= 3
       2381859.3      6978272.91       2380864.8      6968545.85
      2380399.76      6967012.49
#Sta/Elev= 30
    1000   498.7  1081.7  480.91 1862.86  470.04 3538.38  469.91 3665.17     466
 4981.78     466 5012.12     471 5052.58     461 5470.33     461 5571.45  475.11
 6463.29  471.65 6804.14  476.89 6950.59  460.65 7717.98  460.71 7802.81  471.99
 8123.19  479.14 8669.39  471.71 9439.14  471.6910175.42  468.4810219.33  482.24
10297.78  472.5510798.19  475.3510840.44  475.56   11693   480.2   11760   442.5
   11795   442.5   11800   451.8   11871   476.9   12241   477.6   12378   500.2
#Mann= 13 ,-1,0
    1000     .12       0 3538.38     .05       0 3665.17     .03       0
 4981.78     .08       0 5052.58     .03       0 5470.33     .07       0
 6463.29     .05       0 8669.39     .03       0 9439.14     .13       0
10798.19    .035       010840.44     .13       0   11693    .055       0
   11871     .13       0
#XS Ineff= 5 ,-1
    1000    1770     490    5600    6450     490    6450    8424   472.5
    842411695.79   472.5   11871   12378   476.9
Permanent Ineff=
       F       F       F       T       F
Bank Sta=11693,11871
XS Rating Curve= 0 ,0
Exp/Cntr=0.3,0.1

Type RM Length L Ch R = 1 ,144480  ,675,1651,590
BEGIN DESCRIPTION:
144480 Revised w/ 2014 DAS and 2009 TNRIS
---------------------------------------------------------------------
CDC FW 040717-01 Trinity Lakes
Project in LOB.
Cross-section 144480 - 154445
---------------------------------------------------------------------
END DESCRIPTION:
XS GIS Cut Line= 6
  2382309.234191 6978250.7684955   2382309.22295   6978250.58689
   2381668.19011    6967894.5889   2382944.88999   6966391.44886
   2384525.29496   6963417.65101 2384525.3803485 6963417.4903373
#Sta/Elev= 30
    1000  493.93 1064.78  469.87 2705.14  468.04 2959.79   480.2 4356.04     468
 4462.57  479.87 5054.31   462.5 5098.81  472.93  5488.1  471.89 5587.84  486.94
 6056.02  497.02 6452.26  485.78 6592.65  461.64 6660.83  476.42 6806.72  467.81
 7656.64  460.76 7855.87   475.4 9104.78   473.710403.14  474.2210564.55  474.21
11140.39   475.411594.03  476.74   11906   478.3   12001   474.3   12070     442
   12120     444   12146   466.3   12195   477.3   16131   474.8   16716     500
#Mann= 11 ,-1,0
    1000     .12       0 4356.04     .12       0  5488.1     .07       0
 6806.72     .05       0 9104.78     .12       010403.14     .08       0
10564.55     .12       011140.39    .035       011594.03     .12       0
   11906     .05       0   12195     .06       0
#XS Ineff= 7 ,-1
    1000    1343     490    1343    3000   472.4    3000 4382.72     474
    6500    7881   472.4    7881   10260   472.4   12195   13630   475.3
   13630   16716     495
Permanent Ineff=
       F       F       T       F       T       F       T
#Block Obstruct= 1 ,-1
 5015.26 5134.95   462.5
Bank Sta=11906,12195
XS Rating Curve= 0 ,0
Exp/Cntr=0.3,0.1

Type RM Length L Ch R = 1 ,142829  ,27,27,27
XS GIS Cut Line= 6
     2382860.835     6978223.473     2382668.216     6973992.727
      2382576.63     6973877.436      2382378.25     6969527.506
     2382593.053     6967962.481     2384861.041     6964481.326
#Sta/Elev= 30
    1003  486.16    1074  468.09 4767.74   476.2 5242.68  473.72 5292.19     458
 5533.21  484.92 6040.09  493.93 6479.99   486.2 6633.95  462.09 6719.93  479.11
  6863.9  460.52 7778.68  470.4810280.86  479.45 10452.7  440.6310466.69  458.77
10518.64  475.7110595.57  461.8210889.31  481.7312672.92  477.8612831.92  465.71
13116.92  474.4613326.92  470.8613419.92  451.0913441.92  467.6913498.92   470.5
13720.92   454.514049.92  465.7114147.92  481.4615303.92  489.6515471.92  513.19
#Mann= 5 ,-1,0
    1003     .07       0 6719.93     .05       0 7778.68     .13       0
10280.86    .055       010518.64     .06       0
#XS Ineff= 4 ,-1
    1003    1080     490    1080   10256     47110518.6412974.92   474.4
12974.92   15471     505
Permanent Ineff=
       F       F       F       T
Bank Sta=10280.86,10518.64
XS Rating Curve= 0 ,0
Exp/Cntr=0.3,0.1