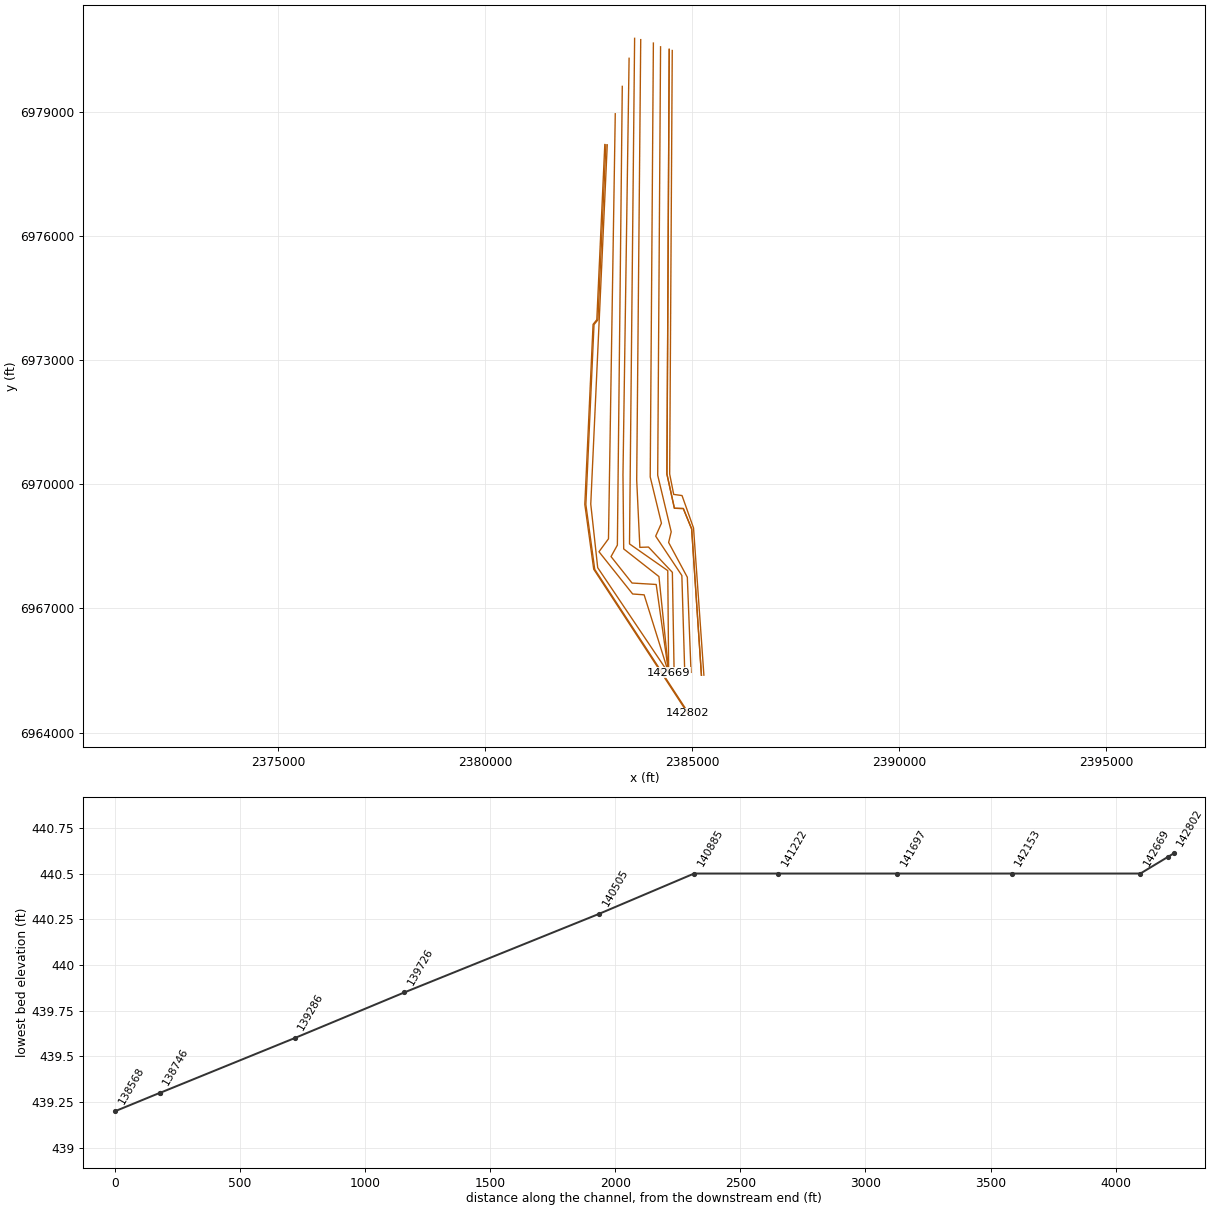
HEC-RAS study CDC_Consolidated_Model.prj: Upper Trinity CDC Consolidated Model

--- CDC_Consolidated_Model.g12 (geometry) --- (continued)

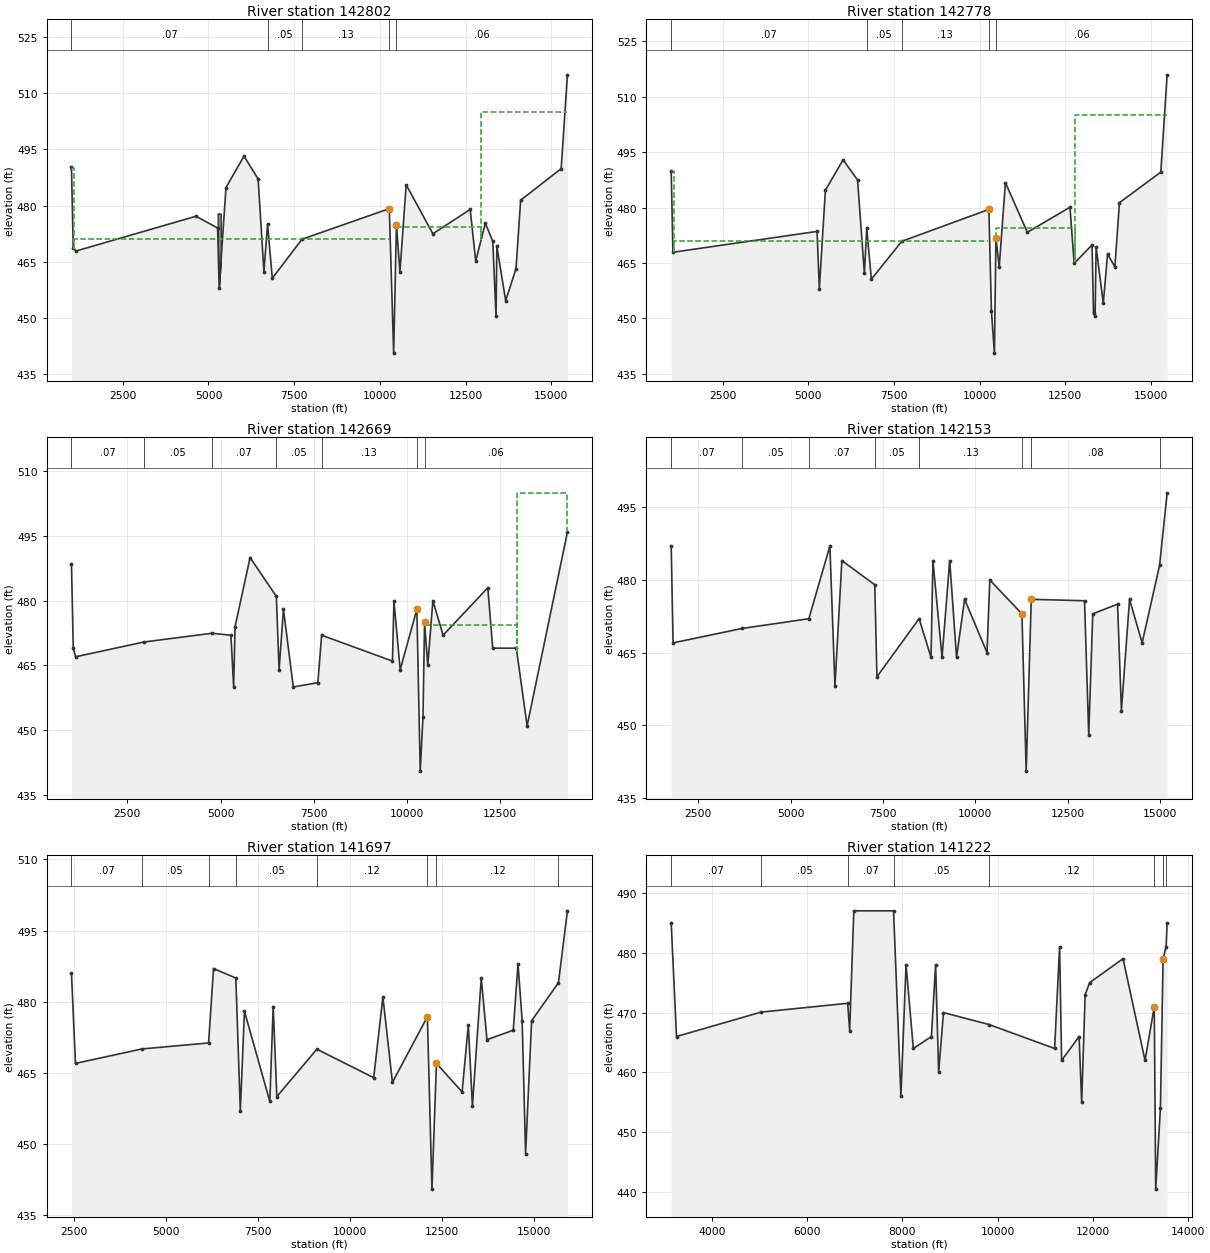
Type RM Length L Ch R = 1 ,142802  ,24,24,24
BEGIN DESCRIPTION:
Created with Pecos 2019 LiDAR
CDC FW 053222-1 Trinity Trails East Phase 2
Added cross-section.
Project located in LOB.
Walker Branch culvert blocked obstruction.
END DESCRIPTION:
XS GIS Cut Line= 6
     2382890.127     6978210.016     2382697.215      6973976.85
     2382606.726     6973863.033     2382407.496     6969513.936
     2382622.406     6967946.886     2384890.304     6964467.632
#Sta/Elev= 30
    1003  490.15    1055  468.65 1132.99  467.85 4636.75  477.14 5266.37     474
 5312.28     458 5511.21  484.81 6036.09  493.18 6447.99  487.11 6617.95  462.39
 6723.93  474.99  6861.9   460.6 7728.69  471.0110275.86  479.1710402.77  440.61
10483.67  474.7710585.58  462.3710768.42  485.5311546.92  472.4612635.92  478.96
12796.92  465.1513076.92   475.313293.92  470.4613389.92   450.413412.92  469.13
13670.92  454.6113970.92  463.1214107.92  481.4215289.92  489.8515471.92  514.88
#Mann= 5 ,-1,0
    1003     .07       0 6723.93     .05       0 7728.69     .13       0
10275.86    .055       010483.67     .06       0
#XS Ineff= 4 ,-1
    1003    1080     490    1080   10256     47110483.67   12950   474.4
   12950   15471     505
Permanent Ineff=
       F       F       F       T
#Block Obstruct= 1 ,-1
 5264.79 5359.07   477.9
Bank Sta=10275.86,10483.67
XS Rating Curve= 0 ,0
Exp/Cntr=0.3,0.1

Type RM Length L Ch R = 1 ,142778  ,34,109,119
BEGIN DESCRIPTION:
Created with Pecos 2019 LiDAR
CDC FW 053222-1 Trinity Trails East Phase 2
Added cross-section.
Project located in LOB.
END DESCRIPTION:
XS GIS Cut Line= 6
     2382916.972     6978202.973     2382723.879     6973973.721
     2382629.756     6973858.683     2382432.919     6969508.515
     2382646.968     6967942.121     2384915.333     6964462.304
#Sta/Elev= 30
    1003  489.94    1054   467.9 5258.63  473.54 5324.73     458 5501.21  484.66
 6017.09  492.92    6440  487.48 6638.95  462.15 6707.93  474.38  6842.9   460.6
 7728.69  470.8610270.87  479.49 10345.8  451.8910432.72  440.5910476.68  471.75
10572.59  463.9310753.43  486.7511393.92  473.2912636.92  480.0912758.92  464.88
13280.92  469.8713323.92  451.3413369.92  450.6113398.92  469.3313608.92  454.13
13733.92  467.4113947.92  463.9314079.92  481.3215286.92  489.5915471.92  515.93
#Mann= 5 ,-1,0
    1003     .07       0 6707.93     .05       0 7728.69     .13       0
10270.87    .055       010476.68     .06       0
#XS Ineff= 4 ,-1
    1003    1080     490    1080   10256     47110476.68   12790   474.4
   12790   15471     505
Permanent Ineff=
       F       F       F       T
Bank Sta=10270.87,10476.68
XS Rating Curve= 0 ,0
Exp/Cntr=0.3,0.1

Type RM Length L Ch R = 1 ,142669  ,260,515,390
BEGIN DESCRIPTION:
Kimley-Horn updated cross section based on on-ground survey and proposed grading for Bell South Airfiled property and TNRIS 2009 LiDAR offsite. Channel flowline interpolated from effective model. (KH, 2017)
END DESCRIPTION:
XS GIS Cut Line= 4
  2382949.248654 6978203.3749724   2382551.17916   6969520.17915
   2382718.62994   6967983.55887 2384427.4746787  6965440.382665
#Sta/Elev= 30
    1000  488.45 1048.76     469 1111.52     467 2945.53  470.43 4767.68  472.45
 5278.52     472 5351.22     460 5389.59     474 5792.04     490 6496.68     481
 6570.56     464 6687.95     478  6951.7     460 7610.62     461 7712.13     472
 9612.55     466 9651.83     480 9819.04     46410267.05     47810357.44   440.5
10431.29     45310473.41     47510560.01     46510696.64     48010971.06     472
12170.83     483 12302.3     46912935.48     469 13225.2     45114306.44  495.89
#Mann= 7 ,-1,0
    1000     .07       0 2945.53     .05       0 4767.68     .07       0
 6496.68     .05       0 7712.13     .13       010267.05    .055       0
10473.41     .06       0
#XS Ineff= 3 ,-1
    1003   10256     471   10476   12950   474.4   12950   14305     505
Permanent Ineff=
       F       F       T
Bank Sta=10267.05,10473.41
XS Rating Curve= 0 ,0
Exp/Cntr=0.3,0.1

Type RM Length L Ch R = 1 ,142153  ,230,456,345
BEGIN DESCRIPTION:
Kimley-Horn added cross section based on on-ground survey and proposed grading for Bell South Airfiled property and TNRIS 2009 LiDAR offsite. Channel flowline interpolated from effective model. (KH, 2017)
END DESCRIPTION:
XS GIS Cut Line= 6
  2383142.6432376978953.611695562382978.942426896968681.18692705
2382749.775760236968368.68692704 2383562.27576026967347.85359371
2383840.053537996967327.020260382384421.303538026965467.29803817
#Sta/Elev= 30
 1770.48     487 1821.49     467 3690.09  469.98 5494.21  471.99 6063.64     487
 6200.66     458 6387.61     484 7277.65     479  7337.2     460 8477.28     472
 8799.83     464 8851.17     484 9097.85     464 9304.97     484 9490.45     464
 9708.37     47610314.04     46510390.07     48011258.63     47311374.28   440.5
11511.95     47612952.52   475.713066.21     44813175.38     47313846.03     475
13950.86     45314170.53     47614511.35     46714982.61     48315187.77     498
#Mann= 8 ,-1,0
 1770.48     .07       0 3690.09     .05       0 5494.21     .07       0
 7277.65     .05       0 8477.28     .13       011258.63    .055       0
11511.95     .08       014982.61     .03       0
#XS Ineff= 2 ,-1
 7277.65 8477.28     460 8477.2811258.63     470
Permanent Ineff=
       T       T
Bank Sta=11258.63,11511.95
XS Rating Curve= 0 ,0
Exp/Cntr=0.3,0.1

Type RM Length L Ch R = 1 ,141697  ,240,476,360
BEGIN DESCRIPTION:
Kimley-Horn added cross section based on on-ground survey and proposed grading for Bell South Airfiled property and TNRIS 2009 LiDAR offsite. Channel flowline interpolated from effective model. (KH, 2017)
END DESCRIPTION:
XS GIS Cut Line= 6
   2383312.15638 6979616.43458482383193.522120776968529.19500145
2383040.744343046968251.417223682383547.688787466967612.52833478
2384131.022120776967577.806112562384423.846194896965498.45136721
#Sta/Elev= 30
 2436.18     486 2545.87     467 4349.06  470.05 6160.72  471.32 6294.96     487
 6900.34     485 7022.49     457 7134.56     478 7823.23     459 7915.36     479
  8014.3     460 9100.18     47010645.12     464 10894.9     48111153.71     463
12103.83  476.8612227.23   440.512348.91     46713046.18     46113214.91   475.1
13326.49     45813566.67     48513721.41     47214435.69     47414564.93     488
14677.57     47614770.51     44814934.16     47615662.78     48415906.67  499.17
#Mann= 8 ,-1,0
 2436.18     .07       0 4349.06     .05       0 6160.72     .07       0
 6900.34     .05       0 9100.18     .12       012103.83    .055       0
12348.91     .12       015662.78     .03       0
#XS Ineff= 2 ,-1
 6900.34 9100.18     460 9100.1812103.83     470
Permanent Ineff=
       T       T
Bank Sta=12103.83,12348.91
XS Rating Curve= 0 ,0
Exp/Cntr=0.3,0.1

Type RM Length L Ch R = 1 ,141222  ,170,337,255
BEGIN DESCRIPTION:
Kimley-Horn added cross section based on on-ground survey and proposed grading for Bell South Airfiled property and TNRIS 2009 LiDAR offsite. Channel flowline interpolated from effective model. (KH, 2017)
END DESCRIPTION:
XS GIS Cut Line= 5
  2383476.5082316980294.820001452383328.938787466970225.37555701
2383346.299898596968437.181112572384196.99434304 6967768.7783348
2384422.327097716965566.73840426
#Sta/Elev= 30
 3145.85     485 3257.36     466  5034.6  470.08 6850.44  471.55 6892.37     467
 6979.92     487 7813.85     487 7968.58     456 8075.82     478 8229.43     464
 8608.65     466 8697.14     478 8760.27     460 8861.56     470 9819.54     468
11195.33     46411300.06     48111342.01     46211709.12     46611762.71     455
11835.99     47311930.81     47512631.34     47913093.61     46213287.23     471
13317.22   440.513416.01     45413472.58     47913535.13     481 13557.5     485
#Mann= 8 ,-1,0
 3145.85     .07       0  5034.6     .05       0 6850.44     .07       0
 7813.85     .05       0 9819.54     .12       013287.23    .055       0
13472.58     .12       013535.13     .03       0
#XS Ineff= 2 ,-1
 6979.92 8638.16     460 8638.1613287.23     470
Permanent Ineff=
       T       T
Bank Sta=13287.23,13472.58
XS Rating Curve= 0 ,0
Exp/Cntr=0.3,0.1

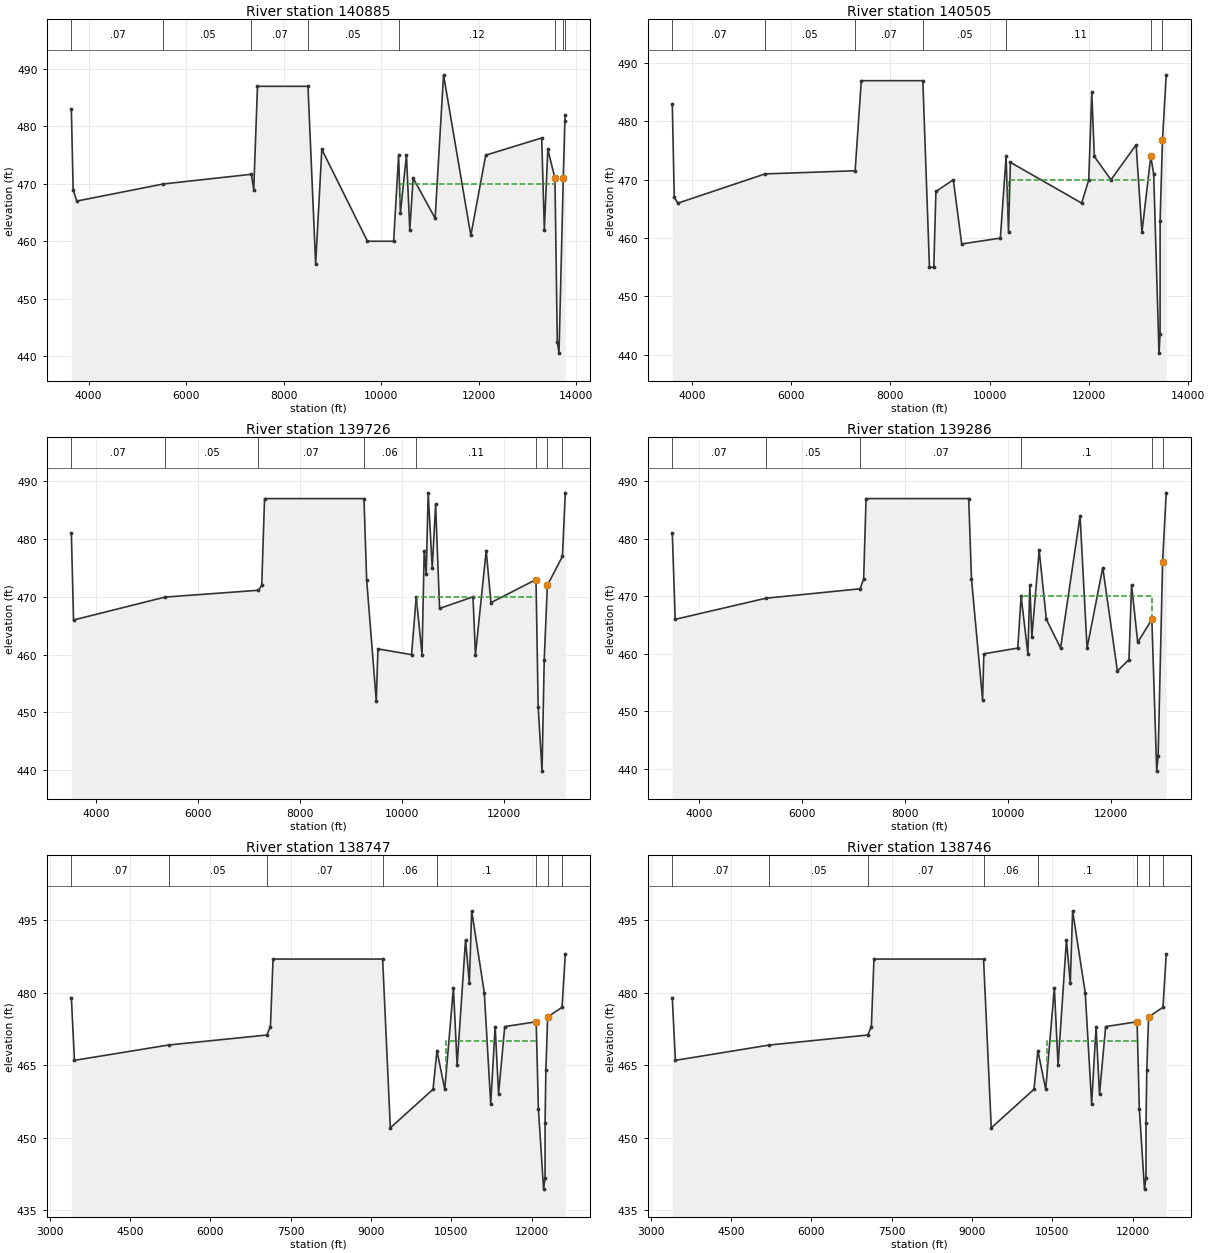
Type RM Length L Ch R = 1 ,140885  ,165,379,340
BEGIN DESCRIPTION:
Kimley-Horn updated cross section based on on-ground survey and proposed grading for Bell South Airfiled property and TNRIS 2009 LiDAR offsite. Channel flowline interpolated from effective model. (KH, 2017)
---------------------------------------------------------------------
CDC FW121505-1 Bell Station Tract
This project is located between cross-sections 140885 - 147512 and within ineffective flow area, therefore the model was not changed.
--------------------------------------------------------------
END DESCRIPTION:
XS GIS Cut Line= 4
  2383609.8270976980776.807848712383486.563208796968558.05784871
2384410.174319866967912.224515362384431.094458796965555.62729315
#Sta/Elev= 30
  3646.1     483 3682.73     469 3757.21     467 5532.29  469.98 7338.33  471.67
 7386.67     469 7463.42     487 8499.08     487 8656.65     456    8783     476
  9719.5     46010256.42     46010357.87     47510395.18     46510518.99     475
10587.28     46210656.76     47111106.81     46411279.43     48911839.29     461
12144.56     47513292.97     47813346.82     46213418.45     47613564.49     471
13612.74   442.513647.74   440.513735.16     47113768.16     48113776.58     482
#Mann= 8 ,-1,0
  3646.1     .07       0 5532.29     .05       0 7338.33     .07       0
 8499.08     .05       010357.87     .12       013564.49    .055       0
13735.16    .055       013768.16     .03       0
#XS Ineff= 2 ,-1
 8499.0810388.48     46010388.4813564.49     470
Permanent Ineff=
       T       T
Bank Sta=13564.49,13735.16
XS Rating Curve= 0 ,0
Exp/Cntr=0.3,0.1

Type RM Length L Ch R = 1 ,140505  ,338,779,698
BEGIN DESCRIPTION:
Kimley-Horn added cross section based on on-ground survey and proposed grading for Bell South Airfiled property and TNRIS 2009 LiDAR offsite. Channel flowline interpolated from effective model. (KH, 2017)
END DESCRIPTION:
XS GIS Cut Line= 6
  2383757.3965426980745.557848692383660.174319896970099.72451538
2383736.563208766968474.72451538 2383944.89654216968481.66895983
  2384521.2854316967870.557848712384562.952097656965502.50229314
#Sta/Elev= 30
 3604.66     483 3644.51     467 3718.86     466 5473.15  471.01 7288.47  471.55
 7413.02     487 8653.04     487 8786.16     455 8873.63     455 8916.51     468
 9266.83     470 9435.89     45910214.73     46010330.63     47410378.93     461
10417.27     47311853.41     46611995.76     47012056.79     48512108.75     474
12443.69     47012950.43     47613067.23     46113245.69     47413304.59     471
13411.19  440.2813432.96  443.53 13433.7     46313480.81  476.7513556.58     488
#Mann= 7 ,-1,0
 3604.66     .07       0 5473.15     .05       0 7288.47     .07       0
 8653.04     .05       010330.63     .11       013245.69    .055       0
13480.81     .03       0
#XS Ineff= 2 ,-1
 8653.0410365.31     46010365.3113245.69     470
Permanent Ineff=
       T       T
Bank Sta=13245.69,13480.81
XS Rating Curve= 0 ,0
Exp/Cntr=0.3,0.1

Type RM Length L Ch R = 1 ,139726  ,191,439,394
BEGIN DESCRIPTION:
Kimley-Horn added cross section based on on-ground survey and proposed grading for Bell South Airfiled property and TNRIS 2009 LiDAR offsite. Channel flowline interpolated from effective model. (KH, 2017)
END DESCRIPTION:
XS GIS Cut Line= 6
  2384062.9520976980662.224515362383986.563208766970176.11340424
2384257.396542136969058.057848692384118.507653246968745.55784871
2384750.452097656967794.168959832384819.896542166965467.78007093
#Sta/Elev= 30
 3522.11     481 3564.86     466  5355.7  469.96 7186.09  471.14 7250.99     472
 7305.96     487 9253.24     487 9305.59     473 9494.15     452 9527.23     461
10185.69     46010276.98     47010390.61     460 10433.3     47810472.51     474
10511.23     48810590.54     47510656.56     48610734.28     46811388.89     470
11436.83     46011647.32     47811740.91     46912623.15     47312665.43     451
12741.01  439.8512783.52     45912845.09     472 13140.6     47713196.49     488
#Mann= 8 ,-1,0
 3522.11     .07       0  5355.7     .05       0 7186.09     .07       0
 9253.24     .06       010276.98     .11       012623.15    .055       0
12845.09      .1       0 13140.6     .03       0
#XS Ineff= 2 ,-1
 9253.2410301.22     46010301.2212623.15     470
Permanent Ineff=
       T       T
Bank Sta=12623.15,12845.09
XS Rating Curve= 0 ,0
Exp/Cntr=0.3,0.1

Type RM Length L Ch R = 1 ,139286  ,234,539,484
BEGIN DESCRIPTION:
Kimley-Horn added cross section based on on-ground survey and proposed grading for Bell South Airfiled property and TNRIS 2009 LiDAR offsite. Channel flowline interpolated from effective model. (KH, 2017)
END DESCRIPTION:
XS GIS Cut Line= 6
  2384236.5632086980571.946737592384167.118764316970217.78007092
2384493.507653246968849.724515362384431.007653216968592.78007092
 2384882.39654216967752.502293142384972.674319866965453.89118205
#Sta/Elev= 30
 3472.17     481 3528.98     466 5293.29  469.67 7125.94  471.31 7195.35     473
 7242.41     487  9239.6     487 9293.69     473 9509.59     452 9533.87     460
10194.37     46110259.26     47010391.36     46010429.32     47210468.64     463
10610.86     47810750.27     46611027.44     46111406.11     48411542.67     461
11848.17     47512132.98     45712357.74     45912408.23     47212528.35     462
12802.95     46612897.52   439.612925.23  442.1913012.37     47613082.44     488
#Mann= 6 ,-1,0
 3472.17     .07       0 5293.29     .05       0 7125.94     .07       0
10259.26      .1       012802.95     .05       013012.37     .03       0
#XS Ineff= 2 ,-1
  9239.610273.05     46010273.0512802.95     470
Permanent Ineff=
       T       T
Bank Sta=12802.95,13012.37
XS Rating Curve= 0 ,0
Exp/Cntr=0.3,0.1

Type RM Length L Ch R = 1 ,138747  ,1,1,1
BEGIN DESCRIPTION:
Kimley-Horn added cross section based on on-ground survey and proposed grading for Bell South Airfiled property and TNRIS 2009 LiDAR offsite. Channel flowline interpolated from effective model. (KH, 2017)
END DESCRIPTION:
XS GIS Cut Line= 6
  2384444.8965426980509.446737622384389.340986556970245.55784872
 2384569.89654216969419.168959832384785.174319896969412.22451538
2384986.563208766968919.168959812385222.67431989 6965384.4467376
#Sta/Elev= 30
 3402.01     479 3459.85     466 5216.54  469.18 7051.96  471.25 7120.64     473
 7168.91     487 9215.89     487  9359.9     45210157.72     46010230.48     468
10376.75     46010538.39     48110607.46     46510764.47     49110835.66     482
10879.12     497 11115.3     48011234.76     45711317.71     473 11381.6     459
11496.05     47312083.68     47412125.13     45612222.04   439.312249.75   441.6
12250.05     453 12264.9     46412298.26     47512567.19     47712627.56     488
#Mann= 8 ,-1,0
 3402.01     .07       0 5216.54     .05       0 7051.96     .07       0
 9215.89     .06       010230.48      .1       012083.68     .05       0
12298.26     .08       012567.19     .03       0
#XS Ineff= 2 ,-1
 9215.8910407.04     46010407.0412083.68     470
Permanent Ineff=
       T       T
Bank Sta=12083.68,12298.26
XS Rating Curve= 0 ,0
Exp/Cntr=0.3,0.1

Type RM Length L Ch R = 1 ,138746  ,76,178,159
BEGIN DESCRIPTION:
Kimley-Horn added cross section based on on-ground survey and proposed grading for Bell South Airfiled property and TNRIS 2009 LiDAR offsite. Channel flowline interpolated from effective model. (KH, 2017)
END DESCRIPTION:
XS GIS Cut Line= 6
  2384445.8965276980509.441324982384390.341571136970245.66314333
  2384570.7072456969420.143328282384785.854822896969413.20308383
2384987.546339826968919.406611272385223.672763866965384.50250176
#Sta/Elev= 30
 3402.01     479 3459.85     466 5216.54  469.18 7051.96  471.25 7120.64     473
 7168.91     487 9215.89     487  9359.9     45210157.72     46010230.48     468
10376.75     46010538.39     48110607.46     46510764.47     49110835.66     482
10879.12     497 11115.3     48011234.76     45711317.71     473 11381.6     459
11496.05     47312083.68     47412125.13     45612222.04   439.312249.75   441.6
12250.05     453 12264.9     46412298.26     47512567.19     47712627.56     488
#Mann= 8 ,-1,0
 3402.01     .07       0 5216.54     .05       0 7051.96     .07       0
 9215.89     .06       010230.48      .1       012083.68     .05       0
12298.26     .08       012567.19     .03       0
#XS Ineff= 2 ,-1
 9215.8910407.04     46010407.0412083.68     470
Permanent Ineff=
       T       T
Bank Sta=12083.68,12298.26
XS Rating Curve= 0 ,0
Exp/Cntr=0.3,0.1

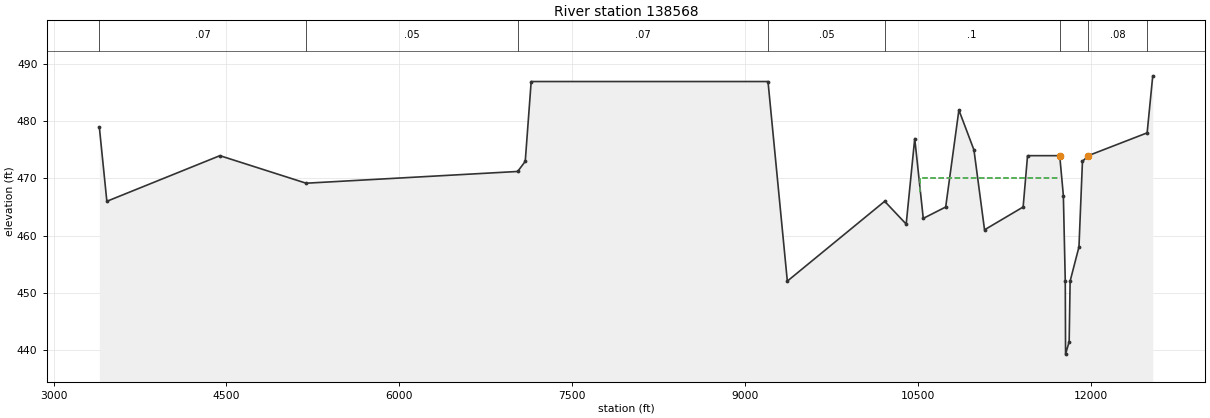
Type RM Length L Ch R = 1 ,138568  ,1,1,1
BEGIN DESCRIPTION:
Kimley-Horn added cross section based on on-ground survey and proposed grading for Bell South Airfiled property and TNRIS 2009 LiDAR offsite. Channel flowline interpolated from effective model. (KH, 2017)
END DESCRIPTION:
XS GIS Cut Line= 6
  2384518.6812646980483.405070952384456.181264316970247.29395983
2384553.403486556969754.238404292384754.79237545 6969726.4606265
2385032.570153216968941.738404272385282.570153246965386.18284871
#Sta/Elev= 30
  3396.3     479 3461.59     466 4442.77     474 5191.23  469.17  7027.3  471.23
 7093.07     473 7144.61     487 9200.18     487 9367.88     45210212.97     466
10399.55     462 10473.7     47710547.74     46310742.46     46510857.05     482
10987.75     47511079.64     46111414.67     46511452.93     47411732.11     474
11763.82     46711780.34     45211782.94   439.211814.17   441.411822.45     452
 11899.2     45811929.47     47311979.87     47412490.97     47812539.61     488
#Mann= 8 ,-1,0
  3396.3     .07       0 5191.23     .05       0  7027.3     .07       0
 9200.18     .05       010212.97      .1       011732.11     .05       0
11979.87     .08       012490.97     .03       0
#XS Ineff= 2 ,-1
 9200.1810523.06     46010523.0611732.11     470
Permanent Ineff=
       T       T
Bank Sta=11732.11,11979.87
XS Rating Curve= 0 ,0
Exp/Cntr=0.3,0.1