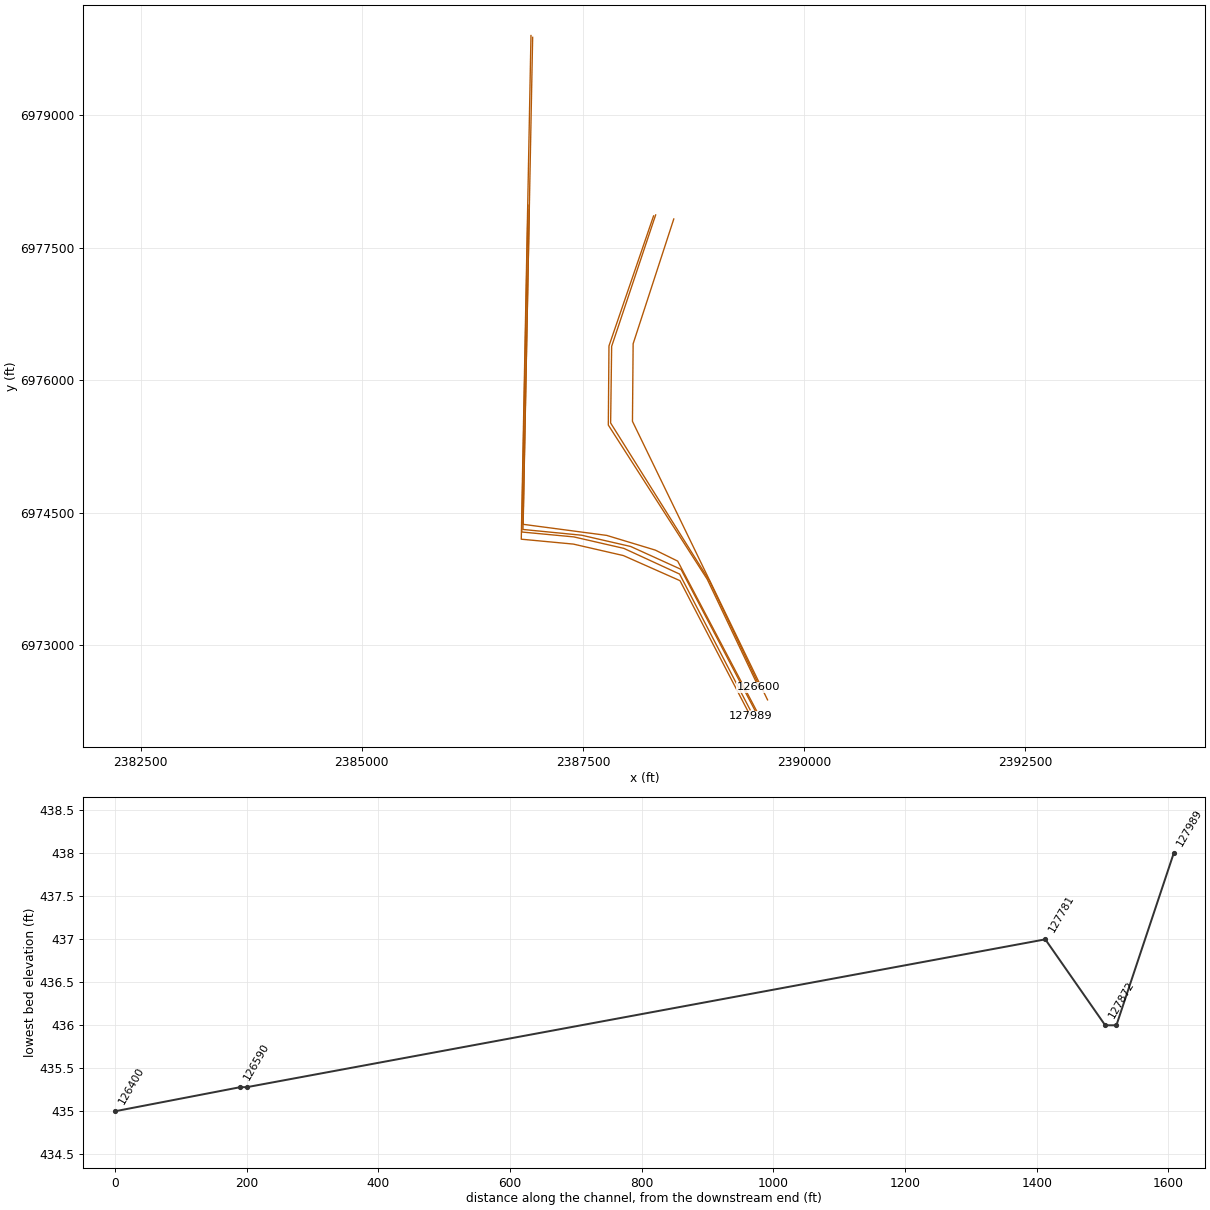
HEC-RAS study CDC_Consolidated_Model.prj: Upper Trinity CDC Consolidated Model

--- CDC_Consolidated_Model.g12 (geometry) --- (continued)

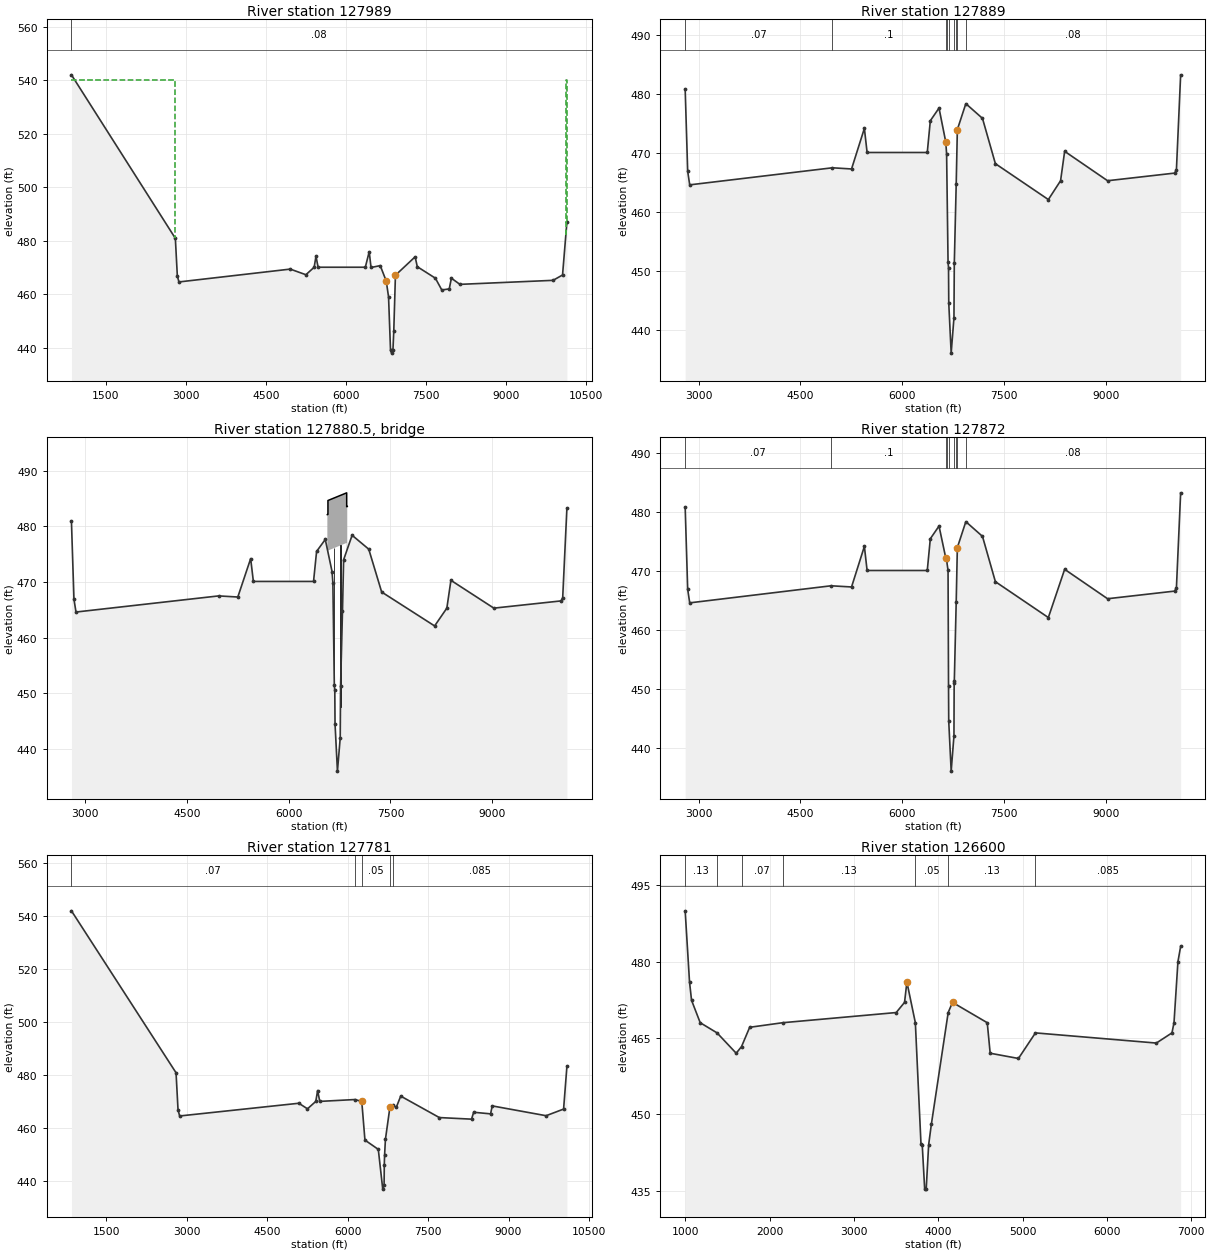
Type RM Length L Ch R = 1 ,127989  ,1,87,87
BEGIN DESCRIPTION:
This cross section corresponds to cross section 127989 of the non-georeferenced CDC model which was the source of this model.
END DESCRIPTION:
XS GIS Cut Line= 6
2386912.758688216979897.78156203 2386803.0685215  6974202.068684
 2387392.1844715  6974146.701664 2387957.8024315  6974016.957834
 2388597.7926215  6973733.117844 2389395.2365872  6972200.747429
#Sta/Elev= 30
     852     542    2802   480.9    2839   466.9    2869   464.6    4958   469.4
    5252   467.3    5407   470.1    5441   474.2    5481   470.1    6367   470.1
    6440   475.9    6474     470    6647   470.7    6760   464.9    6803     459
    6840     439    6860     438    6885     439    6901   446.3    6932   467.1
    7302     474    7342   470.3    7682     466    7802   461.6    7942     462
    7982     466    8142   463.7    9890   465.2   10068   467.2   10150     487
#Mann= 1 ,-1,0
     852     .08       0
#XS Ineff= 2 , 0
            2802     540   10130             540
Permanent Ineff=
       F       F
Bank Sta=6760,6932
XS Rating Curve= 0 ,0
Exp/Cntr=0.3,0.1

Type RM Length L Ch R = 1 ,127889  ,3,17,17
BEGIN DESCRIPTION:
This cross section corresponds to cross section 127889 of the non-georeferenced CDC model which was the source of this model.
Upstream bounding cross-section of Trammel-Davis Road.
END DESCRIPTION:
XS GIS Cut Line= 6
2386878.909217036977979.83039879 2386808.3232034 6974283.3612296
 2387397.4391512 6974227.9942144 2387963.0571144 6974098.2503794
      2388593.48      6973807.732389391.049825476972272.62064861
#Sta/Elev= 30
    2802   480.9    2839   466.9    2869   464.6    4970   467.5    5252   467.3
    5441   474.2    5481   470.1    6367   470.1    6412   475.5    6540  477.65
    6640  471.85 6651.81  469.83    6673   451.5    6680   450.5  6683.5   444.5
    6719     436    6760     442 6765.07  451.24 6793.31  464.82    6810     474
    6935   478.4    7180   475.9    7370   468.2    8150   462.1    8330   465.3
    8390   470.3    9022   465.3   10011   466.6   10036   467.2   10098   483.3
#Mann= 9 ,-1,0
    2802     .07       0    4970      .1       0    6640    .055       0
 6651.81    .045       0    6680    .055       0 6765.07    .045       0
 6793.31    .055       0    6810     .13       0    6935     .08       0
#XS Ineff= 2 , 0
            6640   470.8    6810           462.1
Permanent Ineff=
       F       F
Bank Sta=6640,6810
XS Rating Curve= 0 ,0
Exp/Cntr=0.3,0.1

Type RM Length L Ch R = 3 ,127880.5,,,
BEGIN DESCRIPTION:
Trammel-Davis Road
END DESCRIPTION:
Node Name=Trammel-Davis Ro
Bridge Culvert--1,0,-1,-1, 0
Deck Dist Width WeirC Skew NumUp NumDn MinLoCord MaxHiCord MaxSubmerge Is_Ogee
0.5,16,2.6,0, 6, 6, , , 0.95, 0, ,,,
 6570.25    6579    6579    6855    6855 6863.75
  482.11  482.15  484.65  486.03  483.53  483.57
                  475.65  477.03
 6570.25    6579    6579    6855    6855 6863.75
  482.11  482.15  484.65  486.03  483.53  483.57
                  475.65  477.03
Pier Skew, UpSta & Num, DnSta & Num=  ,6671, 2 ,6671, 2 , 0 , 0 , 0 ,,
     3.5     3.5
     440   478.7
     3.5     3.5
     440   478.7
Pier Skew, UpSta & Num, DnSta & Num=  ,6763, 2 ,6763, 2 , 0 , 0 , 0 ,,
     3.5     3.5
     440     480
     3.5     3.5
     440     480
BR Coef= 1 , 0 , 0 ,1.05, 0 ,,,0.8,-1,0.5,1,
WSPro=,,,, 1 ,,,, 0 ,,,, 0 ,,,,-1 ,-1 ,-1 , 0 , 0 , 0 , 0 , 0
BC Design=,, 0 ,, 0 ,,,,,,
BC HTab HWMax=483.3
BC Use User HTab Curves=0
BC User HTab FreeFlow(D)= 0

Type RM Length L Ch R = 1 ,127872  ,1,91,91
BEGIN DESCRIPTION:
This cross section corresponds to cross section 127872 of the non-georeferenced CDC model which was the source of this model.
Downstream bounding cross-section of Trammel-Davis Road.
Modified bridge as part of CDC FW052322-1 Trinity Trails East Phase 2.
END DESCRIPTION:
XS GIS Cut Line= 6
      2386893.55      6977927.84      2386822.04      6974312.16
 2387484.9901572 6974247.1218008 2388040.8771687 6974119.4501402
      2388609.57      6973861.05 2389452.4008471 6972253.4061766
#Sta/Elev= 30
    2802   480.9    2839   466.9    2869   464.6    4950   467.5    5252   467.3
    5441   474.2    5481   470.1    6367   470.1    6412   475.5    6540  477.65
    6640   472.2 6651.81  471.85    6673   470.1    6680   450.5    6683   444.5
    6719     436    6760     442    6763     451 6765.07  451.24 6793.31  464.82
    6810     474    6935   478.4    7180   475.9    7370   468.2    8150   462.1
    8390   470.3    9022   465.3   10011   466.6   10036   467.2   10098   483.3
#Mann= 9 ,-1,0
    2802     .07       0    4950      .1       0    6640     .05       0
 6651.81    .045       0    6680     .05       0 6765.07    .045       0
 6793.31     .05       0    6810     .13       0    6935     .08       0
#XS Ineff= 2 , 0
            6640   470.8    6810           462.1
Permanent Ineff=
       F       F
Bank Sta=6640,6810
XS Rating Curve= 0 ,0
Exp/Cntr=0.3,0.1

Type RM Length L Ch R = 1 ,127781  ,1017,1213,31
BEGIN DESCRIPTION:
This cross section corresponds to cross section 127781 of the non-georeferenced CDC model which was the source of this model.
END DESCRIPTION:
XS GIS Cut Line= 6
2386931.618928986979877.45992418  2386824.310376 6974370.2773944
 2387769.0867018 6974245.0112407 2388318.2667058 6974078.9124916
 2388571.9568152 6973954.1630691 2389464.9938425 6972259.0895225
#Sta/Elev= 30
     852     542    2802   480.9    2839   466.9    2869   464.6    5091   469.4
    5252   467.3    5407   470.1    5441   474.2    5481   470.1    6135   470.8
    6264   470.1    6323   455.5    6572     452    6655     437    6680   438.5
    6684   446.1    6689   449.7    6705   455.8    6790   468.1    6838   468.6
    6908   467.9    6990   472.1    7710     464    8310   463.4    8350     466
    8665   465.4    8696   468.4    9700   464.7   10026   467.2   10088   483.3
#Mann= 5 ,-1,0
     852     .07       0    6135     .13       0    6264     .05       0
    6790     .13       0    6838    .085       0
#XS Ineff= 2 , 0
            6264   470.1    6790           468.1
Permanent Ineff=
       F       F
Bank Sta=6264,6790
XS Rating Curve= 0 ,0
Exp/Cntr=0.3,0.1

Type RM Length L Ch R = 1 ,126600  ,10,10,10
BEGIN DESCRIPTION:
126600
Effective flow limit set in ROB at Village Creek STP Drying Beds Levee.
END DESCRIPTION:
XS GIS Cut Line= 6
  2388299.036303 6977858.0265513  2388294.313669 6977844.2533861
 2387794.7766111 6976387.3957355 2387787.2940145 6975492.7790864
 2388906.0437455 6973749.0292931      2389487.45      6972528.08
#Sta/Elev= 30
    1000     490 1051.69     476 1075.57  472.41 1178.35     468 1378.09     466
 1604.92     462 1667.97   463.3 1764.61   467.1 2155.82     468 3501.74     470
  3600.6     472 3628.33     476 3728.64     468 3795.53  444.11 3810.14     444
  3839.2  435.28  3857.2  435.28 3886.29     444 3918.12     448 4117.83     470
 4169.13     472 4580.92     468 4615.57     462 4950.74  460.97 5152.15     466
 6585.31     464 6770.58     466 6794.69     468  6841.3     480 6873.42     483
#Mann= 7 ,-1,0
    1000     .13       0 1378.09     .04       0 1667.97     .07       0
 2155.82     .13       0 3728.64     .05       0 4117.83     .13       0
 5152.15    .085       0
Bank Sta=3628.33,4169.13
XS Rating Curve= 0 ,0
Exp/Cntr=0.3,0.1

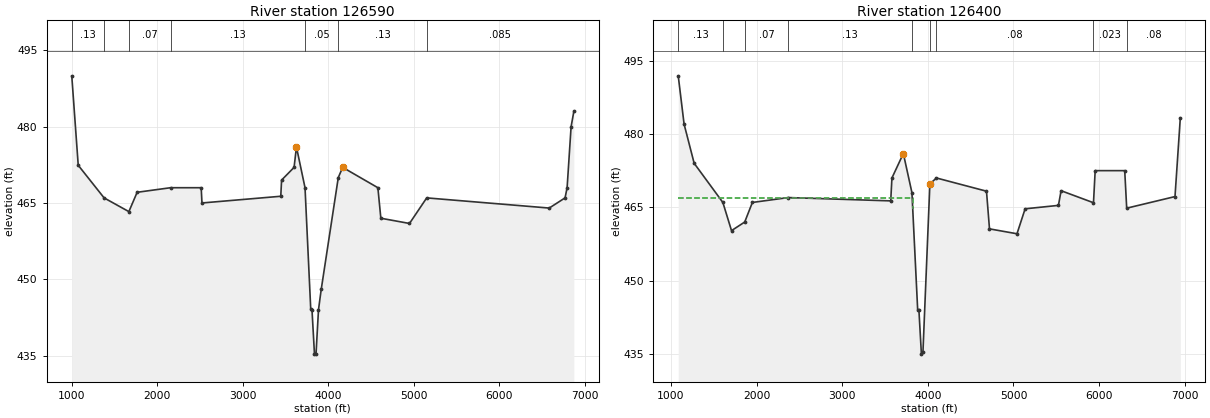
Type RM Length L Ch R = 1 ,126590  ,190,190,190
BEGIN DESCRIPTION:
126590
Effective flow limit set in ROB at Village Creek STP Drying Beds Levee.
END DESCRIPTION:
XS GIS Cut Line= 6
  2388322.501575 6977868.8919064  2388312.181088 6977838.0683591
  2387824.984884 6976382.9902325 2387813.5528202 6975516.0424913
 2388931.2175797 6973731.4945512      2389503.27      6972526.64
#Sta/Elev= 30
    1000     490 1075.57  472.41 1378.09     466 1667.97   463.3 1764.61   467.1
 2155.82     468    2514     468    2523     465    3445  466.32 3454.54   469.5
  3600.6     472 3628.33     476 3728.64     468 3795.53  444.11 3810.14     444
  3839.2  435.28  3857.2  435.28 3886.29     444 3918.12     448 4117.83     470
 4169.13     472 4580.92     468 4615.57     462 4950.74  460.97 5152.15     466
 6585.31     464 6770.58     466 6794.69     468  6841.3     480 6873.42     483
#Mann= 7 ,-1,0
    1000     .13       0 1378.09     .04       0 1667.97     .07       0
 2155.82     .13       0 3728.64     .05       0 4117.83     .13       0
 5152.15    .085       0
Bank Sta=3628.33,4169.13
XS Rating Curve= 0 ,0
Exp/Cntr=0.3,0.1

Type RM Length L Ch R = 1 ,126400  ,183,183,183
BEGIN DESCRIPTION:
126400
Contains proposed pad site by BHB July 2011.
Effective flow limit set in ROB at Village Creek STP Drying Beds Levee.
END DESCRIPTION:
XS GIS Cut Line= 4
     2388527.595     6977823.304     2388068.022     6976412.168
     2388060.395     6975534.975 2389588.1119266 6972385.0073918
#Sta/Elev= 30
  1085.8  491.88 1154.19     482 1271.87     474 1606.85     466 1707.85  460.24
 1862.07     462  1951.6     466  2370.8     467  3566.8  466.32 3580.84     471
 3714.13     476 3814.44     468 3881.33  444.11 3895.94     444    3925     435
    3943   435.4    4024   469.8    4101     471    4685   468.3    4720   460.6
    5041   459.6    5136   464.7    5525   465.4    5556   468.4 5934.31  465.94
 5953.99   472.5 6298.99   472.5    6322  464.83    6886   467.2    6948   483.3
#Mann= 9 ,-1,0
  1085.8     .13       0 1606.85     .04       0 1862.07     .07       0
  2370.8     .13       0 3814.44     .05       0    4024     .13       0
    4101     .08       0 5934.31    .023       0    6322     .08       0
#XS Ineff= 2 , 0
            3824   466.9    4024           469.8
Permanent Ineff=
       F       F
Bank Sta=3714.13,4024
XS Rating Curve= 0 ,0
Exp/Cntr=0.3,0.1