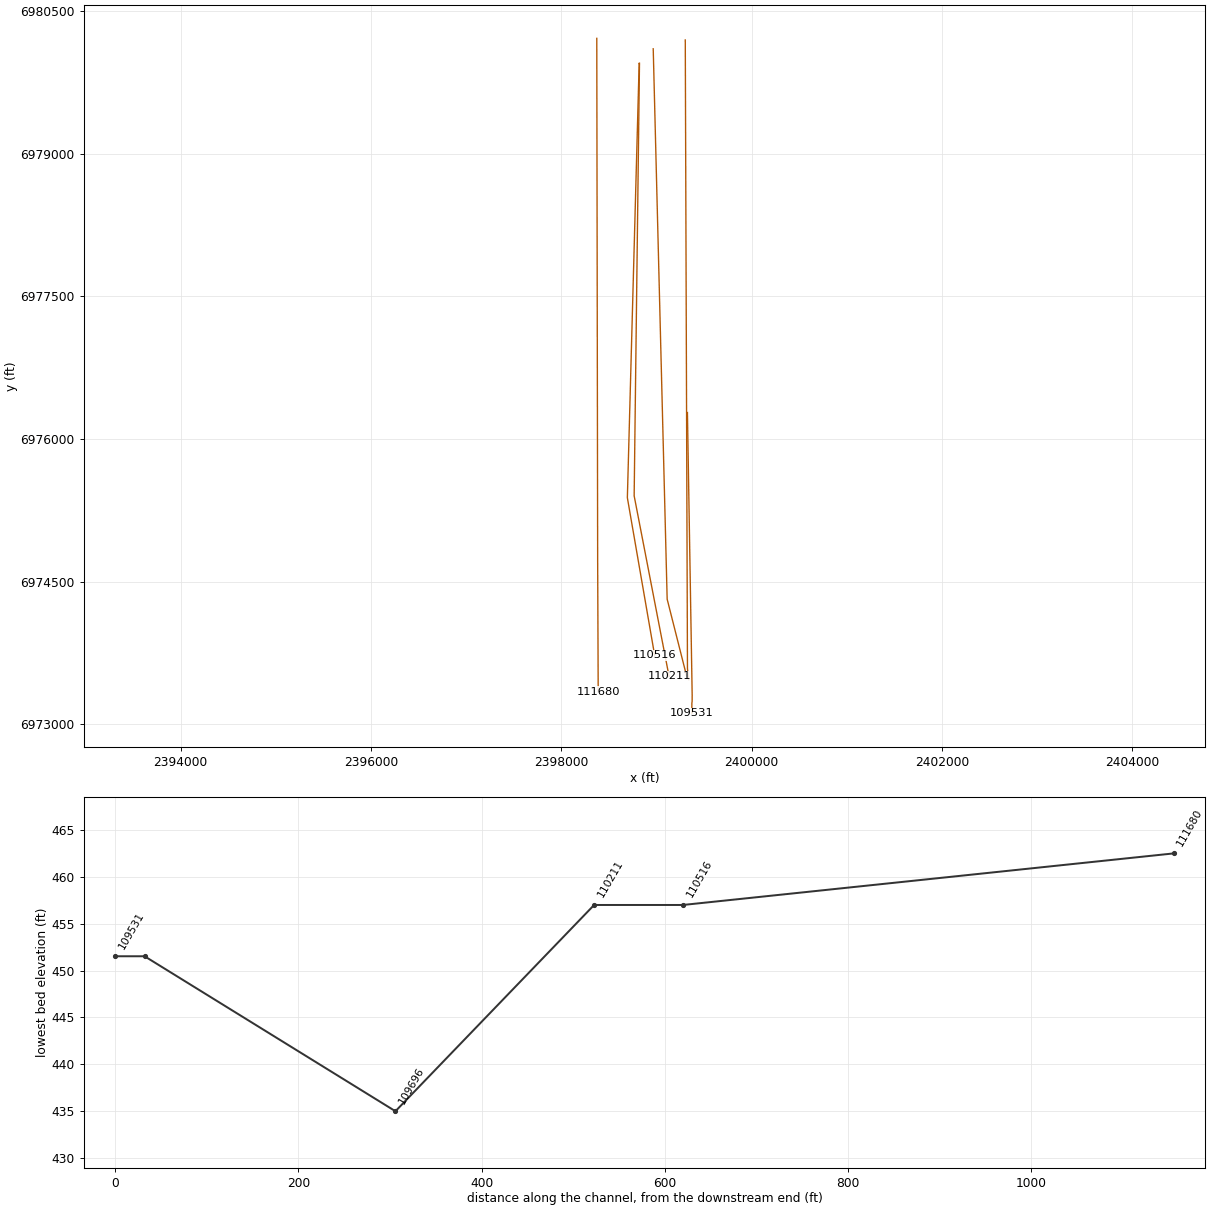
HEC-RAS study CDC_Consolidated_Model.prj: Upper Trinity CDC Consolidated Model

--- CDC_Consolidated_Model.g12 (geometry) --- (continued)

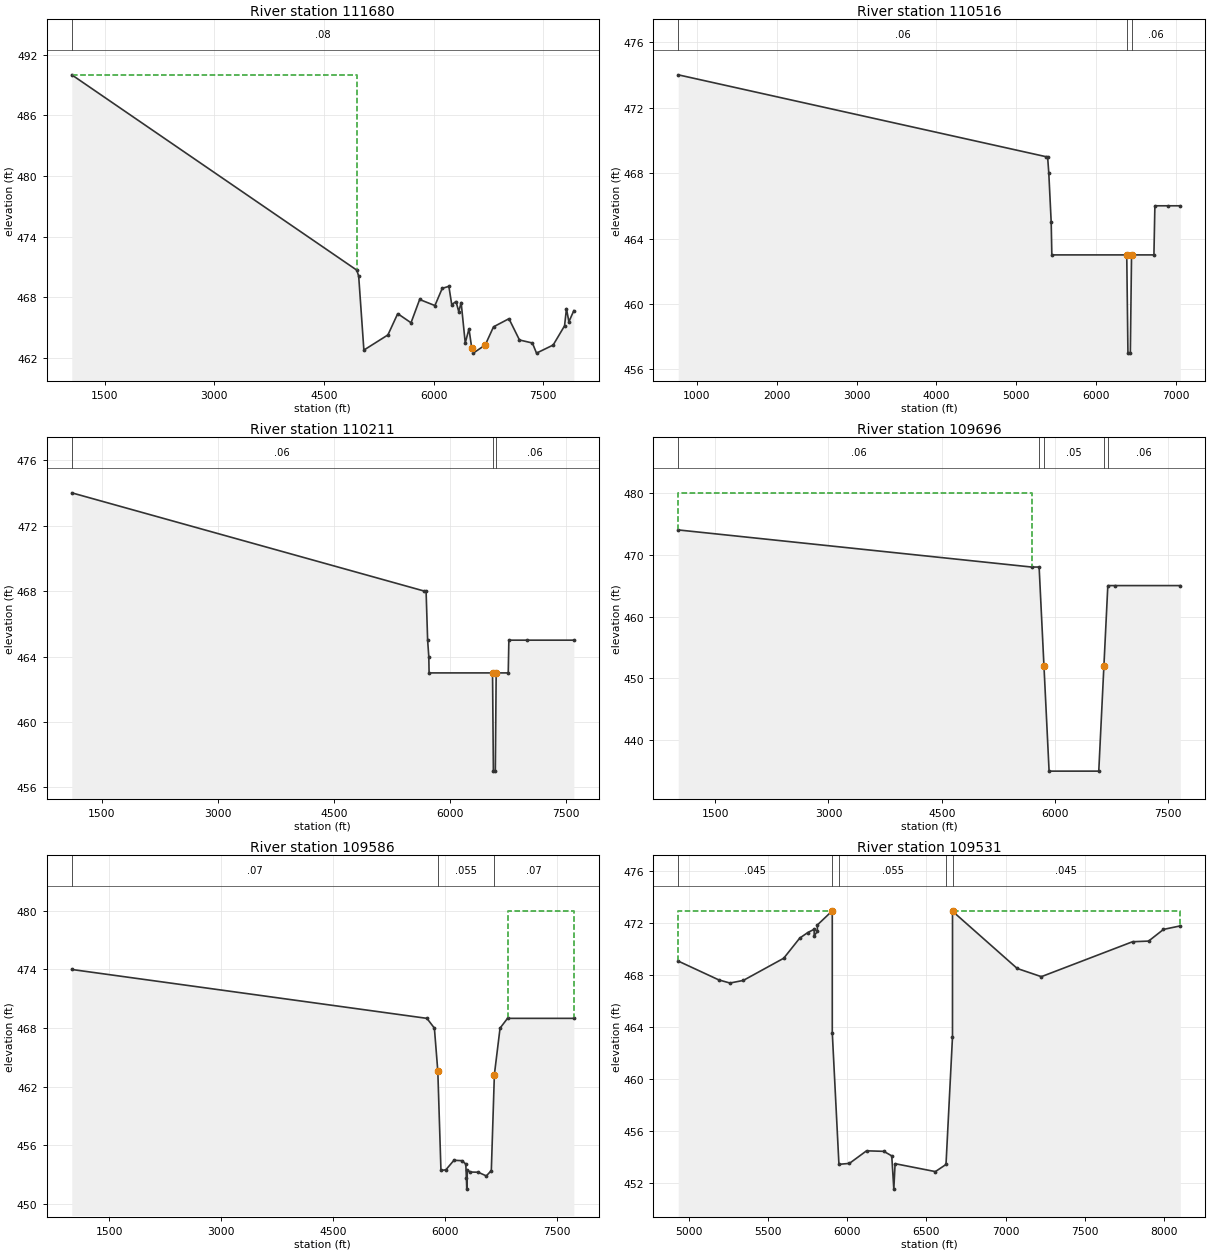
Type RM Length L Ch R = 1 ,111680  ,417,536,775
BEGIN DESCRIPTION:
This cross section corresponds to cross section 111680 of the non-georeferenced CDC model which was the source of this model.
Cross Section Truncated due to Ineffective Flow Areas
END DESCRIPTION:
XS GIS Cut Line= 5
2398373.658956566980213.55459825      2398380.15      6976313.56
      2398382.81      6974715.36      2398386.71      6973771.74
2398388.479685916973343.55768674
#Sta/Elev= 30
    1050     490    4950   470.7    4976   470.1    5047   462.8    5376   464.3
    5510   466.4    5692   465.5    5810   467.8    6019   467.2    6119   468.9
    6210   469.1    6249   467.3    6308   467.6    6345   466.6    6378   467.5
    6434   463.5    6485   464.9    6523     463    6543   462.5    6707   463.3
    6821   465.1    7032   465.9    7176   463.8    7353   463.5    7409   462.5
    7637   463.3    7793   465.2    7819   466.9    7852   465.6    7920   466.7
#Mann= 1 ,-1,0
    1050     .08       0
#XS Ineff= 2 , 0
            4950     490
Permanent Ineff=
       F       F
#Block Obstruct= 2 , 0
            5255     480    7155             480
Bank Sta=6523,6707
XS Rating Curve= 0 ,0
Exp/Cntr=0.3,0.1

Type RM Length L Ch R = 1 ,110516  ,87,97,97
BEGIN DESCRIPTION:
This cross section corresponds to cross section 110516 of the non-georeferenced CDC model which was the source of this model.
Old roadway embankment lowered from 466 to 463.  Section just upstream of old Collins St. alignment.  Section based on 2006 topography.
END DESCRIPTION:
XS GIS Cut Line= 6
     2398818.978     6979950.345     2398818.957     6979950.612
  2398694.954069 6975382.0308141      2398794.94        6974804.
 2398955.7359303  6973874.419186 2398981.3027794 6973726.6141244
#Sta/Elev= 14
     770     474    5370     469    5390     469    5405     468    5435     465
    5443     463    6380     463    6395     457    6425     457    6440     463
    6720     463    6732     466    6900     466    7050     466
#Mann= 3 ,0,0
     770     .06       0    6380    .055       0    6440     .06       0
#Block Obstruct= 2 , 0
            5460     480    6800             480
Bank Sta=6380,6440
XS Rating Curve= 0 ,0
Exp/Cntr=0.5,0.3

Type RM Length L Ch R = 1 ,110211  ,276,217,197
BEGIN DESCRIPTION:
This cross section corresponds to cross section 110211of the non-georeferenced CDC model which was the source of this model.
Old roadway embankment lowered to 463.  END RELIEF CHANNEL CUT  Section along old Collins St. alignment.  Section based on 2006 topography.
END DESCRIPTION:
XS GIS Cut Line= 6
     2398822.329     6979951.664  2398766.326591 6975401.9177591
      2398835.47        6975044.       2398950.4      6974449.07
 2399019.5434086 6974091.15224092399133.348719726973502.04414287
#Sta/Elev= 14
    1110     474    5665     468    5690     468    5710     465    5725     464
    5729     463    6549     463    6560     457    6585     457    6596     463
    6752     463    6760     465    7000     465    7600     465
#Mann= 3 ,0,0
    1110     .06       0    6549    .055       0    6596     .06       0
#Block Obstruct= 2 , 0
            5760     480    6925             480
Bank Sta=6549,6596
XS Rating Curve= 0 ,0
Exp/Cntr=0.5,0.3

Type RM Length L Ch R = 1 ,109696  ,262,274,251
BEGIN DESCRIPTION:
This cross section corresponds to cross section 109696 of the non-georeferenced CDC model which was the source of this model.
Proposed fill & lake.
END DESCRIPTION:
XS GIS Cut Line= 6
2398966.652370336980103.23848301      2399088.99      6975270.48
      2399109.27      6974469.35 2399113.1749059 6974315.0927396
     2399302.364     6973566.7692399323.96551022 6973481.3257931
#Sta/Elev= 10
    1010     474    5690     468    5790     468    5854     452    5922     435
    6580     435    6648     452    6700     465    6800     465    7660     465
#Mann= 5 ,-1,0
    1010     .06       0    5790     .08       0    5854     .05       0
    6648     .08       0    6700     .06       0
#XS Ineff= 2 ,-1
    1010    5690     480    5700    6800     451
Permanent Ineff=
       F       T
#Block Obstruct= 2 , 0
                            6790             470
Bank Sta=5854,6648
XS Rating Curve= 0 ,0
Exp/Cntr=0.5,0.3

Type RM Length L Ch R = 1 ,109586  ,32,32,32
BEGIN DESCRIPTION:
This cross section corresponds to cross section 109586 of the non-georeferenced CDC model which was the source of this model.
35 FT U/S OF F.M. 157 ROADWAY EMBANKMENT
END DESCRIPTION:
XS GIS Cut Line= 6
2399303.552761076980196.19362542 2399307.3414275 6979103.3941244
     2399323.557     6974426.189  2399323.705268 6974383.4224906
 2399326.4757117 6973584.3140952      2399340.28      6973468.05
#Sta/Elev= 20
    1000     474    5760     469    5860     468    5906  463.58    5948  453.44
    6014  453.51    6122  454.48    6231  454.44    6281  454.09    6289  452.66
    6294  451.53    6302  453.49    6339  453.28    6447  453.26    6556  452.88
    6623  453.43    6664  463.25    6740     468    6840     469    7729     469
#Mann= 3 ,-1,0
    1000     .07       0    5906    .055       0    6664     .07       0
#XS Ineff= 2 , 0
                            6840             480
Permanent Ineff=
       F       F
#Block Obstruct= 2 , 0
            5140     480
Bank Sta=5906,6664
XS Rating Curve= 0 ,0
Exp/Cntr=0.5,0.3

Type RM Length L Ch R = 1 ,109531  ,156,156,156
BEGIN DESCRIPTION:
This cross section corresponds to cross section 109531 of the non-georeferenced CDC model which was the source of this model.
U/S FACE OF F.M. 157 BRIDGE Surveyed 2006
END DESCRIPTION:
XS GIS Cut Line= 6
2399326.140747616976278.32917722     2399354.518     6974584.992
     2399375.965     6973305.249      2399375.55        6973241.
      2399372.83       6973220.7      2399372.47      6973113.93
#Sta/Elev= 30
    4935  469.09    5191  467.64    5261   467.4    5345   467.6    5600  469.31
    5701  470.86    5752  471.29    5792  471.54    5792  471.04    5812  471.37
    5812  471.87    5906  472.96  5906.1  463.58    5948  453.44    6014  453.51
    6122  454.48    6231  454.44    6281  454.09    6294  451.53    6302  453.49
    6556  452.88    6623  453.43 6663.87  463.25    6664  472.93    7072  468.52
    7224  467.89    7799  470.58    7900  470.63    7994  471.53    8100   471.8
#Mann= 5 ,-1,0
    4935    .045       0    5906     .02       0    5948    .055       0
    6623     .02       0    6664    .045       0
#XS Ineff= 2 , 0
            5906  472.96    6664          472.96
Permanent Ineff=
       T       T
Bank Sta=5906,6664
XS Rating Curve= 0 ,0
Exp/Cntr=0.5,0.3

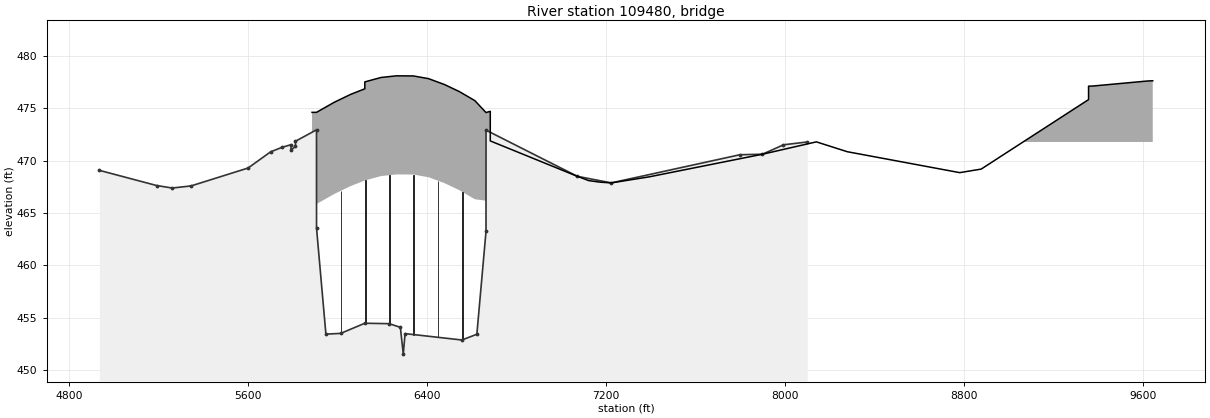
Type RM Length L Ch R = 3 ,109480  ,,,
BEGIN DESCRIPTION:
FM 157
NEW X-SECTION BASED ON 1991 SURVEY DATA AND COE BRIDGE SECTIONS
D/S FACE OF WIDENED AND REALIGNED F.M. 157 BRIDGE
END DESCRIPTION:
Node Name=FM 157
Bridge Culvert--1,0,-1,-1, 0
Deck Dist Width WeirC Skew NumUp NumDn MinLoCord MaxHiCord MaxSubmerge Is_Ogee
1,154,2.6,0, 31, 31, , , 0.95, 0, 0,0,,
    5886    5906    5986    6059    6122    6122    6194    6263    6339    6407
    6478    6545    6614 6663.87    6683    6683    7072    7123    7174    7224
    7394    7900    8141    8279    8782    8878    9358    9358    9379    9624
    9645
  474.63  474.63   475.6  476.35  476.88  477.54  477.96  478.12  478.11  477.85
  477.29  476.61  475.75  474.61  474.73   471.9  468.52  468.11  467.96  467.89
  468.47  470.63  471.81  470.87  468.87  469.21  475.85  477.13  477.15  477.63
  477.65
     465  465.87  466.84  467.59  468.12  468.12  468.54   468.7  468.69  468.43
  467.87  467.19  466.33  466.19  466.19     465     465     465     465     465
     465     465     465     465     465     465     465     465  469.15  469.63
     465
    5886    5906    5986    6059    6122    6122    6194    6263    6339    6407
    6478    6545    6614 6663.87    6683    6683    7072    7123    7174    7224
    7394    7900    8141    8279    8782    8878    9358    9358    9379    9624
    9645
  474.63  474.63   475.6  476.35  476.88  477.54  477.96  478.12  478.11  477.85
  477.29  476.61  475.75  474.61  474.73   471.9  468.52  468.11  467.96  467.89
  468.47  470.63  471.81  470.87  468.87  469.21  475.85  477.13  477.15  477.63
  477.65
     465  465.87  466.84  467.59  468.12  468.12  468.54   468.7  468.69  468.43
  467.87  467.19  466.33  466.19  466.19     465     465     465     465     465
     465     465     465     465     465     465     465     465  469.15  469.63
     465
Pier Skew, UpSta & Num, DnSta & Num=  ,6015.91, 2 ,6015.91, 2 , 0 , 0 , 0 ,,
    3.28    3.28
  419.95     468
    3.28    3.28
  419.95     468
Pier Skew, UpSta & Num, DnSta & Num=  ,6124.18, 2 ,6124.18, 2 , 0 , 0 , 0 ,,
    3.28    3.28
  419.95   469.8
    3.28    3.28
  419.95   469.8
Pier Skew, UpSta & Num, DnSta & Num=  ,6232.44, 2 ,6232.44, 2 , 0 , 0 , 0 ,,
    3.28    3.28
  413.39   469.8
    3.28    3.28
  413.39   469.8
Pier Skew, UpSta & Num, DnSta & Num=  ,6340.71, 2 ,6340.71, 2 , 0 , 0 , 0 ,,
    3.28    3.28
  413.39   469.8
    3.28    3.28
  413.39   469.8
Pier Skew, UpSta & Num, DnSta & Num=  ,6448.98, 2 ,6448.98, 2 , 0 , 0 , 0 ,,
    3.28    3.28
  413.39   469.8
    3.28    3.28
  413.39   469.8
Pier Skew, UpSta & Num, DnSta & Num=  ,6557.25, 2 ,6557.25, 2 , 0 , 0 , 0 ,,
    3.28    3.28
  413.39   469.8
    3.28    3.28
  413.39   469.8
Pier Skew, UpSta & Num, DnSta & Num=  ,9449, 2 ,9449, 2 , 0 , 0 , 0 ,,
       3       3
     445   469.8
       3       3
     445   469.8
Pier Skew, UpSta & Num, DnSta & Num=  ,9555, 2 ,9555, 2 , 0 , 0 , 0 ,,
       3       3
     450   469.8
       3       3
     450   469.8
BR Coef= 0 , 0 , 1 ,1.05, 0 ,,,0.8,0,1.2,0,468.7
WSPro=,,,, 1 ,,,, 0 ,,,, 0 ,,,,-1 ,-1 ,-1 , 0 , 0 , 0 , 0 , 0
BC Design=,, 0 ,, 0 ,,,,,,
BC Use User HTab Curves=0
BC User HTab FreeFlow(D)= 0