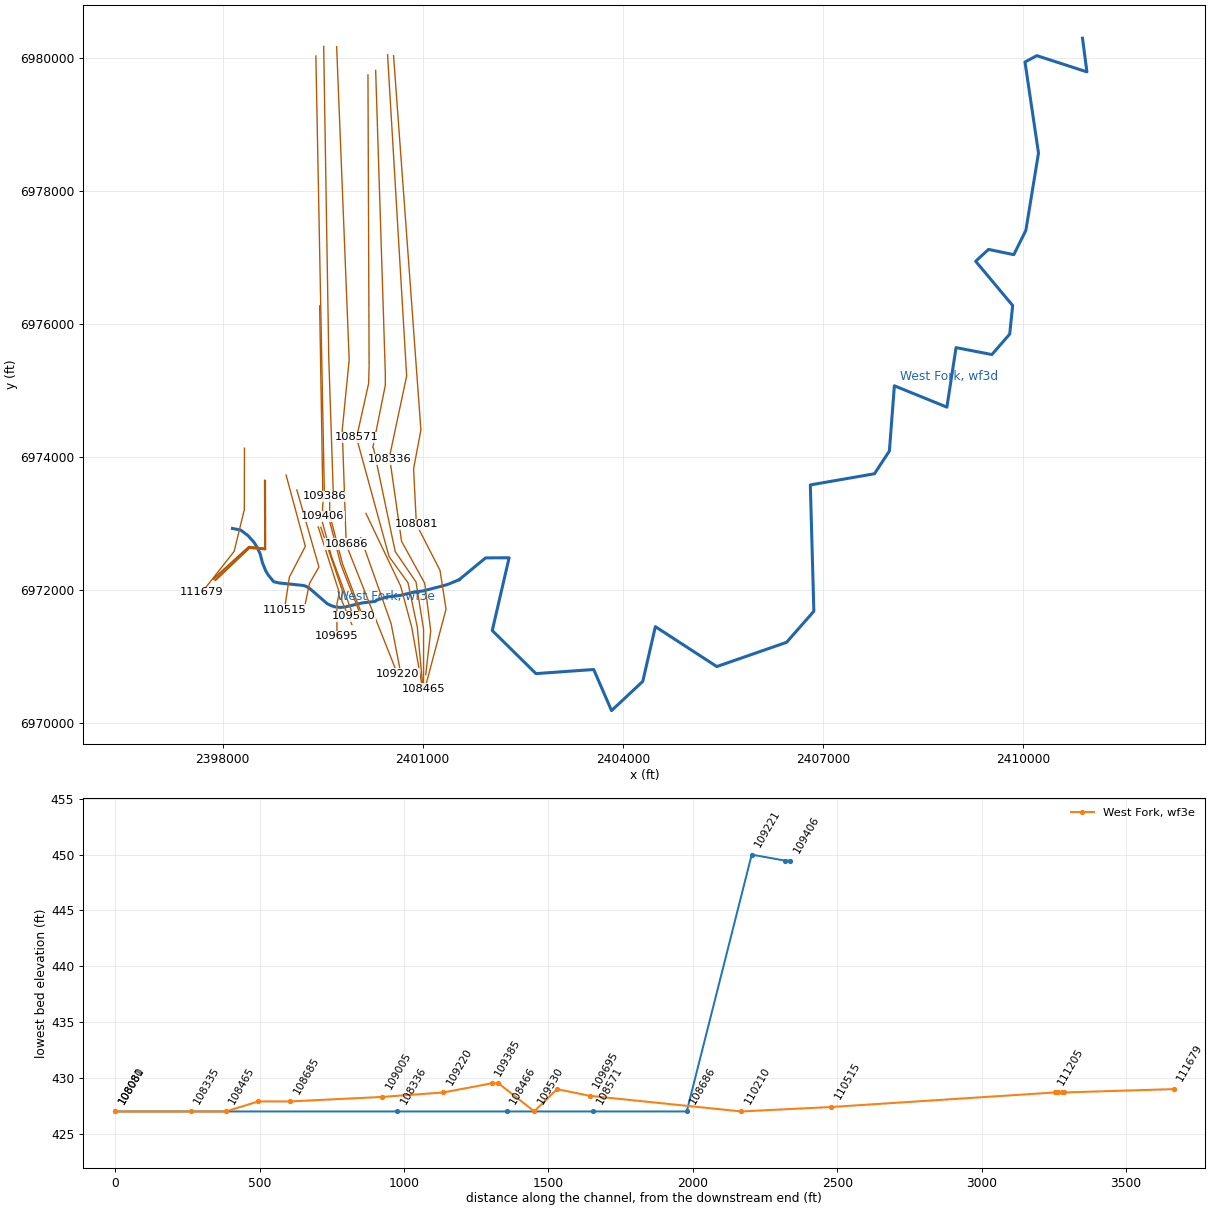
HEC-RAS study CDC_Consolidated_Model.prj: Upper Trinity CDC Consolidated Model

--- CDC_Consolidated_Model.g12 (geometry) --- (continued)

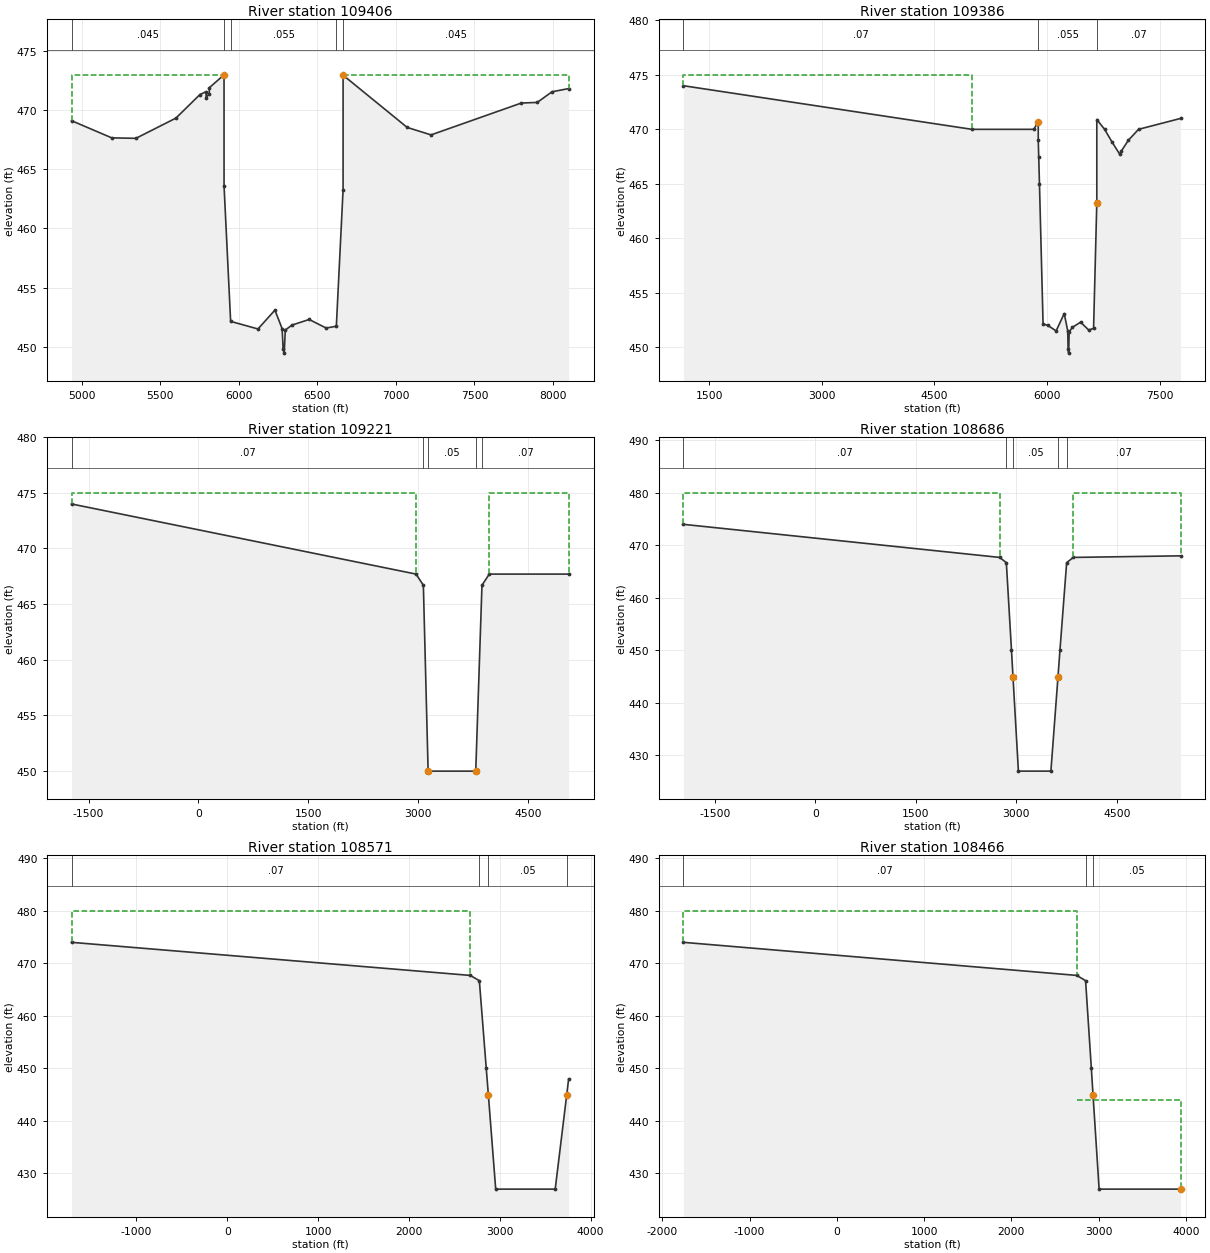
Type RM Length L Ch R = 1 ,109406  ,20,20,20
BEGIN DESCRIPTION:
This cross section corresponds to cross section 109406 of the non-georeferenced CDC model which was the source of this model.
D/S FACE OF F.M. 157 BRIDGE Surveyed 2006
END DESCRIPTION:
XS GIS Cut Line= 6
2399455.860605496976278.27811241     2399477.207     6974997.382
     2399480.587     6974794.562     2399505.265     6973313.691
      2399499.58      6973243.43      2399501.24      6973113.93
#Sta/Elev= 30
    4935  469.09    5191  467.64    5345   467.6    5600  469.31    5752  471.29
    5792  471.54    5792  471.04    5812  471.37    5812  471.87    5906  472.96
  5906.1  463.58    5948  452.15    6122  451.51    6230   453.1    6276  451.53
    6282  449.86    6289  449.47    6296  451.42    6339  451.84    6448  452.31
    6556  451.59    6621  451.74 6663.87  463.25    6664  472.93    7072  468.52
    7224  467.89    7799  470.58    7900  470.63    7994  471.53    8100   471.8
#Mann= 5 ,-1,0
    4935    .045       0    5906     .02       0    5948    .055       0
    6621     .02       0    6664    .045       0
#XS Ineff= 2 , 0
            5906  472.96    6664          472.96
Permanent Ineff=
       T       T
Bank Sta=5906,6664
XS Rating Curve= 0 ,0
Exp/Cntr=0.5,0.3

Type RM Length L Ch R = 1 ,109386  ,114,114,114
BEGIN DESCRIPTION:
This cross section corresponds to cross section 109386 of the non-georeferenced CDC model which was the source of this model.
20 FT D/S OF F.M. 157 ROADWAY EMBANKMENT  Surveyed 2006
END DESCRIPTION:
XS GIS Cut Line= 6
2399399.121551346980037.14590349     2399471.774      6976283.13
     2399494.984     6975083.875     2399502.357     6974702.906
 2399525.0942352 6973528.0270434       2399522.7      6973414.39
#Sta/Elev= 28
    1156     474    5000     470    5824     470    5884   470.7    5884     469
    5890   467.5    5900     465    5948  452.15    6012  452.01    6122  451.51
    6230   453.1    6276  451.53    6282  449.86    6289  449.47    6296  451.42
    6339  451.84    6448  452.31    6556  451.59    6621  451.74    6664  463.25
    6664   470.9    6768     470    6870   468.8    6971   467.7    6990     468
    7085     469    7220     470    7780     471
#Mann= 3 ,0,0
    1156     .07       0    5884    .055       0    6664     .07       0
#XS Ineff= 2 , 0
            5000     475    7780             475
Permanent Ineff=
       F       F
#Block Obstruct= 2 , 0
                            6664
Bank Sta=5884,6664
XS Rating Curve= 0 ,0
Exp/Cntr=0.5,0.3

Type RM Length L Ch R = 1 ,109221  ,275,225,183
BEGIN DESCRIPTION:
This cross section corresponds to cross section 109221 of the non-georeferenced CDC model which was the source of this model.
Proposed fill & lake.
END DESCRIPTION:
XS GIS Cut Line= 5
2399516.235699716980181.61877655      2399517.05      6980131.73
     2399592.973     6975480.245 2399626.2878738 6974480.8000945
 2399662.3678821 6973398.4012618
#Sta/Elev= 8
   -1732     474    2970   467.7    3070   466.7    3135     450    3785     450
    3870   466.7    3970   467.7    5053   467.7
#Mann= 5 ,-1,0
   -1732     .07       0    3070     .08       0    3135     .05       0
    3785     .08       0    3870     .07       0
#XS Ineff= 2 , 0
            2970     475    3970             475
Permanent Ineff=
       F       F
Bank Sta=3135,3785
XS Rating Curve= 0 ,0
Exp/Cntr=0.5,0.3

Type RM Length L Ch R = 1 ,108686  ,387,325,300
BEGIN DESCRIPTION:
This cross section corresponds to cross section 108686 of the non-georeferenced CDC model which was the source of this model.
Proposed fill & lake.
END DESCRIPTION:
XS GIS Cut Line= 4
      2399710.63      6980176.55     2399898.529     6975466.356
     2399794.362       6974410.8     2399853.926     6972696.601
#Sta/Elev= 12
   -1969     474    2750   467.7    2850   466.7    2927     450    2949     445
    3030     427    3515     427    3621     445    3650     450    3750   466.7
    3850   467.7    5450     468
#Mann= 5 ,-1,0
   -1969     .07       0    2850     .08       0    2949     .05       0
    3621     .08       0    3750     .07       0
#XS Ineff= 3 ,-1
   -1969    2750     480    2750    3850     444    3850    5450     480
Permanent Ineff=
       F       T       F
#Block Obstruct= 2 , 0
            3850     440
Bank Sta=2949,3621
XS Rating Curve= 0 ,0
Exp/Cntr=0.3,0.1

Type RM Length L Ch R = 1 ,108571  ,293,299,304
BEGIN DESCRIPTION:
This cross section corresponds to cross section 108571 of the non-georeferenced CDC model which was the source of this model.
Proposed fill & lake.
END DESCRIPTION:
XS GIS Cut Line= 5
2400179.903046936979751.74120671      2400180.04      6979716.92
      2400197.14     6975369.134     2400190.196     6975112.189
      2400009.64     6974299.689
#Sta/Elev= 9
   -1714     474    2675   467.7    2775   466.7    2851     450    2874     445
    2955     427    3610     427    3737     445    3758     448
#Mann= 4 ,-1,0
   -1714     .07       0    2775     .08       0    2874     .05       0
    3737     .08       0
#XS Ineff= 3 ,-1
   -1714    2675     480    2675    3758     444    3758    3758     468
Permanent Ineff=
       F       F       T
#Block Obstruct= 2 , 0
            3758     440
Bank Sta=2874,3737
XS Rating Curve= 0 ,0
Exp/Cntr=0.3,0.1

Type RM Length L Ch R = 1 ,108466  ,349,378,381
BEGIN DESCRIPTION:
This cross section corresponds to cross section 108466 of the non-georeferenced CDC model which was the source of this model.
Proposed fill & lake.
END DESCRIPTION:
XS GIS Cut Line= 5
2400295.081287336979821.03792808      2400296.99      6979761.02
     2400440.196     6975258.023     2400440.196     6975084.411
     2400252.696     6974146.911
#Sta/Elev= 7
   -1757     474    2750   467.7    2850   466.7    2916     450    2935     445
    3005     427    3938     427
#Mann= 3 ,-1,0
   -1757     .07       0    2850     .08       0    2935     .05       0
#XS Ineff= 3 ,-1
   -1757    2750     480    2750    3938     444    3938    3939     480
Permanent Ineff=
       F       T       F
#Block Obstruct= 2 , 0
            3938     440
Bank Sta=2935,3938
XS Rating Curve= 0 ,0
Exp/Cntr=0.3,0.1

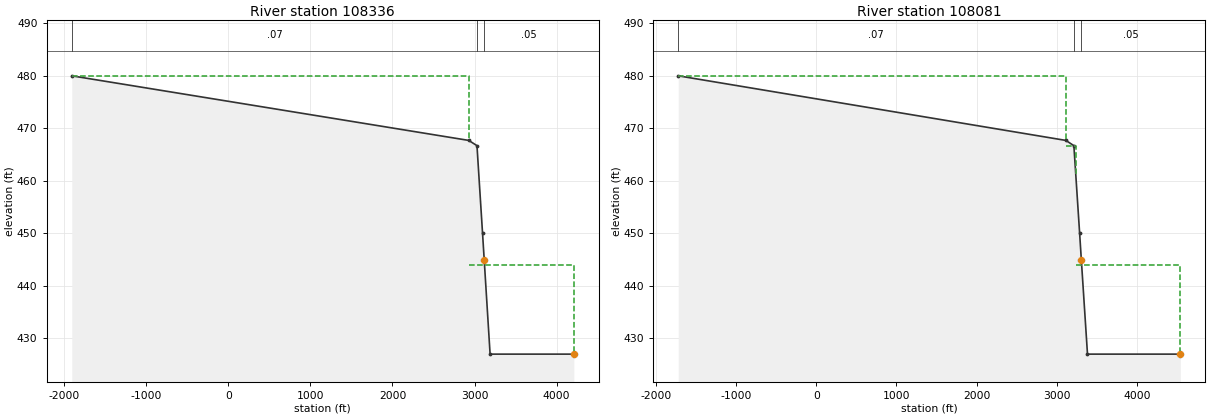
Type RM Length L Ch R = 1 ,108336  ,912,977,1015
BEGIN DESCRIPTION:
This cross section corresponds to cross section 108336 of the non-georeferenced CDC model which was the source of this model.
Proposed fill & lake.
END DESCRIPTION:
XS GIS Cut Line= 5
2400473.856313566980054.855410512400481.849440816979919.72090473
      2400759.64       6975223.3     2400502.696     6974008.023
 2400508.1618044 6973969.5520072
#Sta/Elev= 7
   -1910     480    2930   467.7    3030   466.7    3098     450    3118     445
    3190     427    4211     427
#Mann= 3 ,-1,0
   -1910     .07       0    3030     .08       0    3118     .05       0
#XS Ineff= 3 ,-1
   -1910    2930     480    2930    4211     444    4211    4212     480
Permanent Ineff=
       F       T       F
#Block Obstruct= 2 , 0
            4211     440
Bank Sta=3118,4211
XS Rating Curve= 0 ,0
Exp/Cntr=0.3,0.1

Type RM Length L Ch R = 1 ,108081  ,0,0,0
BEGIN DESCRIPTION:
This cross section corresponds to cross section 108081 of the non-georeferenced CDC model which was the source of this model.
Proposed fill & lake.
END DESCRIPTION:
XS GIS Cut Line= 4
     2400563.489     6980041.378 2400973.3897839 6974411.9083682
     2400863.807     6973827.467     2400905.473     6972994.134
#Sta/Elev= 7
   -1725     480    3115   467.7    3215   466.7    3287     450    3308     445
    3385     427    4544     427
#Mann= 3 ,-1,0
   -1725     .07       0    3215     .08       0    3308     .05       0
#XS Ineff= 4 ,-1
   -1725    3115     480    3115    3240   466.7    3240    4544     444
    4544    4545     480
Permanent Ineff=
       F       T       T       F
#Block Obstruct= 2 , 0
                            3115             440
Bank Sta=3308,4544
XS Rating Curve= 0 ,0
Exp/Cntr=0.3,0.1

River Reach=West Fork       ,wf3e
Reach XY= 30
      2398149.68       6972930.3       2398272.9      6972905.14
      2398380.45      6972824.06      2398470.39       6972723.8
      2398513.59      6972656.52      2398565.14      6972545.81
       2398598.1      6972415.21      2398648.54      6972291.67
      2398682.44       6972234.1      2398766.02      6972130.07
      2398844.89      6972110.64      2399209.83      6972073.04
      2399251.73      6972060.05        2399308.       6972026.2
      2399568.34      6971799.56      2399629.26      6971768.58
       2399694.8      6971749.25      2399762.78      6971742.21
       2399830.9      6971747.72      2400100.05      6971811.56
       2400284.1      6971832.38      2400299.67      6971840.13
      2400309.83      6971854.25      2400472.44      6971900.62
      2400668.07       6971924.4      2400880.81      6971976.72
       2401003.6      6971989.88      2401324.96       6972073.4
      2401404.06      6972099.66      2401546.94      6972159.85

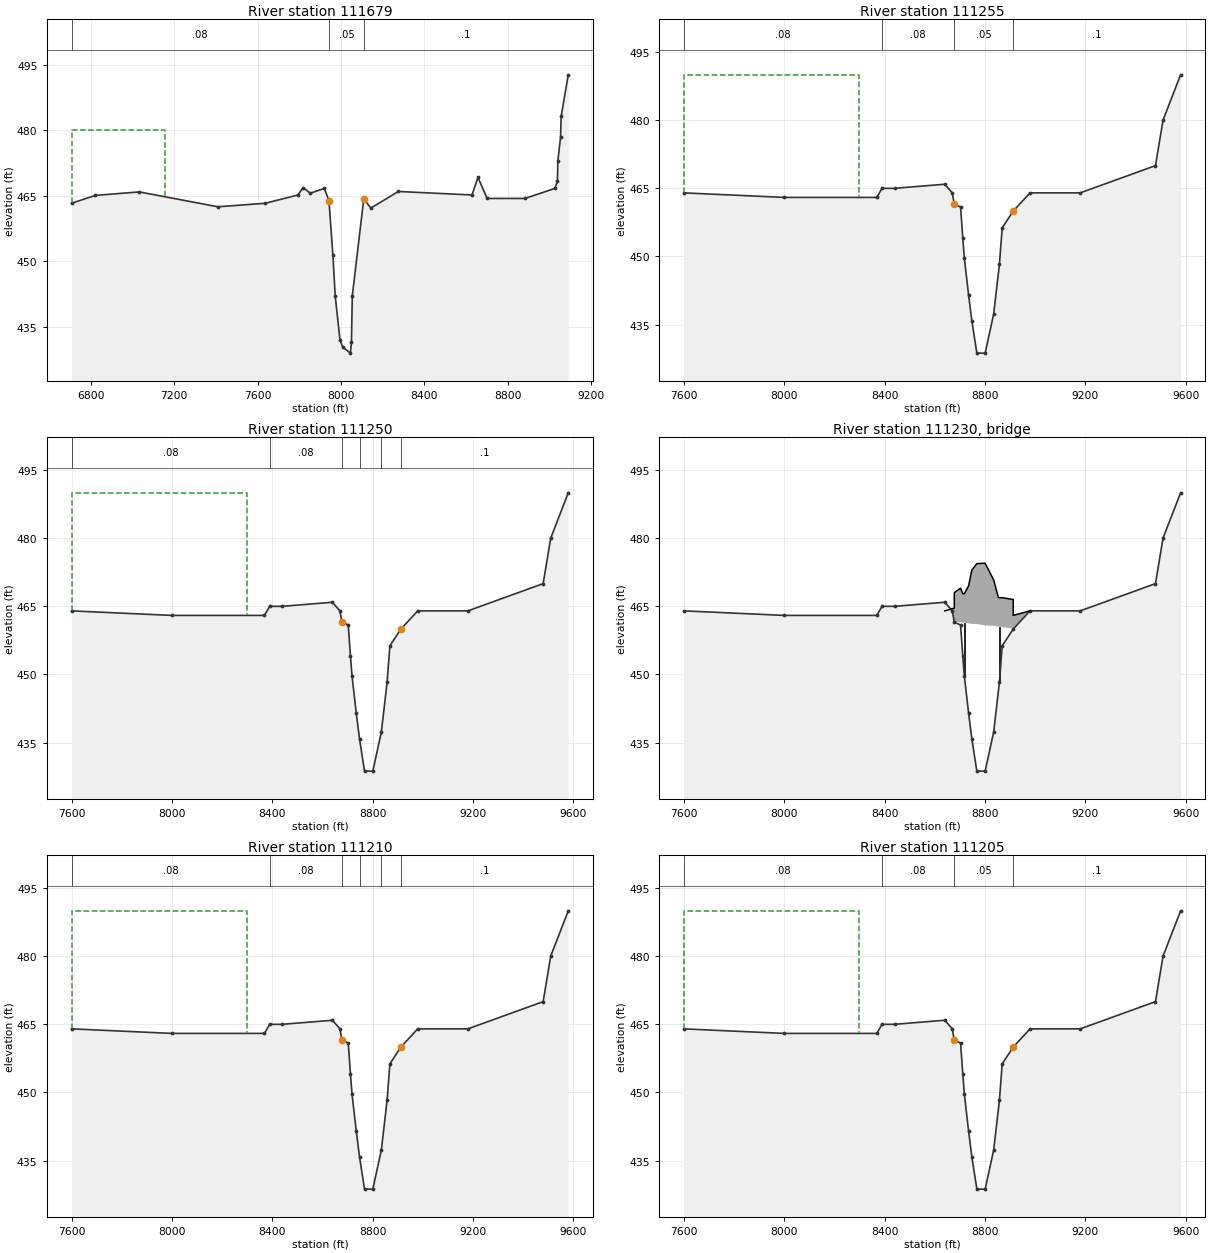
Type RM Length L Ch R = 1 ,111679  ,118,381,189
BEGIN DESCRIPTION:
This cross section corresponds to cross section 111679 of the non-georeferenced CDC model which was the source of this model.
Cross Section Truncated due to Ineffective Flow Areas
END DESCRIPTION:
XS GIS Cut Line= 6
     2398328.751     6974137.508     2398328.715     6974119.508
     2398328.522     6974023.508     2398326.893     6973214.789
     2398174.252     6972585.482      2397691.47     6971969.229
#Sta/Elev= 30
    6707   463.3    6821   465.1    7032   465.9    7409   462.5    7637   463.3
    7793   465.2    7819   466.9    7852   465.6    7920   466.7    7942   463.9
    7961   451.4    7972   442.1    7995     432    8008   430.4    8045     429
    8050   431.5    8054   442.1    8109   464.3    8143   462.2    8275     466
    8628   465.2    8657   469.2    8701   464.4    8882   464.4    9026   466.7
    9038   468.3    9040   472.9    9053   478.4    9056   483.2    9090   492.7
#Mann= 3 ,0,0
    6707     .08       0    7942     .05       0    8109      .1       0
#XS Ineff= 2 , 0
            7155     480
Permanent Ineff=
       F       F
Bank Sta=7942,8109
XS Rating Curve= 0 ,0
Exp/Cntr=0.3,0.1

Type RM Length L Ch R = 1 ,111255  ,6,6,6
BEGIN DESCRIPTION:
This cross section corresponds to cross section 111255 of the non-georeferenced CDC model which was the source of this model.
END DESCRIPTION:
XS GIS Cut Line= 5
  2398629.665616 6973654.1282992     2398631.009     6973333.515
      2398633.94     6972634.264      2398394.66     6972660.029
     2397863.089     6972175.199
#Sta/Elev= 24
    7600     464    8000     463    8369     463    8390     465    8440     465
    8640   465.9    8670     464    8678   461.5    8703   460.9    8712     454
    8718   449.7    8735   441.5    8748   435.8    8768   428.7    8801   428.7
    8835   437.3    8858   448.3    8869   456.3    8913     460    8980     464
    9180     464    9480     470    9510     480    9580     490
#Mann= 4 ,-1,0
    7600     .08       0    8390     .08       0    8678     .05       0
    8913      .1       0
#XS Ineff= 2 , 0
            8300     490
Permanent Ineff=
       F       F
Bank Sta=8678,8913
XS Rating Curve= 0 ,0
Exp/Cntr=0.3,0.1

Type RM Length L Ch R = 1 ,111250  ,14,14,14
BEGIN DESCRIPTION:
This cross section corresponds to cross section 111250 of the non-georeferenced CDC model which was the source of this model.
END DESCRIPTION:
XS GIS Cut Line= 5
  2398633.710544 6973648.3301982     2398635.046     6973329.609
     2398637.976     6972630.358     2398397.013     6972653.605
     2397867.326     6972166.018
#Sta/Elev= 24
    7600     464    8000     463    8369     463    8390     465    8440     465
    8640   465.9    8670     464    8678   461.5    8703   460.9    8712     454
    8718   449.7    8735   441.5    8748   435.8    8768   428.7    8801   428.7
    8835   437.3    8858   448.3    8869   456.3    8913     460    8980     464
    9180     464    9480     470    9510     480    9580     490
#Mann= 6 ,-1,0
    7600     .08       0    8390     .08       0    8678     .03       0
    8748     .05       0    8835     .03       0    8913      .1       0
#XS Ineff= 2 , 0
            8300     490
Permanent Ineff=
       F       F
Bank Sta=8678,8913
XS Rating Curve= 0 ,0
Exp/Cntr=0.3,0.1

Type RM Length L Ch R = 3 ,111230  ,,,
BEGIN DESCRIPTION:
River Legacy Parks Pedestrian Bridge
END DESCRIPTION:
Node Name=River Legacy Par
Bridge Culvert--1,0,-1,-1, 0
Deck Dist Width WeirC Skew NumUp NumDn MinLoCord MaxHiCord MaxSubmerge Is_Ogee
0.5,12,2.6,0, 16, 16, , , 0.95, 0, 0,0,,
    8640    8678  8678.1    8703    8712    8718    8735    8748    8768    8801
    8835    8854    8869    8913    8913    8980
     464   464.6     468     469   467.8  467.75   469.5     473   474.4   474.5
   470.8   466.9   466.9   466.5     463     464
     464   461.6   461.6   461.5   461.4   461.4  461.25  461.15   461.1   460.8
   460.7   460.5   460.4   460.1   460.1     464
    8640    8678  8678.1    8703    8712    8718    8735    8748    8768    8801
    8835    8854    8869    8913    8913    8980
     464   464.6     468     469   467.8  467.75   469.5     473   474.4   474.5
   470.8   466.9   466.9   466.5     463     464
     464   461.6   461.6   461.5   461.4   461.4  461.25  461.15   461.1   460.8
   460.7   460.5   460.4   460.1   460.1     464
Pier Skew, UpSta & Num, DnSta & Num=  ,8718, 2 ,8718, 2 , 0 , 0 , 0 ,,
       5       5
     454   461.4
       5       5
     454   461.4
Pier Skew, UpSta & Num, DnSta & Num=  ,8858, 2 ,8858, 2 , 0 , 0 , 0 ,,
       5       5
   448.3   463.4
       5       5
   448.3   463.4
BR Coef=-1 , 0 , 0 ,, 0 ,,,0.8,-1,,0,
WSPro=,,,, 1 ,,,, 0 ,,,, 0 ,,,,-1 ,-1 ,-1 , 0 , 0 , 0 , 0 , 0
BC Design=,, 0 ,, 0 ,,,,,,
BC Use User HTab Curves=0
BC User HTab FreeFlow(D)= 0

Type RM Length L Ch R = 1 ,111210  ,11,11,11
BEGIN DESCRIPTION:
This cross section corresponds to cross section 111210 of the non-georeferenced CDC model which was the source of this model.
END DESCRIPTION:
XS GIS Cut Line= 5
  2398636.512847 6973652.5738443     2398637.884     6973325.333
     2398640.156     6972620.358     2398401.527     6972639.716
     2397886.857     6972152.997
#Sta/Elev= 24
    7600     464    8000     463    8369     463    8390     465    8440     465
    8640   465.9    8670     464    8678   461.5    8703   460.9    8712     454
    8718   449.7    8735   441.5    8748   435.8    8768   428.7    8801   428.7
    8835   437.3    8858   448.3    8869   456.3    8913     460    8980     464
    9180     464    9480     470    9510     480    9580     490
#Mann= 6 ,-1,0
    7600     .08       0    8390     .08       0    8678     .03       0
    8748     .05       0    8835     .03       0    8913      .1       0
#XS Ineff= 2 , 0
            8300     490
Permanent Ineff=
       F       F
Bank Sta=8678,8913
XS Rating Curve= 0 ,0
Exp/Cntr=0.3,0.1

Type RM Length L Ch R = 1 ,111205  ,512,773,736
BEGIN DESCRIPTION:
This cross section corresponds to cross section 111205 of the non-georeferenced CDC model which was the source of this model.
END DESCRIPTION:
XS GIS Cut Line= 5
  2398643.253853 6973644.8589526      2398644.33     6973299.942
     2398646.483     6972609.437      2398403.35     6972630.775
     2397895.972     6972147.789
#Sta/Elev= 24
    7600     464    8000     463    8369     463    8390     465    8440     465
    8640   465.9    8670     464    8678   461.5    8703   460.9    8712     454
    8718   449.7    8735   441.5    8748   435.8    8768   428.7    8801   428.7
    8835   437.3    8858   448.3    8869   456.3    8913     460    8980     464
    9180     464    9480     470    9510     480    9580     490
#Mann= 4 ,-1,0
    7600     .08       0    8390     .08       0    8678     .05       0
    8913      .1       0
#XS Ineff= 2 , 0
            8300     490
Permanent Ineff=
       F       F
Bank Sta=8678,8913
XS Rating Curve= 0 ,0
Exp/Cntr=0.3,0.1

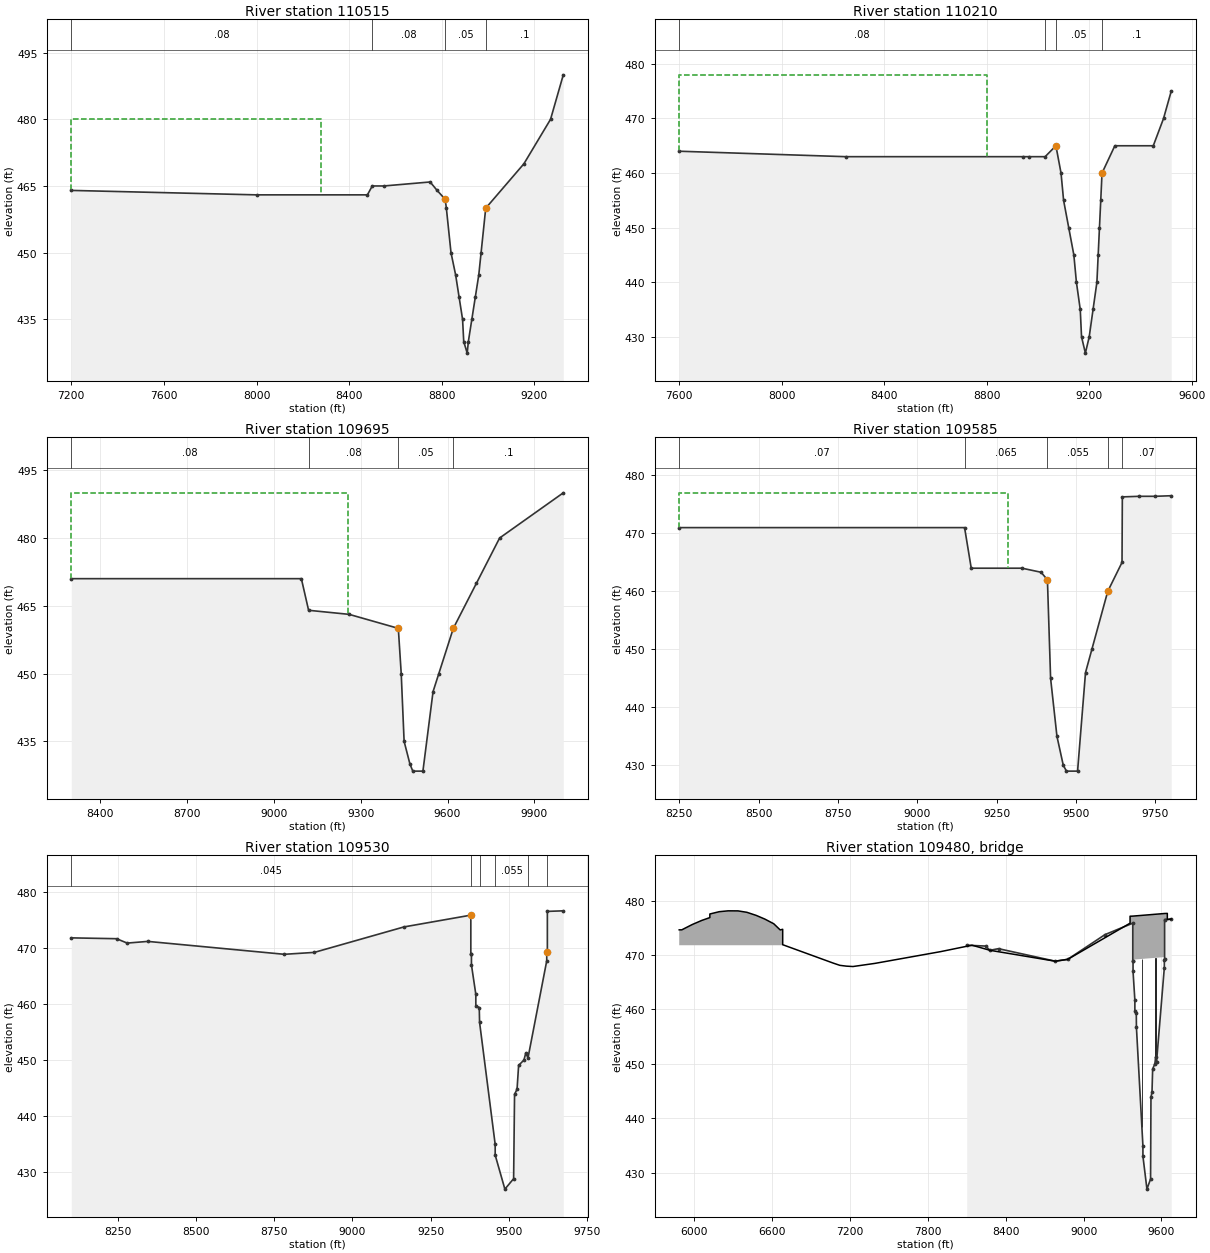
Type RM Length L Ch R = 1 ,110515  ,332,312,306
BEGIN DESCRIPTION:
This cross section corresponds to cross section 110515 of the non-georeferenced CDC model which was the source of this model.
Flow limit due to Collins St.  LOB realigned
END DESCRIPTION:
XS GIS Cut Line= 6
  2398952.920099 6973733.2811278  2399160.774652 6972960.7550861
 2399241.3734685 6972661.1961669 2399001.9766376 6972197.6829863
 2398961.2280314 6971927.7248648 2398929.2069109 6971709.9803793
#Sta/Elev= 24
    7200     464    8000     463    8479     463    8500     465    8550     465
    8750   465.9    8780     464    8815     462    8820     460    8840     450
    8860     445    8875     440    8890     435    8895     430    8910   427.4
    8915     430    8930     435    8945     440    8960     445    8970     450
    8990     460    9155     470    9270     480    9325     490
#Mann= 4 ,-1,0
    7200     .08       0    8500     .08       0    8815     .05       0
    8990      .1       0
#XS Ineff= 2 , 0
            8280     480
Permanent Ineff=
       F       F
Bank Sta=8815,8990
XS Rating Curve= 0 ,0
Exp/Cntr=0.3,0.1

Type RM Length L Ch R = 1 ,110210  ,500,525,510
BEGIN DESCRIPTION:
This cross section corresponds to cross section 110210 of the non-georeferenced CDC model which was the source of this model.
Flow limit due to Collins St.  LOB realigned  X-SECTION BASED ON 1991 SURVEY DATA
END DESCRIPTION:
XS GIS Cut Line= 6
 2399113.76565436973510.21347595  2399292.334293  6972885.222883
 2399328.0480208 6972760.2247642  2399445.115187 6972350.4894392
 2399302.4960497 6972100.9056208 2399216.6191972  6971683.232204
#Sta/Elev= 25
    7600     464    8250     463    8941     463    8965     463    9028     463
    9070     465    9090     460    9100     455    9120     450    9140     445
    9150     440    9165     435    9170     430    9185     427    9200     430
    9215     435    9230     440    9235     445    9240     450    9245     455
    9250     460    9300     465    9450     465    9490     470    9520     475
#Mann= 4 ,-1,0
    7600     .08       0    9028     .08       0    9070     .05       0
    9250      .1       0
#XS Ineff= 2 , 0
            8800     478
Permanent Ineff=
       F       F
Bank Sta=9070,9250
XS Rating Curve= 0 ,0
Exp/Cntr=0.3,0.1

Type RM Length L Ch R = 1 ,109695  ,46,113,186
BEGIN DESCRIPTION:
This cross section corresponds to cross section 109695 of the non-georeferenced CDC model which was the source of this model.
Flow limit due to Collins St.  LOB realigned  X-SECTION BASED ON 1991 SURVEY DATA
END DESCRIPTION:
XS GIS Cut Line= 4
  2399434.578781 6972953.1941999 2399750.7284209 6971963.3799772
 2399715.0733085 6971800.3862087 2399715.0733085 6971306.3120657
#Sta/Elev= 16
    8300     471    9095     471    9120     464    9260   463.1    9430     460
    9440     450    9450     435    9470     430    9480   428.4    9515   428.4
    9550     446    9570     450    9620     460    9700     470    9780     480
   10000     490
#Mann= 4 ,-1,0
    8300     .08       0    9120     .08       0    9430     .05       0
    9620      .1       0
#XS Ineff= 2 , 0
            9255     490
Permanent Ineff=
       F       F
Bank Sta=9430,9620
XS Rating Curve= 0 ,0
Exp/Cntr=0.5,0.3

Type RM Length L Ch R = 1 ,109585  ,72,79,72
BEGIN DESCRIPTION:
This cross section corresponds to cross section 109585 of the non-georeferenced CDC model which was the source of this model.
Flow limit due to Collins St.  X-SECTION BASED ON 1991 SURVEY DATA
END DESCRIPTION:
XS GIS Cut Line= 5
  2399472.927761 6972948.6862018 2399561.2135832 6972688.2430917
 2399796.5701928 6971993.9412678 2399786.3832052 6971846.2283087
 2399939.3448134  6971483.319005
#Sta/Elev= 19
    8250     471    9149     471    9170     464    9330     464    9390   463.3
    9410     462    9420     445    9440     435    9460     430    9470     429
    9505     429    9530     446    9550     450    9600     460    9645     465
    9646   476.3    9700   476.4    9750   476.4    9800   476.5
#Mann= 5 ,-1,0
    8250     .07       0    9149    .065       0    9410    .055       0
    9600    .065       0    9646     .07       0
#XS Ineff= 2 , 0
            9285     477
Permanent Ineff=
       F       F
Bank Sta=9410,9600
XS Rating Curve= 0 ,0
Exp/Cntr=0.5,0.3

Type RM Length L Ch R = 1 ,109530  ,124,124,124
BEGIN DESCRIPTION:
This cross section corresponds to cross section 109530 of the non-georeferenced CDC model which was the source of this model.
U/S FACE OF F.M. 157 BRIDGE Surveyed 2006  n values in channel reflect conc. and gabions
END DESCRIPTION:
XS GIS Cut Line= 6
  2399475.411282 6973101.9116035 2399562.2400671 6972783.5395535
 2399562.2400671 6972783.5395535 2399562.2668556 6972783.4413292
 2399628.4832586 6972523.6701952 2399963.5271664  6971606.106114
#Sta/Elev= 30
    8100   471.8    8245  471.65    8279  470.87    8345  471.17    8782  468.87
    8878  469.21    9165  473.75    9379  475.85    9379  468.86    9381  468.84
    9381  466.99    9395  461.73    9395  459.71    9406  459.38    9407  456.74
    9457  434.97    9457  433.08    9488  427.01    9516  428.87    9519  443.91
    9527  444.82    9532  449.07    9549  450.02    9555  451.28    9562   450.4
    9622  467.71    9622  469.18    9624  469.21    9624  476.52    9675  476.62
#Mann= 6 ,-1,0
    8100    .045       0    9379     .02       0    9407     .03       0
    9457    .055       0    9562     .02       0    9624    .045       0
#Block Obstruct= 2 , 0
            9379
Bank Sta=9379,9624
XS Rating Curve= 0 ,0
Exp/Cntr=0.5,0.3

Type RM Length L Ch R = 3 ,109480  ,,,
BEGIN DESCRIPTION:
FM 157
NEW X-SECTION BASED ON 1991 SURVEY DATA AND COE BRIDGE SECTIONS
D/S FACE OF WIDENED AND REALIGNED F.M. 157 BRIDGE
END DESCRIPTION:
Node Name=FM 157
Bridge Culvert--1,0,0,-1, 0
Deck Dist Width WeirC Skew NumUp NumDn MinLoCord MaxHiCord MaxSubmerge Is_Ogee
0.01,123,2.6,0, 34, 34, , , 0.95, 0, 0,0,,
    5886    5906    5986    6059    6122    6122    6194    6263    6339    6407
    6478    6545    6614 6663.87    6683    6683    7072    7123    7174    7224
    7394    7900    8141    8279    8782    8878    9358    9358    9379    9624
    9645    9645    9656    9675
  474.63  474.63   475.6  476.35  476.88  477.54  477.96  478.12  478.11  477.85
  477.29  476.61  475.75  474.61  474.73   471.9  468.52  468.11  467.96  467.89
  468.47  470.63  471.81  470.87  468.87  469.21  475.85  477.13  477.15  477.63
  477.65  476.52  476.53  476.62
     465  465.87  466.84  467.59  468.12  468.12  468.54   468.7  468.69  468.43
  467.87  467.19  466.33  466.19  466.19     465     465     465     465     465
     465     465     465     465     465     465     465     465  469.15  469.63
     465     465     465     465
    5886    5906    5986    6059    6122    6122    6194    6263    6339    6407
    6478    6545    6614 6663.87    6683    6683    7072    7123    7174    7224
    7394    7900    8141    8279    8782    8878    9358    9358    9379    9624
    9645    9645    9656    9675
  474.63  474.63   475.6  476.35  476.88  477.54  477.96  478.12  478.11  477.85
  477.29  476.61  475.75  474.61  474.73   471.9  468.52  468.11  467.96  467.89
  468.47  470.63  471.81  470.87  468.87  469.21  475.85  477.13  477.15  477.63
  477.65  476.52  476.53  476.62
     465  465.87  466.84  467.59  468.12  468.12  468.54   468.7  468.69  468.43
  467.87  467.19  466.33  466.19  466.19     465     465     465     465     465
     465     465     465     465     465     465     465     465  469.15  469.63
     465     465     465     465
Pier Skew, UpSta & Num, DnSta & Num=  ,6015.91, 2 ,6015.91, 2 , 0 , 0 , 0 ,,
    3.28    3.28
  419.95  466.78
    3.28    3.28
  419.95  466.78
Pier Skew, UpSta & Num, DnSta & Num=  ,6124.18, 2 ,6124.18, 2 , 0 , 0 , 0 ,,
    3.28    3.28
  419.95   469.8
    3.28    3.28
  419.95   469.8
Pier Skew, UpSta & Num, DnSta & Num=  ,6232.44, 2 ,6232.44, 2 , 0 , 0 , 0 ,,
    3.28    3.28
  413.39   469.8
    3.28    3.28
  413.39   469.8
Pier Skew, UpSta & Num, DnSta & Num=  ,6340.71, 2 ,6340.71, 2 , 0 , 0 , 0 ,,
    3.28    3.28
  413.39   469.8
    3.28    3.28
  413.39   469.8
Pier Skew, UpSta & Num, DnSta & Num=  ,6448.98, 2 ,6448.98, 2 , 0 , 0 , 0 ,,
    3.28    3.28
  413.39   469.8
    3.28    3.28
  413.39   469.8
Pier Skew, UpSta & Num, DnSta & Num=  ,6557.25, 2 ,6557.25, 2 , 0 , 0 , 0 ,,
    3.28    3.28
  413.39   469.8
    3.28    3.28
  413.39   469.8
Pier Skew, UpSta & Num, DnSta & Num=  ,9449, 2 ,9449, 2 , 0 , 0 , 0 ,,
       3       3
     445   469.8
       3       3
     445   469.8
Pier Skew, UpSta & Num, DnSta & Num=  ,9555, 2 ,9555, 2 , 0 , 0 , 0 ,,
       3       3
     450   469.8
       3       3
     450   469.8
BR Coef= 0 , 0 , 1 ,1.05, 0 ,,,0.8006408,-1,1.2,2,469.63
WSPro=,,,, 1 ,,,, 0 ,,,, 0 ,,,,-1 ,-1 ,-1 , 0 , 0 , 0 , 0 , 0
BC Design=,, 0 ,, 0 ,,,,,,
BC HTab HWMax=476.5
BC Use User HTab Curves=0
BC User HTab FreeFlow(D)= 0

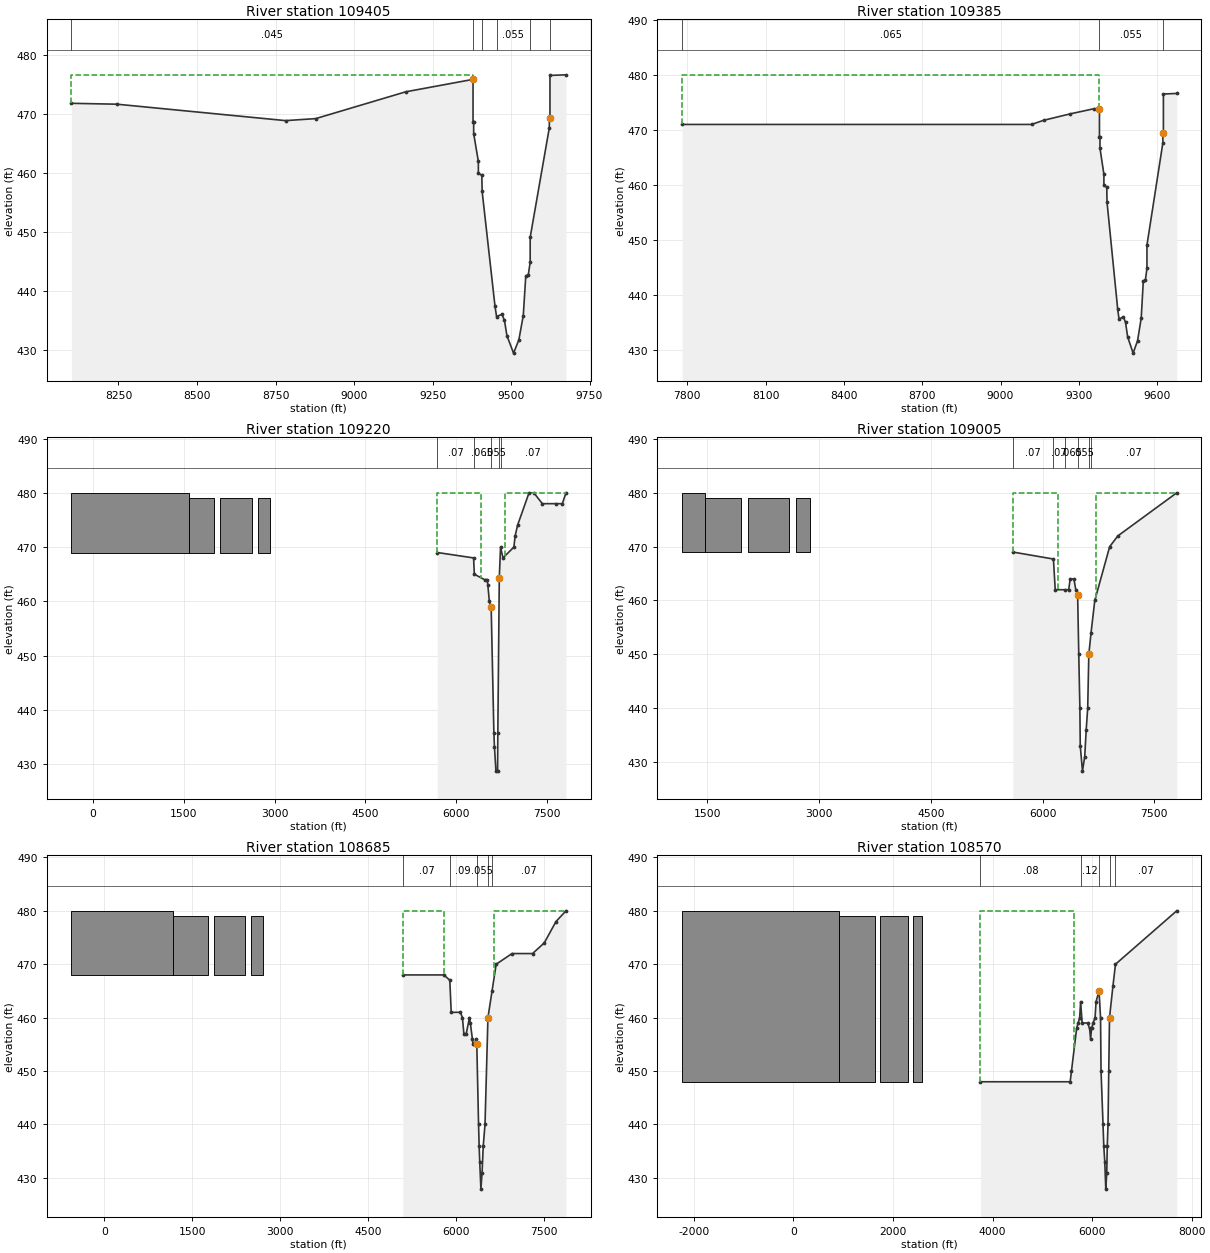
Type RM Length L Ch R = 1 ,109405  ,23,23,23
BEGIN DESCRIPTION:
This cross section corresponds to cross section 109405 of the non-georeferenced CDC model which was the source of this model.
D/S FACE OF F.M. 157 BRIDGE Surveyed 2006  n values in channel reflect conc. and gabions
END DESCRIPTION:
XS GIS Cut Line= 3
     2399586.066     6973112.325     2399773.956     6972387.607
     2400063.843     6971641.416
#Sta/Elev= 30
    8100   471.8    8245  471.65    8782  468.87    8878  469.21    9165  473.75
    9379  475.85    9379   468.7    9381  468.69    9381  466.69    9396  461.96
    9396  459.95    9407  459.62    9408  456.91    9449  437.45    9454  435.71
    9471  436.09    9479  435.08    9487  432.47    9508  429.52    9525  431.77
    9539  435.87    9547  442.58    9555  442.77    9561  444.91    9561  449.11
    9622  467.67    9622  469.34    9624  469.38    9624  476.52    9675  476.62
#Mann= 6 ,-1,0
    8100    .045       0    9379     .02       0    9408     .03       0
    9454    .055       0    9561     .02       0    9624    .045       0
#XS Ineff= 2 , 0
            9379  476.62
Permanent Ineff=
       F       F
Bank Sta=9379,9624
XS Rating Curve= 0 ,0
Exp/Cntr=0.5,0.3

Type RM Length L Ch R = 1 ,109385  ,122,168,168
BEGIN DESCRIPTION:
This cross section corresponds to cross section 109385 of the non-georeferenced CDC model which was the source of this model.
20 FT D/S OF F.M. 157 ROADWAY EMBANKMENT  X-SECTION BASED ON 1991 SURVEY DATA
END DESCRIPTION:
XS GIS Cut Line= 4
2399607.089271096973459.57179626   2399606.13214  6973138.973548
 2399799.6868712 6972395.3155865 2400087.3454747 6971642.4314873
#Sta/Elev= 30
    7780     471    9119     471    9165  471.75    9266  472.91    9358  473.85
    9379  473.85    9379   468.7    9381  468.69    9381  466.69    9396  461.96
    9396  459.95    9407  459.62    9408  456.91    9449  437.45    9454  435.71
    9471  436.09    9479  435.08    9487  432.47    9508  429.52    9525  431.77
    9539  435.87    9547  442.58    9555  442.77    9561  444.91    9561  449.11
    9622  467.67    9622  469.34    9624  469.38    9624  476.52    9675  476.62
#Mann= 3 ,-1,0
    7780    .065       0    9379    .055       0    9624     .12       0
#XS Ineff= 2 , 0
            9379     480
Permanent Ineff=
       F       F
Bank Sta=9379,9624
XS Rating Curve= 0 ,0
Exp/Cntr=0.5,0.3

Type RM Length L Ch R = 1 ,109220  ,212,212,207
BEGIN DESCRIPTION:
This cross section corresponds to cross section 109220 of the non-georeferenced CDC model which was the source of this model.
Proposed fill on LOB.  Left flow limit due to Collins.  LOB realigned.  LOB from 2001 aerial topo.  ROB of X-SECTION BASED ON 1991 AND 2001 SURVEY DATA
END DESCRIPTION:
XS GIS Cut Line= 4
2399839.477446266972722.24075148      2400023.23      6972257.23
     2400426.307     6971237.1892400620.425799676970745.94505769
#Sta/Elev= 26
    5685     469    6285     468    6297     465    6465     464    6510     464
    6520     463    6545     460    6565     459    6575     459    6620   435.7
    6629   433.2    6654   428.7    6681   428.8    6685   435.7    6709   464.3
    6730     470    6770     468    6950     470    6970     472    7010     474
    7200     480    7280     480    7420     478    7650     478    7750     478
    7810     480
#Mann= 5 ,-1,0
    5685     .07       0    6285    .065       0    6575    .055       0
    6709     .12       0    6730     .07       0
#XS Ineff= 2 , 0
            6405     480    6810             480
Permanent Ineff=
       F       F
#Block Obstruct= 4 ,-1
    -355    1580     480    1580    2005     479    2100    2625     479
    2725    2920     479
Bank Sta=6575,6709
XS Rating Curve= 0 ,0
Exp/Cntr=0.5,0.3

Type RM Length L Ch R = 1 ,109005  ,238,317,302
BEGIN DESCRIPTION:
This cross section corresponds to cross section 109005 of the non-georeferenced CDC model which was the source of this model.
Proposed fill on LOB.  Left flow limit due to Collins.  LOB realigned.  LOB from 2001 aerial topo.  ROB of X-SECTION BASED ON 1991 AND 2001 SURVEY DATA
END DESCRIPTION:
XS GIS Cut Line= 5
2400071.17191322 6972792.1401285      2400219.08      6972372.44
     2400527.214     6971498.087     2400567.192     6971291.532
2400684.539321576970685.23163465
#Sta/Elev= 22
    5600     469    6145   467.7    6169     462    6300     462    6350     462
    6370     464    6420     464    6445     462    6470     461    6485     450
    6500     440    6505     433    6535   428.3    6565     431    6585     436
    6605     440    6620     450    6650     454    6700     460    6900     470
    7010     472    7800     480
#Mann= 6 ,-1,0
    5600     .07       0    6145     .07       0    6300    .065       0
    6470    .055       0    6620     .12       0    6650     .07       0
#XS Ineff= 2 , 0
            6200     480    6710             480
Permanent Ineff=
       F       F
#Block Obstruct= 4 ,-1
    1160    1470     480    1470    1950     479    2050    2590     479
    2690    2880     479
Bank Sta=6470,6620
XS Rating Curve= 0 ,0
Exp/Cntr=0.5,0.3

Type RM Length L Ch R = 1 ,108685  ,154,111,101
BEGIN DESCRIPTION:
This cross section corresponds to cross section 108685 of the non-georeferenced CDC model which was the source of this model.
Proposed fill on LOB.  LOB realigned.  LOB from 2001 aerial topo.  ROB of X-SECTION BASED ON 1991 AND 2001 SURVEY DATA
END DESCRIPTION:
XS GIS Cut Line= 6
 2400149.74043816973156.69791381      2400249.84      6972946.12
     2400669.362     6972063.578     2400836.029     6971445.523
 2400991.3839815 6970558.6361728      2400992.24      6970529.51
#Sta/Elev= 30
    5090     468    5790     468    5890     467    5914     461    6070     461
    6105     460    6130     457    6170     457    6225     460    6240     459
    6275     456    6285     455    6305     455    6340     456    6350     455
    6380     440    6390     436    6400     433    6420   427.9    6440     431
    6460     436    6490     440    6540     460    6610     465    6680     470
    6950     472    7300     472    7500     474    7700     478    7870     480
#Mann= 5 ,-1,0
    5090     .07       0    5890     .09       0    6350    .055       0
    6540     .12       0    6610     .07       0
#XS Ineff= 2 , 0
            5790     480    6650             480
Permanent Ineff=
       F       F
#Block Obstruct= 4 ,-1
    -560    1180     480    1180    1765     479    1865    2405     479
    2505    2700     479
Bank Sta=6350,6540
XS Rating Curve= 0 ,0
Exp/Cntr=0.5,0.3

Type RM Length L Ch R = 1 ,108570  ,124,113,108
BEGIN DESCRIPTION:
This cross section corresponds to cross section 108570 of the non-georeferenced CDC model which was the source of this model.
Proposed lake on LOB.  LOB realigned.  LOB from 2001 aerial topo.  ROB of X-SECTION BASED ON 1991 AND 2001 SURVEY DATA
END DESCRIPTION:
XS GIS Cut Line= 6
      2400009.58      6974291.02 2400481.4957202 6972560.5638811
     2400495.751     6972508.023     2400780.473     6972112.189
     2400919.362     6971445.5232401004.479133336970524.11449762
#Sta/Elev= 30
    3758     448    5560     448    5586     450    5690     458    5720     459
    5750     460    5770     463    5800     459    5910     459    5950     458
    5970     456    5990     458    6020     459    6060     460    6080     463
    6140     465    6170     460    6180     450    6220     440    6235     436
    6255     433    6275   427.9    6295     431    6305     436    6320     440
    6335     450    6350     460    6420     466    6470     470    7700     480
#Mann= 5 ,-1,0
    3758     .08       0    5770     .12       0    6140    .055       0
    6350     .12       0    6470     .07       0
#XS Ineff= 2 , 0
            5634     480
Permanent Ineff=
       F       F
#Block Obstruct= 4 ,-1
   -2235     920     480     920    1645     479    1745    2295     479
    2395    2575     479
Bank Sta=6140,6350
XS Rating Curve= 0 ,0
Exp/Cntr=0.5,0.3

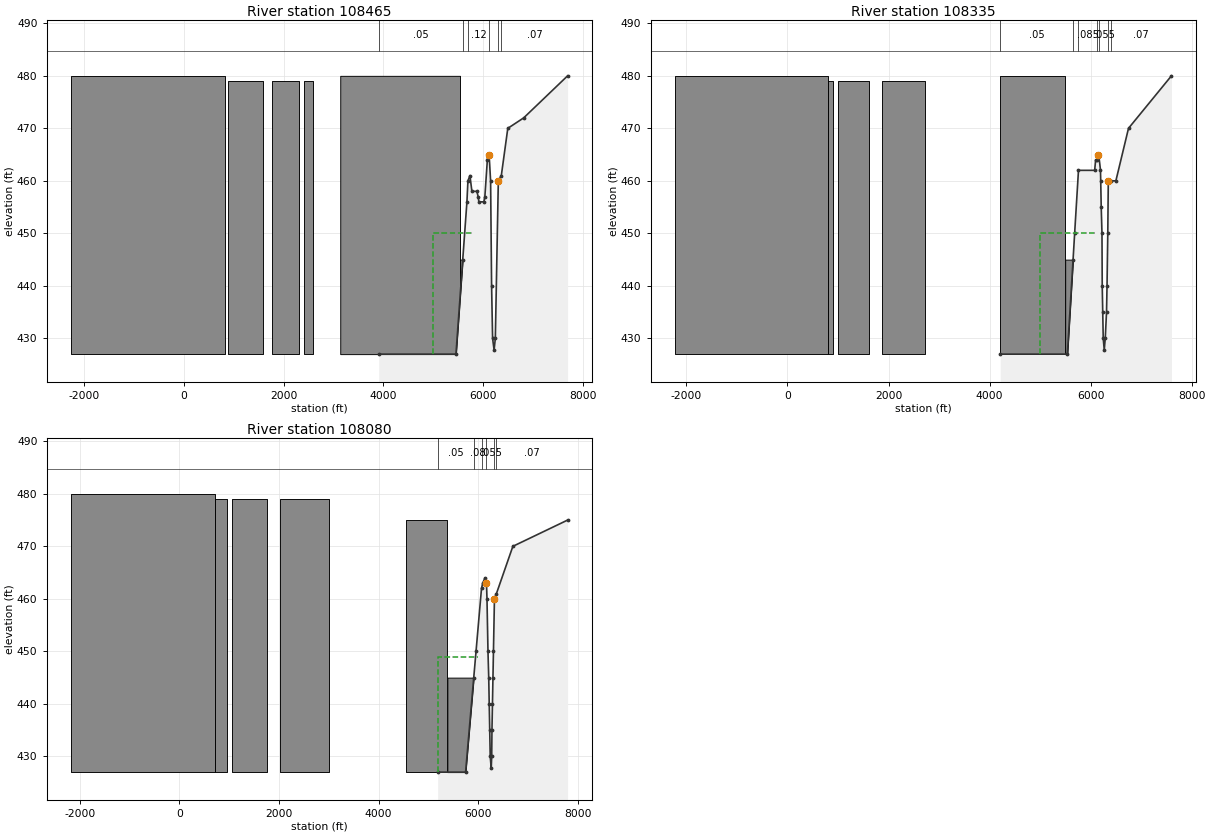
Type RM Length L Ch R = 1 ,108465  ,136,122,108
BEGIN DESCRIPTION:
This cross section corresponds to cross section 108465 of the non-georeferenced CDC model which was the source of this model.
Proposed lake on LOB.  Flow limited in LOB for continuity.   LOB realigned.  LOB from 2001 aerial topo.  ROB of X-SECTION BASED ON 1991 AND 2001 SURVEY DATA
END DESCRIPTION:
XS GIS Cut Line= 6
2400263.141973266974138.898653352400580.078811376972621.64750715
 2400588.0344891 6972583.5618077     2400900.346     6972124.416
     2401013.618     6971411.467      2401012.78      6970517.18
#Sta/Elev= 25
    3910     427    5460     427    5596     445    5680     456    5700     460
    5740     461    5780     458    5880     458    5905     457    5920     456
    6020     456    6040     457    6090     464    6100     465    6125     465
    6155     460    6175     440    6195     430    6225   427.8    6250     430
    6310     460    6370     461    6500     470    6820     472    7700     480
#Mann= 6 ,-1,0
    3910     .05       0    5596     .08       0    5700     .12       0
    6125    .055       0    6310     .12       0    6370     .07       0
#XS Ineff= 1 ,-1
    5000    5800     450
Permanent Ineff=
       T
#Block Obstruct= 6 ,-1
   -2255     825     480     885    1595     479    1760    2315     479
    2415    2600     479    3138    5541     480    5541    6125     445
Bank Sta=6125,6310
XS Rating Curve= 0 ,0
Exp/Cntr=0.5,0.3

Type RM Length L Ch R = 1 ,108335  ,307,261,256
BEGIN DESCRIPTION:
This cross section corresponds to cross section 108335 of the non-georeferenced CDC model which was the source of this model.
Proposed fill & lake on LOB.  Flow limited in LOB for continuity.  LOB realigned.  LOB from 2001 aerial topo.  ROB of X-SECTION BASED ON 1991 AND 2001 SURVEY DATA
END DESCRIPTION:
XS GIS Cut Line= 5
     2400502.696     6974008.023     2400683.251     6972737.189
     2401030.473     6972105.245     2401120.751     6971389.967
2401045.613043426970730.83696045
#Sta/Elev= 27
    4211     427    5540     427    5653     445    5684     450    5760     462
    6080     462    6100     464    6130     464    6145     465    6160     465
    6195   462.1    6200     460    6210     455    6225     450    6230     440
    6240     435    6250     430    6270   427.8    6290     430    6315     435
    6325     440    6340     450    6350     460    6400     460    6500     460
    6750     470    7600     480
#Mann= 7 ,-1,0
    4211     .05       0    5653     .08       0    5760    .085       0
    6130     .12       0    6160    .055       0    6350     .12       0
    6400     .07       0
#XS Ineff= 1 ,-1
    5000    6100     450
Permanent Ineff=
       T
#Block Obstruct= 6 ,-1
   -2220     795     480     795     905     479    1005    1620     479
    1880    2730     479    4211    5497     480    5497    6145     445
Bank Sta=6145,6350
XS Rating Curve= 0 ,0
Exp/Cntr=0.5,0.3

Type RM Length L Ch R = 1 ,108080  ,0,0,0
BEGIN DESCRIPTION:
This cross section corresponds to cross section 108080 of the non-georeferenced CDC model which was the source of this model.
Proposed lake on LOB.  LOB realigned.  LOB from 2001 aerial topo.  ROB of X-SECTION BASED ON 1991 AND 2001 SURVEY DATA
END DESCRIPTION:
XS GIS Cut Line= 5
2400913.062849776972979.251943732400927.601286056972950.74520995
      2401259.64     6972299.689     2401349.918     6971716.356
      2401028.27      6970500.29
#Sta/Elev= 24
    5189     427    5750     427    5914     445    5960     450    6070     462
    6095     463    6140     464    6170     463    6180     460    6200     450
    6215     445    6225     440    6235     435    6245     430    6265   427.7
    6275     430    6280     435    6290     440    6300     445    6310     450
    6330     460    6370     461    6700     470    7800     475
#Mann= 6 ,-1,0
    5189     .05       0    5914     .08       0    6070     .12       0
    6170    .055       0    6330     .12       0    6370     .07       0
#XS Ineff= 2 , 0
            6000     449
Permanent Ineff=
       T       F
#Block Obstruct= 6 ,-1
   -2170     715     480     715     965     479    1060    1755     479
    2020    3005     479    4544    5384     475    5384    6170     445
Bank Sta=6170,6330
XS Rating Curve= 0 ,0
Exp/Cntr=0.3,0.1

River Reach=West Fork       ,wf3d
Reach XY= 30
      2401546.94      6972159.85      2401942.48      6972487.32
      2402295.53       6972489.5      2402042.69      6971394.87
      2402697.66      6970746.65      2403563.16      6970808.94
      2403830.51      6970190.26      2404298.63      6970630.22
      2404487.36      6971453.34      2405408.25      6970852.89
      2406453.87      6971217.74      2406862.66      6971685.13
       2406809.8      6973584.94      2407771.12      6973753.18
      2407994.65      6974095.37      2408069.42      6975076.27
      2408856.59      6974754.96      2408993.75      6975650.26
      2409531.11       6975545.9      2409797.89       6975854.3
      2409842.31       6976283.3      2409287.51      6976949.93
      2409480.59      6977127.45       2409859.3       6977048.8
      2410039.92       6977413.3      2410229.47      6978577.08
      2410027.07      6979946.39      2410204.66      6980041.97
      2410954.98      6979798.04      2410888.67      6980304.42