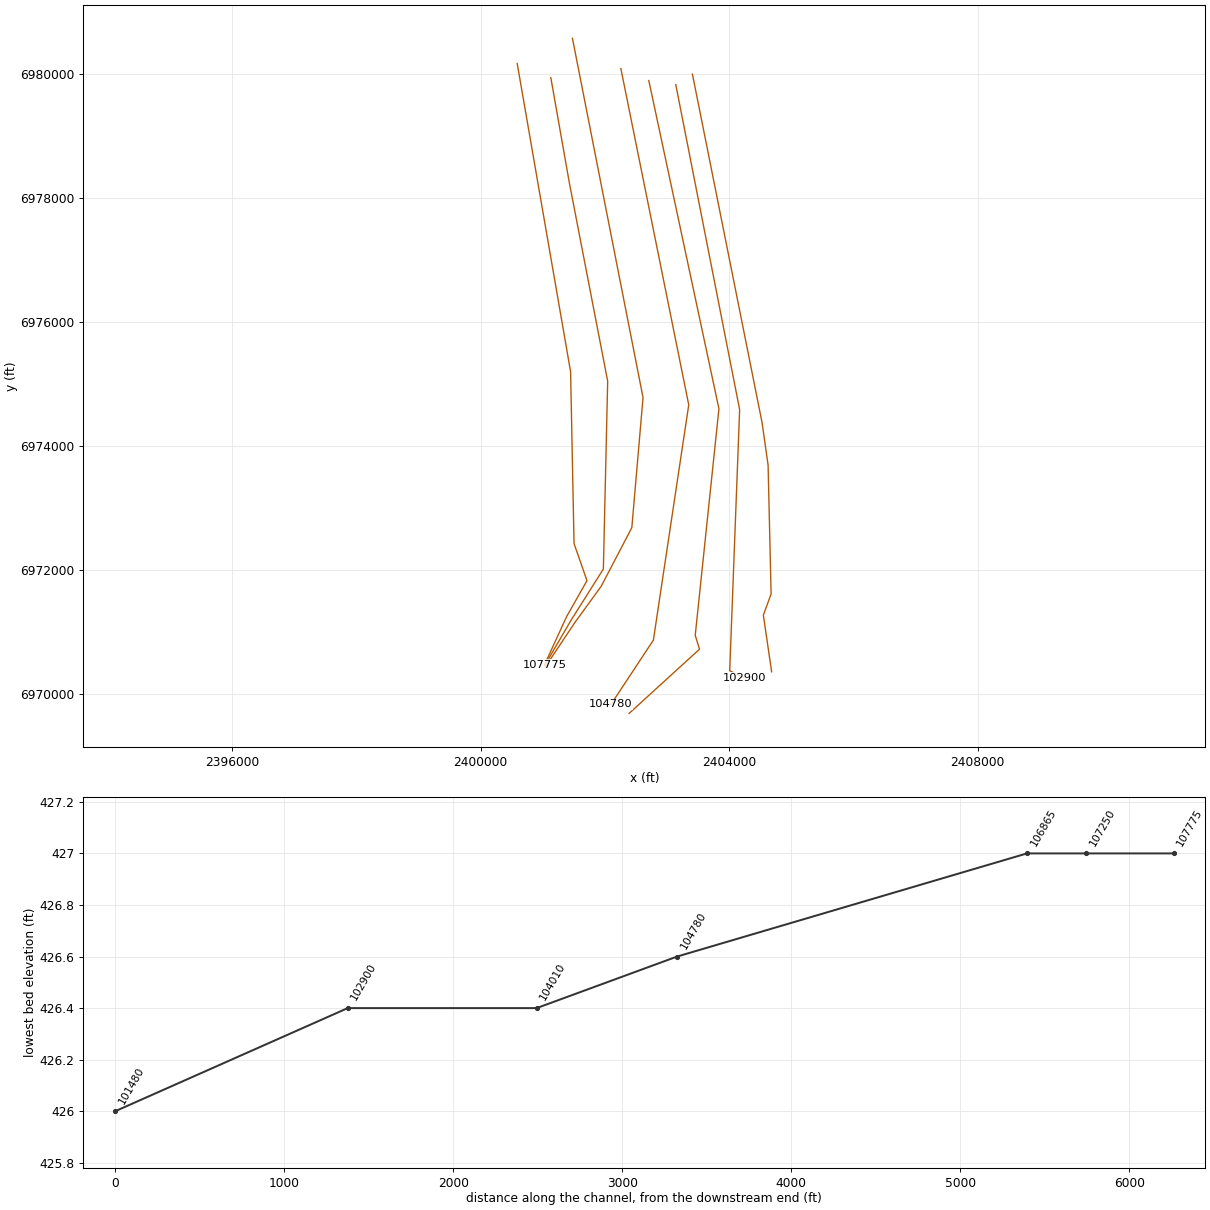
HEC-RAS study CDC_Consolidated_Model.prj: Upper Trinity CDC Consolidated Model

--- CDC_Consolidated_Model.g12 (geometry) --- (continued)

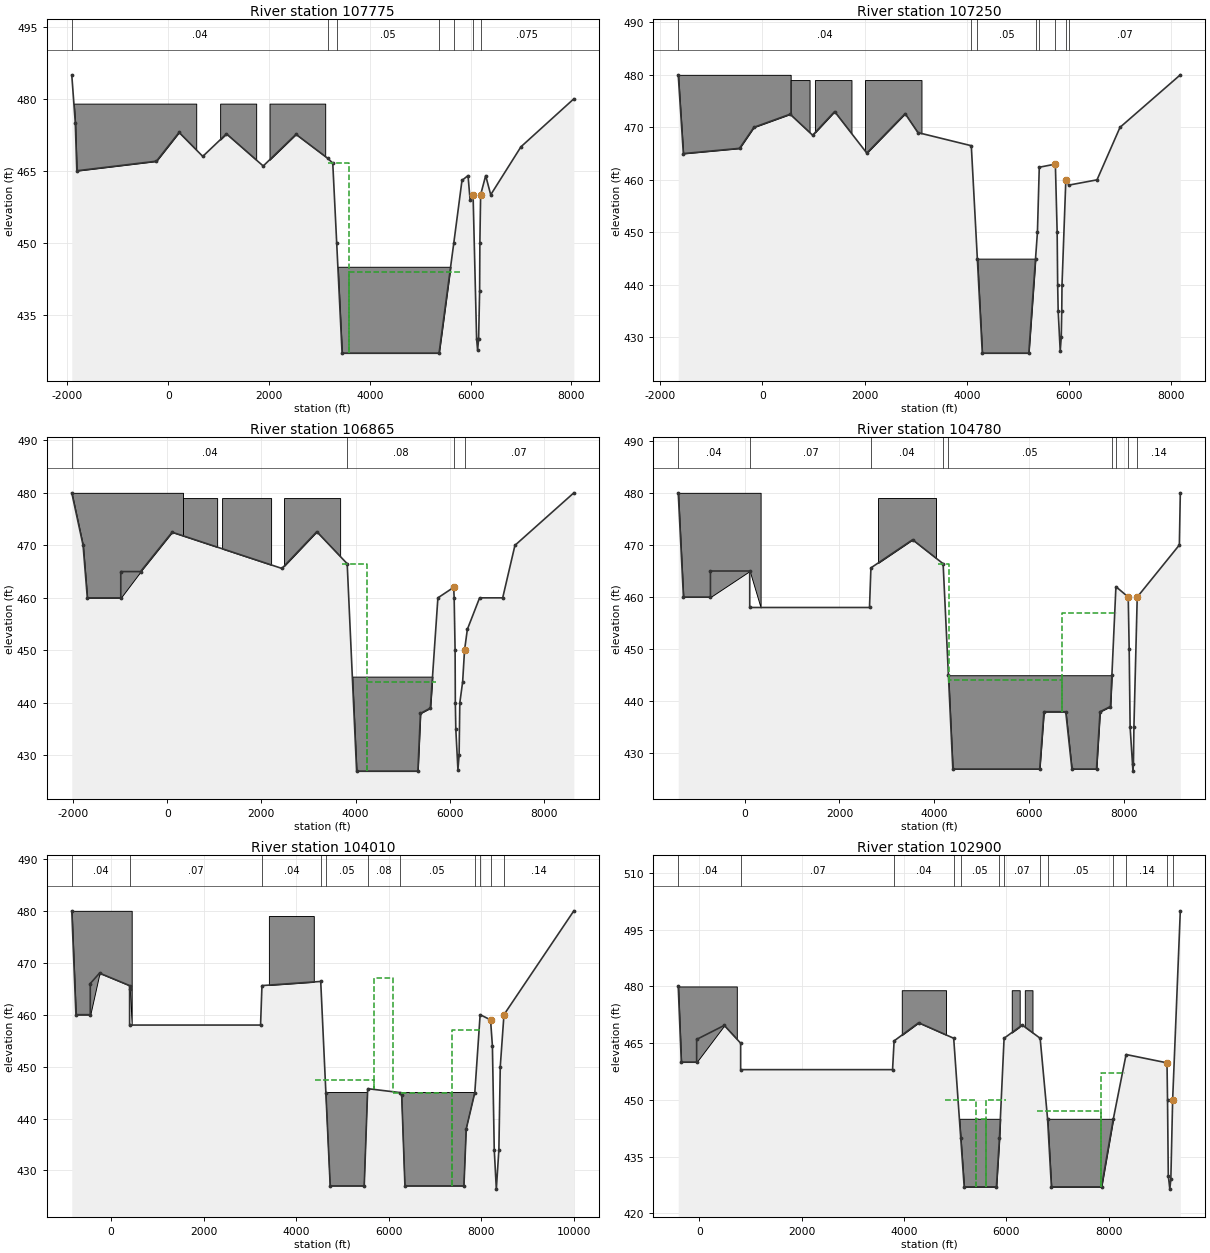
Type RM Length L Ch R = 1 ,107775  ,521,516,123
BEGIN DESCRIPTION:
This cross section corresponds to cross section 107775 of the non-georeferenced CDC model which was the source of this model.
Proposed fill & lake on LOB.  LOB from 2001 aerial topo.  ROB of X-SECTION BASED ON 1991 AND 2001 SURVEY DATA
END DESCRIPTION:
XS GIS Cut Line= 6
2400587.20206217 6980170.9974937      2401447.14     6975202.467
     2401502.696     6972431.634     2401711.029     6971834.411
      2401384.64     6971258.023      2401027.75      6970479.63
#Sta/Elev= 30
   -1915     485   -1845     475   -1815     465    -235     467     215     473
     685     468    1155   472.7    1885     466    2535   472.6    3165   467.6
    3265   466.6    3343     450    3450     427    5375     427    5668     450
    5830     463    5950     464    5990     459    6040     460    6050     460
    6120     430    6140   427.6    6160     430    6180     440    6185     450
    6200     460    6300     464    6400     460    7000     470    8050     480
#Mann= 7 ,-1,0
   -1915     .04       0    3165     .08       0    3343     .05       0
    5375     .08       0    5668     .12       0    6040    .055       0
    6200    .075       0
#XS Ineff= 2 ,-1
    3170    3580   466.6    3580    5800     444
Permanent Ineff=
       T       T
#Block Obstruct= 4 ,-1
   -1915     555     479    1030    1745     479    2010    3115     479
    3115    6050     445
Bank Sta=6050,6200
XS Rating Curve= 0 ,0
Exp/Cntr=0.3,0.1

Type RM Length L Ch R = 1 ,107250  ,489,352,110
BEGIN DESCRIPTION:
This cross section corresponds to cross section 107250 of the non-georeferenced CDC model which was the source of this model.
Proposed fill & lake on LOB.  LOB from 2001 aerial topo.  ROB OF X-SECTION BASED ON 1991 AND 2001 SURVEY DATA
END DESCRIPTION:
XS GIS Cut Line= 6
2401129.036748146979940.51921208     2401426.307     6978251.078
     2402044.362     6975049.689     2401974.918     6972021.911
     2401454.085     6971195.523      2401029.07      6970466.69
#Sta/Elev= 30
   -1645     480   -1545     465    -445     466    -165     470     545   472.5
     985   468.5    1415     473    2045   465.1    2795   472.6    3045     469
    4090   466.5    4208     445    4305     427    5215     427    5347     445
    5384     450    5420   462.4    5735     463    5770     450    5780     440
    5790     435    5830   427.4    5850     430    5860     435    5865     440
    5940     460    6000     459    6550     460    7000     470    8180     480
#Mann= 8 ,-1,0
   -1645     .04       0    4090     .08       0    4208     .05       0
    5347     .08       0    5420     .12       0    5735    .055       0
    5940     .15       0    6000     .07       0
#XS Ineff= 1 ,-1
    4000    5400     444
Permanent Ineff=
       T
#Block Obstruct= 5 ,-1
   -1915     555     480     555     925     479    1030    1745     479
    2010    3115     479    3115    5735     445
Bank Sta=5735,5940
XS Rating Curve= 0 ,0
Exp/Cntr=0.3,0.1

Type RM Length L Ch R = 1 ,106865  ,710,2070,1320
BEGIN DESCRIPTION:
This cross section corresponds to cross section 106865 of the non-georeferenced CDC model which was the source of this model.
Proposed fill & lake on LOB.  LOB from 2001 aerial topo. ROB OF X-SECTION BASED ON 1991 AND 2001 SURVEY DATA
END DESCRIPTION:
XS GIS Cut Line= 6
2401476.807675366980575.83576698     2402613.807       6974785.8
     2402433.251     6972688.578     2401940.196     6971744.134
     2401516.585       6971160.8      2401038.14      6970442.49
#Sta/Elev= 30
   -2025     480   -1785     470   -1695     460    -985     460    -985     465
    -565     465     105   472.5    2435   465.6    3175   472.6    3820   466.5
    4020     427    5320     427    5375     438    5585     439    5745     460
    6080     462    6090     460    6110     450    6115     440    6125     435
    6170   427.3    6195     430    6210     440    6270     444    6310     450
    6370     454    6630     460    7120     460    7380     470    8630     480
#Mann= 4 ,-1,0
   -2025     .04       0    3820     .08       0    6080     .05       0
    6310     .07       0
#XS Ineff= 2 ,-1
    3700    4250   466.5    4250    5700     444
Permanent Ineff=
       T       T
#Block Obstruct= 5 ,-1
   -2025     335     480     335    1060     479    1165    2205     479
    2480    3670     479    3670    6080     445
Bank Sta=6080,6310
XS Rating Curve= 0 ,0
Exp/Cntr=0.3,0.1

Type RM Length L Ch R = 1 ,104780  ,610,831,885
BEGIN DESCRIPTION:
This cross section corresponds to cross section 104780 of the non-georeferenced CDC model which was the source of this model.
Proposed fill & lake on LOB.  LOB from 2001 aerial topo. ROB OF X-SECTION BASED ON 1991 AND 2001 SURVEY DATA
END DESCRIPTION:
XS GIS Cut Line= 5
2402256.848760756980087.92074455      2402509.64     6978834.411
     2403349.918     6974667.745     2402780.473     6970876.078
      2402097.09      6969839.57
#Sta/Elev= 30
   -1405     480   -1295     460    -725     460    -725     465     105     465
     105     458    2635     458    2665   465.6    3545     471    4190   466.4
    4302     445    4395     427    6230     427    6320     438    6780     438
    6910     427    7430     427    7505     438    7725     439    7755     445
    7840     462    8100     460    8120     450    8140     435    8200   426.6
    8210     428    8220     435    8290     460    9180     470    9200     480
#Mann= 9 ,-1,0
   -1405     .04       0     105     .07       0    2665     .04       0
    4190     .08       0    4302     .05       0    7755     .08       0
    7840     .14       0    8100    .057       0    8290     .14       0
#XS Ineff= 3 ,-1
    4090    4310   466.4    4310    6700     444    6700    7870     457
Permanent Ineff=
       T       T       T
#Block Obstruct= 3 ,-1
   -1405     335     480    2815    4040     479    4040    8100     445
Bank Sta=8100,8290
XS Rating Curve= 0 ,0
Exp/Cntr=0.3,0.1

Type RM Length L Ch R = 1 ,104010  ,443,1118,1027
BEGIN DESCRIPTION:
This cross section corresponds to cross section 104010 of the non-georeferenced CDC model which was the source of this model.
Proposed fill & lake on LOB.  LOB from 2001 aerial topo. ROB OF X-SECTION BASED ON 1991 AND 2001 SURVEY DATA
END DESCRIPTION:
XS GIS Cut Line= 6
  2402706.558179 6979895.4893627     2402891.585     6979028.856
     2403836.029     6974605.245     2403454.085     6970952.467
     2403523.529     6970730.245 2402389.9418359 6969695.2313528
#Sta/Elev= 30
    -850     480    -760     460    -450     460    -450     466    -250     468
     400   465.6     400     465     400     458    3230     458    3260   465.6
    4530   466.4    4641     445    4735     427    5470     427    5545  445.75
    6237     445    6280   444.5    6350     427    7625     427    7675     438
    7860     445    7975     460    8200     459    8240     454    8280     434
    8325   426.4    8380     434    8410     450    8490     460   10000     480
#Mann= 11 ,-1,0
    -850     .04       0     400     .07       0    3260     .04       0
    4530     .08       0    4641     .05       0    5545     .08       0
    6237     .05       0    7860     .08       0    7975     .14       0
    8200    .057       0    8490     .14       0
#XS Ineff= 4 ,-1
    4400    5675   447.4    5675    6085     467    6085    7365     445
    7365    8000     457
Permanent Ineff=
       T       T       T       T
#Block Obstruct= 3 ,-1
    -850     445     480    3410    4380     479    4380    8200     445
Bank Sta=8200,8490
XS Rating Curve= 0 ,0
Exp/Cntr=0.3,0.1

Type RM Length L Ch R = 1 ,102900  ,485,1376,727
BEGIN DESCRIPTION:
This cross section corresponds to cross section 102900 of the non-georeferenced CDC model which was the source of this model.
Proposed fill & lake on LOB.  LOB from 2001 aerial topo. ROB OF X-SECTION BASED ON 1991 AND 2001 SURVEY DATA
END DESCRIPTION:
XS GIS Cut Line= 5
  2403140.720865 6979830.9963793     2403280.473     6979119.134
     2404169.362     6974591.356      2404009.64     6970383.023
     2404245.751     6970264.967
#Sta/Elev= 30
    -415     480    -355     460     -55     460     -55     466     485   469.7
     805     465     805     458    3775     458    3805   465.6    4285   470.4
    4970   466.3    5107     440    5175     427    5805     427    5865     440
    5955   466.3    6310   469.8    6660   466.3    6805     445    6880     427
    7860     427    8091     445    8340     462    9140   459.8    9150     450
    9165     430    9195   426.4    9215     429    9250     450    9400     500
#Mann= 13 ,-1,0
    -415     .04       0     805     .07       0    3805     .04       0
    4970     .08       0    5107     .05       0    5865     .08       0
    5955     .07       0    6660     .08       0    6805     .05       0
    8091     .08       0    8340     .14       0    9140    .055       0
    9250     .14       0
#XS Ineff= 5 ,-1
    4800    5400     450    5400    5600     445    5600    6000     450
    6600    7850     447    7850    8310     457
Permanent Ineff=
       T       T       T       T       T
#Block Obstruct= 6 ,-1
    -415     730     480    3955    4820     479    4820    6105     445
    6105    6260     479    6360    6510     479    6510    8420     445
Bank Sta=9140,9250
XS Rating Curve= 0 ,0
Exp/Cntr=0.3,0.1

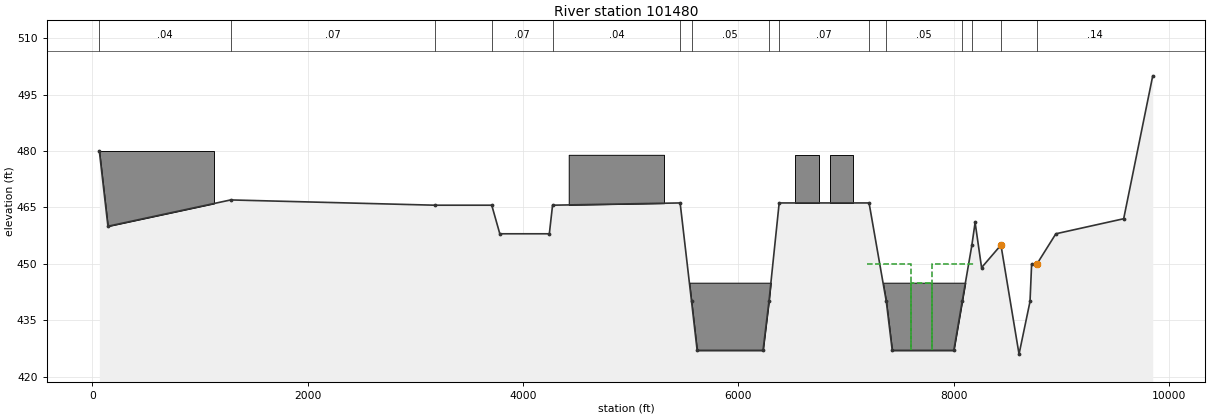
Type RM Length L Ch R = 1 ,101480  ,749,1508,1558
BEGIN DESCRIPTION:
This cross section corresponds to cross section 101480 of the non-georeferenced CDC model which was the source of this model.
Proposed fill & lake on LOB.  LOB from 2001 aerial topo.  ROB OF X-SECTION BASED ON 1991 AND 2001 SURVEY DATA
END DESCRIPTION:
XS GIS Cut Line= 6
2403408.778260246979999.87063879     2404530.473     6974383.023
     2404627.696     6973695.523     2404676.307     6971619.134
     2404551.307     6971278.856       2404684.8      6970365.12
#Sta/Elev= 30
      65     480     145     460    1285     467    3180   465.6    3710   465.6
    3785     458    4245     458    4275   465.6    5460   466.2    5566     440
    5618     427    6230     427    6285     440    6380   466.2    7215   466.2
    7375     440    7430     427    8002     427    8080     440    8170     455
    8200     461    8260     449    8440     455    8608     426    8710     440
    8725     450    8775     450    8950     458    9580     462    9850     500
#Mann= 15 ,-1,0
      65     .04       0    1285     .07       0    3180     .04       0
    3710     .07       0    4275     .04       0    5460     .08       0
    5566     .05       0    6285     .08       0    6380     .07       0
    7215     .08       0    7375     .05       0    8080     .08       0
    8170     .14       0    8440    .055       0    8775     .14       0
#XS Ineff= 4 ,-1
    5400    6400   449.3    7200    7600     450    7600    7800     445
    7800    8200     450
Permanent Ineff=
       T       T       T       T
#Block Obstruct= 6 ,-1
      65    1130     480    4425    5310     479    5310    6530     445
    6530    6750     479    6850    7065     479    7065    8440     445
Bank Sta=8440,8775
XS Rating Curve= 0 ,0
Exp/Cntr=0.3,0.1