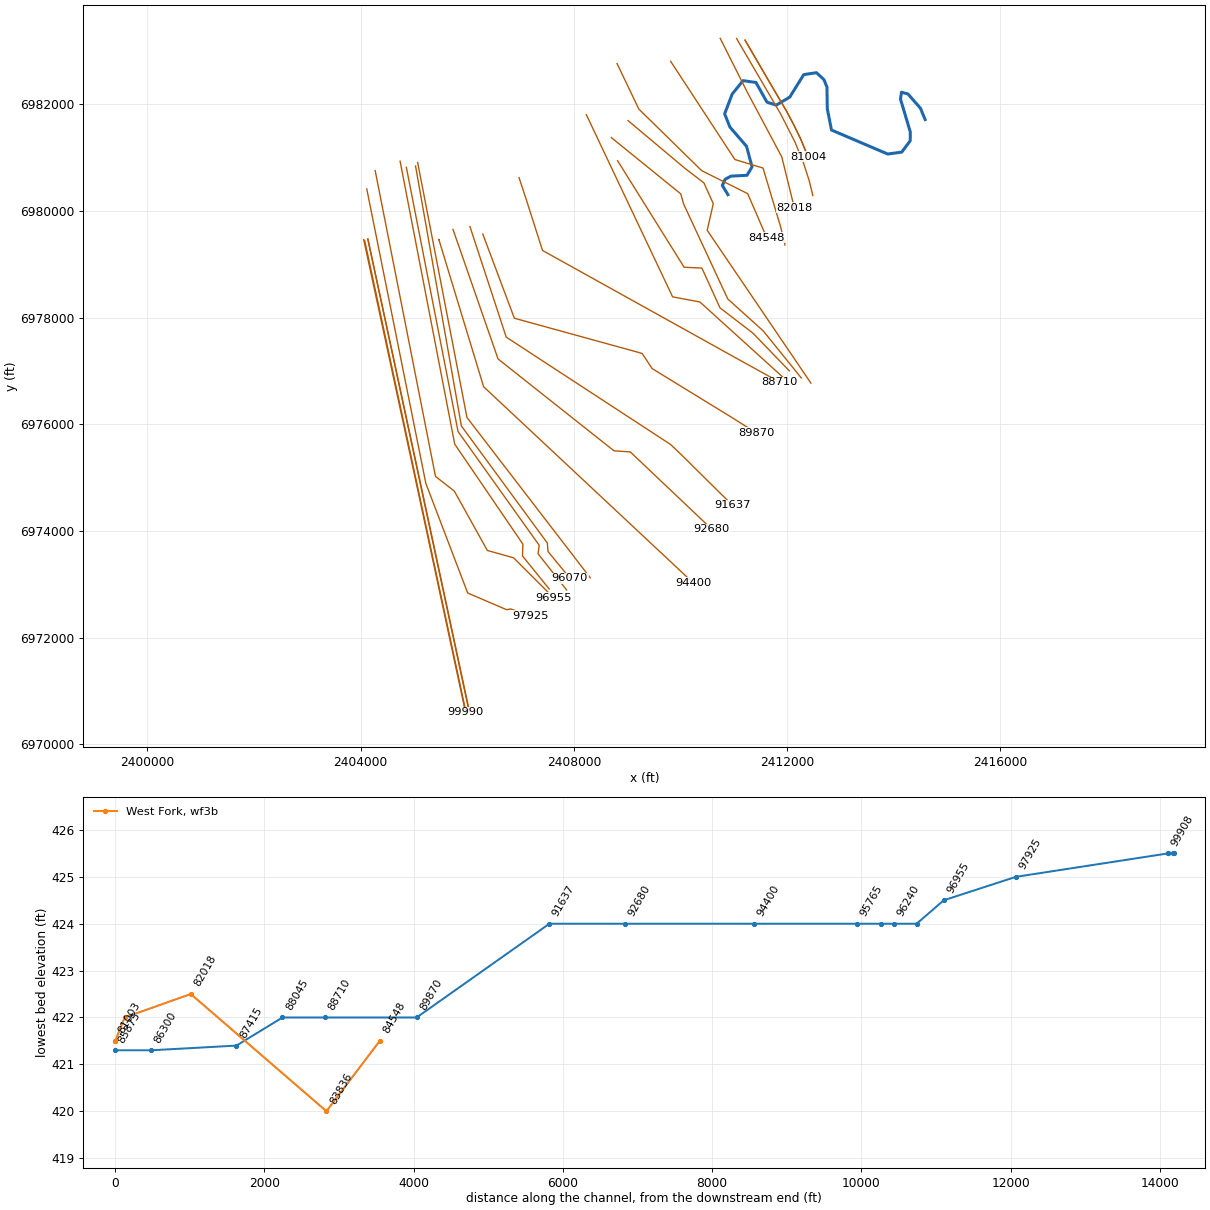
HEC-RAS study CDC_Consolidated_Model.prj: Upper Trinity CDC Consolidated Model

--- CDC_Consolidated_Model.g12 (geometry) --- (continued)

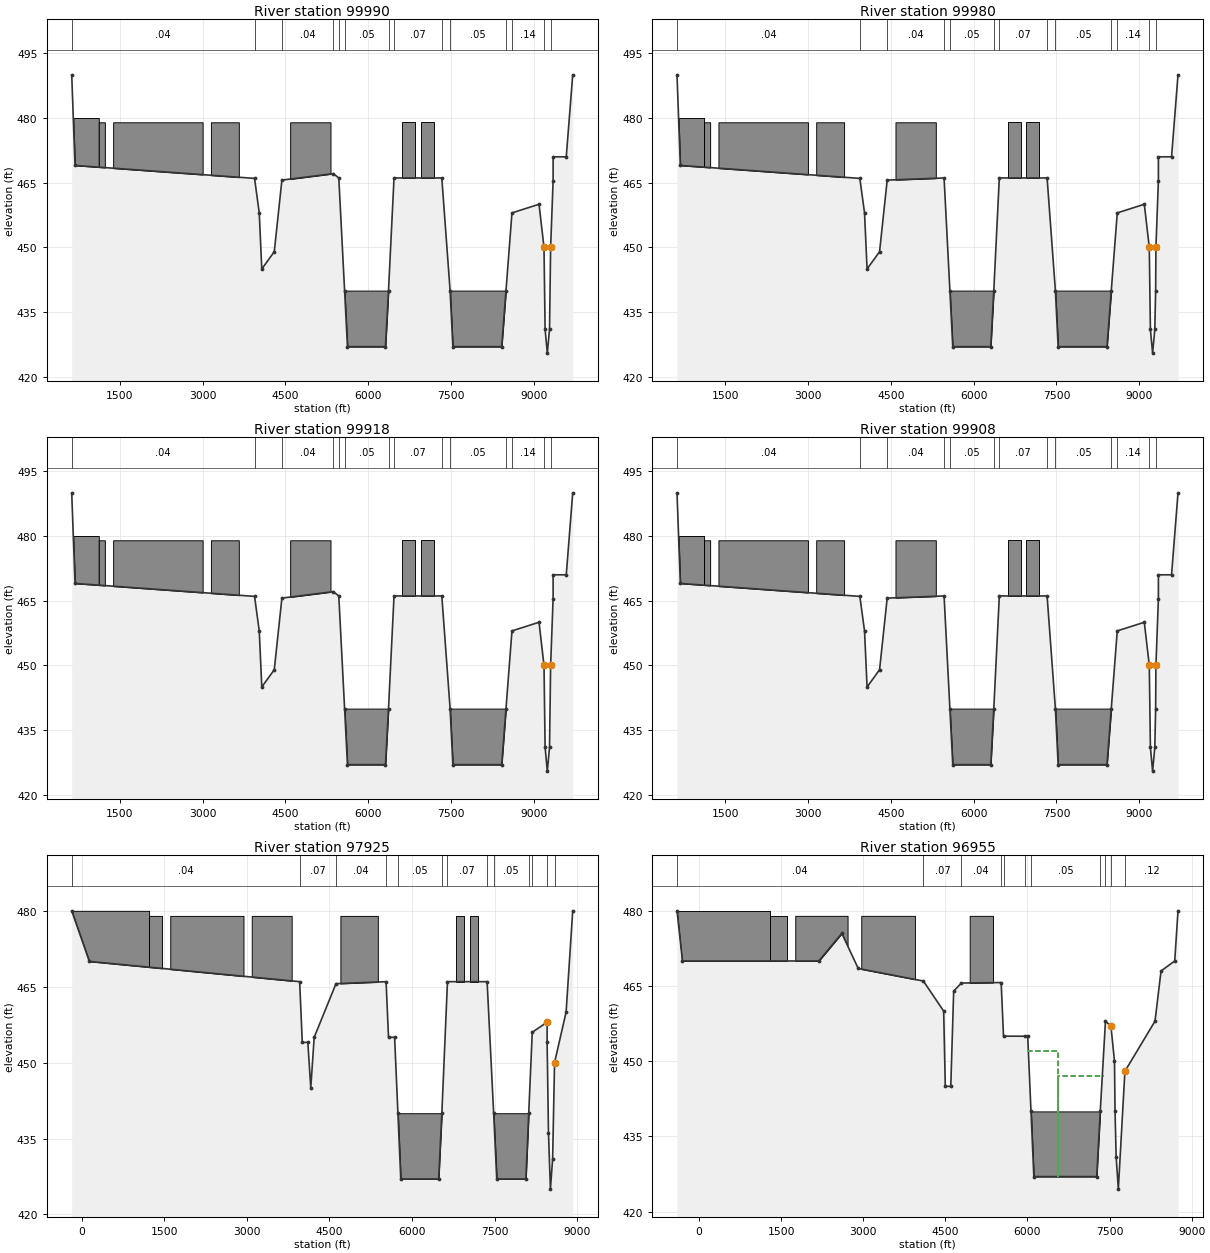
Type RM Length L Ch R = 1 ,99990   ,10,10,10
BEGIN DESCRIPTION:
This cross section corresponds to cross section 99990 of the non-georeferenced CDC model which was the source of this model.
U/S of Bridge #1 & #2.  Proposed fill & lake on LOB.  Repeat of 99980.  X-SECTION BASED ON 1991 AND 2001 SURVEY DATA.
END DESCRIPTION:
XS GIS Cut Line= 3
     2404059.717     6979460.783     2405081.398     6974727.361
     2405969.484     6970594.128
#Sta/Elev= 30
     630     490     690     469    3940     466    4025     458    4071     445
    4297     449    4435   465.6    5365   467.1    5465   466.1    5570     440
    5622     427    6310     427    6365     440    6465   466.1    7330   466.1
    7480     440    7530     427    8414     427    8492     440    8600     458
    9090     460    9180     450    9200     431    9240   425.5    9280     431
    9300     450    9345   465.5    9345     471    9583     471    9700     490
#Mann= 14 ,-1,0
     630     .04       0    3940     .07       0    4435     .04       0
    5365     .07       0    5465     .08       0    5570     .05       0
    6365     .08       0    6465     .07       0    7330     .08       0
    7480     .05       0    8492     .08       0    8600     .14       0
    9180    .055       0    9300     .14       0
#XS Ineff= 2 ,-1
    5200    6800     449    7200    8800     447
Permanent Ineff=
       T       T
#Block Obstruct= 9 ,-1
     630    1120     480    1120    1230     479    1380    3000     479
    3150    3655     479    4585    5315     479    5315    6615     440
    6615    6850     479    6950    7180     479    7180    8920     440
Bank Sta=9180,9300
XS Rating Curve= 0 ,0
Exp/Cntr=0.4,0.2

Type RM Length L Ch R = 1 ,99980   ,60,60,60
BEGIN DESCRIPTION:
This cross section corresponds to cross section 99980 of the non-georeferenced CDC model which was the source of this model.
U/S face of Bridge #1 & #2.  Proposed fill & lake on LOB.  Repeat of 99980.  X-SECTION BASED ON 1991 AND 2001 SURVEY DATA.
END DESCRIPTION:
XS GIS Cut Line= 4
   2404078.04193  6979445.353264     2404113.807     6979278.856
      2405947.14     6970744.134 2405982.9050698 6970577.6367361
#Sta/Elev= 30
     630     490     690     469    3940     466    4025     458    4071     445
    4297     449    4435   465.6    5465   466.1    5570     440    5622     427
    6310     427    6365     440    6465   466.1    7330   466.1    7480     440
    7530     427    8414     427    8492     440    8600     458    9090     460
    9180     450    9200     431    9240   425.5    9280     431    9295     440
    9300     450    9345   465.5    9345     471    9583     471    9700     490
#Mann= 13 ,-1,0
     630     .04       0    3940     .07       0    4435     .04       0
    5465     .08       0    5570     .05       0    6365     .08       0
    6465     .07       0    7330     .08       0    7480     .05       0
    8492     .08       0    8600     .14       0    9180    .055       0
    9300     .14       0
#XS Ineff= 2 ,-1
    5200    6800     449    7200    8800     447
Permanent Ineff=
       T       T
#Block Obstruct= 9 ,-1
     630    1120     480    1120    1230     479    1380    3000     479
    3150    3655     479    4585    5315     479    5315    6615     440
    6615    6850     479    6950    7180     479    7180    8730     440
Bank Sta=9180,9300
XS Rating Curve= 0 ,0
Exp/Cntr=0.4,0.2

Type RM Length L Ch R = 1 ,99918   ,6,6,6
BEGIN DESCRIPTION:
This cross section corresponds to cross section 99918 of the non-georeferenced CDC model which was the source of this model.
D/S face of Bridge #1 & #2.  Proposed fill & lake on LOB.  Repeat of 99980
END DESCRIPTION:
XS GIS Cut Line= 4
  2404136.934075 6979468.0216169     2404174.942     6979290.844
     2406001.331     6970776.955 2406039.3389245 6970599.7773831
#Sta/Elev= 30
     630     490     690     469    3940     466    4025     458    4071     445
    4297     449    4435   465.6    5365   467.1    5465   466.1    5570     440
    5622     427    6310     427    6365     440    6465   466.1    7330   466.1
    7480     440    7530     427    8414     427    8492     440    8600     458
    9090     460    9180     450    9200     431    9240   425.5    9280     431
    9300     450    9345   465.5    9345     471    9583     471    9700     490
#Mann= 14 ,-1,0
     630     .04       0    3940     .07       0    4435     .04       0
    5365     .07       0    5465     .08       0    5570     .05       0
    6365     .08       0    6465     .07       0    7330     .08       0
    7480     .05       0    8492     .08       0    8600     .14       0
    9180    .055       0    9300     .14       0
#XS Ineff= 2 ,-1
    5200    6800     449    7200    8800     447
Permanent Ineff=
       T       T
#Block Obstruct= 9 ,-1
     630    1120     480    1120    1230     479    1380    3000     479
    3150    3655     479    4585    5315     479    5315    6615     440
    6615    6850     479    6950    7180     479    7180    8730     440
Bank Sta=9180,9300
XS Rating Curve= 0 ,0
Exp/Cntr=0.4,0.2

Type RM Length L Ch R = 1 ,99908   ,257,2038,2145
BEGIN DESCRIPTION:
This cross section corresponds to cross section 99908 of the non-georeferenced CDC model which was the source of this model.
D/S of Bridge #1 & #2.  Proposed fill & lake on LOB.  Repeat of 99980
END DESCRIPTION:
XS GIS Cut Line= 4
      2404138.47     6979473.908     2405155.749     6974749.724
     2406008.784     6970770.542     2406048.819     6970605.992
#Sta/Elev= 30
     630     490     690     469    3940     466    4025     458    4071     445
    4297     449    4435   465.6    5465   466.1    5570     440    5622     427
    6310     427    6365     440    6465   466.1    7330   466.1    7480     440
    7530     427    8414     427    8492     440    8600     458    9090     460
    9180     450    9200     431    9240   425.5    9280     431    9295     440
    9300     450    9345   465.5    9345     471    9583     471    9700     490
#Mann= 13 ,-1,0
     630     .04       0    3940     .07       0    4435     .04       0
    5465     .08       0    5570     .05       0    6365     .08       0
    6465     .07       0    7330     .08       0    7480     .05       0
    8492     .08       0    8600     .14       0    9180    .055       0
    9300     .14       0
#XS Ineff= 2 ,-1
    5200    6800     449    7200    8800     447
Permanent Ineff=
       T       T
#Block Obstruct= 9 ,-1
     630    1120     480    1120    1230     479    1380    3000     479
    3150    3655     479    4585    5315     479    5315    6615     440
    6615    6850     479    6950    7180     479    7180    8730     440
Bank Sta=9180,9300
XS Rating Curve= 0 ,0
Exp/Cntr=0.4,0.2

Type RM Length L Ch R = 1 ,97925   ,688,967,818
BEGIN DESCRIPTION:
This cross section corresponds to cross section 97925 of the non-georeferenced CDC model which was the source of this model.
Proposed fill & lake on LOB.  453.7 for continuity around island.  LOB from 2001 aerial topo.  ROB OF X-SECTION BASED ON 1991 AND 2001 SURVEY DATA
END DESCRIPTION:
XS GIS Cut Line= 6
  2404117.181044  6980411.203205     2405224.918     6974889.967
      2406009.64     6972834.411     2406738.807     6972521.911
     2406815.196       6972535.8     2407190.196     6972403.856
#Sta/Elev= 30
    -180     480     140     470    3960     466    4008     454    4109     454
    4162     445    4224     455    4620   465.6    5530     466    5574     455
    5685     455    5745     440    5797     427    6485     427    6543     440
    6645     466    7365     466    7484     440    7540     427    8069     427
    8121     440    8185     456    8455     458    8455     454    8480     436
    8515     425    8555     431    8590     450    8800     460    8920     480
#Mann= 13 ,-1,0
    -180     .04       0    3960     .07       0    4620     .04       0
    5530     .08       0    5745     .05       0    6543     .08       0
    6645     .07       0    7365     .08       0    7484     .05       0
    8121     .08       0    8185     .14       0    8455     .06       0
    8590     .12       0
#XS Ineff= 2 ,-1
    5500    6700   452.3    7200    8200     446
Permanent Ineff=
       T       T
#Block Obstruct= 9 ,-1
    -180    1225     480    1225    1460     479    1610    2940     479
    3090    3815     479    4700    5380     479    5380    6795     440
    6795    6950     479    7050    7200     479    7200    8305     440
Bank Sta=8455,8590
XS Rating Curve= 0 ,0
Exp/Cntr=0.3,0.1

Type RM Length L Ch R = 1 ,96955   ,538,363,108
BEGIN DESCRIPTION:
This cross section corresponds to cross section 96955 of the non-georeferenced CDC model which was the source of this model.
Proposed fill & lake on LOB. Far LOB realigned for hydraulics.  LOB from 2001 aerial topo.  ROB OF X-SECTION BASED ON 1991 AND 2001 SURVEY DATA
END DESCRIPTION:
XS GIS Cut Line= 6
  2404274.836498 6980755.8538621 2405405.4730169 6975021.9109336
 2405759.6399595 6974744.1339302 2406377.6961381 6973633.0229634
 2406870.7509263 6973494.1341336 2407617.8842745 6972748.3311632
#Sta/Elev= 30
    -400     480    -300     470    2190     470    2610   475.5    2910   468.5
    4100     466    4470     460    4500     445    4600     445    4653     464
    4795   465.6    5520   465.7    5563     455    5950     455    6005     455
    6065     440    6117     427    7265     427    7330     440    7425     458
    7525     457    7590     450    7600     440    7620     431    7660   424.5
    7780     448    8330     458    8440     468    8690     470    8750     480
#Mann= 11 ,-1,0
    -400     .04       0    4100     .07       0    4795     .04       0
    5520     .09       0    5563     .12       0    5950     .09       0
    6065     .05       0    7330     .09       0    7425     .14       0
    7525     .06       0    7780     .12       0
#XS Ineff= 2 ,-1
    6000    6550     452    6550    7400     447
Permanent Ineff=
       T       T
#Block Obstruct= 6 ,-1
    -400    1300     480    1300    1610     479    1760    2715     479
    2965    3945     479    4945    5370     479    5370    7525     440
Bank Sta=7525,7780
XS Rating Curve= 0 ,0
Exp/Cntr=0.3,0.1

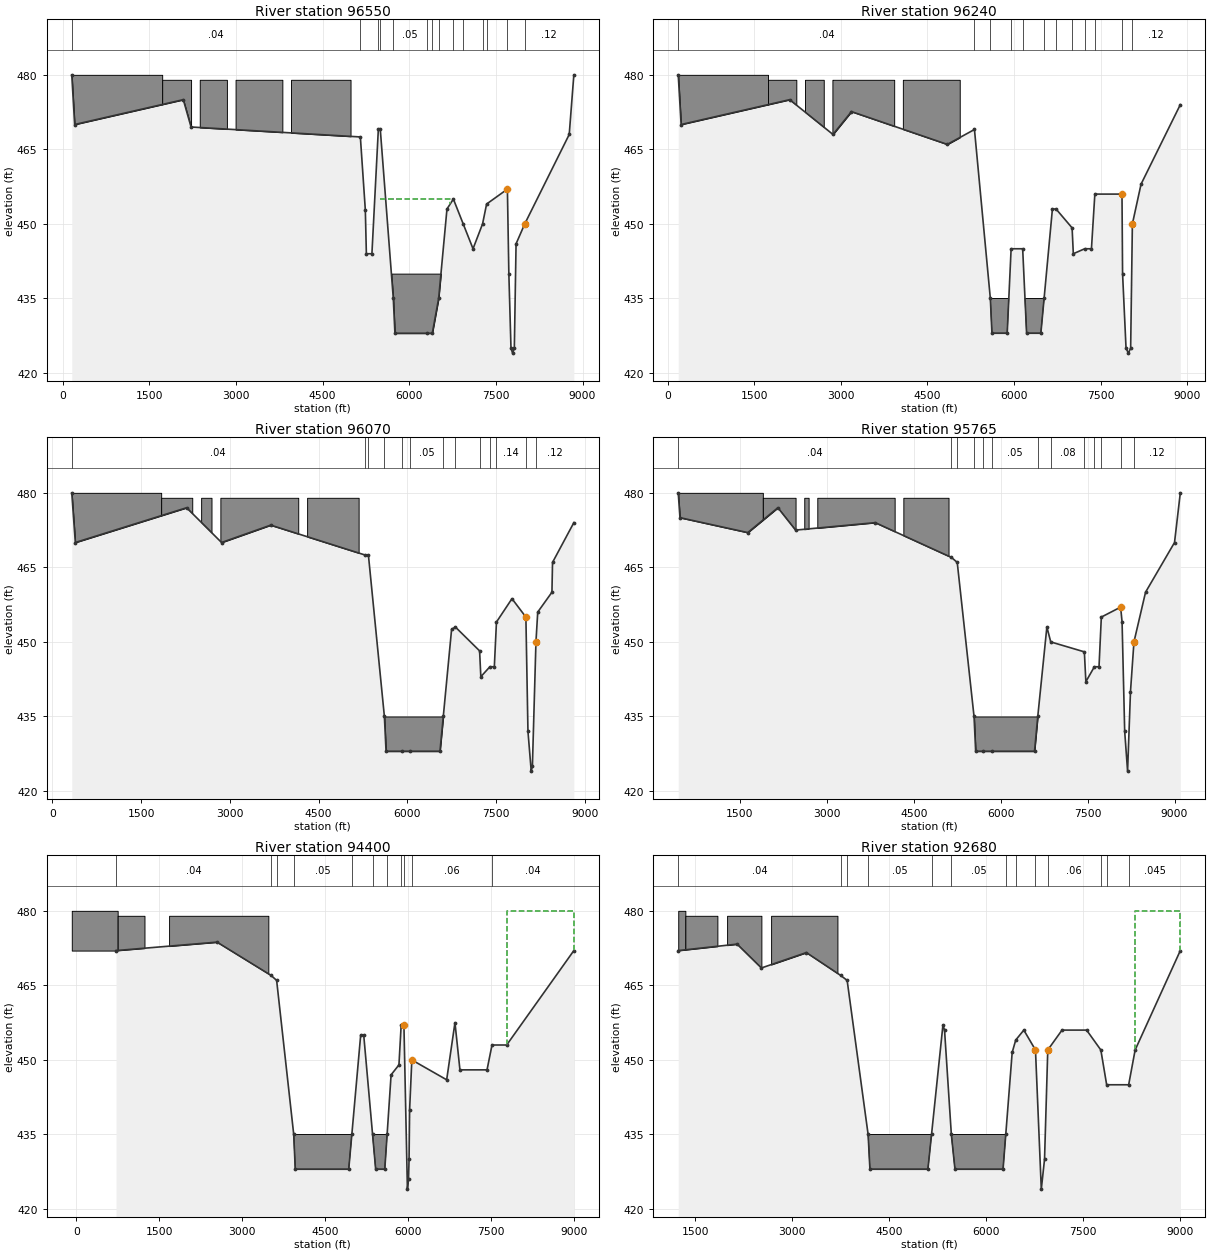
Type RM Length L Ch R = 1 ,96550   ,199,301,272
BEGIN DESCRIPTION:
This cross section corresponds to cross section 96550 of the non-georeferenced CDC model which was the source of this model.
Proposed fill & lake overflow structure on LOB.  Flow limited in LOB due to sewer ridge.  LOB from 2001 aerial topo.  ROB OF X-SECTION BASED ON 1991 AND 2001 SURVEY DATA
END DESCRIPTION:
XS GIS Cut Line= 6
  2404742.167568 6980931.7807449     2405030.473     6979438.578
     2405766.585     6975626.078     2407044.362     6973751.078
     2407037.418     6973528.856     2407537.418       6972910.8
#Sta/Elev= 30
     160     480     210     470    2090     475    2225   469.5    5155   467.5
    5241   452.8    5259     444    5355     444    5466     469    5500     469
    5725     435    5753     428    6300     428    6400     428    6510     435
    6654     453    6765     455    6935     450    7105     445    7270     450
    7340     454    7700     457    7725     440    7762     425    7790     424
    7820     425    7850     446    8000     450    8770     468    8850     480
#Mann= 14 ,-1,0
     160     .04       0    5155     .07       0    5466     .04       0
    5500     .09       0    5725     .05       0    6300     .12       0
    6400     .05       0    6510     .09       0    6765     .08       0
    6935    .025       0    7270     .08       0    7340     .14       0
    7700     .06       0    8000     .12       0
#XS Ineff= 1 ,-1
    5500    6700     455
Permanent Ineff=
       T
#Block Obstruct= 6 ,-1
     160    1725     480    1725    2225     479    2375    2845     479
    2995    3805     479    3955    4985     479    4985    7700     440
Bank Sta=7700,8000
XS Rating Curve= 0 ,0
Exp/Cntr=0.3,0.1

Type RM Length L Ch R = 1 ,96240   ,166,176,166
BEGIN DESCRIPTION:
This cross section corresponds to cross section 96240 of the non-georeferenced CDC model which was the source of this model.
Proposed fill, lake, & lake overflow structure on LOB.  Flow limited in LOB due to sewer ridge.  LOB from 2001 aerial topo.  ROB OF X-SECTION BASED ON 1991 AND 2001 SURVEY DATA
END DESCRIPTION:
XS GIS Cut Line= 6
  2404859.079752 6980817.8589874 2405829.0850306 6975862.1891087
 2407349.9179469 6973730.2452099 2407329.0849833 6973570.5230884
 2407766.5850926 6973014.9671129 2407865.2499215 6972891.2121111
#Sta/Elev= 30
     185     480     235     470    2115     475    2865     468    3185   472.6
    4845     466    5315     469    5590     435    5618     428    5882     428
    5950     445    6150     445    6218     428    6465     428    6521     435
    6665     453    6728     453    7006   449.2    7027     444    7224     445
    7341     445    7400     456    7870     456    7880     440    7940     425
    7980     424    8020     425    8050     450    8200     458    8880     474
#Mann= 12 ,-1,0
     185     .04       0    5315     .09       0    5590     .05       0
    5950     .12       0    6150     .05       0    6521     .09       0
    6728     .08       0    7006     .06       0    7224     .08       0
    7400     .14       0    7870     .06       0    8050     .12       0
#XS Ineff= 1 ,-1
    5400    6700   452.5
Permanent Ineff=
       T
#Block Obstruct= 6 ,-1
     185    1740     480    1740    2230     479    2380    2705     479
    2855    3925     479    4075    5060     479    5060    7870     435
Bank Sta=7870,8050
XS Rating Curve= 0 ,0
Exp/Cntr=0.3,0.1

Type RM Length L Ch R = 1 ,96070   ,213,317,333
BEGIN DESCRIPTION:
This cross section corresponds to cross section 96070 of the non-georeferenced CDC model which was the source of this model.
Proposed fill, lake, & lake outfall on LOB.  Flow limited in LOB due to sewer ridge.  LOB from 2001 aerial topo.  ROB OF X-SECTION BASED ON 1991 AND 2001 SURVEY DATA
END DESCRIPTION:
XS GIS Cut Line= 6
2405031.750791536980841.999992842405891.432054886975967.22326714
     2405891.585     6975966.356     2407502.696     6973771.911
     2407516.585     6973612.189     2407926.307     6973112.189
#Sta/Elev= 30
     330     480     390     470    2270     477    2860     470    3690   473.5
    5280   467.5    5340   467.5    5610     435    5638     428    5900     428
    6050     428    6549     428    6605     435    6745   452.5    6809     453
    7218   448.2    7239     443    7392     445    7467     445    7503     454
    7765   458.7    8000     455    8035     432    8090     424    8110     425
    8170     450    8200     456    8440     460    8450     466    8810     474
#Mann= 13 ,-1,0
     330     .04       0    5280     .07       0    5340     .09       0
    5610     .05       0    5900     .12       0    6050     .05       0
    6605     .09       0    6809     .08       0    7218     .06       0
    7392     .08       0    7503     .14       0    8000     .06       0
    8170     .12       0
#XS Ineff= 1 ,-1
    5300    6800   452.5
Permanent Ineff=
       T
#Block Obstruct= 6 ,-1
     330    1840     480    1840    2365     479    2515    2690     479
    2840    4155     479    4305    5175     479    5175    8000     435
Bank Sta=8000,8170
XS Rating Curve= 0 ,0
Exp/Cntr=0.3,0.1

Type RM Length L Ch R = 1 ,95765   ,885,1380,1203
BEGIN DESCRIPTION:
This cross section corresponds to cross section 95765 of the non-georeferenced CDC model which was the source of this model.
Proposed fill, lake, & lake outfall on LOB.  Flow limited in LOB due to sewer ridge.  LOB from 2001 aerial topo.  ROB OF X-SECTION BASED ON 1991 AND 2001
END DESCRIPTION:
XS GIS Cut Line= 4
2405071.277154396980909.225099432405966.020859676976279.89915477
     2405995.751     6976126.078     2408308.251     6973119.134
#Sta/Elev= 30
     435     480     465     475    1635     472    2155     477    2460   472.5
    3835     474    5150     467    5250     466    5540     435    5568     428
    5700     428    5850     428    6584     428    6640     435    6797     453
    6864     450    7444     448    7470     442    7617     445    7697     445
    7737     455    8070     457    8095     454    8140     432    8190     424
    8240     440    8300     450    8500     460    9000     470    9100     480
#Mann= 13 ,-1,0
     435     .04       0    5150     .07       0    5250     .09       0
    5540     .05       0    5700     .12       0    5850     .05       0
    6640     .09       0    6864     .08       0    7444     .06       0
    7617     .08       0    7737     .14       0    8070     .06       0
    8300     .12       0
#XS Ineff= 1 ,-1
    5300    6800     452
Permanent Ineff=
       T
#Block Obstruct= 6 ,-1
     435    1895     480    1895    2460     479    2610    2685     479
    2835    4170     479    4320    5100     479    5100    8070     435
Bank Sta=8070,8300
XS Rating Curve= 0 ,0
Exp/Cntr=0.3,0.1

Type RM Length L Ch R = 1 ,94400   ,679,1731,1006
BEGIN DESCRIPTION:
This cross section corresponds to cross section 94400 of the non-georeferenced CDC model which was the source of this model.
Proposed fill & lakes (2) on LOB.  Flow limited in LOB due to sewer ridge.  LOB from 2001 aerial topo.  ROB OF X-SECTION BASED ON 1991 AND 2001 SURVEY DATA  SET COE NON-EFFECTIVE FLOW LIMIT AT FILL LINE IN ROB
END DESCRIPTION:
XS GIS Cut Line= 6
       2405469.6      6979463.07 2405467.9728919  6979466.356113
  2406308.251067 6976702.4669557 2409901.0682527 6973340.6249538
 2410193.4239009 6973067.06427792410242.166687916973021.45506925
#Sta/Elev= 30
     720     472    2548   473.7    3525     467    3625     466    3934     435
    3962     428    4929     428    4985     435    5145     455    5200     455
    5360     435    5416     428    5581     428    5623     435    5695     447
    5837     449    5877     457    5927     457    5990     424    6010     426
    6020     430    6030     440    6070     450    6700     446    6850   457.5
    6940     448    7430     448    7520     453    7785     453    9000     472
#Mann= 11 ,-1,0
     720     .04       0    3525     .07       0    3625     .09       0
    3934     .05       0    4985     .09       0    5360     .05       0
    5623     .09       0    5877     .14       0    5927    .055       0
    6070     .06       0    7520     .04       0
#XS Ineff= 2 ,-1
    3600    5800   447.5    7785    9000     480
Permanent Ineff=
       T       F
#Block Obstruct= 4 ,-1
     -80     750     480     750    1235     479    1680    3475     479
    3475    5927     435
Bank Sta=5927,6070
XS Rating Curve= 0 ,0
Exp/Cntr=0.3,0.1

Type RM Length L Ch R = 1 ,92680   ,555,1016,585
BEGIN DESCRIPTION:
This cross section corresponds to cross section 92680 of the non-georeferenced CDC model which was the source of this model.
Proposed fill & lakes (2) on LOB.  Flow limited in LOB due to sewer ridge.  LOB from 2001 aerial topo.  ROB OF X-SECTION BASED ON 1991 AND 2001 SURVEY DATA  SET COE NON-EFFECTIVE FLOW LIMIT AT FILL LINE IN ROB
END DESCRIPTION:
XS GIS Cut Line= 6
  2405734.098521 6979652.6362441     2406579.085       6977223.3
     2408752.696     6975501.078     2409058.251     6975480.245
     2410080.402      6974511.272410586.963188996974031.06196018
#Sta/Elev= 30
    1240     472    2150   473.3    2525   468.5    3220   471.6    3750     467
    3850     466    4174     435    4202     428    5098     428    5154     435
    5330     457    5355     456    5460     435    5516     428    6259     428
    6301     435    6400   451.5    6455     454    6580     456    6760     452
    6850     424    6900     430    6950     452    7170     456    7550     456
    7770     452    7860     445    8200     445    8300     452    8998     472
#Mann= 13 ,-1,0
    1240     .04       0    3750     .07       0    3850     .09       0
    4174     .05       0    5154     .09       0    5460     .05       0
    6301     .09       0    6455     .14       0    6760    .055       0
    6950     .06       0    7770    .055       0    7860    .035       0
    8200    .045       0
#XS Ineff= 2 ,-1
    4000    6500     449    8300    8998     480
Permanent Ineff=
       T       F
#Block Obstruct= 5 ,-1
    1240    1350     480    1350    1845     479    1995    2525     479
    2675    3700     479    3700    6760     435
Bank Sta=6760,6950
XS Rating Curve= 0 ,0
Exp/Cntr=0.3,0.1

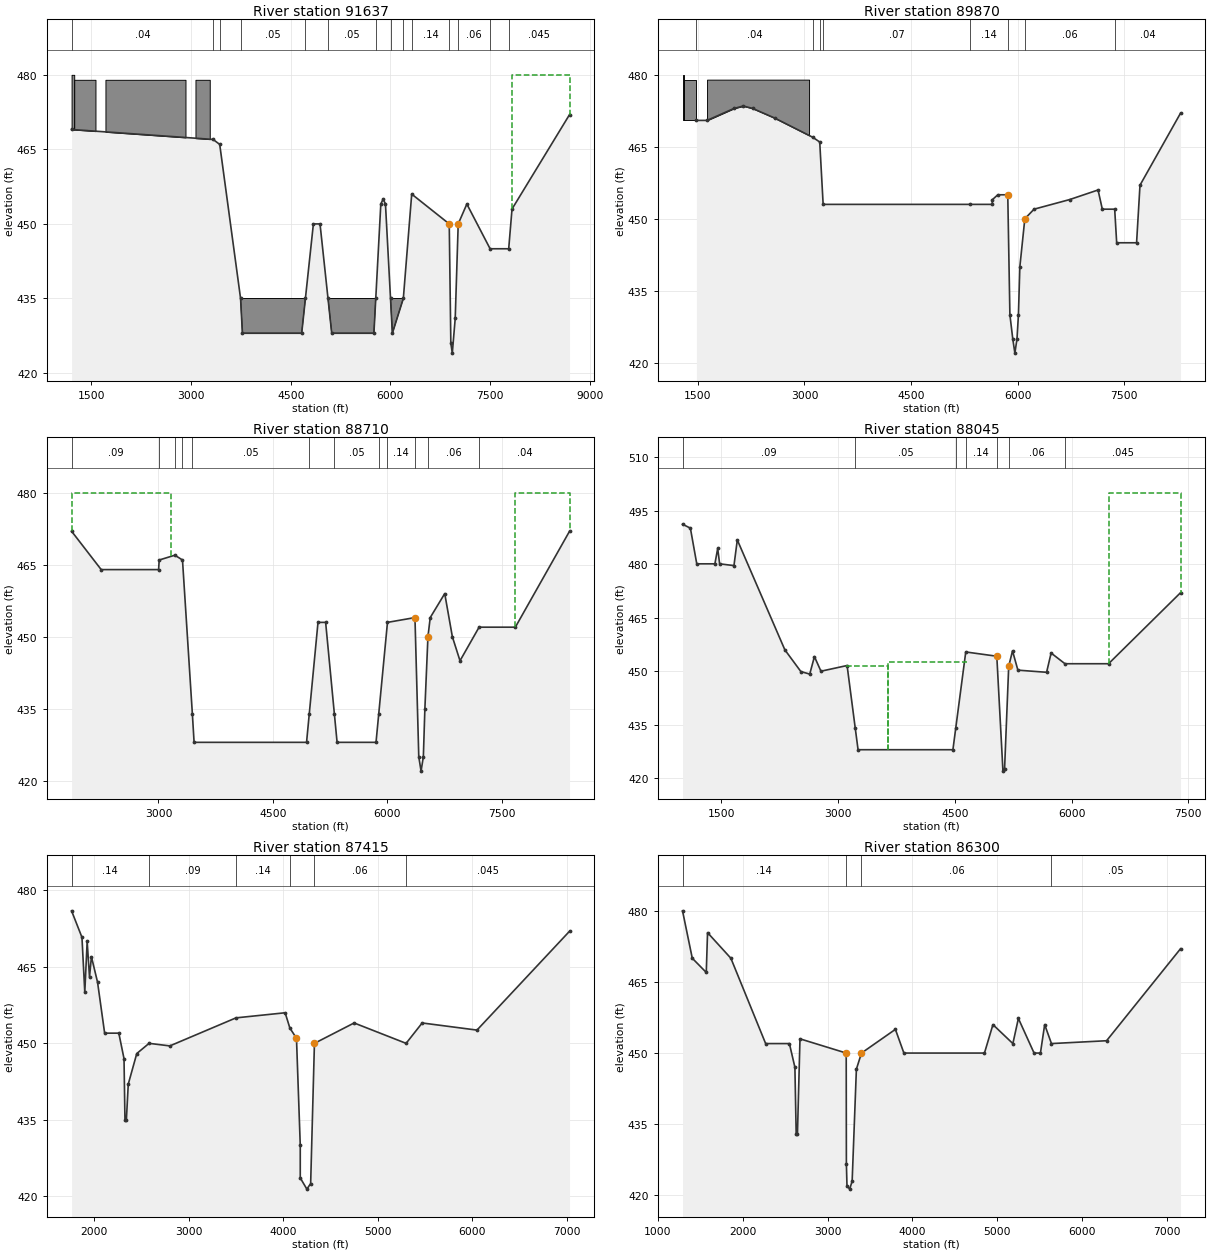
Type RM Length L Ch R = 1 ,91637   ,856,1779,1148
BEGIN DESCRIPTION:
This cross section corresponds to cross section 91637 of the non-georeferenced CDC model which was the source of this model.
Proposed fill & lakes (3) on LOB.  Flow limited in LOB due to sewer ridge.  LOB from 2001 aerial topo.  ROB OF X-SECTION BASED ON 1991 AND 2001 SURVEY DATA  SET COE NON-EFFECTIVE FLOW LIMIT AT FILL LINE IN ROB
END DESCRIPTION:
XS GIS Cut Line= 6
2406051.617410346979706.46123584 2406731.8620964 6977633.0231655
 2409815.1961528 6975619.1341486 2410079.0358482 6975366.1579486
 2410266.5617199 6975179.0769579     2410978.678     6974476.078
#Sta/Elev= 30
    1200     469    3330     467    3430     466    3744     435    3772     428
    4664     428    4720     435    4840     450    4940     450    5060     435
    5116     428    5751     428    5779     435    5855     454    5890     455
    5925     454    6001     435    6029     428    6194     435    6320     456
    6885     450    6909     426    6931     424    6975     431    7020     450
    7150     454    7500     445    7780     445    7830     453    8696     472
#Mann= 14 ,-1,0
    1200     .04       0    3330     .07       0    3430     .09       0
    3744     .05       0    4720     .09       0    5060     .05       0
    5779     .09       0    6001     .05       0    6194     .09       0
    6320     .14       0    6885    .055       0    7020     .06       0
    7500    .035       0    7780    .045       0
#XS Ineff= 2 ,-1
    3500    6300     452    7830    8696     480
Permanent Ineff=
       T       F
#Block Obstruct= 5 ,-1
    1200    1240     480    1240    1560     479    1710    2915     479
    3065    3280     479    3280    6885     435
Bank Sta=6885,7020
XS Rating Curve= 0 ,0
Exp/Cntr=0.3,0.1

Type RM Length L Ch R = 1 ,89870   ,1028,1230,1023
BEGIN DESCRIPTION:
This cross section corresponds to cross section 89870 of the non-georeferenced CDC model which was the source of this model.
Proposed fill on LOB.  LOB ground lowered to 457 and 453  LOB along sewer ridge.  Existing pond added to ROB.  LOB from 2001 aerial topo.  ROB OF X-SECTION BASED ON 1991 AND 2001 SURVEY DATA  SET COE NON-EFFECTIVE FLOW LIMIT AT FILL LINE IN ROB
END DESCRIPTION:
XS GIS Cut Line= 6
 2406292.59418366979565.97784169      2406884.64     6977987.189
     2409280.473     6977327.467     2409467.973     6977042.745
     2410940.196     6976139.967     2411422.949     6975835.105
#Sta/Elev= 30
    1480   470.5    1630   470.5    2010     473    2140   473.5    2270     473
    2580     471    3115     467    3215     466    3263     453    5325     453
    5640     453    5645     454    5720     455    5860     455    5890     430
    5930     425    5960     422    5990     425    6010     430    6030     440
    6100     450    6230     452    6730     454    7130     456    7190     452
    7364     452    7392     445    7672     445    7720     457    8290     472
#Mann= 8 ,-1,0
    1480     .04       0    3115     .07       0    3215     .09       0
    3263     .07       0    5325     .14       0    5860    .055       0
    6100     .06       0    7364     .04       0
#XS Ineff= 2 , 0
                            7720
Permanent Ineff=
       F       F
#Block Obstruct= 3 ,-1
    1285    1305     480    1305    1480     479    1630    3065     479
Bank Sta=5860,6100
XS Rating Curve= 0 ,0
Exp/Cntr=0.3,0.1

Type RM Length L Ch R = 1 ,88710   ,1110,568,444
BEGIN DESCRIPTION:
This cross section corresponds to cross section 88710 of the non-georeferenced CDC model which was the source of this model.
Proposed fill and lakes (2) in LOB.  Flow limited in LOB due to sewer ridge and D/S high ground.  LOB from 2001 aerial topo. - realigned for hydraulics - ROB OF X-SECTION BASED ON 1991 AND 2001 SURVEY DATA  SET COE NON-EFFECTIVE FLOW LIMIT AT FILL LINE IN ROB
END DESCRIPTION:
XS GIS Cut Line= 6
2406972.58467316 6980623.2162594     2407069.565     6980329.208
     2407099.918     6980237.189     2407412.418     6979258.023
     2411174.952     6977166.217     2411861.317     6976787.796
#Sta/Elev= 30
    1862     472    2250     464    3002     464    3010     466    3215     467
    3315     466    3444     434    3467     428    4940     428    4976     434
    5090     453    5190     453    5304     434    5340     428    5850     428
    5886     434    6000     453    6360     454    6410     425    6440     422
    6470     425    6490     435    6530     450    6560     454    6750     459
    6850     450    6950     445    7200     452    7675     452    8385     472
#Mann= 12 ,-1,0
    1862     .09       0    3010     .04       0    3215     .07       0
    3315     .09       0    3444     .05       0    4976     .09       0
    5304     .05       0    5886     .09       0    6000     .14       0
    6360    .055       0    6530     .06       0    7200     .04       0
#XS Ineff= 4 ,-1
    1862    3160     480    3315    5100     453    5190    6000     453
    7675    8385     480
Permanent Ineff=
       F       T       T       F
#Block Obstruct= 2 , 0
            6360     434
Bank Sta=6360,6530
XS Rating Curve= 0 ,0
Exp/Cntr=0.3,0.1

Type RM Length L Ch R = 1 ,88045   ,377,617,157
BEGIN DESCRIPTION:
This cross section corresponds to cross section 88045 of the non-georeferenced CDC model which was the source of this model.
Proposed lakes (2) in LOB.  Flow limited in LOB due to sewer ridge and D/S high ground.  CHANNEL BASED ON 1991 SURVEY DATA  SET COE NON-EFFECTIVE FLOW LIMIT AT FILL LINE IN ROB
END DESCRIPTION:
XS GIS Cut Line= 6
  2408234.632056 6981803.1598383 2409022.6114519 6980139.1474183
 2409395.8925295 6979350.9380367 2409852.1491629 6978387.5771026
 2410363.9699897 6978291.61108712411920.069879886976881.40313752
#Sta/Elev= 30
    1000   491.2    1101   490.1    1183   480.1    1416   480.1    1452   484.4
    1477   480.1    1661   479.6    1704   486.8    2315     456    2521   449.9
    2635   449.2    2695   454.1    2779     450    3115   451.6    3220     434
    3256     428    4475     428    4511     434    4640   455.4    5039   454.2
    5118     422    5139   422.7    5192   451.4    5241   455.7    5310   450.3
    5679   449.7    5737   455.1    5915   452.1    6475   452.1    7400     472
#Mann= 7 ,-1,0
    1000     .09       0    3220     .05       0    4511     .09       0
    4640     .14       0    5039    .055       0    5192     .06       0
    5915    .045       0
#XS Ineff= 3 ,-1
    3100    3640   451.5    3640    4650   452.5    6475    7400     500
Permanent Ineff=
       T       T       F
#Block Obstruct= 2 , 0
            5039     434
Bank Sta=5039,5192
XS Rating Curve= 0 ,0
Exp/Cntr=0.3,0.1

Type RM Length L Ch R = 1 ,87415   ,688,1145,205
BEGIN DESCRIPTION:
This cross section corresponds to cross section 87415 of the non-georeferenced CDC model which was the source of this model.
Transition to proposed lake in LOB.  LOB from 2001 aerial topo. Far ROB from 1991 aerial topo - realigned for hydraulics -  ROB OF X-SECTION BASED ON 1991 AND 2001 SURVEY DATA  SET COE NON-EFFECTIVE FLOW LIMIT AT FILL LINE IN ROB
END DESCRIPTION:
XS GIS Cut Line= 6
  2408820.035741 6980940.3439786 2410068.0693348 6978942.9368842
 2410401.4026576 6978927.3119155 2410739.9443033  6978182.520098
     2411359.031     6977706.677      2412040.02     6977000.947
#Sta/Elev= 30
    1760     476    1870   470.8    1900     460    1925     470    1950     463
    1970     467    2035     462    2110     452    2260     452    2315     447
    2325     435    2340     435    2360     442    2450     448    2580     450
    2800   449.5    3500     455    4020     456    4070     453    4140     451
    4180     430    4180   423.6    4250   421.4    4290   422.5    4330     450
    4750     454    5300     450    5470     454    6050   452.6  7029.6     472
#Mann= 6 ,-1,0
    1760     .14       0    2580     .09       0    3500     .14       0
    4070    .055       0    4330     .06       0    5300    .045       0
#XS Ineff= 2 , 0
                            6050
Permanent Ineff=
       F       F
Bank Sta=4140,4330
XS Rating Curve= 0 ,0
Exp/Cntr=0.3,0.1

Type RM Length L Ch R = 1 ,86300   ,394,480,411
BEGIN DESCRIPTION:
This cross section corresponds to cross section 86300
of the non-georeferenced CDC model which was the source of this model.
LOB from 2001 aerial topo. - realigned for hydraulics -  ROB OF X-SECTION BASED ON 1991 AND 2001 SURVEY DATA  SET COE NON-EFFECTIVE FLOW LIMIT AT FILL LINE IN ROB
END DESCRIPTION:
XS GIS Cut Line= 6
  2408703.405725 6981373.7450147 2410005.5694597 6980317.9367589
 2410057.6526889 6980130.4368058 2410885.7776731 6978349.1867594
     2411553.041     6977747.0412412264.945886776976866.92982125
#Sta/Elev= 30
    1290     480    1405     470    1570     467    1585   475.4    1860     470
    2270     452    2550     452    2615     447    2630     433    2645     433
    2675     453    3220     450    3222   426.7    3229     422    3261   421.3
    3290     423    3340   446.6    3400     450    3800     455    3900     450
    4850     450    4950     456    5185     452    5250   457.3    5435     450
    5510     450    5560     456    5640     452    6290   452.6 7161.68     472
#Mann= 4 ,-1,0
    1290     .14       0    3220    .055       0    3400     .06       0
    5640     .05       0
#XS Ineff= 2 , 0
                            6080
Permanent Ineff=
       F       F
Bank Sta=3220,3400
XS Rating Curve= 0 ,0
Exp/Cntr=0.3,0.1

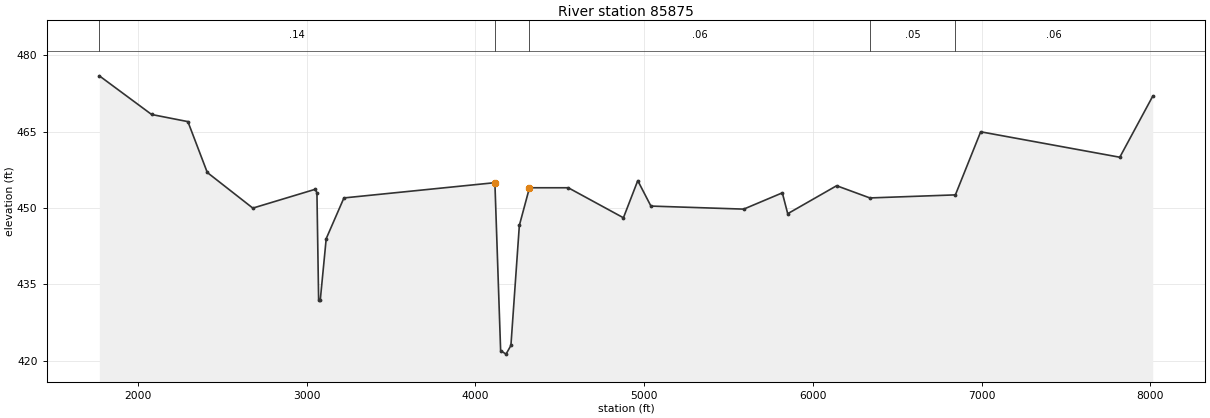
Type RM Length L Ch R = 1 ,85875   ,0,0,0
BEGIN DESCRIPTION:
This cross section corresponds to cross section 85875 of the non-georeferenced CDC model which was the source of this model.
LOB from 2001 aerial topo.  - realigned for hydraulics - ROB from COE section 86951.  CHANNEL BASED ON 1991/2001 SURVEY DATA  SET COE NON-EFFECTIVE FLOW LIMIT AT FILL LINE IN ROB
CDC GP041795-1 Riverside Development
Cross-section 85875 - 94400
Located in ROB.
END DESCRIPTION:
XS GIS Cut Line= 6
  2409015.986137 6981692.9366336 2410083.6943035 6980797.1034515
  2410437.860918 6980526.2700037 2410614.9442253 6980135.6451287
 2410500.3611211 6979635.64514452412445.345349716976769.76970388
#Sta/Elev= 30
    1770     476    2080   468.4    2295     467    2410     457    2680     450
    3050   453.7    3060     453    3070     432    3080     432    3115     444
    3220     452    4115     455    4149     422    4181   421.3    4210     423
    4260   446.6    4320     454    4550     454    4877   448.1    4962   455.4
    5040   450.4    5590   449.8    5819     453    5851   448.9    6141   454.4
    6338     452    6845   452.6    6995     465 7819.67     460    8015     472
#Mann= 5 ,-1,0
    1770     .14       0    4115    .055       0    4320     .06       0
    6338     .05       0    6845     .06       0
#XS Ineff= 2 , 0
                            6690
Permanent Ineff=
       F       F
Bank Sta=4115,4320
XS Rating Curve= 0 ,0
Exp/Cntr=0.3,0.1

River Reach=West Fork       ,wf3b
Reach XY= 30
      2410888.67      6980304.42      2410784.74      6980476.92
      2410835.94      6980591.48      2410946.27      6980651.27
      2411247.15      6980667.45      2411342.02      6980824.89
      2411237.75      6981211.42      2410927.26      6981570.09
      2410827.71       6981819.3      2410970.53      6982192.71
      2411173.38      6982442.14      2411415.39      6982407.12
      2411621.82      6982038.06      2411794.92      6981983.32
      2412049.43      6982133.87      2412310.38      6982554.41
      2412549.67      6982591.51      2412687.55      6982463.44
      2412746.07      6982324.19      2412752.37      6981914.05
      2412831.77      6981515.33      2413886.28      6981065.86
      2414148.36      6981102.17      2414307.71      6981313.73
       2414308.6      6981481.91      2414124.62      6982096.97
      2414142.77      6982224.68      2414263.28      6982193.73
      2414499.74      6981923.982414587.114293436981711.49772928

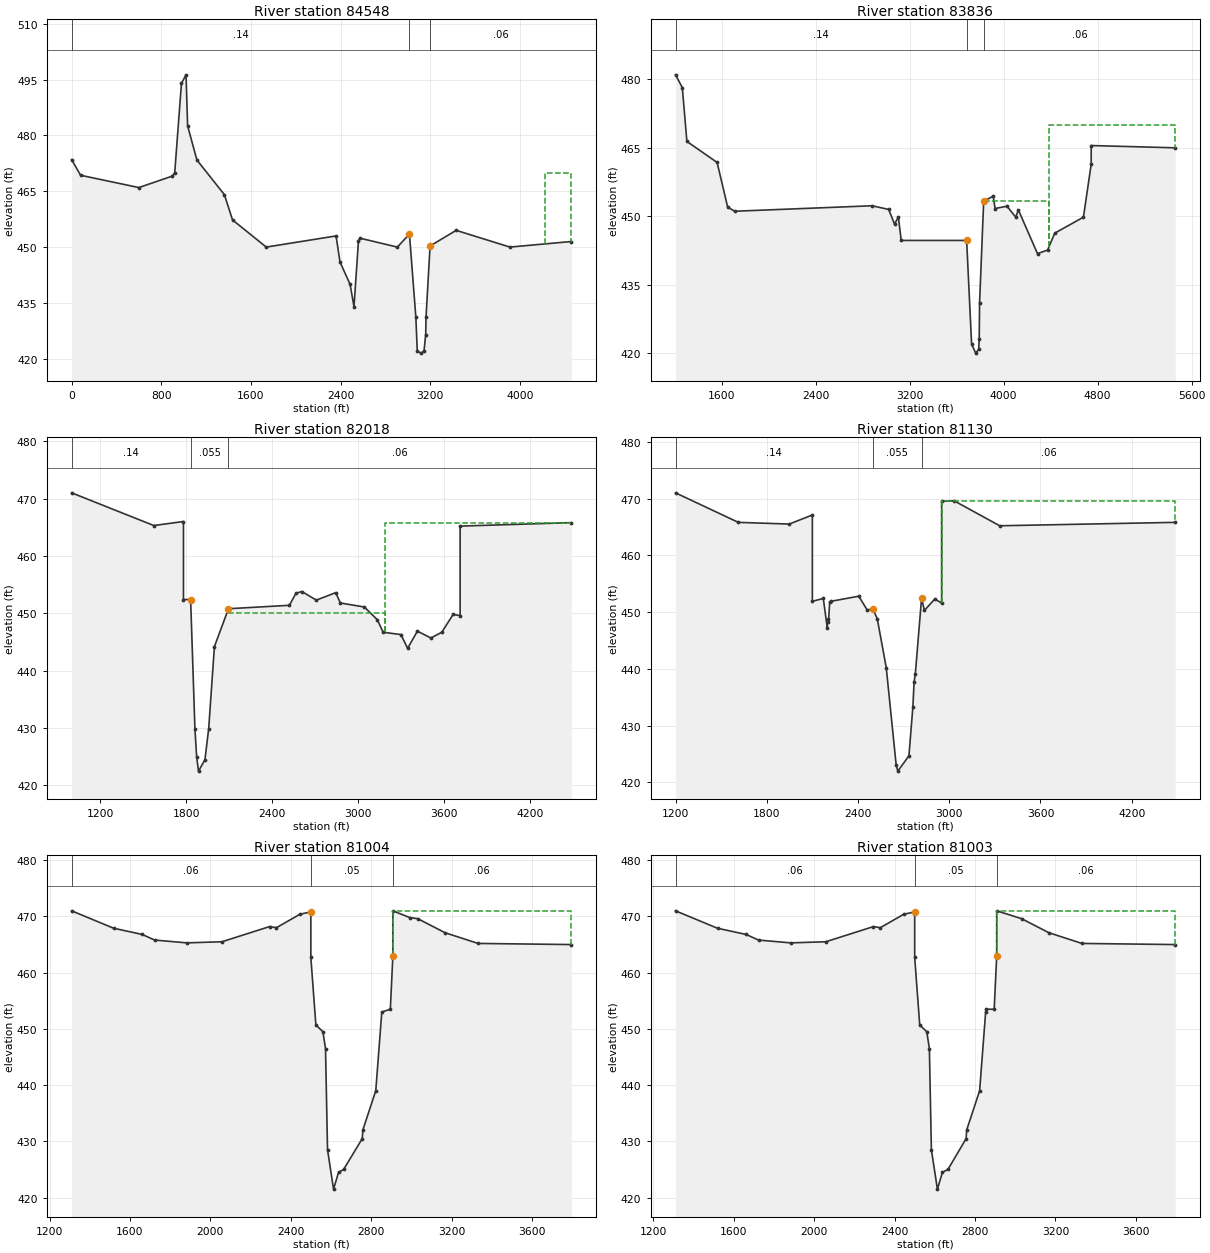
Type RM Length L Ch R = 1 ,84548   ,902,714,637
BEGIN DESCRIPTION:
This cross section corresponds to cross section 84548 of the non-georeferenced CDC model which was the source of this model.
Section realigned to be perpindicular to flow, effectively moving right flow limit.  Boyd Branch channel added.
END DESCRIPTION:
XS GIS Cut Line= 6
  2408810.039042 6982762.3931561 2409218.4988554 6981908.8650075
 2409872.6330458 6981267.6845313 2410395.9590989 6980754.7498616
 2411259.6581589 6980322.9009878 2411617.00194386979497.56881227
#Sta/Elev= 30
       0   473.5      80   469.3     600     466     900   469.1     920     470
     980     494    1021   496.3    1035   482.6    1118   473.4    1363   464.1
    1436   457.3    1737     450    2360     453    2395     446    2485     440
    2520     434    2560   451.7    2573   452.4    2907     450    3015   453.5
    3072   431.2    3085     422    3120   421.5    3145   422.1    3160   426.5
    3163   431.2    3199   450.3    3432   454.5    3912     450    4460   451.5
#Mann= 3 ,0,0
       0     .14       0    3015    .055       0    3199     .06       0
#XS Ineff= 3 ,-1
       0    3015   453.5    3199    4227   450.3    4227    4460     470
Permanent Ineff=
       F       F       F
Bank Sta=3015,3199
XS Rating Curve= 0 ,0
Exp/Cntr=0.3,0.1

Type RM Length L Ch R = 1 ,83836   ,950,1818,800
BEGIN DESCRIPTION:
This cross section corresponds to cross section 83836 of the non-georeferenced CDC model which was the source of this model.
Cont/Exp raised due to influences from SH 360.  Section alignment altered to be perpindicular to flow, effectively moving right flow limit.
END DESCRIPTION:
XS GIS Cut Line= 6
  2409814.435655 6982804.58795362410025.656436026982483.22047439
 2411019.7409878 6980962.6779235 2411547.5568613 6980802.7340177
 2411878.9489151 6979696.0360998 2411959.3860902 6979360.3166269
#Sta/Elev= 30
    1207     481    1265   478.2    1304   466.4    1561   461.8    1651     452
    1711   451.1    2880   452.3    3021   451.5    3071   448.3    3104   449.8
    3128   444.7    3685   444.7    3727     422    3762     420    3787   420.8
    3792     423    3795     431    3830   453.3    3911   454.4    3927   451.7
    4028   452.2    4103   449.8    4125   451.4    4288   441.8    4374   442.6
    4435   446.3    4679   449.8    4745   461.4    4745   465.5    5460     465
#Mann= 3 ,0,0
    1207     .14       0    3685    .055       0    3830     .06       0
#XS Ineff= 3 ,-1
    1207    3685   444.7    3830    4384   453.3    4384    5460     470
Permanent Ineff=
       F       F       F
Bank Sta=3685,3830
XS Rating Curve= 0 ,0
Exp/Cntr=0.3,0.1

Type RM Length L Ch R = 1 ,82018   ,309,886,309
BEGIN DESCRIPTION:
This cross section corresponds to cross section 82018 of the non-georeferenced CDC model which was the source of this model.
Cont/Exp raised due to influences from SH 360.  Section alignment altered to be perpindicular to flow, effectively moving right flow limit.
END DESCRIPTION:
XS GIS Cut Line= 6
  2410744.471853 6983235.2931289 2410994.0638738 6982738.7609855
 2411243.6631122 6982242.2311387 2411549.6834975 6981667.4967238
 2411899.4341103 6981010.6610952 2412134.0293114 6980059.9239353
#Sta/Elev= 30
    1000     471    1573   465.3    1780     466    1780   452.4    1830   452.4
    1860   429.9    1872     425    1885   422.5    1930   424.5    1956   429.9
    1996   444.2    2094   450.8    2519   451.4    2565   453.5    2606   453.8
    2707   452.3    2842   453.6    2875   451.8    3042   451.1    3132   448.9
    3173   446.7    3297   446.3    3344   443.9    3412   446.9    3506   445.7
    3582   446.7    3661   449.8    3710   449.6    3710   465.2    4486   465.8
#Mann= 3 ,0,0
    1000     .14       0    1830    .055       0    2094     .06       0
#XS Ineff= 3 ,-1
    1000    1830   452.4    2094    3184     450    3184    4486   465.8
Permanent Ineff=
       F       F       F
Bank Sta=1830,2094
XS Rating Curve= 0 ,0
Exp/Cntr=0.3,0.1

Type RM Length L Ch R = 1 ,81130   ,126,126,126
BEGIN DESCRIPTION:
This cross section corresponds to cross section 81130 of the non-georeferenced CDC model which was the source of this model.
Cont/Exp raised due to influences from SH 360.  ROB 'n' value lowered to match neighboring cross sections.
END DESCRIPTION:
XS GIS Cut Line= 6
  2411052.250109 6983229.9142027 2411881.4899205 6981811.2050978
 2412147.2449664 6981288.3380333 2412300.6478748 6980914.5530197
 2412410.8389274 6980575.3371627 2412481.7994154 6980286.2376753
#Sta/Elev= 30
    1200     471    1613   465.8    1948   465.5    2100   467.1    2100   451.9
    2172   452.4    2198   447.2    2200   448.7    2206   448.2    2214   451.8
    2222   451.9    2405   452.8    2460   450.4    2499   450.5    2527   448.8
    2586   440.2    2651   423.1    2662     422    2735   424.7    2761   433.3
    2769   437.7    2777   439.1    2818   452.4    2837   450.3    2905   452.3
    2950   451.6    2950   469.5    3032   469.6    3332   465.2    4486   465.8
#Mann= 3 ,0,0
    1200     .14       0    2499    .055       0    2818     .06       0
#XS Ineff= 3 ,-1
    1200    2499     450    2818    2950     450    2950    4486   469.5
Permanent Ineff=
       F       F       F
Bank Sta=2499,2818
XS Rating Curve= 0 ,0
Exp/Cntr=0.5,0.3

Type RM Length L Ch R = 1 ,81004   ,1,1,1
BEGIN DESCRIPTION:
This cross section corresponds to cross section 81004 of the non-georeferenced CDC model which was the source of this model.
END DESCRIPTION:
XS GIS Cut Line= 6
  2411208.826895  6983203.073049 2411646.9644709 6982449.9712087
 2411986.1793437 6981873.0881762 2412126.6193515 6981607.3331302
 2412251.9343896 6981350.2211117  2412388.420009 6981017.6574723
#Sta/Elev= 30
    1310     471    1519   467.9    1661   466.8    1723   465.8    1883   465.3
    2058   465.5    2295   468.2    2329     468    2446   470.4    2500   470.8
    2500   462.7    2525   450.7    2560   449.5    2573   446.5    2583   428.5
    2613   421.5    2638   424.5    2663     425    2756   430.5  2758.5     432
    2823     439    2853     453  2895.5   453.5    2908     463    2908     471
    2992   469.8    3032   469.6    3168   467.1    3332   465.2    3796     465
#Mann= 3 ,0,0
    1310     .06       0    2500     .05       0    2908     .06       0
#XS Ineff= 2 , 0
                            2908             471
Permanent Ineff=
       F       T
Bank Sta=2500,2908
XS Rating Curve= 0 ,0
Exp/Cntr=0.5,0.3

Type RM Length L Ch R = 1 ,81003   ,901,90,90
BEGIN DESCRIPTION:
This cross section corresponds to cross section 81003 of the non-georeferenced CDC model which was the source of this model.
END DESCRIPTION:
XS GIS Cut Line= 6
  2411213.260613  6983197.478572  2411647.531727 6982450.9416792
 2411986.8407597 6981873.8988701 2412127.4631818 6981607.7986805
 2412252.9901618 6981350.2519515 2412391.9150808 6981011.7434422
#Sta/Elev= 30
    1310     471    1519   467.9    1661   466.8    1723   465.8    1883   465.3
    2058   465.5    2295   468.2    2329     468    2446   470.4    2500   470.8
    2500   462.7    2525   450.7    2560   449.5    2573   446.5    2583   428.5
    2613   421.5    2638   424.5  2665.5     425    2756   430.5  2758.5     432
    2823     439    2853     453  2855.5   453.5  2895.5   453.5    2908     463
    2908     471    3032   469.6    3168   467.1    3332   465.2    3796     465
#Mann= 3 ,0,0
    1310     .06       0    2500     .05       0    2908     .06       0
#XS Ineff= 2 , 0
                            2908             471
Permanent Ineff=
       F       T
Bank Sta=2500,2908
XS Rating Curve= 0 ,0
Exp/Cntr=0.5,0.3