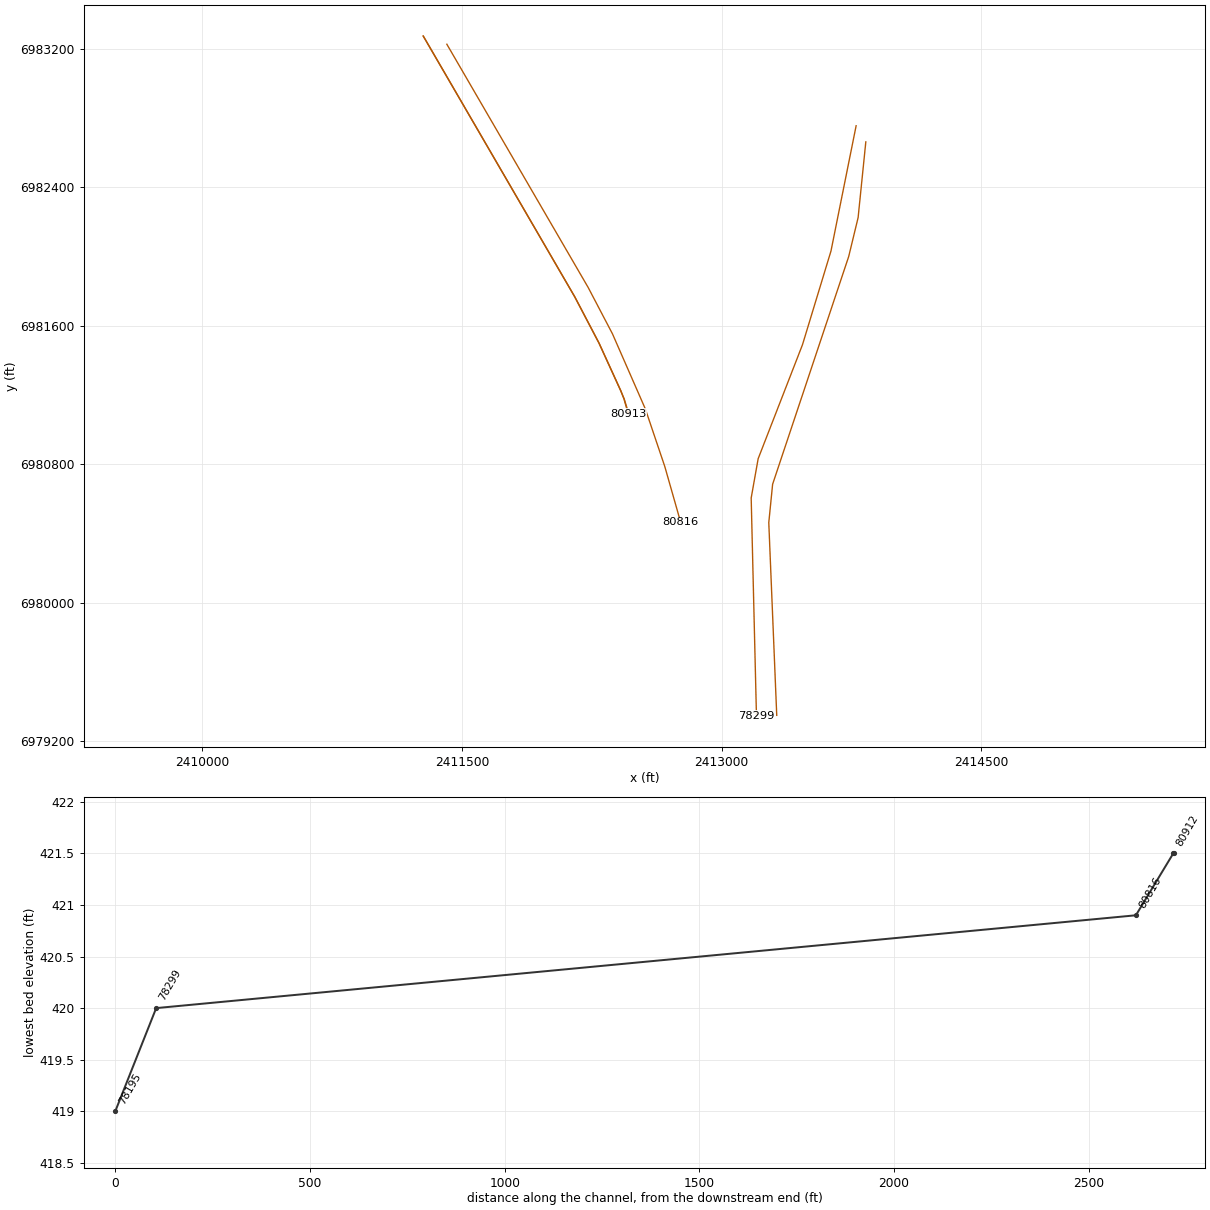
HEC-RAS study CDC_Consolidated_Model.prj: Upper Trinity CDC Consolidated Model

--- CDC_Consolidated_Model.g12 (geometry) --- (continued)

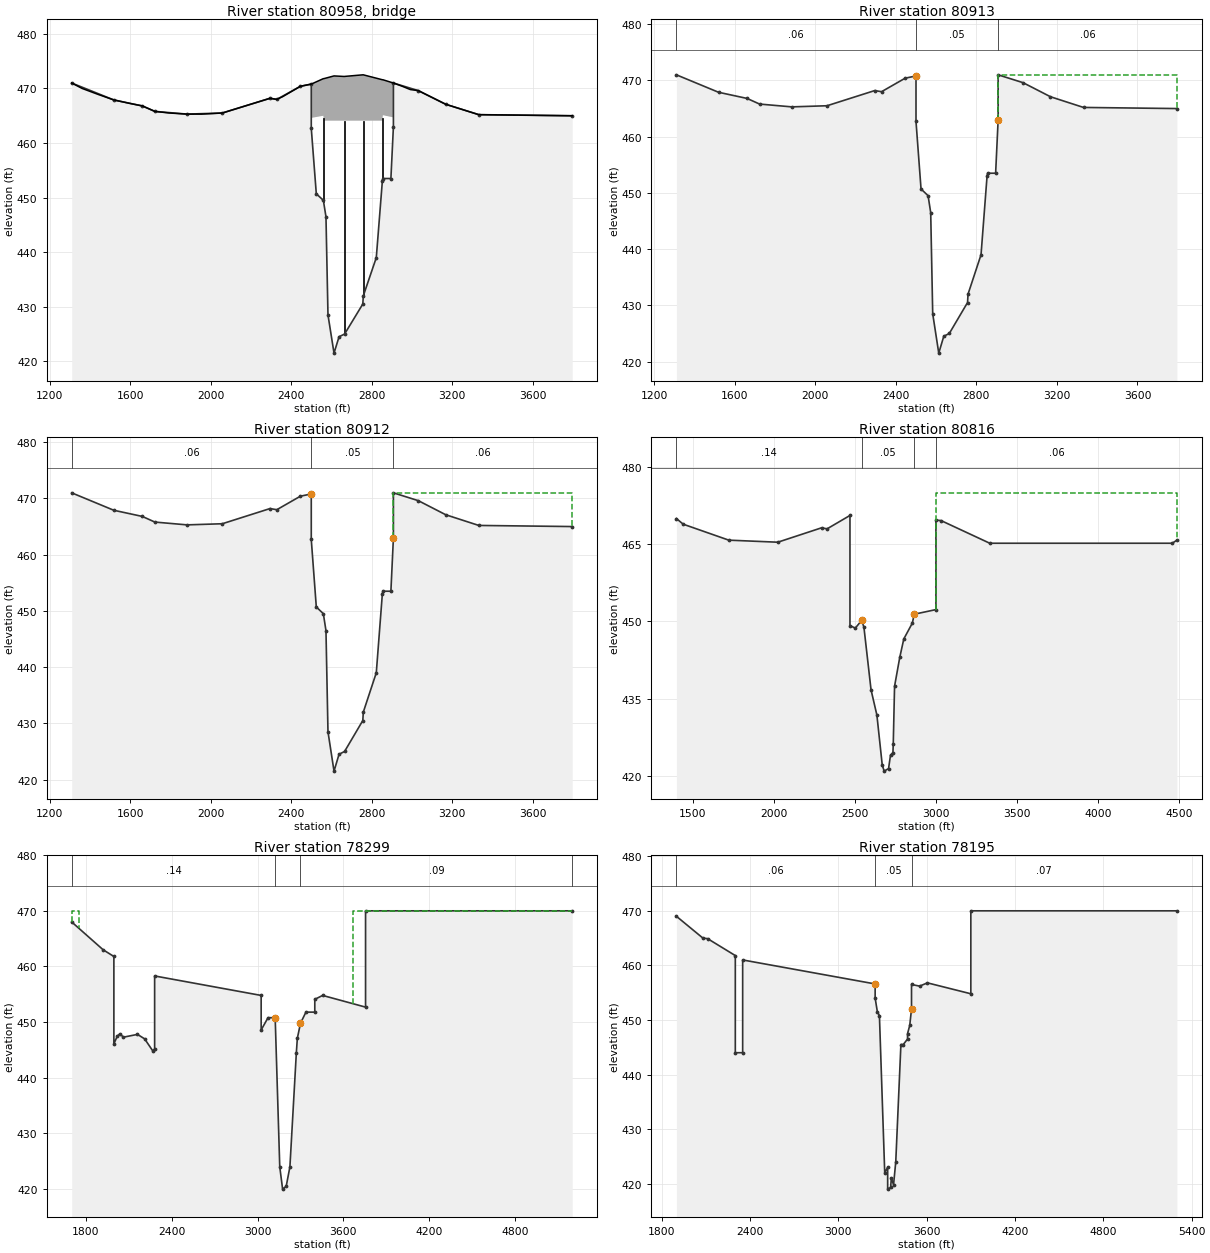
Type RM Length L Ch R = 3 ,80958   ,,,
BEGIN DESCRIPTION:
SH 360
END DESCRIPTION:
Node Name=SH 360
Bridge Culvert--1,0,-1,-1, 0
Deck Dist Width WeirC Skew NumUp NumDn MinLoCord MaxHiCord MaxSubmerge Is_Ogee
1,88,2.6,0, 33, 33, , , 0.95, 0, 0,0,,
    1310    1362    1442    1519    1606    1661    1723    1795    1883    1956
    2058    2295    2329    2358    2446    2500    2500    2560  2562.5    2613
    2663    2756  2758.5    2853  2855.5    2908    2908    2952    2992    3032
    3168    3332    3796
     471     470   468.9   467.9   467.2   466.8   465.8   465.5   465.3   465.3
   465.5   468.2     468   468.5   470.4   470.8   470.8   471.8   471.8   472.3
   472.2   472.5   472.5   471.6   471.6     471     471   470.4   469.8   469.6
   467.1   465.2     465
     471     470   468.9   467.9   467.2   466.8   465.8   465.5   465.3   465.3
   465.5   468.2     468   468.5   470.4   470.8   464.6     465   464.1   464.1
   464.1   464.1   464.1   464.1   465.1   464.7     471   470.4   469.8   469.6
   467.1   465.2     465
    1310    1362    1442    1519    1606    1661    1723    1795    1883    1956
    2058    2295    2329    2358    2446    2500    2500    2560  2562.5    2613
    2663    2756  2758.5    2853  2855.5    2908    2908    2952    2992    3032
    3168    3332    3796
     471     470   468.9   467.9   467.2   466.8   465.8   465.5   465.3   465.3
   465.5   468.2     468   468.5   470.4   470.8   470.8   471.8   471.8   472.3
   472.2   472.5   472.5   471.6   471.6     471     471   470.4   469.8   469.6
   467.1   465.2     465
     471     470   468.9   467.9   467.2   466.8   465.8   465.5   465.3   465.3
   465.5   468.2     468   468.5   470.4   470.8   464.6     465   464.1   464.1
   464.1   464.1   464.1   464.1   465.1   464.7     471   470.4   469.8   469.6
   467.1   465.2     465
Pier Skew, UpSta & Num, DnSta & Num=  ,2561.25, 2 ,2561.25, 2 , 0 , 0 , 0 ,,
     2.5     2.5
     420     467
     2.5     2.5
     420     467
Pier Skew, UpSta & Num, DnSta & Num=  ,2664.25, 2 ,2664.25, 2 , 0 , 0 , 0 ,,
     2.5     2.5
     420     467
     2.5     2.5
     420     467
Pier Skew, UpSta & Num, DnSta & Num=  ,2758.25, 2 ,2758.25, 2 , 0 , 0 , 0 ,,
     2.5     2.5
     420     467
     2.5     2.5
     420     467
Pier Skew, UpSta & Num, DnSta & Num=  ,2854.25, 2 ,2854.25, 2 , 0 , 0 , 0 ,,
     2.5     2.5
     420     467
     2.5     2.5
     420     467
BR Coef=-1 , 0 , 0 ,1.05, 0 ,,,0.8,-1,0.5,0,
WSPro=,,,, 1 ,,,, 0 ,,,, 0 ,,,,-1 ,-1 ,-1 , 0 , 0 , 0 , 0 , 0
BC Design=,, 0 ,, 0 ,,,,,,
BC Use User HTab Curves=0
BC User HTab FreeFlow(D)= 0

Type RM Length L Ch R = 1 ,80913   ,1,1,1
BEGIN DESCRIPTION:
This cross section corresponds to cross section 80913 of the non-georeferenced CDC model which was the source of this model.
END DESCRIPTION:
XS GIS Cut Line= 6
2411276.153289516983274.31275937 2412151.3437115 6981767.9099088
 2412291.5563576 6981500.4291446 2412416.6683121 6981226.4752962
 2412436.0189952 6981178.7434362      2412460.38        6981093.
#Sta/Elev= 30
    1310     471    1519   467.9    1661   466.8    1723   465.8    1883   465.3
    2058   465.5    2295   468.2    2329     468    2446   470.4    2500   470.8
    2500   462.7    2525   450.7    2560   449.5    2573   446.5    2583   428.5
    2613   421.5    2638   424.5  2665.5     425    2756   430.5  2758.5     432
    2823     439    2853     453  2855.5   453.5  2895.5   453.5    2908     463
    2908     471    3032   469.6    3168   467.1    3332   465.2    3796     465
#Mann= 3 ,0,0
    1310     .06       0    2500     .05       0    2908     .06       0
#XS Ineff= 2 , 0
                            2908             471
Permanent Ineff=
       F       T
Bank Sta=2500,2908
XS Rating Curve= 0 ,0
Exp/Cntr=0.5,0.3

Type RM Length L Ch R = 1 ,80912   ,96,96,96
BEGIN DESCRIPTION:
This cross section corresponds to cross section 80912 of the non-georeferenced CDC model which was the source of this model.
Copy of 80913
END DESCRIPTION:
XS GIS Cut Line= 6
2411277.416279926983274.14288345 2412152.2009932 6981768.4387792
 2412292.6410011 6981500.5239607 2412417.9557111 6981226.1258874
 2412438.2630852 6981176.0347802      2412463.66      6981093.43
#Sta/Elev= 30
    1310     471    1519   467.9    1661   466.8    1723   465.8    1883   465.3
    2058   465.5    2295   468.2    2329     468    2446   470.4    2500   470.8
    2500   462.7    2525   450.7    2560   449.5    2573   446.5    2583   428.5
    2613   421.5    2638   424.5  2665.5     425    2756   430.5  2758.5     432
    2823     439    2853     453  2855.5   453.5  2895.5   453.5    2908     463
    2908     471    3032   469.6    3168   467.1    3332   465.2    3796     465
#Mann= 3 ,0,0
    1310     .06       0    2500     .05       0    2908     .06       0
#XS Ineff= 2 , 0
                            2908             471
Permanent Ineff=
       F       T
Bank Sta=2500,2908
XS Rating Curve= 0 ,0
Exp/Cntr=0.5,0.3

Type RM Length L Ch R = 1 ,80816   ,2199,2516,1590
BEGIN DESCRIPTION:
This cross section corresponds to cross section 80816 of the non-georeferenced CDC model which was the source of this model.
'n' value lowered in ROB to be consistent.
END DESCRIPTION:
XS GIS Cut Line= 6
  2411413.125043 6983226.9089593 2412229.3481487 6981822.0078977
 2412369.7881565 6981554.0930792 2412559.9209783 6981119.8101552
 2412672.2731158 6980787.0768967 2412763.5671592  6980466.485415
#Sta/Elev= 30
    1400     470    1442   468.9    1723   465.8    2025   465.4    2295   468.2
    2329     468    2470   470.6    2470   449.2    2503   448.7    2542   450.2
    2556   448.9    2600   436.7    2636   431.8    2669   422.1    2681   420.9
    2708   421.4    2720     424    2735   424.5    2737   426.2    2745   437.4
    2777     443    2802   446.6    2855   449.7    2866   451.4    3000   452.3
    3000   469.7    3032   469.6    3332   465.2    4457   465.2    4486   465.8
#Mann= 4 ,-1,0
    1400     .14       0    2542     .05       0    2866     .09       0
    3000     .06       0
#XS Ineff= 3 ,-1
    1400    2542     450    2866    3000   451.4    3000    4486     475
Permanent Ineff=
       F       F       T
Bank Sta=2542,2866
XS Rating Curve= 0 ,0
Exp/Cntr=0.5,0.3

Type RM Length L Ch R = 1 ,78299   ,105,105,105
BEGIN DESCRIPTION:
This cross section corresponds to cross section 78299 of the non-georeferenced CDC model which was the source of this model.
LOB lowered 2' below railroad.  Right flow limit adjusted due to SH 360 and flow over railroad.  LOB 'n' value corrected from 0.014 to 0.14.
END DESCRIPTION:
XS GIS Cut Line= 6
2413777.517136776982755.92061994 2413632.3000672 6982032.7138412
 2413467.6439004 6981491.1801473 2413211.5141633 6980832.5590892
    2413171.2649 6980605.6999629 2413201.7204611 6979348.0385658
#Sta/Elev= 30
    1700     468    1920     463    1995   461.8    1995   446.1    2019   447.5
    2037   447.9    2062   447.3    2160   447.8    2210     447    2268   444.8
    2280   445.2    2280   458.3    3025   454.8    3025   448.6    3073   450.8
    3123   450.8    3155     424    3175     420    3200   420.5    3226     424
    3271   444.5    3278   447.1    3300   449.8    3338   451.8    3400   451.8
    3400   454.1    3455   454.8    3755   452.7    3755     470    5200     470
#Mann= 4 ,-1,0
    1700     .14       0    3123     .05       0    3300     .09       0
    5200    .065       0
#XS Ineff= 4 ,-1
    1700    1750     470    1750    3123     450    3300    3670   449.8
    3670    5200     470
Permanent Ineff=
       F       F       F       F
Bank Sta=3123,3300
XS Rating Curve= 0 ,0
Exp/Cntr=0.5,0.3

Type RM Length L Ch R = 1 ,78195   ,1,1,1
BEGIN DESCRIPTION:
This cross section corresponds to cross section 78195 of the non-georeferenced CDC model which was the source of this model.
Right flow limit adjusted due to SH 360 and flow over railroad.  'n' value raised in ROB  to be consistent.
END DESCRIPTION:
XS GIS Cut Line= 6
  2413833.478142 6982662.7444052 2413788.9933233 6982225.4155555
  2413734.573812 6982000.4803098 2413295.1006103 6980685.3123365
 2413272.9149592 6980463.4548406 2413318.8902609 6979349.8438788
#Sta/Elev= 30
    1900     469    2080     465    2112   464.9    2300   461.8    2300     444
    2350     444    2350     461    3250   456.6    3250     454    3265   451.5
    3279   450.8    3315     422    3335     423    3335     419    3355   419.3
    3360     421    3375   419.8    3390     424    3425   445.5    3441   445.5
    3470   446.5    3470   447.5    3485     449    3497     452    3497   456.5
    3552   456.2    3605   456.8    3900   454.8    3900     470    5300     470
#Mann= 3 ,0,0
    1900     .06       0    3250     .05       0    3497     .07       0
#XS Ineff= 2 , 0
            3250     450
Permanent Ineff=
       F       F
Bank Sta=3250,3497
XS Rating Curve= 0 ,0
Exp/Cntr=0,0