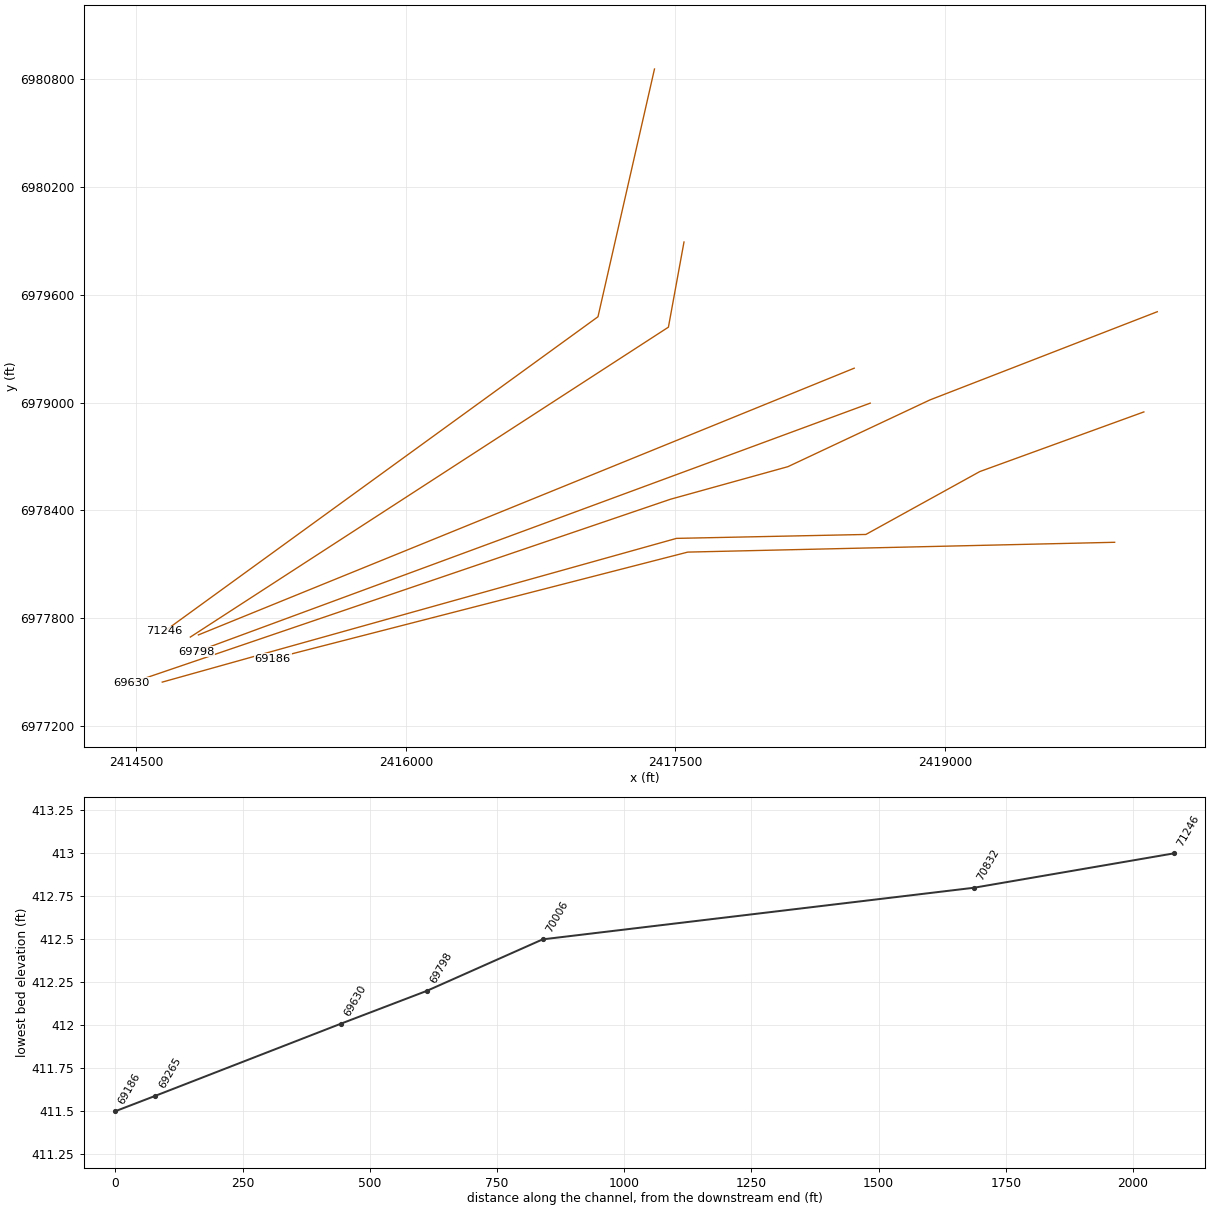
HEC-RAS study CDC_Consolidated_Model.prj: Upper Trinity CDC Consolidated Model

--- CDC_Consolidated_Model.g12 (geometry) --- (continued)

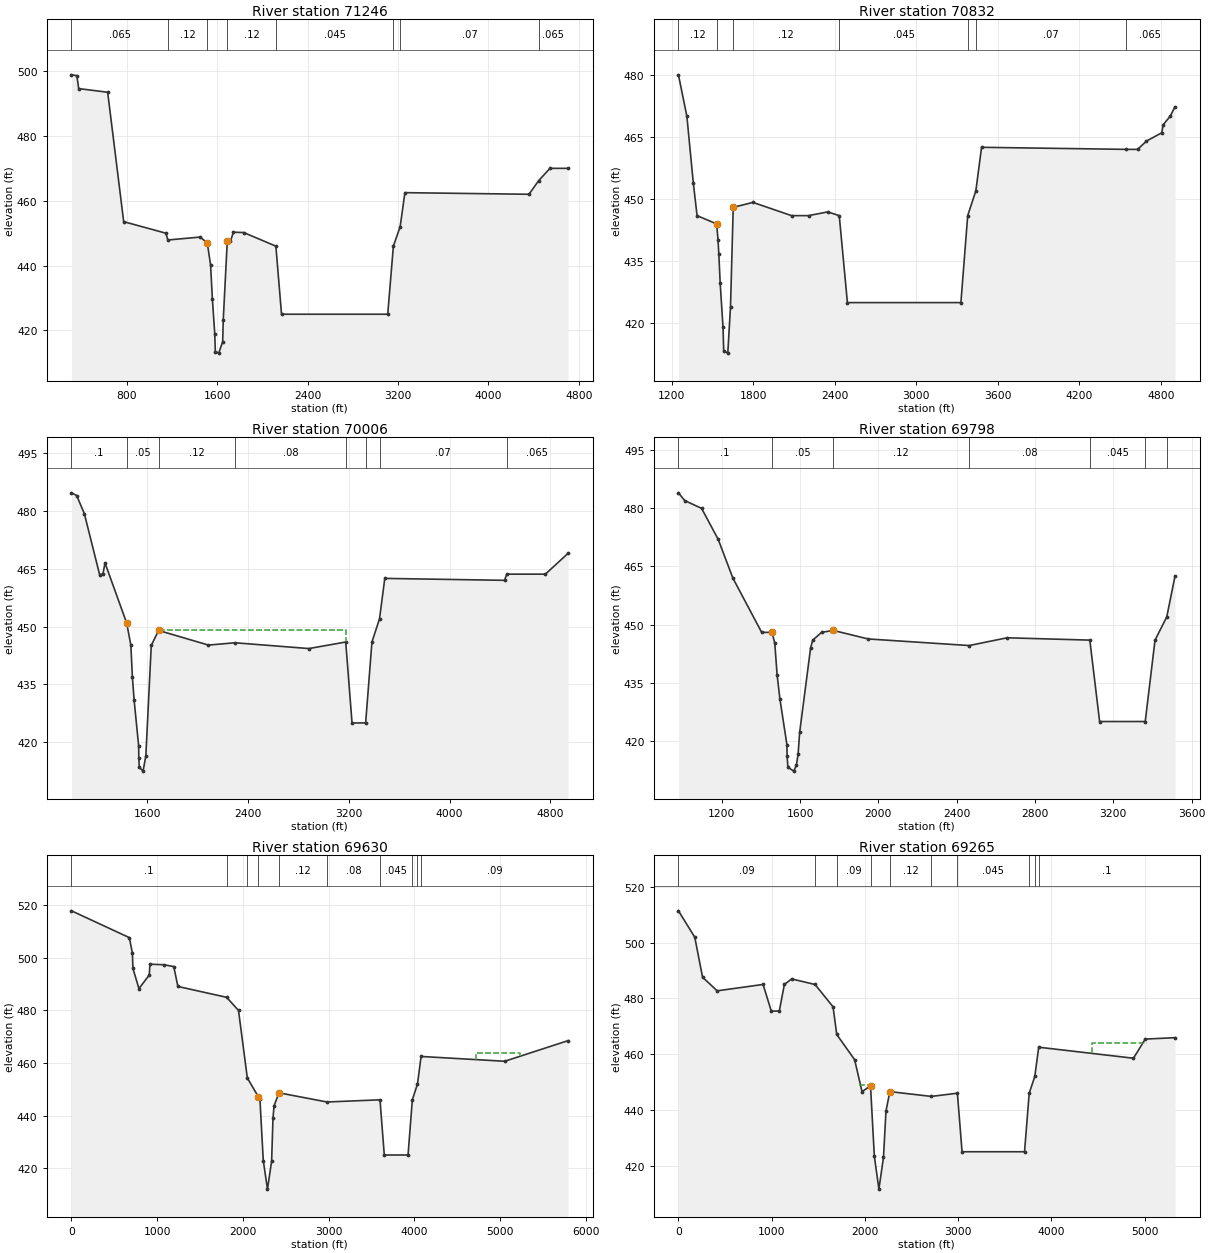
Type RM Length L Ch R = 1 ,71246   ,380,393,241
BEGIN DESCRIPTION:
This cross section corresponds to cross section 71246 of the non-georeferenced CDC model which was the source of this model.
---------------------------------------------------------------------
CDC FW020105-01 Riverpark Addition
Cross-section 71246 - 74891
Located in LOB.
---------------------------------------------------------------------
END DESCRIPTION:
XS GIS Cut Line= 4
     2417383.365     6980857.409     2417068.926     6979477.766
2415825.941552736978575.404959822414657.399211596977727.08615361
#Sta/Elev= 30
 309.988498.8458357.3073   498.6 373.718   494.6630.1356493.4716771.8537453.5542
1144.922     450    1163   447.9    1449   448.8    1512     447    1541   440.2
    1557   429.7    1578     419    1583   413.5    1613     413    1648   416.5
    1653   423.1    1689   447.7    1717   447.5    1743   450.3    1834   450.2
    2119     446    2169     425    3109     425    3159     446    3219     452
    3261   462.5    4359     462    4445   466.2    4545     470    4705     470
#Mann= 8 ,-1,0
 309.988    .065       0    1163     .12       0    1512     .05       0
    1689     .12       0    2119    .045       0    3159     .08       0
    3219     .07       0    4445    .065       0
#XS Ineff= 1 ,-1
    2119    3159     446
Permanent Ineff=
       T
Bank Sta=1512,1689
XS Rating Curve= 0 ,0
Exp/Cntr=0.3,0.1

Type RM Length L Ch R = 1 ,70832   ,1077,847,406
BEGIN DESCRIPTION:
This cross section corresponds to cross section 70832 of the non-georeferenced CDC model which was the source of this model.
END DESCRIPTION:
XS GIS Cut Line= 4
  2417547.578325 6979894.0199558 2417460.8819769 6979419.8174921
 2415994.4300846 6978468.6054099 2414800.58818956977694.22144216
#Sta/Elev= 30
    1250     480    1312     470    1359     454    1387     446    1531     444
    1541   440.2    1547   436.8    1557   429.7    1578     419    1583   413.3
    1613   412.8    1633     424    1653     448    1798   449.2    2082     446
    2207     446    2348   446.9    2433     446    2493     425    3328     425
    3378     446    3438     452    3480   462.5    4541     462    4628     462
    4693     464    4805     466    4817     468    4868     470    4903   472.3
#Mann= 7 ,-1,0
    1250     .12       0    1531     .05       0    1653     .12       0
    2433    .045       0    3378     .08       0    3438     .07       0
    4541    .065       0
#XS Ineff= 1 ,-1
    2433    3378     446
Permanent Ineff=
       T
Bank Sta=1531,1653
XS Rating Curve= 0 ,0
Exp/Cntr=0.3,0.1

Type RM Length L Ch R = 1 ,70006   ,228,228,228
BEGIN DESCRIPTION:
This cross section corresponds to cross section 70006 of the non-georeferenced CDC model which was the source of this model.
END DESCRIPTION:
XS GIS Cut Line= 6
  2418494.785092 6979191.3750356 2417704.1078684 6978869.5475953
 2417308.7635148  6978708.641093 2416913.4152241 6978547.7395119
  2416201.778524 6978258.12887072414845.433627836977706.17004218
#Sta/Elev= 30
    1000   484.7    1041     484    1102   479.3    1223   463.5    1249   463.6
    1266   466.5    1438   450.9    1471   445.2    1483     437    1497   430.9
    1533     419    1534     416    1538   413.5    1568   412.5    1590   416.5
    1633   445.1    1691     449    2087   445.2    2297   445.8    2884   444.3
    3176     446    3226     425    3334     425    3384     446    3444     452
    3486   462.5    4436     462    4454   463.6    4760   463.6    4940     469
#Mann= 8 ,-1,0
    1000      .1       0    1438     .05       0    1691     .12       0
    2297     .08       0    3176    .045       0    3334     .08       0
    3444     .07       0    4454    .065       0
#XS Ineff= 2 ,-1
    1691    3176     449    3176    3384     446
Permanent Ineff=
       F       T
Bank Sta=1438,1691
XS Rating Curve= 0 ,0
Exp/Cntr=0.3,0.1

Type RM Length L Ch R = 1 ,69798   ,166,168,109
BEGIN DESCRIPTION:
69798
END DESCRIPTION:
XS GIS Cut Line= 2
  2418583.8709296978996.755135862414833.43700001     6977612.207
#Sta/Elev= 30
     979     484    1011     482    1097     480    1182     472    1257     462
    1404     448    1457     448    1471   445.2    1483     437    1497   430.9
    1533     419    1534     416    1538   413.2    1568   412.2    1581   413.7
    1590   416.5    1598   422.2    1654     444    1665     446    1710     448
    1770   448.5    1948   446.3    2464   444.6    2657   446.6    3080     446
    3130     425    3363     425    3413     446    3473     452    3515   462.5
#Mann= 7 ,-1,0
     979      .1       0    1457     .05       0    1770     .12       0
    2464     .08       0    3080    .045       0    3363     .08       0
    3473     .07       0
#XS Ineff= 1 ,-1
    3080    3413     446
Permanent Ineff=
       T
Bank Sta=1457,1770
XS Rating Curve= 0 ,0
Exp/Cntr=0.3,0.1

Type RM Length L Ch R = 1 ,69630   ,425,365,210
BEGIN DESCRIPTION:
69630
2009 LiDAR - LOB Includes Pettigrew Fill.
END DESCRIPTION:
XS GIS Cut Line= 5
  2420181.3521216979505.819805952418915.727122046979014.50036153
2418125.796566436978642.972583742417472.071161366978461.55258952
2414474.024286366977440.01034415
#Sta/Elev= 30
       0  517.92  675.07  507.72  711.01  501.76  716.97  496.01  786.99  488.32
  907.71   493.5  915.19  497.62 1077.64   497.4 1193.47  496.71 1241.54  489.14
 1810.87     485 1948.99     480 2051.75  454.31 2179.17  447.24 2198.94  446.23
 2237.89   422.9    2287  412.01 2335.36  422.68  2351.1  438.91 2363.59  443.69
 2421.06  448.66  2981.7  445.17    3600     446    3650     425 3927.34     425
 3977.34     446 4037.34     452 4079.34   462.5 5055.06  460.67  5794.4  468.52
#Mann= 10 ,-1,0
       0      .1       0 1810.87     .07       0 2051.75      .1       0
 2179.17     .05       0 2421.06     .12       0  2981.7     .08       0
    3600    .045       0 3977.34     .08       0 4037.34     .07       0
 4079.34     .09       0
#XS Ineff= 2 ,-1
    3600 3977.34     446 4715.94 5235.39  463.64
Permanent Ineff=
       T       F
Bank Sta=2179.17,2421.06
XS Rating Curve= 0 ,0
Exp/Cntr=0.3,0.1

Type RM Length L Ch R = 1 ,69265   ,78,79,80
BEGIN DESCRIPTION:
69265
2009 LiDAR - LOB Includes Pettigrew Fill.
END DESCRIPTION:
XS GIS Cut Line= 5
  2420106.5098186978947.835141612419193.749402116978615.80389161
2418559.634818736978265.543474962417505.815374346978243.69741014
2414644.270000046977443.35000001
#Sta/Elev= 30
       0  511.43  175.08  501.97  258.55  487.63   415.5  482.73  907.77  485.02
  996.08  475.43 1082.03  475.51    1136     485    1214     487 1465.46     485
 1658.23     477 1697.95  467.07 1889.67  458.03 1969.17  446.55 2060.18  448.66
    2101  423.46    2150  411.59 2199.25  422.95 2225.88  439.59 2267.44  446.58
 2712.06  444.85 2992.02     446 3042.02     425 3712.25     425 3762.25     446
 3822.25     452 3864.25   462.5 4880.77  458.55 5006.35  465.42 5326.06  465.92
#Mann= 10 ,-1,0
       0     .09       0 1465.46     .07       0 1697.95     .09       0
 2060.18     .05       0 2267.44     .12       0 2712.06     .08       0
 2992.02    .045       0 3762.25     .08       0 3822.25     .07       0
 3864.25      .1       0
#XS Ineff= 4 ,-1
  164.38    1214     487  1934.3 2055.48     449 2992.02 3762.25     446
 4437.25 5027.87  463.98
Permanent Ineff=
       F       F       T       F
Bank Sta=2060.18,2267.44
XS Rating Curve= 0 ,0
Exp/Cntr=0.3,0.1

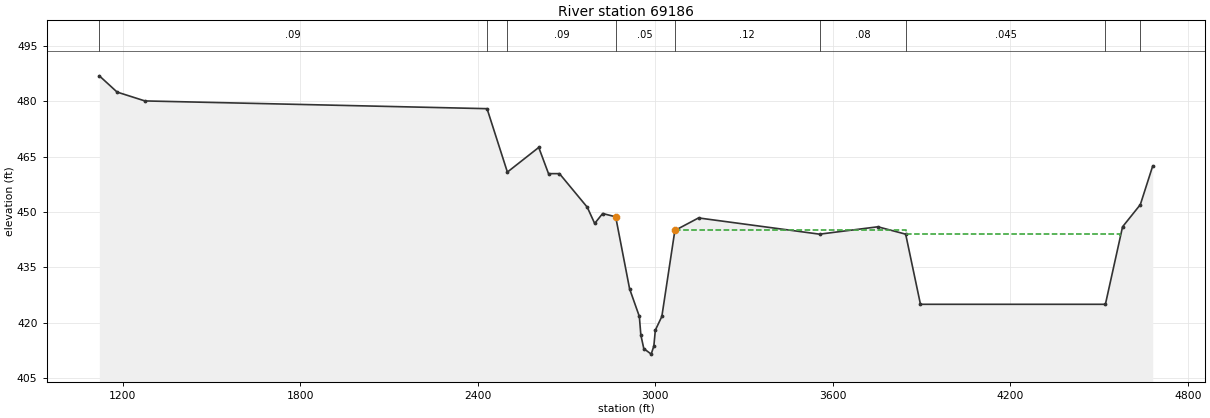
Type RM Length L Ch R = 1 ,69186   ,850,857,800
BEGIN DESCRIPTION:
69186
--------------------------------------------------------------------
LOMR#17-06-0659P & CDC FW050115-01 Pettigrew Development
Cross-sections 69186 - 69630
--------------------------------------------------------------------
LOB includes Pettigrew Fill.
END DESCRIPTION:
XS GIS Cut Line= 6
  2419943.983309 6978221.9225782 2419339.5317629 6978208.0065956
  2418749.186815 6978194.4262421 2417568.4959349 6978167.2980156
  2416741.462484 6977954.59207622415259.73833976 6977573.5434931
#Sta/Elev= 30
    1121   486.9    1181   482.5    1275   480.1 2431.28     478    2500  460.82
    2606   467.5    2639   460.4    2676   460.4    2770   451.3    2795   446.9
    2822   449.6    2866   448.7    2913   429.2    2946   421.7    2951   416.7
    2961     413    2986   411.5    2995   413.7    3000     418    3022   421.7
    3066     445    3146   448.4    3555     444    3752     446    3846     444
    3896     425    4521     425    4579     446    4639     452    4681   462.5
#Mann= 9 ,-1,0
    1121     .09       0 2431.28     .07       0    2500     .09       0
    2866     .05       0    3066     .12       0    3555     .08       0
    3846    .045       0    4521     .08       0    4639     .07       0
#XS Ineff= 3 ,-1
    2000    2866   448.7    3066    3846     445    3846    4571     444
Permanent Ineff=
       F       F       T
Bank Sta=2866,3066
XS Rating Curve= 0 ,0
Exp/Cntr=0.3,0.1