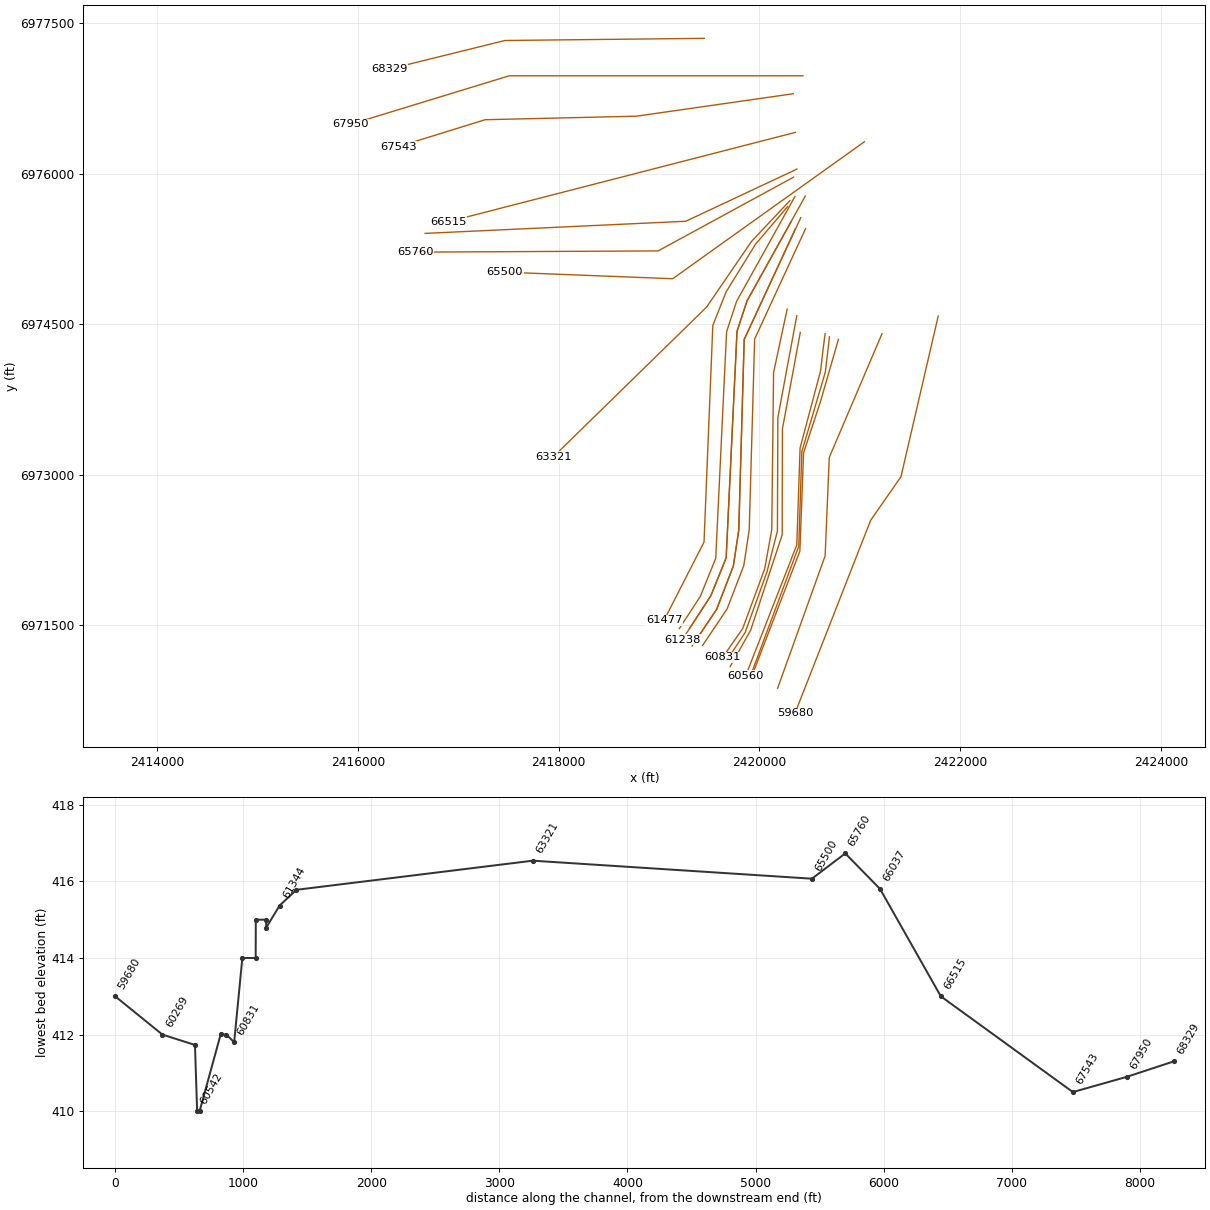
HEC-RAS study CDC_Consolidated_Model.prj: Upper Trinity CDC Consolidated Model

--- CDC_Consolidated_Model.g12 (geometry) --- (continued)

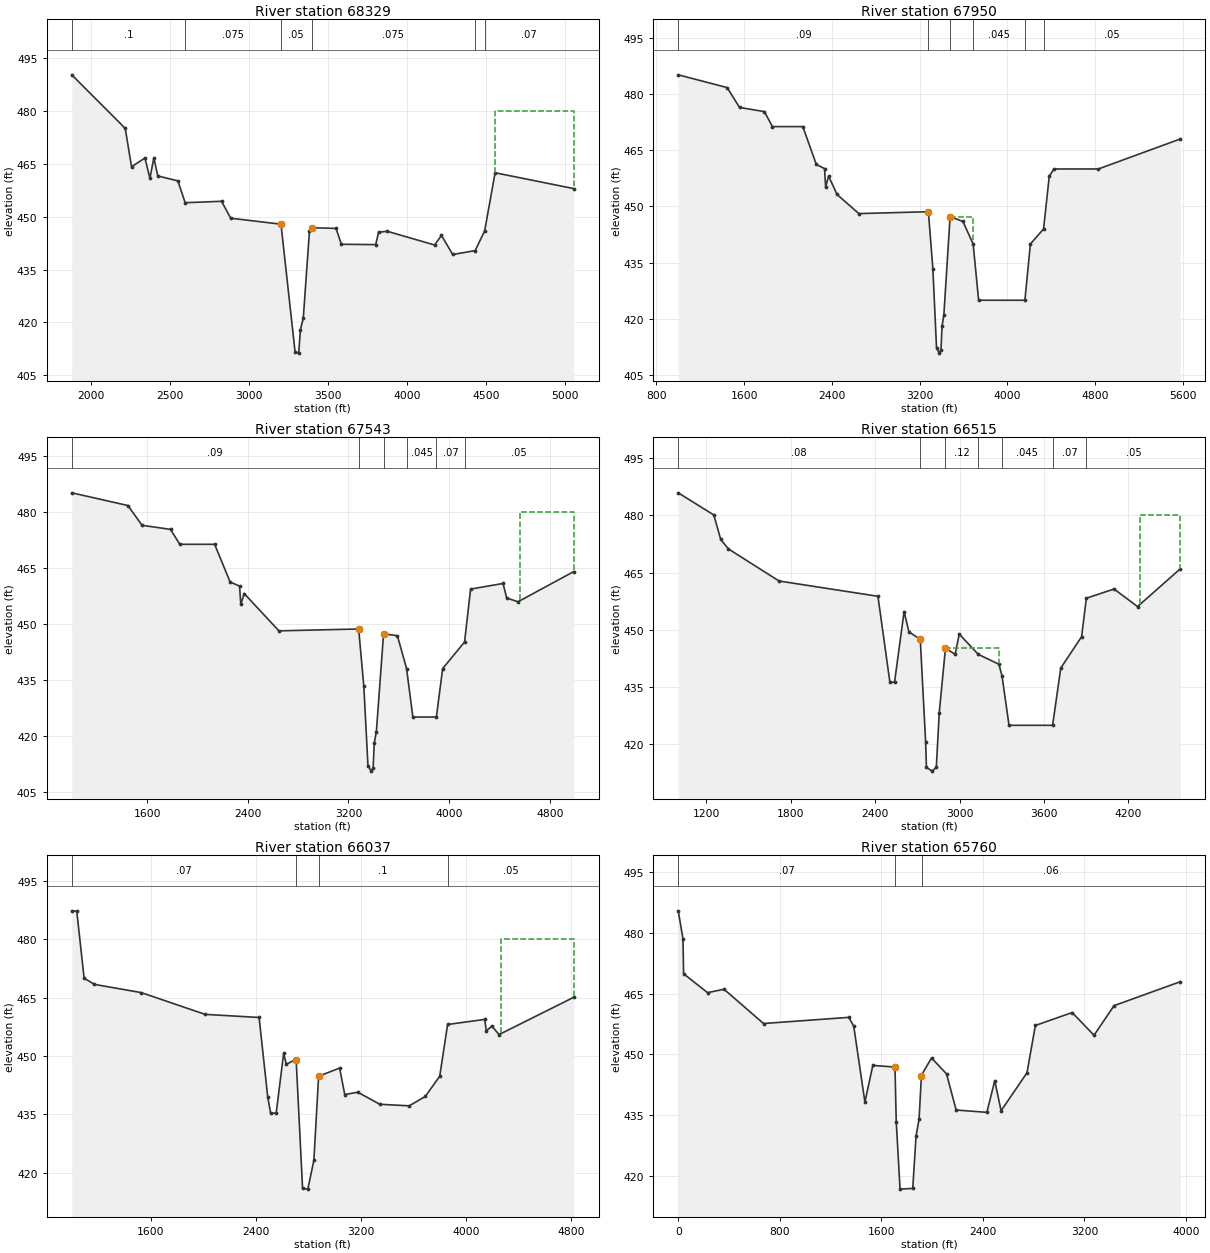
Type RM Length L Ch R = 1 ,68329   ,339,364,334
BEGIN DESCRIPTION:
This cross section corresponds to cross section 68329 of the non-georeferenced CDC model which was the source of this model.
END DESCRIPTION:
XS GIS Cut Line= 6
2419451.021301856977349.46259518 2418555.6301155 6977339.7366786
 2417968.6099641 6977333.3741585 2417465.4498812 6977327.9289594
 2416881.8818226 6977183.58410372416310.928618726977042.37117316
#Sta/Elev= 30
    1879   490.3    2217   475.1    2257   464.2    2342   466.7    2373   460.9
    2398   466.7    2423   461.6    2550   460.2    2596     454    2826   454.4
    2884   449.6    3202   447.9    3291   411.7    3314   411.3    3325     418
    3343   421.2    3382   445.9    3395   446.9    3550   446.7    3584   442.2
    3801   442.1    3819   445.6    3873   445.9    4173     442    4217   444.7
    4288   439.3    4430   440.4    4490     446    4556   462.5    5054     458
#Mann= 6 ,-1,0
    1879      .1       0    2596    .075       0    3202     .05       0
    3395    .075       0    4430     .08       0    4490     .07       0
#XS Ineff= 3 ,-1
    1879    3202   447.9    3395    4556   446.9    4556    5054     480
Permanent Ineff=
       F       F       F
Bank Sta=3202,3395
XS Rating Curve= 0 ,0
Exp/Cntr=0.3,0.1

Type RM Length L Ch R = 1 ,67950   ,454,423,449
BEGIN DESCRIPTION:
This cross section corresponds to cross section 67950 of the non-georeferenced CDC model which was the source of this model.
END DESCRIPTION:
XS GIS Cut Line= 3
  2420433.972159 6976976.2410145 2417508.6249917 6976976.2410145
  2415928.247575 6976492.8486086
#Sta/Elev= 30
    1000   485.1    1446   481.7    1559   476.4    1785   475.3    1859   471.3
    2136   471.3    2259   461.2    2334   460.1    2344   455.2    2371   458.1
    2448   453.2    2647   448.1    3281   448.6    3322   433.3    3355   412.4
    3380   410.9    3396   411.7    3405     418    3422   421.1    3479   447.3
    3596     446    3689     440    3739     425    4161     425    4211     440
    4331     444    4383     458    4425     460    4831     460    5578     468
#Mann= 6 ,-1,0
    1000     .09       0    3281    .055       0    3479     .07       0
    3689    .045       0    4161     .07       0    4331     .05       0
#XS Ineff= 3 ,-1
    2000    3281   448.6    3479    3684   447.3    3684    4211     440
Permanent Ineff=
       F       F       T
Bank Sta=3281,3479
XS Rating Curve= 0 ,0
Exp/Cntr=0.3,0.1

Type RM Length L Ch R = 1 ,67543   ,522,1031,853
BEGIN DESCRIPTION:
This cross section corresponds to cross section 67543 of the non-georeferenced CDC model which was the source of this model.
END DESCRIPTION:
XS GIS Cut Line= 6
    2420337.2381 6976797.2948501 2419597.4981105 6976691.3432903
 2418775.5591376 6976573.6391294 2417937.7222306 6976554.0158091
 2417267.4519176 6976538.33309772416402.437933516976269.79467283
#Sta/Elev= 30
    1000   485.1    1446   481.7    1559   476.4    1785   475.3    1859   471.3
    2136   471.3    2259   461.2    2334   460.1    2344   455.2    2371   458.1
    2647   448.1    3281   448.6    3322   433.3    3355     412    3380   410.5
    3396   411.3    3405     418    3422   421.1    3479   447.3    3589   446.8
    3662     438    3712     425    3899     425    3949     438    4123   445.1
    4171   459.3    4429   460.8    4458   456.9    4548   455.9    4992     464
#Mann= 6 ,-1,0
    1000     .09       0    3281    .055       0    3479     .07       0
    3662    .045       0    3899     .07       0    4123     .05       0
#XS Ineff= 3 ,-1
    2000    3281   448.6    3662    4567     438    4567    4992     480
Permanent Ineff=
       F       T       F
Bank Sta=3281,3479
XS Rating Curve= 0 ,0
Exp/Cntr=0.3,0.1

Type RM Length L Ch R = 1 ,66515   ,526,474,298
BEGIN DESCRIPTION:
This cross section corresponds to cross section 66515 of the non-georeferenced CDC model which was the source of this model.
END DESCRIPTION:
XS GIS Cut Line= 6
  2420357.846983 6976412.1230482 2419529.0172763 6976198.6093677
 2419114.5981577 6976091.8605654 2418617.2920657 6975963.7689581
 2417871.3253818 6975771.64598272416900.677700116975521.68416544
#Sta/Elev= 30
    1000   485.9    1253   480.1    1302   473.7    1357   471.2    1717   462.8
    2420   458.8    2505   436.3    2538   436.3    2606   454.8    2640   449.5
    2721   447.5    2759   420.7    2765     414    2805     413    2835     414
    2856   428.3    2900   445.2    2969   443.6    2998   448.9    3133   443.6
    3280     441    3302     438    3352     425    3662     425    3720     440
    3868   448.2    3902   458.3    4099   460.7    4266   456.1    4570     466
#Mann= 7 ,-1,0
    1000     .08       0    2721     .05       0    2900     .12       0
    3133     .07       0    3302    .045       0    3662     .07       0
    3902     .05       0
#XS Ineff= 5 ,-1
    2420    2606   454.5    2606    2721   447.5    2900    3280   445.2
    3280    3750     438    4285    4570     480
Permanent Ineff=
       T       F       F       T       F
Bank Sta=2721,2900
XS Rating Curve= 0 ,0
Exp/Cntr=0.3,0.1

Type RM Length L Ch R = 1 ,66037   ,265,272,243
BEGIN DESCRIPTION:
This cross section corresponds to cross section 66037
of the non-georeferenced CDC model which was the source of this model.
END DESCRIPTION:
XS GIS Cut Line= 6
  2420373.650101 6976046.3809976 2419819.9149885 6975786.3592079
 2419266.1710172 6975526.3469327 2418596.2547062 6975495.1635961
 2417926.3370827  6975463.994039 2416670.4752935 6975405.5967403
#Sta/Elev= 30
    1000   487.3    1038   487.2    1094     470    1173   468.4    1528   466.3
    2015   460.7    2426   459.9    2492   439.4    2514   435.3    2556   435.3
    2613   450.7    2633   447.9    2708   449.1    2757     416    2797   415.8
    2843   423.2    2879   444.8    3039   446.9    3078   440.1    3177   440.7
    3345   437.6    3569   437.2    3691   439.6    3801   444.8    3861   458.1
    4143   459.4    4156   456.5    4199   457.7    4252   455.5    4822   465.1
#Mann= 4 ,-1,0
    1000     .07       0    2708    .055       0    2879      .1       0
    3861     .05       0
#XS Ineff= 3 ,-1
    2426    2708   449.1    2879    4271   444.8    4271    4822     480
Permanent Ineff=
       T       F       F
Bank Sta=2708,2879
XS Rating Curve= 0 ,0
Exp/Cntr=0.3,0.1

Type RM Length L Ch R = 1 ,65760   ,302,260.4,218
XS GIS Cut Line= 4
      2420340.23     6975965.957     2418991.532     6975231.001
      2416572.87     6975218.711      2416572.87     6975218.711
#Sta/Elev= 30
       0  485.41   37.53  478.47   42.08  469.88  231.01  465.22  360.65  466.06
   671.9   457.6  1344.1  459.12 1382.65  456.93 1470.61  438.21 1533.03  447.26
 1707.45  446.86 1717.45  433.38 1747.45  416.73 1847.45  416.91 1873.45  429.79
 1897.45  434.05 1915.45   444.6 1917.45  444.93 1995.45  449.09 2113.45  445.18
 2189.46  436.25 2431.46  435.68 2493.46  443.48 2543.46  436.07 2747.46  445.45
 2813.46  457.12 3103.47  460.31 3275.47   454.7 3433.47  462.01 3955.31  467.92
#Mann= 3 ,-1,0
       0     .07       0 1707.45    .055       0 1917.45     .06       0
Bank Sta=1707.45,1915.45
XS Rating Curve= 0 ,0
Exp/Cntr=0.3,0.1

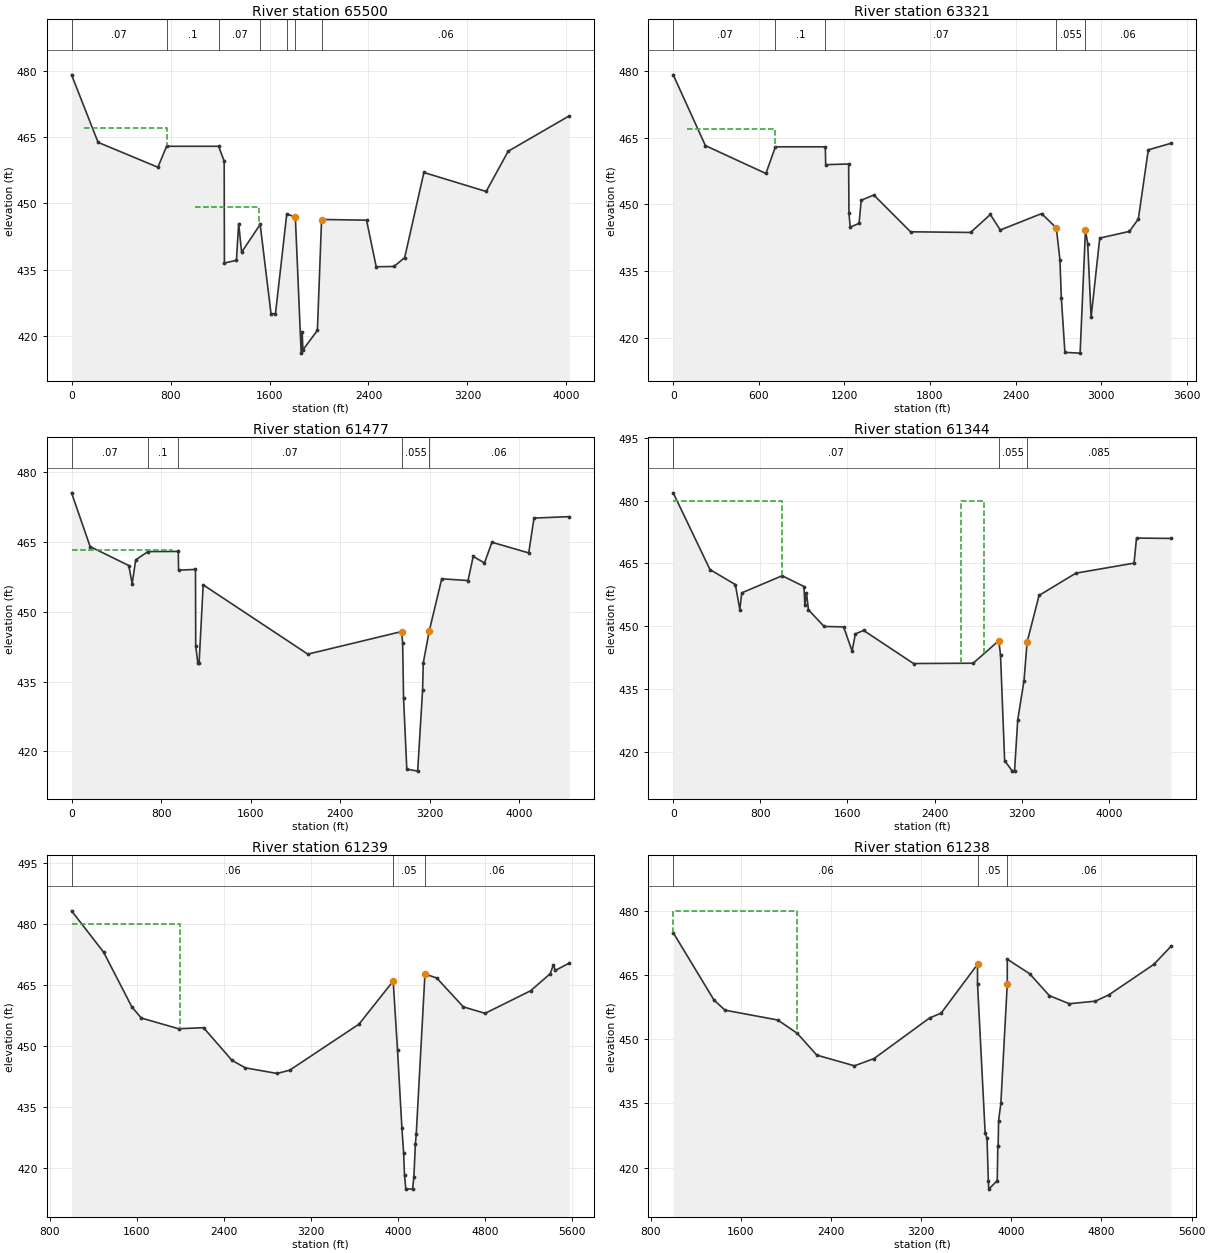
Type RM Length L Ch R = 1 ,65500   ,511.3,2179,1785
XS GIS Cut Line= 4
2421045.881304976976318.90643336  2420232.389229 6975737.3304346
  2419136.229348 6974953.67156882417464.841823746975019.11162293
#Sta/Elev= 30
       0  479.13  214.32  463.83  697.85  458.19  768.29  462.94 1188.67  462.94
 1233.67  459.57 1235.67  436.49 1332.67   437.1 1350.67  445.43 1374.67  438.94
  1524.5  445.23 1612.25     425 1648.27     425 1739.41  447.59  1807.9  446.94
 1808.91  446.88 1855.94  416.07 1863.95  420.95 1869.95   416.8 1987.04  421.21
 2020.71  446.17 2022.07  446.36 2384.34  446.19 2462.41  435.64 2606.52  435.71
 2692.58  437.71  2847.7     457 3351.09   452.7 3529.22  461.82  4022.8  469.83
#Mann= 7 ,-1,0
       0     .07       0  768.29      .1       0 1188.67     .07       0
  1524.5    .045       0 1739.41     .07       0  1807.9    .055       0
 2022.07     .06       0
#XS Ineff= 4 ,-1
     100  768.29   467.1    1000    1515   449.1    1515    1800   444.5
 2020.34    3500   444.8
Permanent Ineff=
       F       F       T       F
Bank Sta=1808.91,2020.71
XS Rating Curve= 0 ,0
Exp/Cntr=0.3,0.1

Type RM Length L Ch R = 1 ,63321   ,559,1845.5,1805
BEGIN DESCRIPTION:
Note:
- Sta.0 to 1600 updated with 2016 LIDAR.
END DESCRIPTION:
XS GIS Cut Line= 5
     2420303.952      6975732.37     2419920.675     6975324.966
     2419474.108     6974671.059     2417945.272     6973176.737
     2417945.272     6973176.737
#Sta/Elev= 30
       0  479.13  225.58  463.21  649.89  456.94  716.47  462.94  1066.3  462.94
 1068.72  458.92 1229.72  459.08 1232.14  448.02 1240.61  444.86  1302.9  445.73
 1318.01  450.93 1406.42   452.1 1663.72  443.83 2084.56  443.68 2223.15  447.72
  2292.9  444.23 2582.33  447.92  2685.8   444.7 2710.97   437.5 2720.76     429
 2745.92   416.7 2852.43  416.54 2889.88  444.23 2905.62  441.15 2929.51  424.59
 2990.03  442.41 3197.52  443.91 3260.48  446.69 3330.39  462.25 3489.03  463.73
#Mann= 5 ,-1,0
       0     .07       0  716.47      .1       0  1066.3     .07       0
  2685.8    .055       0 2889.88     .06       0
#XS Ineff= 1 ,-1
     100 716.469     467
Permanent Ineff=
       F
Bank Sta=2685.8,2889.88
XS Rating Curve= 0 ,0
Exp/Cntr=0.3,0.1

Type RM Length L Ch R = 1 ,61477   ,255,131.5,359
XS GIS Cut Line= 6
     2420281.179      6975672.93     2419961.206     6975297.601
     2419668.601     6974822.975     2419535.963     6974488.464
     2419448.391     6972329.063     2419050.487     6971550.205
#Sta/Elev= 30
       0  475.52  166.08  463.98  511.09  459.92  541.64  456.01  573.35  461.12
  682.97  462.91  953.94  462.94  956.29  458.92 1107.55  459.08  1109.7   442.7
 1128.57  438.94 1139.79  438.94 1176.33  455.77 2111.34  440.89 2949.23  445.74
 2959.03  443.34 2967.04  431.48 2996.06  416.21 3093.15  415.78  3137.2  433.18
  3143.2  439.02 3197.46  445.95 3308.35  457.07 3543.25  456.69  3589.3  461.86
 3690.36  460.47 3756.75  464.91 4085.61  462.62 4132.84   470.1 4447.94  470.41
#Mann= 5 ,-1,0
       0     .07       0  682.97      .1       0  953.94     .07       0
 2949.23    .055       0 3197.46     .06       0
#XS Ineff= 2 , 0
          899.26  463.35
Permanent Ineff=
       F       F
Bank Sta=2949.23,3197.46
XS Rating Curve= 0 ,0
Exp/Cntr=0.3,0.1

Type RM Length L Ch R = 1 ,61344   ,105,105,105
BEGIN DESCRIPTION:
This cross section corresponds to cross section 61344 of the non-georeferenced CDC model which was the source of this model.
END DESCRIPTION:
XS GIS Cut Line= 6
  2420353.863326 6975773.0377739 2419772.2940207 6974727.1129668
 2419673.1288647 6974425.1109462 2419564.9499472  6972166.854964
 2419411.6950044 6971788.2251438 2419202.5428637 6971467.2021638
#Sta/Elev= 30
       0  481.86   337.6  463.53  570.68  459.94  611.87  453.96  629.03  457.96
 1000.65  462.05 1200.76  459.48 1209.18  455.02 1223.91  457.94 1241.83  453.91
    1386  449.93 1564.87  449.83 1642.58  444.06 1672.85  448.15 1748.54  448.99
 2206.72  441.08 2754.79  441.15  2989.8  446.53  3005.8  443.17  3043.8  417.86
 3114.81  415.37 3134.81  415.46 3163.81  427.58 3221.81  437.02 3249.81  446.18
 3359.82  457.35 3698.16  462.67 4231.96  465.06 4254.94  471.05 4570.79  470.97
#Mann= 3 ,0,0
       0     .07       0  2989.8    .055       0 3249.81    .085       0
#XS Ineff= 3 ,-1
       0    1000     480    1000    2640     441    2640    2850     480
Permanent Ineff=
       T       F       T
Bank Sta=2989.8,3249.81
XS Rating Curve= 0 ,0
Exp/Cntr=0.3,0.1

Type RM Length L Ch R = 1 ,61239   ,1,1,1
BEGIN DESCRIPTION:
Cross-section recut part of:
CDC GP092922-1 Roy Orr LGD Holdings Industrial Development
Cross-sections 61239 - 65760
Project located in LOB.
END DESCRIPTION:
XS GIS Cut Line= 6
  2420457.213843 6975777.6361889 2419875.6445358 6974731.7113828
 2419776.4793798 6974429.7093622 2419668.3004623   6972171.45338
 2419515.0455195 6971792.8235598 2419305.8933787 6971471.8005798
#Sta/Elev= 30
    1000  483.15 1294.56     473 1553.54  459.58 1640.11  456.83 1983.14  454.19
    2213  454.44 2474.02  446.43 2596.88  444.58  2889.5   443.2  3005.5  444.02
 3641.53  455.32 3955.54   465.9 3995.54  448.85 4035.54  429.86 4051.54  423.71
 4059.54  418.25 4071.54  414.84 4133.54  414.79 4145.55  417.67 4159.59  425.94
 4167.55  428.36 4247.55  467.64 4355.55  466.65 4600.25  459.56 4800.25  457.97
 5218.83  463.52 5398.36   467.7 5426.96  469.81 5446.06  468.52 5573.56  470.31
#Mann= 3 ,0,0
    1000     .06       0 3955.54     .05       0 4247.55     .06       0
#XS Ineff= 2 , 0
            2000     480    4300           448.4
Permanent Ineff=
       T       F
Bank Sta=3955.54,4247.55
XS Rating Curve= 0 ,0
Exp/Cntr=0.5,0.3

Type RM Length L Ch R = 1 ,61238   ,80,80,80
BEGIN DESCRIPTION:
This cross section corresponds to cross section 61238 of the non-georeferenced CDC model which was the source of this model.
END DESCRIPTION:
XS GIS Cut Line= 6
  2420314.953696  6975521.336444 2419876.5254396 6974731.3990475
 2419777.4774093 6974429.7536534 2419669.2984918 6972171.4976712
  2419516.043549 6971792.8678511 2419231.2531081 6971355.7558644
#Sta/Elev= 30
    1000   474.9    1361   459.2    1459   456.8    1928   454.5    2100   451.4
    2274   446.3    2608   443.8    2782   445.5    3276     455    3377   456.1
    3700   467.5    3700     463    3768     428    3784     427    3796     417
    3800     415    3875     417    3880     425    3883     425    3887     431
    3907     435    3964     463    3964   468.7    4163   465.3    4337   460.2
    4514   458.3    4746   458.9    4867   460.4    5265   467.5    5416   471.7
#Mann= 3 ,0,0
    1000     .06       0    3700     .05       0    3964     .06       0
#XS Ineff= 2 , 0
            2100     480    3964           458.3
Permanent Ineff=
       T       F
Bank Sta=3700,3964
XS Rating Curve= 0 ,0
Exp/Cntr=0.3,0.1

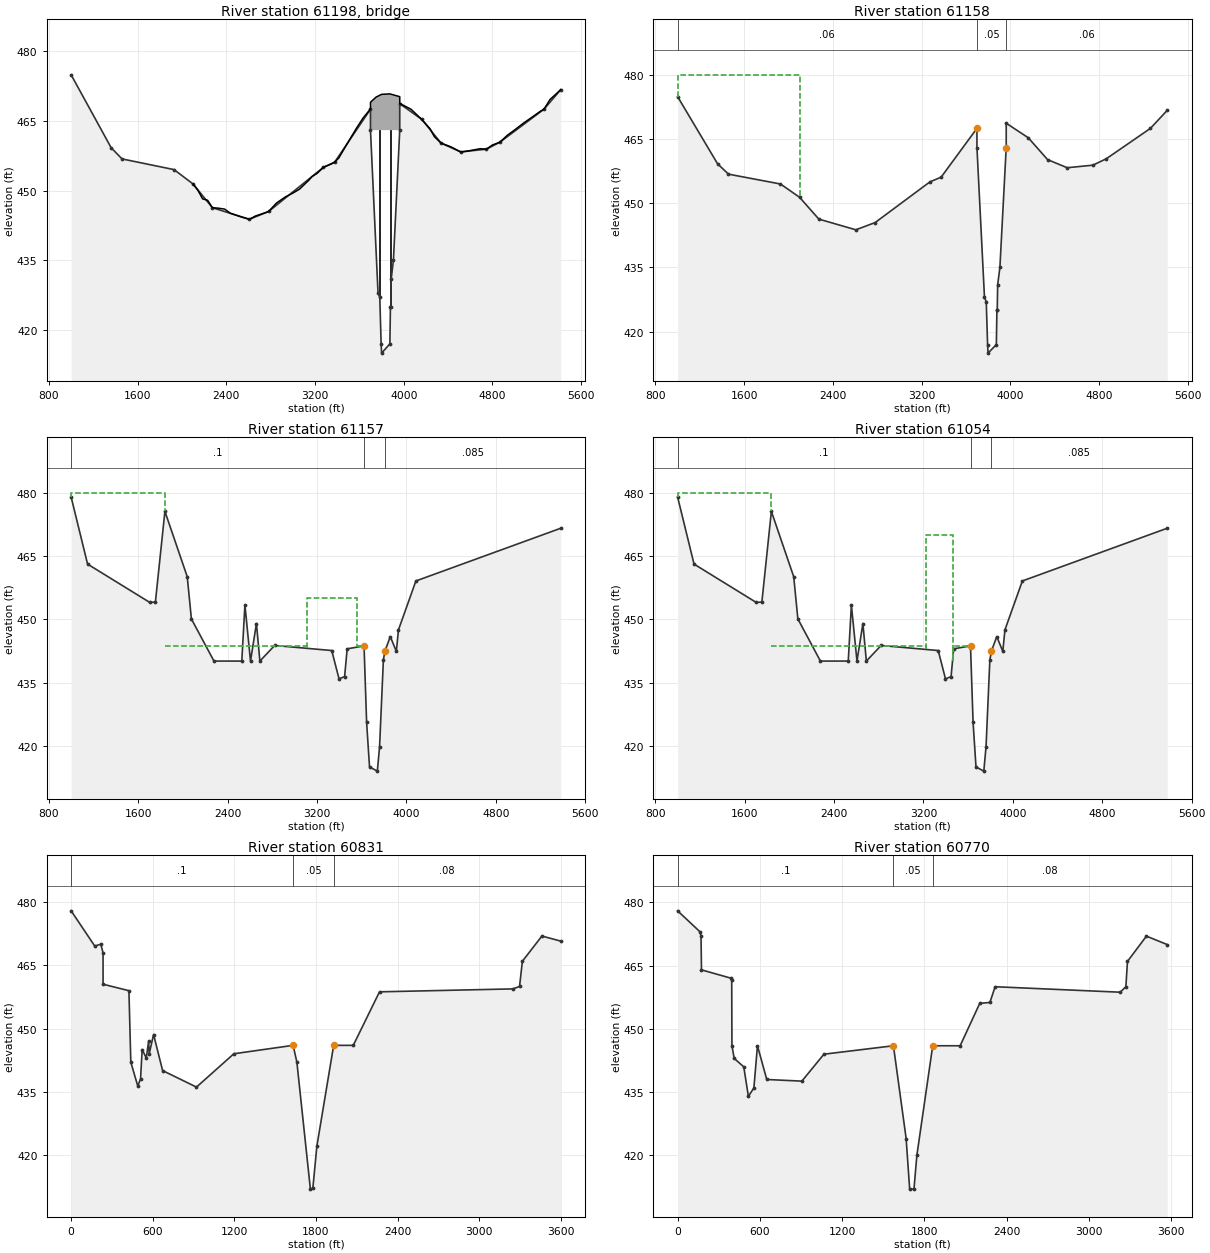
Type RM Length L Ch R = 3 ,61198   ,,,
BEGIN DESCRIPTION:
Roy Orr Boulevard/NW 19th Street
END DESCRIPTION:
Node Name=NW 19th Street
Bridge Culvert--1,0,-1,-1, 0
Deck Dist Width WeirC Skew NumUp NumDn MinLoCord MaxHiCord MaxSubmerge Is_Ogee
1,78,2.6,0, 57, 57, , , 0.95, 0, ,,,
    2100    2142    2186    2231    2274    2328    2384    2437    2524    2608
    2661    2749    2782    2852    2931    3004    3060    3143    3173    3219
    3276    3354    3377    3414    3503    3576    3633    3698    3700    3700
    3750    3800    3875    3964    3964    3967    4065    4163    4237    4276
    4337    4426    4514    4578    4645    4690    4746    4800    4867    4935
    5004    5080    5158    5229    5265    5320    5416
   451.4   450.1   448.2   447.9   446.3   446.2     446   445.1   444.4   443.8
   444.5   445.2   445.5   447.3   448.6   449.5   450.3   452.2     453   453.7
     455   455.8   456.1     457   460.6   463.5   465.6   467.5   467.5     469
   470.1   470.7   470.8   470.2   468.7   468.7   467.5   465.3   463.3   461.6
   460.2   459.4   458.3   458.5   458.8     459   458.9   459.8   460.4   461.9
   463.1   464.5   465.8     467   467.5   469.6   471.7
   451.4   450.1   448.2   447.9   446.3   446.2     446   445.1   444.4   443.8
   444.5   445.2   445.5   447.3   448.6   449.5   450.3   452.2     453   453.7
     455   455.8   456.1     457   460.6   463.5   465.6   467.5   467.5     463
     463     463     463     463   468.7   468.7   467.5   465.3   463.3   461.6
   460.2   459.4   458.3   458.5   458.8     459   458.9   459.8   460.4   461.9
   463.1   464.5   465.8     467   467.5   469.6   471.7
    2100    2142    2186    2231    2274    2328    2384    2437    2524    2608
    2661    2749    2782    2852    2931    3004    3060    3143    3173    3219
    3276    3354    3377    3414    3503    3576    3633    3698    3700    3700
    3750    3800    3875    3964    3964    3967    4065    4163    4237    4276
    4337    4426    4514    4578    4645    4690    4746    4800    4867    4935
    5004    5080    5158    5229    5265    5320    5416
   451.4   450.1   448.2   447.9   446.3   446.2     446   445.1   444.4   443.8
   444.5   445.2   445.5   447.3   448.6   449.5   450.3   452.2     453   453.7
     455   455.8   456.1     457   460.6   463.5   465.6   467.5   467.5     469
   470.1   470.7   470.8   470.2   468.7   468.7   467.5   465.3   463.3   461.6
   460.2   459.4   458.3   458.5   458.8     459   458.9   459.8   460.4   461.9
   463.1   464.5   465.8     467   467.5   469.6   471.7
   451.4   450.1   448.2   447.9   446.3   446.2     446   445.1   444.4   443.8
   444.5   445.2   445.5   447.3   448.6   449.5   450.3   452.2     453   453.7
     455   455.8   456.1     457   460.6   463.5   465.6   467.5   467.5     463
     463     463     463     463   468.7   468.7   467.5   465.3   463.3   461.6
   460.2   459.4   458.3   458.5   458.8     459   458.9   459.8   460.4   461.9
   463.1   464.5   465.8     467   467.5   469.6   471.7
Pier Skew, UpSta & Num, DnSta & Num=  ,3782.5, 2 ,3782.5, 2 , 0 , 0 , 0 ,,
       3       3
     400     464
       3       3
     400     464
Pier Skew, UpSta & Num, DnSta & Num=  ,3881.5, 2 ,3881.5, 2 , 0 , 0 , 0 ,,
       3       3
     400     464
       3       3
     400     464
BR Coef= 1 , 0 , 0 ,1.05, 0 ,,,0.8,-1,0.5,1,
WSPro=,,,, 1 ,,,, 0 ,,,, 0 ,,,,-1 ,-1 ,-1 , 0 , 0 , 0 , 0 , 0
BC Design=,, 0 ,, 0 ,,,,,,
BC HTab HWMax=471.7
BC Use User HTab Curves=0
BC User HTab FreeFlow(D)= 0

Type RM Length L Ch R = 1 ,61158   ,1,1,1
BEGIN DESCRIPTION:
This cross section corresponds to cross section 61158 of the non-georeferenced CDC model which was the source of this model.
END DESCRIPTION:
XS GIS Cut Line= 6
  2420411.951534 6975562.1680552 2419847.8857331 6974348.3325564
 2419793.7959462 6972446.1683817 2419739.7058313 6972090.0765742
 2419573.0805084 6971657.7516515 2419379.3362925 6971369.8189847
#Sta/Elev= 30
    1000   474.9    1361   459.2    1459   456.8    1928   454.5    2100   451.4
    2274   446.3    2608   443.8    2782   445.5    3276     455    3377   456.1
    3700   467.5    3700     463    3768     428    3784     427    3796     417
    3800     415    3875     417    3880     425    3883     425    3887     431
    3907     435    3964     463    3964   468.7    4163   465.3    4337   460.2
    4514   458.3    4746   458.9    4867   460.4    5265   467.5    5416   471.7
#Mann= 3 ,0,0
    1000     .06       0    3700     .05       0    3964     .06       0
#XS Ineff= 2 , 0
            2100     480    3964           458.3
Permanent Ineff=
       T       F
Bank Sta=3700,3964
XS Rating Curve= 0 ,0
Exp/Cntr=0.3,0.1

Type RM Length L Ch R = 1 ,61157   ,104,104,104
BEGIN DESCRIPTION:
This cross section corresponds to cross section 61157 of the non-georeferenced CDC model which was the source of this model.
END DESCRIPTION:
XS GIS Cut Line= 6
  2420356.356172 6975448.9612607 2419848.8840907 6974348.3768477
 2419794.7943038  6972446.212673 2419740.7041889 6972090.1208655
 2419573.9272915 6971657.4019147 2419329.7361788 6971293.5089417
#Sta/Elev= 30
    1000     479    1147   463.1    1704     454    1754   454.1    1839   475.6
    2039   460.1    2076   450.1    2278   440.1    2527   440.1    2555   453.4
    2605   440.1    2658     449    2689   440.1    2821   443.8    3332   442.6
    3397   435.9    3447   436.4    3470     443    3621   443.7    3644   425.6
    3670     415    3740     414    3760   419.8    3794   440.3    3807   442.4
    3856   445.9    3910   442.4    3929   447.5    4085   459.1    5381   471.6
#Mann= 3 ,0,0
    1000      .1       0    3621     .05       0    3807    .085       0
#XS Ineff= 5 ,-1
    1000    1839     480    1839    3110   443.7    3110    3560     455
    3560    3621   443.7    3807    5381   442.4
Permanent Ineff=
       T       F       T       F       F
Bank Sta=3621,3807
XS Rating Curve= 0 ,0
Exp/Cntr=0.3,0.1

Type RM Length L Ch R = 1 ,61054   ,174,64,145
BEGIN DESCRIPTION:
This cross section corresponds to cross section 61054 of the non-georeferenced CDC model which was the source of this model.
END DESCRIPTION:
XS GIS Cut Line= 6
  2420460.065865 6975453.5752782  2419952.593857 6974352.9910117
 2419898.5040702  6972450.826837 2419844.4139552 6972094.7350295
 2419677.6370578 6971662.0160787 2419433.4459452 6971298.1231057
#Sta/Elev= 30
    1000     479    1147   463.1    1704     454    1754   454.1    1839   475.6
    2039   460.1    2076   450.1    2278   440.1    2527   440.1    2555   453.4
    2605   440.1    2658     449    2689   440.1    2821   443.8    3332   442.6
    3397   435.9    3447   436.4    3470     443    3621   443.7    3644   425.6
    3670     415    3740     414    3760   419.8    3794   440.3    3807   442.4
    3856   445.9    3910   442.4    3929   447.5    4085   459.1    5381   471.6
#Mann= 3 ,0,0
    1000      .1       0    3621     .05       0    3807    .085       0
#XS Ineff= 5 ,-1
    1000    1839     480    1839    3220   443.7    3220    3460     470
    3460    3621   443.7    3807    5381   442.4
Permanent Ineff=
       T       F       T       F       F
Bank Sta=3621,3807
XS Rating Curve= 0 ,0
Exp/Cntr=0.3,0.1

Type RM Length L Ch R = 1 ,60831   ,88,60,45
XS GIS Cut Line= 6
  2420276.5518396974651.243947642420141.135172816974018.43144765
 2420122.90600616972450.72311433 2420052.59350616972062.70228098
2419834.277533926971469.38630877 2419634.62475616971180.75783654
#Sta/Elev= 30
       0     478  173.65  469.62  218.23  470.06  234.62     468   234.8  460.54
  424.75     459   438.8     442  489.84  436.33  510.21     438  522.32     445
   552.4     443  569.77     447  573.98     444  606.09  448.58  672.52     440
  921.53  436.07 1196.42     444 1632.08     446 1659.78     442 1759.11   411.8
 1777.41  412.08 1806.67     422  1930.2     446 2074.33     446 2267.28  458.73
 3247.35  459.43 3296.92     460 3317.83     466 3461.29     472 3599.73   470.8
#Mann= 3 ,0,0
       0      .1       0 1632.08     .05       0  1930.2     .08       0
#XS Ineff= 2 , 0
         1632.08     446
Permanent Ineff=
       F       F
Bank Sta=1632.08,1930.2
XS Rating Curve= 0 ,0
Exp/Cntr=0.3,0.1

Type RM Length L Ch R = 1 ,60770   ,53,45,36
XS GIS Cut Line= 6
  2420372.4719786974585.705753192420183.669894996973570.08075319
2420179.32961726 6972439.43839212420075.16295055  6972031.452281
2419858.149061656971428.153669862419669.346978346971141.69533655
#Sta/Elev= 30
       0     478  164.16     473  170.76     472  174.08     464  391.84     462
  394.52  461.51  396.17     446   412.7     443  482.42     441  516.14     434
  556.25     436  582.37     446  650.14     438  906.05  437.61 1067.03     444
 1573.82     446 1666.53     424 1692.23     412 1723.56     412 1744.73     420
 1860.34     446  2060.3     446 2203.57  456.07 2277.17  456.26 2315.41     460
 3227.46   458.7  3268.9     460 3280.51     466 3418.75     472 3570.18     470
#Mann= 3 ,0,0
       0      .1       0 1573.82     .05       0 1860.34     .08       0
#XS Ineff= 2 , 0
         1573.82     446
Permanent Ineff=
       F       F
Bank Sta=1573.82,1860.34
XS Rating Curve= 0 ,0
Exp/Cntr=0.3,0.1

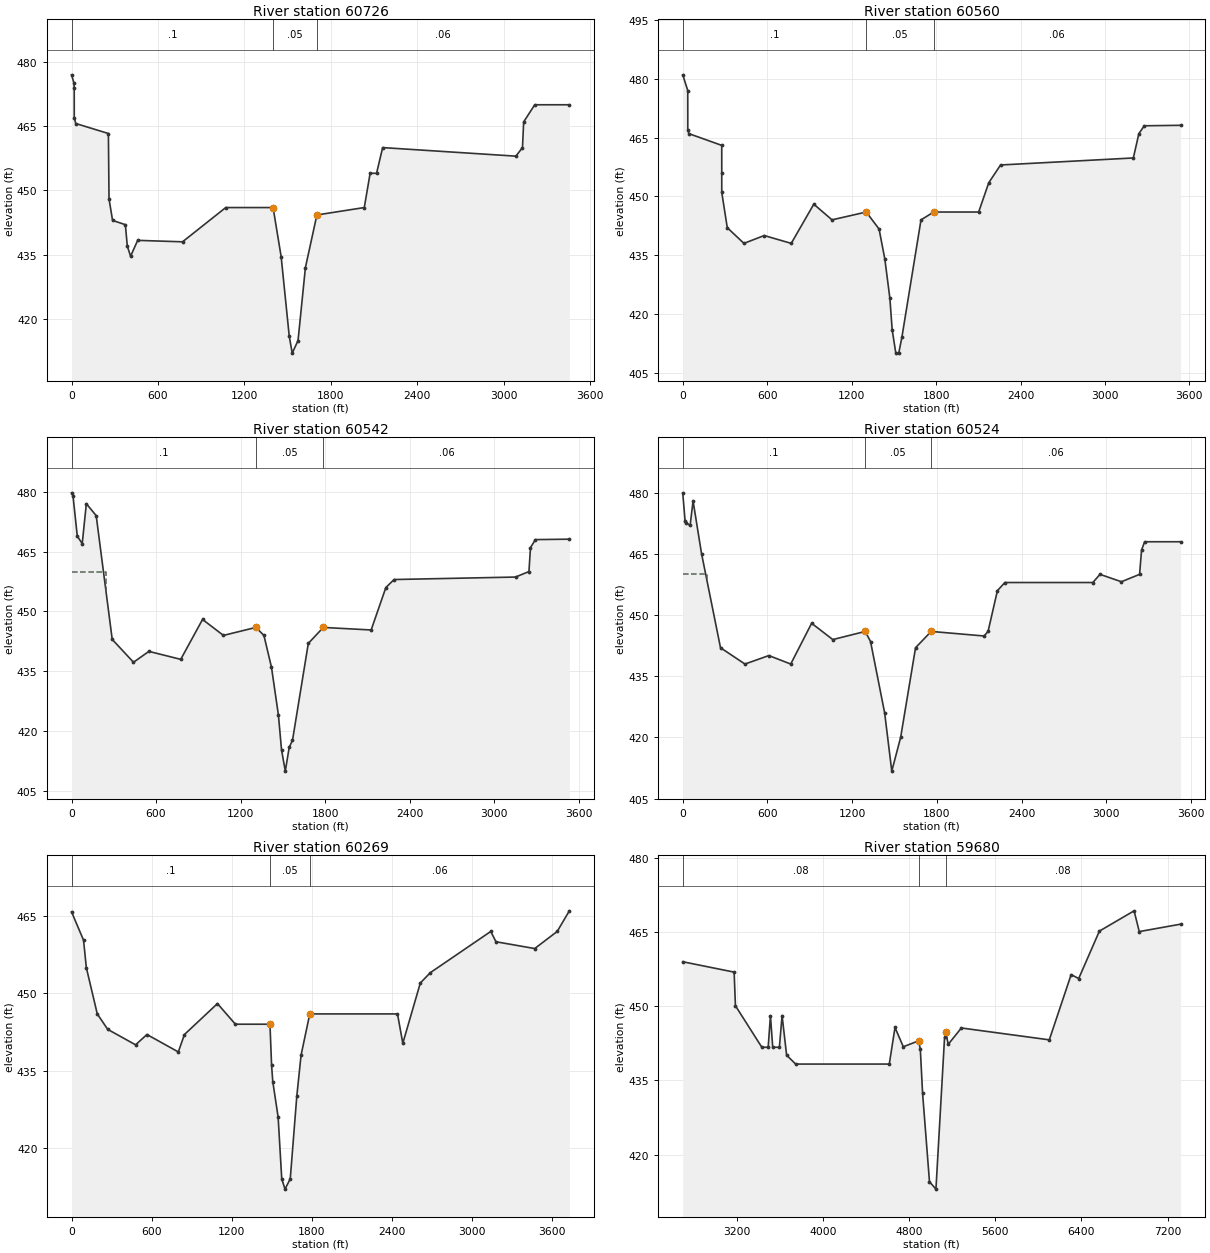
Type RM Length L Ch R = 1 ,60726   ,213,165,125
XS GIS Cut Line= 5
    2420407.19426974418.605058762420229.242811686973457.23353098
2420227.07267281  6972402.5460312419912.402533896971449.85505877
2419708.409478376971087.44186433
#Sta/Elev= 30
       0  476.99    17.3     475   18.61     474   18.79     467    29.1  465.62
  255.82  463.29  260.28     448   284.9     443  373.65     442   387.2     437
   409.9  434.63  459.22  438.34  770.72     438 1070.87     446 1399.62     446
 1455.66  434.54 1511.77     416  1532.5  412.01 1572.96  414.95 1624.22     432
 1703.91  444.27 2033.04     446 2073.65     454 2118.35     454 2160.61     460
 3086.09     458 3131.74     460 3140.01     466 3216.87     470 3457.15     470
#Mann= 3 ,0,0
       0      .1       0 1399.62     .05       0 1703.91     .06       0
#XS Ineff= 2 , 0
         1399.62     446
Permanent Ineff=
       F       F
Bank Sta=1399.62,1703.91
XS Rating Curve= 0 ,0
Exp/Cntr=0.3,0.1

Type RM Length L Ch R = 1 ,60560   ,20,19,16
XS GIS Cut Line= 6
  2420654.5900336974405.584225432420635.058783926974258.01478098
 2420609.01711726974034.490475432420405.024061686973266.26130876
2420372.471978376972300.549503192419862.48933944 6970994.1258921
#Sta/Elev= 30
       0     481   35.62     477   35.84     467   43.36     466  277.09     463
  277.23     456  277.24     451  316.47     442  434.77     438   578.8     440
  770.88     438  931.21     448 1060.47     444 1303.94     446 1394.97  441.65
 1435.86     434 1471.75     424 1487.89     416 1513.83     410 1534.67     410
 1556.88     414 1692.94     444 1783.37     446 2102.54     446  2174.3  453.47
 2258.18     458 3201.62  459.79 3240.83     466 3279.35     468 3536.81  468.12
#Mann= 3 ,0,0
       0      .1       0 1303.94     .05       0 1783.37     .06       0
#XS Ineff= 2 , 0
         1303.94     446
Permanent Ineff=
       F       F
Bank Sta=1303.94,1783.37
XS Rating Curve= 0 ,0
Exp/Cntr=0.3,0.1

Type RM Length L Ch R = 1 ,60542   ,20,17,13
XS GIS Cut Line= 5
  2420697.9928116974375.202280982420656.76017281  6974023.639781
2420422.385172816973229.368947652420392.003228376972287.52866986
2419910.232395056970991.95575321
#Sta/Elev= 30
       0  479.72   10.11     479   40.85  468.85   75.73     467  104.96     477
     175     474  288.73     443   439.8  437.27   549.3     440  775.25     438
  930.15     448 1078.37     444 1308.86     446  1365.9     444 1419.71     436
 1469.02     424 1490.76  415.39 1517.69     410 1545.74     416 1568.77   417.7
 1681.09     442 1787.63     446  2127.3  445.36 2231.82     456 2290.31     458
 3152.41  458.62 3247.73     460 3258.78     466 3293.69     468 3534.58  468.11
#Mann= 3 ,0,0
       0      .1       0 1308.86     .05       0 1787.63     .06       0
#XS Ineff= 2 ,-1
       0   245.7     460   245.7 1308.86     446
Permanent Ineff=
       F       F
Bank Sta=1308.86,1787.63
XS Rating Curve= 0 ,0
Exp/Cntr=0.3,0.1

Type RM Length L Ch R = 1 ,60524   ,267,254,195
XS GIS Cut Line= 5
  2420786.9685066974349.160614312420606.846978346973724.16061433
2420439.746283926973218.518253192420402.853922816972237.61547543
2419918.912950556970978.93491988
#Sta/Elev= 30
       0     480    16.7     473    24.1  472.62   52.28     472   73.12     478
  133.09   465.1  267.49     442  440.71     438  609.94  440.08  764.92     438
  913.07     448 1062.89     444 1292.82     446 1330.19  443.52 1430.22     426
 1480.62  411.73 1543.42     420    1649     442 1759.69     446 2134.45  444.88
 2162.69     446 2228.79     456 2281.76     458 2904.78     458  2955.4     460
 3107.27  458.19 3235.82     460 3250.02     466  3271.8     468 3525.87     468
#Mann= 3 ,0,0
       0      .1       0 1292.82     .05       0 1759.69     .06       0
#XS Ineff= 2 ,-1
       0   168.8     460   168.8 1292.82     446
Permanent Ineff=
       F       F
Bank Sta=1292.82,1759.69
XS Rating Curve= 0 ,0
Exp/Cntr=0.3,0.1

Type RM Length L Ch R = 1 ,60269   ,425,369,245
BEGIN DESCRIPTION:
-------------------------------------------------------------
CDC GP020915-1 Elmore Drill Site
Cross-section 60269 - 60831.  Project in LOB.
------------------------------------------------------------
END DESCRIPTION:
XS GIS Cut Line= 4
  2421220.9962836974405.584225432420695.822672786973172.94533654
2420654.590033896972192.042558772420181.499756136970872.59811433
#Sta/Elev= 30
       0   465.8   90.04  460.29  110.66     455  192.82     446   271.1     443
  480.15     440  565.36     442  800.66  438.62  846.61     442 1094.09     448
 1228.47     444 1487.88     444 1500.14     436 1508.98  432.88 1549.08     426
 1576.25     414 1600.67     412 1640.12     414 1689.05     430 1721.23     438
 1786.51     446 2444.25     446 2484.14   440.3 2615.56     452 2690.61     454
 3143.78     462 3182.84     460 3473.32  458.68 3642.03     462    3733     466
#Mann= 3 ,0,0
       0      .1       0 1487.88     .05       0 1786.51     .06       0
#XS Ineff= 2 , 0
         1487.88     444 1786.51             446
Permanent Ineff=
       F       F
Bank Sta=1487.88,1786.51
XS Rating Curve= 0 ,0
Exp/Cntr=0.3,0.1

Type RM Length L Ch R = 1 ,59680   ,419,812,882
BEGIN DESCRIPTION:
59680
END DESCRIPTION:
XS GIS Cut Line= 4
   2421781.16304 6974582.5035938 2421409.6450831  6972979.853912
 2421108.0761325  6972546.346905 2420353.9240975 6970621.9219481
#Sta/Elev= 30
    2700     459    3177   456.9    3189   450.1    3434   441.7    3493   441.7
    3514   448.1    3535   441.7    3597   441.7    3622   448.1    3664   440.1
    3748   438.3    4617   438.3    4670   445.7    4747   441.8    4889     443
    4905   441.3    4926   432.4    4990   414.5    5050     413    5130   443.7
    5142   444.7    5164   442.3    5286   445.6    6102   443.2    6305   456.4
    6375   455.6    6567   465.2    6889   469.3    6937   465.1    7320   466.6
#Mann= 3 ,0,0
    2700     .08       0    4889     .05       0    5142     .08       0
#XS Ineff= 3 ,-1
    2700    3622   448.1    3622    4659   440.1    5142    7320   444.7
Permanent Ineff=
       T       T       F
Bank Sta=4889,5142
XS Rating Curve= 0 ,0
Exp/Cntr=0.3,0.1