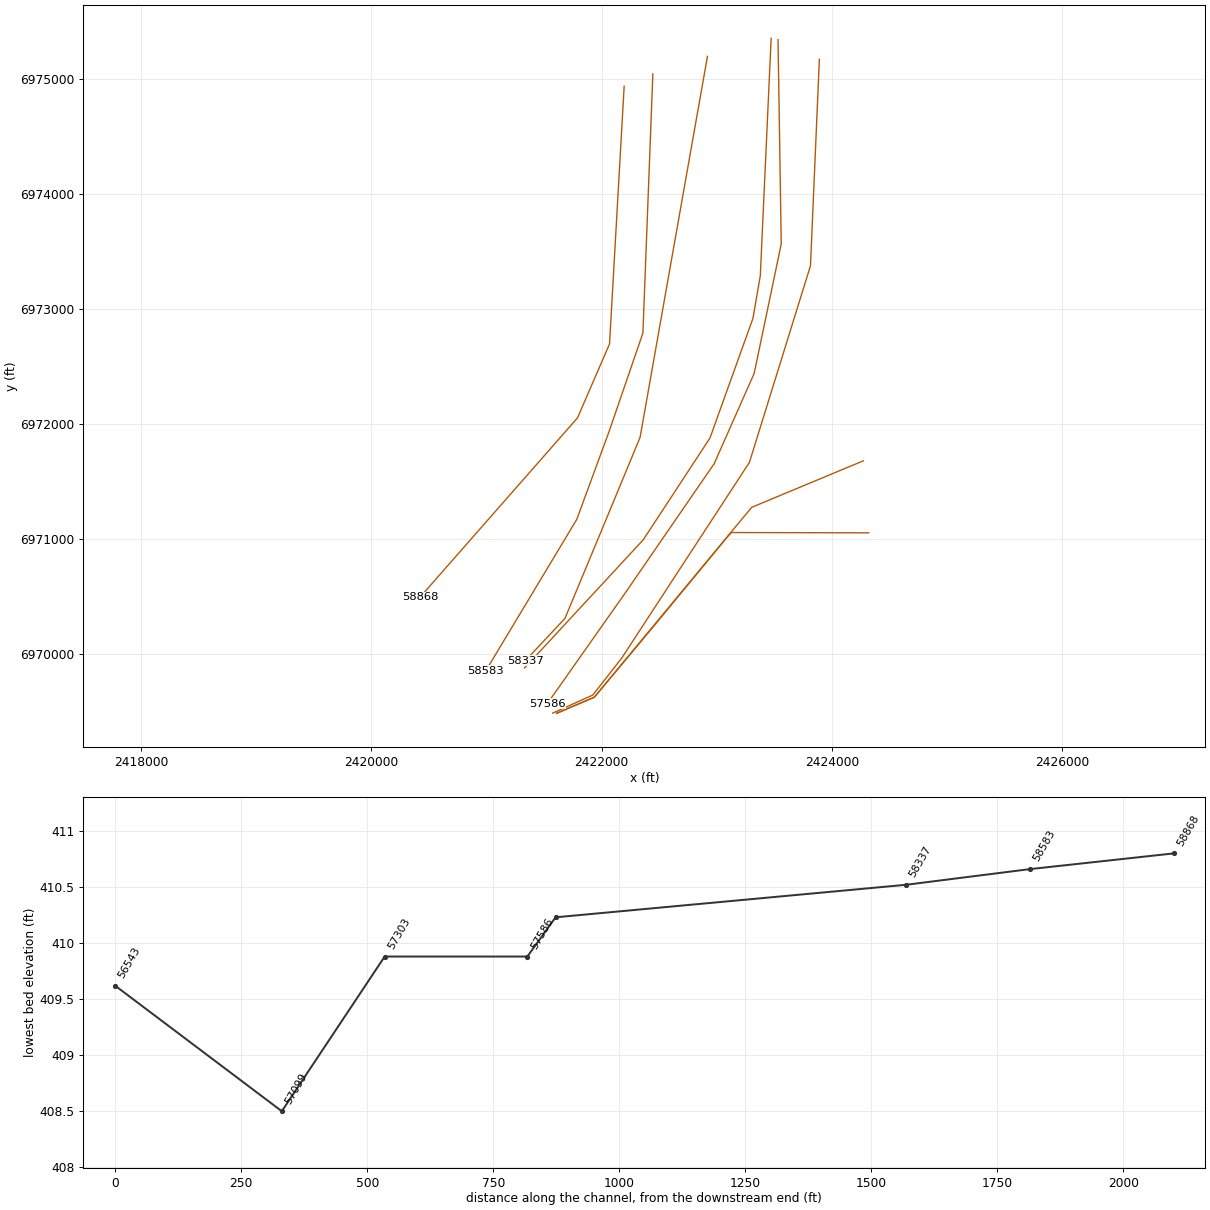
HEC-RAS study CDC_Consolidated_Model.prj: Upper Trinity CDC Consolidated Model

--- CDC_Consolidated_Model.g12 (geometry) --- (continued)

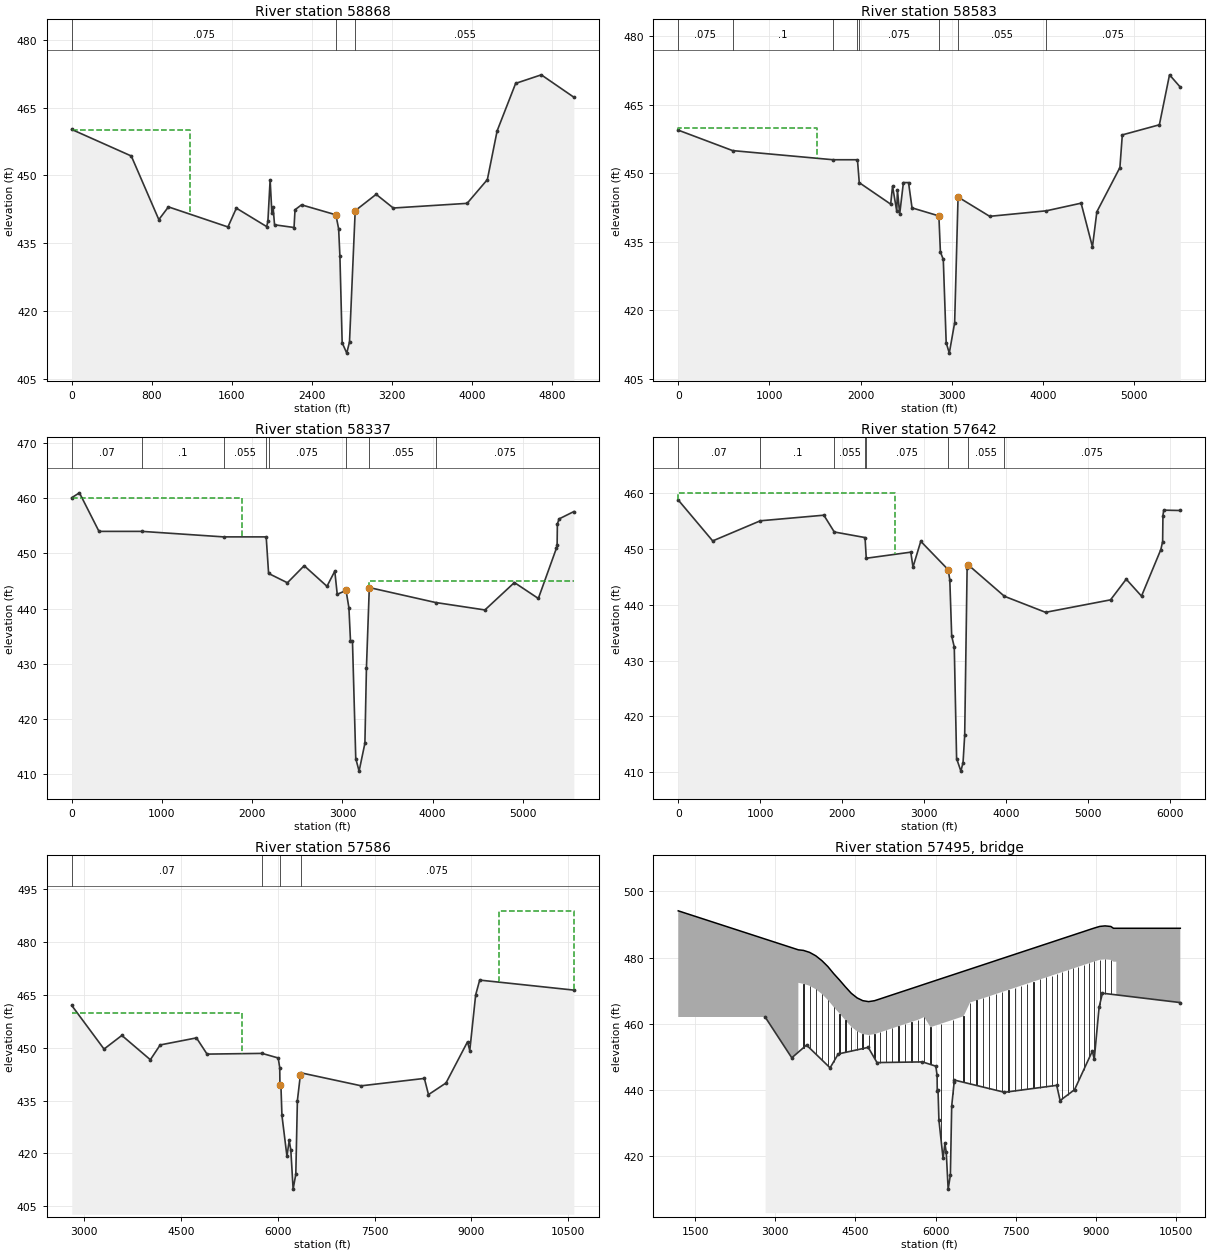
Type RM Length L Ch R = 1 ,58868   ,267,285,457
BEGIN DESCRIPTION:
XS added for transition to natural ground.
2009 lidar
END DESCRIPTION:
XS GIS Cut Line= 5
  2422196.122184 6974935.7709319 2422173.2751176 6974533.0919472
 2422069.1083311 6972697.1543461 2421791.3306715 6972054.7930981
 2420424.1431171 6970496.6334847
#Sta/Elev= 30
       0  460.15  594.41   454.3  869.61  440.26  965.45  443.07 1559.99  438.64
 1644.05  442.79 1946.76  438.72 1958.98  439.87 1981.33  449.06 1998.55  441.82
 2010.85  443.02 2025.36  439.12 2220.15  438.52 2230.02  442.44 2294.81  443.52
 2637.96  441.32 2665.58  438.24 2678.28  432.23 2700.86  413.09 2746.74   410.8
 2774.16  413.28 2831.06  442.23 3040.34  445.84 3211.19  442.82 3948.86  443.85
 4151.14  449.09 4248.83  459.85 4433.67  470.32 4689.82  472.21    5015  467.27
#Mann= 3 ,-1,0
       0    .075       0 2637.96     .05       0 2831.06    .055       0
#XS Ineff= 2 , 0
            1183     460
Permanent Ineff=
       F       F
Bank Sta=2637.96,2831.06
XS Rating Curve= 0 ,0
Exp/Cntr=0.3,0.1

Type RM Length L Ch R = 1 ,58583   ,264,246,261
BEGIN DESCRIPTION:
XS 57642 - 58583 represent Oakdale.
XS 58583 added to represent Oakdale STA 581 - 1924
2009 lidar with 2001 in LOB STA 0 to 2153
END DESCRIPTION:
XS GIS Cut Line= 5
  2422445.340846   6975043.90687  2422358.898762  6972791.866427
  2422065.496134   6971936.83172  2421784.974057  6971172.670847
   2420995.04355  6969857.566849
#Sta/Elev= 30
       0  459.48   596.5     455  1697.1     453  1965.4     453  1985.2  447.98
 2329.53  443.28 2350.14   447.2 2396.13  441.75 2403.82  446.38 2428.59  441.13
 2469.19     448 2525.51     448 2563.86  442.46 2858.32   440.7 2874.83  432.82
 2906.61  431.16 2938.39  412.94 2972.48  410.66 3031.16  417.32 3068.52  444.84
 3415.29  440.61 4036.73  441.82 4418.04  443.49 4542.33  433.92  4590.7  441.61
 4843.36  451.29 4869.79  458.44  5276.2  460.65 5387.42  471.59  5505.8  468.89
#Mann= 8 ,-1,0
       0    .075       0   596.5      .1       0  1697.1    .055       0
  1965.4     .06       0  1985.2    .075       0 2858.32     .05       0
 3068.52    .055       0 4036.73    .075       0
#XS Ineff= 2 , 0
            1525     460
Permanent Ineff=
       F       F
Bank Sta=2858.32,3068.52
XS Rating Curve= 0 ,0
Exp/Cntr=0.3,0.1

Type RM Length L Ch R = 1 ,58337   ,635,695,520
BEGIN DESCRIPTION:
XS 57642 - 58583 represent Oakdale.
XS 58337 present in effective. Fill STA 2828 - 4169
2009 lidar with 2001 in LOB STA 2062 to 4401
END DESCRIPTION:
XS GIS Cut Line= 5
  2422919.422247  6975195.555189  2422334.451961  6971885.196981
  2422075.859302  6971259.801578  2421682.070719  6970311.927161
  2421338.760054  6969945.227107
#Sta/Elev= 30
       0  460.11   84.92  460.99  301.66     454  778.34     454 1682.49     453
 2154.99     453 2181.57  446.37 2390.08  444.68 2575.94  447.77 2828.52  444.04
  2915.4  446.79 2942.19  442.59 3040.19  443.28 3071.72  440.15 3089.22  434.15
 3111.23  434.09  3147.7  412.81 3184.61  410.52 3249.04  415.58 3266.07  429.26
 3297.86  443.81 4032.69   441.1 4579.31  439.75 4906.05  444.72 5171.51  441.83
 5372.08  450.96 5379.48  451.47  5382.4  455.34 5401.19  456.26 5564.93  457.59
#Mann= 8 ,-1,0
       0     .07       0  778.34      .1       0 1682.49    .055       0
 2154.99     .06       0 2181.57    .075       0 3040.19     .05       0
 3297.86    .055       0 4032.69    .075       0
#XS Ineff= 2 , 0
         1890.79     460 3297.86             445
Permanent Ineff=
       F       F
Bank Sta=3040.19,3297.86
XS Rating Curve= 0 ,0
Exp/Cntr=0.3,0.1

Type RM Length L Ch R = 1 ,57642   ,79,56,219
BEGIN DESCRIPTION:
XS 57642 - 58583 represent Oakdale.
XS 57642 added to represent Oakdale STA 998 - 2235
2009 lidar with 2001 in LOB STA 0 to 2436
END DESCRIPTION:
XS GIS Cut Line= 6
  2423472.470026   6975352.26813  2423378.200201  6973289.557361
  2423313.964109  6972918.029561  2422941.061968  6971878.967006
  2422362.719949  6970995.937604  2421331.469715  6969881.354203
#Sta/Elev= 30
       0  458.72  420.04   451.4    1001     455    1775     456    1902     453
    2277     452 2291.79   448.3 2834.74  449.39 2861.32  446.72  2956.3  451.33
 3289.97  446.26 3310.08  444.45 3333.24  434.38 3364.56  432.44 3392.98  412.48
 3445.37  410.23 3471.69  411.77  3491.7  416.68 3521.11   446.5 3534.01  447.12
 3975.73   441.5 4477.45  438.63 5269.41  440.86 5460.45  444.56 5646.82  441.53
 5882.75  449.86 5904.49  451.29 5908.16  455.94 5917.78   456.9  6119.9  456.84
#Mann= 8 ,-1,0
       0     .07       0    1001      .1       0    1902    .055       0
    2277     .06       0 2291.79    .075       0 3289.97     .05       0
 3534.01    .055       0 3975.73    .075       0
#XS Ineff= 2 , 0
            2637     460
Permanent Ineff=
       F       F
#Block Obstruct= 2 , 0
             900     455
Bank Sta=3289.97,3534.01
XS Rating Curve= 0 ,0
Exp/Cntr=0.3,0.1

Type RM Length L Ch R = 1 ,57586   ,354,283,357
BEGIN DESCRIPTION:
57586
Upstream bounding cross-section.
Section data is generated through the TXdot's topo file.
END DESCRIPTION:
XS GIS Cut Line= 6
  2423532.232701  6975340.146435  2423560.017751  6973565.834367
  2423325.022158  6972440.851709  2422977.504152  6971655.989434
  2422200.099539  6970525.219057  2421528.704884  6969571.131727
#Sta/Elev= 30
    2807     462    3307  449.63    3583   453.5 4024.62   446.6 4177.12   450.8
 4739.32   452.8 4903.42   448.2 5756.12   448.4 6006.02   447.1 6029.82   444.3
 6032.72  439.46 6047.22   439.8 6063.82   430.8 6141.52   419.2 6176.42   423.7
 6201.42     421 6237.12  409.88 6278.62   414.1 6303.32     435 6350.22   442.4
 6353.92   442.9 7292.62   439.2 8270.82   441.3 8334.92   436.7 8605.92     440
 8939.92   451.7 8974.52   449.2 9065.82     465 9128.12   469.210587.26  466.36
#Mann= 4 ,-1,0
    2807     .07       0 5756.12    .075       0 6032.72     .05       0
 6353.92    .075       0
#XS Ineff= 2 , 0
            5445     460 9422.26          488.86
Permanent Ineff=
       F       F
Bank Sta=6032.72,6350.22
XS Rating Curve= 0 ,0
Exp/Cntr=0.5,0.3

Type RM Length L Ch R = 3 ,57495   ,,,
BEGIN DESCRIPTION:
SH 161
---------------------
CDC GP011404-1 SH 161
---------------------
END DESCRIPTION:
Node Name=SH 161
Bridge Culvert--1,0,-1,-1, 0
Deck Dist Width WeirC Skew NumUp NumDn MinLoCord MaxHiCord MaxSubmerge Is_Ogee
47,166,2.6,0, 57, 57, , , 0.95, 0, 3,3,,
 1179.12 3430.12 3430.12 3525.12 3641.12 3757.12 3872.12 3982.12 4092.12 4202.12
 4312.12 4422.12 4532.12 4637.12 4747.12 4857.12 4967.12 5077.12 5187.12 5307.12
 5427.12 5547.12 5667.12 5787.12 5907.12 6107.12 6327.12 6527.12 6647.12 6767.12
 6887.12 7007.12 7127.12 7247.12 7367.12 7487.12 7595.26 7715.26 7835.26 7955.26
 8075.26 8176.26 8277.26 8377.26 8477.26 8577.26 8677.26 8777.26 8877.26 8977.26
 9077.26 9177.26 9285.26    9335 9387.26 9387.2610587.26
  494.14  482.33  482.33  482.16  481.56  480.52  479.04  477.28  475.13  473.17
  471.11  469.17  467.76  466.94  466.65  466.93  467.51   468.1  468.69  469.33
  469.97  470.61  471.25   471.9  472.54  473.61  474.78  475.85  476.49  477.13
  477.77  478.41  479.06   479.7  480.34  480.98  481.56   482.2  482.84  483.48
  484.12  484.66   485.2  485.74  486.27   486.8  487.34  487.87  488.41  488.94
  489.42  489.58   489.4  488.86  488.86  488.86  488.86
       0       0  472.33  472.04  471.44   470.4  468.95  467.16  465.01  463.05
  460.99  459.05  457.64  456.82  456.53  456.81  457.39  457.98  458.57  459.21
  459.85  460.49  461.13  461.98  458.92  459.99  461.16  462.23  466.37  467.01
  467.65  468.29  468.94  469.58  470.22  470.86  471.44  472.08  472.72  473.36
     474  474.54  475.08  475.62  476.15  476.68  477.22  477.75  478.29  478.82
   479.3  479.46  479.28  478.74  478.74       0       0
 1179.12 3430.12 3430.12 3525.12 3641.12 3757.12 3872.12 3982.12 4092.12 4202.12
 4312.12 4422.12 4532.12 4637.12 4747.12 4857.12 4967.12 5077.12 5187.12 5307.12
 5427.12 5547.12 5667.12 5787.12 5907.12 6107.12 6327.12 6527.12 6647.12 6767.12
 6887.12 7007.12 7127.12 7247.12 7367.12 7487.12 7595.26 7715.26 7835.26 7955.26
 8075.26 8176.26 8277.26 8377.26 8477.26 8577.26 8677.26 8777.26 8877.26 8977.26
 9077.26 9177.26 9285.26    9335 9387.26 9387.2610587.26
  494.14  482.33  482.33  482.16  481.56  480.52  479.04  477.28  475.13  473.17
  471.11  469.17  467.76  466.94  466.65  466.93  467.51   468.1  468.69  469.33
  469.97  470.61  471.25   471.9  472.54  473.61  474.78  475.85  476.49  477.13
  477.77  478.41  479.06   479.7  480.34  480.98  481.56   482.2  482.84  483.48
  484.12  484.66   485.2  485.74  486.27   486.8  487.34  487.87  488.41  488.94
  489.42  489.58   489.4  488.86  488.86  488.86  488.86
       0       0  472.33  472.04  471.44   470.4  468.95  467.16  465.01  463.05
  460.99  459.05  457.64  456.82  456.53  456.81  457.39  457.98  458.57  459.21
  459.85  460.49  461.13  461.98  458.92  459.99  461.16  462.23  466.37  467.01
  467.65  468.29  468.94  469.58  470.22  470.86  471.44  472.08  472.72  473.36
     474  474.54  475.08  475.62  476.15  476.68  477.22  477.75  478.29  478.82
   479.3  479.46  479.28  478.74  478.74       0       0
Pier Skew, UpSta & Num, DnSta & Num=  ,3525.12, 2 ,3525.12, 2 , 0 , 0 , 0 ,,
       4       4
     440  482.33
       4       4
     440  482.33
Pier Skew, UpSta & Num, DnSta & Num=  ,3641.12, 2 ,3641.12, 2 , 0 , 0 , 0 ,,
       4       4
     440  482.33
       4       4
     440  482.33
Pier Skew, UpSta & Num, DnSta & Num=  ,3757.12, 2 ,3757.12, 2 , 0 , 0 , 0 ,,
       4       4
     440  482.33
       4       4
     440  482.33
Pier Skew, UpSta & Num, DnSta & Num=  ,3872.12, 2 ,3872.12, 2 , 0 , 0 , 0 ,,
       4       4
     440  482.33
       4       4
     440  482.33
Pier Skew, UpSta & Num, DnSta & Num=  ,3982.12, 2 ,3982.12, 2 , 0 , 0 , 0 ,,
       4       4
     440  482.33
       4       4
     440  482.33
Pier Skew, UpSta & Num, DnSta & Num=  ,4092.12, 2 ,4092.12, 2 , 0 , 0 , 0 ,,
       4       4
     440  482.33
       4       4
     440  482.33
Pier Skew, UpSta & Num, DnSta & Num=  ,4202.12, 2 ,4202.12, 2 , 0 , 0 , 0 ,,
       4       4
     440  482.33
       4       4
     440  482.33
Pier Skew, UpSta & Num, DnSta & Num=  ,4312.12, 2 ,4312.12, 2 , 0 , 0 , 0 ,,
       4       4
     440  482.33
       4       4
     440  482.33
Pier Skew, UpSta & Num, DnSta & Num=  ,4422.12, 2 ,4422.12, 2 , 0 , 0 , 0 ,,
       4       4
     440  482.33
       4       4
     440  482.33
Pier Skew, UpSta & Num, DnSta & Num=  ,4532.12, 2 ,4532.12, 2 , 0 , 0 , 0 ,,
       4       4
     440  482.33
       4       4
     440  482.33
Pier Skew, UpSta & Num, DnSta & Num=  ,4632.12, 2 ,4632.12, 2 , 0 , 0 , 0 ,,
       4       4
     440  482.33
       4       4
     440  482.33
Pier Skew, UpSta & Num, DnSta & Num=  ,4747.12, 2 ,4747.12, 2 , 0 , 0 , 0 ,,
       4       4
     440  479.46
       4       4
     440  479.46
Pier Skew, UpSta & Num, DnSta & Num=  ,4857.12, 2 ,4857.12, 2 , 0 , 0 , 0 ,,
       4       4
     440  482.33
       4       4
     440  482.33
Pier Skew, UpSta & Num, DnSta & Num=  ,4967.12, 2 ,4967.12, 2 , 0 , 0 , 0 ,,
       4       4
     440  482.33
       4       4
     440  482.33
Pier Skew, UpSta & Num, DnSta & Num=  ,5077.12, 2 ,5077.12, 2 , 0 , 0 , 0 ,,
       4       4
     440  482.33
       4       4
     440  482.33
Pier Skew, UpSta & Num, DnSta & Num=  ,5187.12, 2 ,5187.12, 2 , 0 , 0 , 0 ,,
       4       4
     440  482.33
       4       4
     440  482.33
Pier Skew, UpSta & Num, DnSta & Num=  ,5307.12, 2 ,5307.12, 2 , 0 , 0 , 0 ,,
       4       4
     440  479.46
       4       4
     440  479.46
Pier Skew, UpSta & Num, DnSta & Num=  ,5427.12, 2 ,5427.12, 2 , 0 , 0 , 0 ,,
       8       8
     440  482.33
       8       8
     440  482.33
Pier Skew, UpSta & Num, DnSta & Num=  ,5547.12, 2 ,5547.12, 2 , 0 , 0 , 0 ,,
       8       8
     440  482.33
       8       8
     440  482.33
Pier Skew, UpSta & Num, DnSta & Num=  ,5667.12, 2 ,5667.12, 2 , 0 , 0 , 0 ,,
       8       8
     440  482.33
       8       8
     440  482.33
Pier Skew, UpSta & Num, DnSta & Num=  ,5787.12, 2 ,5787.12, 2 , 0 , 0 , 0 ,,
       8       8
     440  482.33
       8       8
     440  482.33
Pier Skew, UpSta & Num, DnSta & Num=  ,5907.12, 2 ,5907.12, 2 , 0 , 0 , 0 ,,
       8       8
     440  482.33
       8       8
     440  482.33
Pier Skew, UpSta & Num, DnSta & Num=  ,6107.12, 2 ,6107.12, 2 , 0 , 0 , 0 ,,
       8       8
     440  482.33
       8       8
     440  482.33
Pier Skew, UpSta & Num, DnSta & Num=  ,6327.12, 2 ,6327.12, 2 , 0 , 0 , 0 ,,
       8       8
     440  482.33
       8       8
     440  482.33
Pier Skew, UpSta & Num, DnSta & Num=  ,6527.12, 2 ,6527.12, 2 , 0 , 0 , 0 ,,
       8       8
     440  482.33
       8       8
     440  482.33
Pier Skew, UpSta & Num, DnSta & Num=  ,6647.12, 2 ,6647.12, 2 , 0 , 0 , 0 ,,
       8       8
     440  482.33
       8       8
     440  482.33
Pier Skew, UpSta & Num, DnSta & Num=  ,6767.12, 2 ,6767.12, 2 , 0 , 0 , 0 ,,
       8       8
     440  482.33
       8       8
     440  482.33
Pier Skew, UpSta & Num, DnSta & Num=  ,6887.12, 2 ,6887.12, 2 , 0 , 0 , 0 ,,
       8       8
     440  482.33
       8       8
     440  482.33
Pier Skew, UpSta & Num, DnSta & Num=  ,7007.12, 2 ,7007.12, 2 , 0 , 0 , 0 ,,
       4       4
     440  482.33
       4       4
     440  482.33
Pier Skew, UpSta & Num, DnSta & Num=  ,7127.12, 2 ,7127.12, 2 , 0 , 0 , 0 ,,
       4       4
     440  482.33
       4       4
     440  482.33
Pier Skew, UpSta & Num, DnSta & Num=  ,7247.12, 2 ,7247.12, 2 , 0 , 0 , 0 ,,
       4       4
     440  482.33
       4       4
     440  482.33
Pier Skew, UpSta & Num, DnSta & Num=  ,7367.12, 2 ,7367.12, 2 , 0 , 0 , 0 ,,
       4       4
     440  482.33
       4       4
     440  482.33
Pier Skew, UpSta & Num, DnSta & Num=  ,7487.12, 2 ,7487.12, 2 , 0 , 0 , 0 ,,
       4       4
     440  482.33
       4       4
     440  482.33
Pier Skew, UpSta & Num, DnSta & Num=  ,7595.26, 2 ,7595.26, 2 , 0 , 0 , 0 ,,
       4       4
     440  482.33
       4       4
     440  482.33
Pier Skew, UpSta & Num, DnSta & Num=  ,7715.26, 2 ,7715.26, 2 , 0 , 0 , 0 ,,
       4       4
     440  482.33
       4       4
     440  482.33
Pier Skew, UpSta & Num, DnSta & Num=  ,7835.26, 2 ,7835.26, 2 , 0 , 0 , 0 ,,
       4       4
     440  482.33
       4       4
     440  482.33
Pier Skew, UpSta & Num, DnSta & Num=  ,7955.26, 2 ,7955.26, 2 , 0 , 0 , 0 ,,
       4       4
     440  482.33
       4       4
     440  482.33
Pier Skew, UpSta & Num, DnSta & Num=  ,8075.26, 2 ,8075.26, 2 , 0 , 0 , 0 ,,
       4       4
     440  482.33
       4       4
     440  482.33
Pier Skew, UpSta & Num, DnSta & Num=  ,8176.26, 2 ,8176.26, 2 , 0 , 0 , 0 ,,
       4       4
     440  482.33
       4       4
     440  482.33
Pier Skew, UpSta & Num, DnSta & Num=  ,8277.26, 2 ,8277.26, 2 , 0 , 0 , 0 ,,
       4       4
     440  482.33
       4       4
     440  482.33
Pier Skew, UpSta & Num, DnSta & Num=  ,8377.26, 2 ,8377.26, 2 , 0 , 0 , 0 ,,
       4       4
     440  482.33
       4       4
     440  482.33
Pier Skew, UpSta & Num, DnSta & Num=  ,8477.26, 2 ,8477.26, 2 , 0 , 0 , 0 ,,
       4       4
     440  482.33
       4       4
     440  482.33
Pier Skew, UpSta & Num, DnSta & Num=  ,8577.26, 2 ,8577.26, 2 , 0 , 0 , 0 ,,
       4       4
     440  482.33
       4       4
     440  482.33
Pier Skew, UpSta & Num, DnSta & Num=  ,8677.26, 2 ,8677.26, 2 , 0 , 0 , 0 ,,
       4       4
     440  482.33
       4       4
     440  482.33
Pier Skew, UpSta & Num, DnSta & Num=  ,8777.26, 2 ,8777.26, 2 , 0 , 0 , 0 ,,
       4       4
     440  482.33
       4       4
     440  482.33
Pier Skew, UpSta & Num, DnSta & Num=  ,8877.26, 2 ,8877.26, 2 , 0 , 0 , 0 ,,
       4       4
     440  482.33
       4       4
     440  482.33
Pier Skew, UpSta & Num, DnSta & Num=  ,8977.26, 2 ,8977.26, 2 , 0 , 0 , 0 ,,
       4       4
     440  482.33
       4       4
     440  482.33
Pier Skew, UpSta & Num, DnSta & Num=  ,9077.26, 2 ,9077.26, 2 , 0 , 0 , 0 ,,
       4       4
     440  482.33
       4       4
     440  482.33
Pier Skew, UpSta & Num, DnSta & Num=  ,9177.26, 2 ,9177.26, 2 , 0 , 0 , 0 ,,
       4       4
     440  482.33
       4       4
     440  482.33
Pier Skew, UpSta & Num, DnSta & Num=  ,9282.26, 2 ,9282.26, 2 , 0 , 0 , 0 ,,
       4       4
     440  482.33
       4       4
     440  482.33
Abutment Skew #Up #Dn= , 2 , 2
 3430.12    3465
  482.33     440
 3430.12    3465
  482.33     440
Abutment Skew #Up #Dn= , 2 , 2
    9335 9387.26
     440  488.86
    9335 9387.26
     440  488.86
BR Coef=-1 , 1 , 1 ,0.9, 0 ,,,0.8,-1,1.33,0,
WSPro=,,,, 1 ,,,, 0 ,,,, 0 ,,,,-1 ,-1 ,-1 , 0 , 0 , 0 , 0 , 0
BC Design=,, 0 ,, 0 ,,,,,,
BC Use User HTab Curves=0
BC User HTab FreeFlow(D)= 0

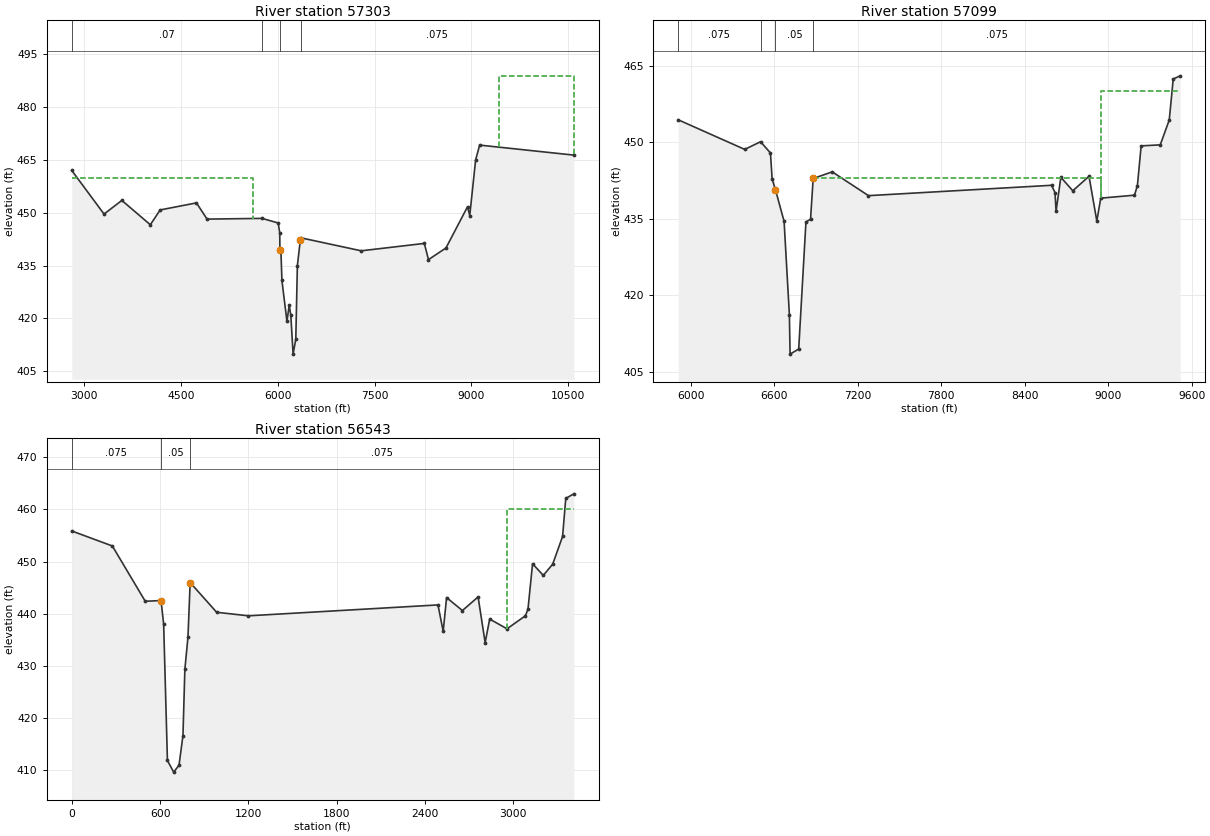
Type RM Length L Ch R = 1 ,57303   ,926,204,183
BEGIN DESCRIPTION:
57303
Downstream bounding cross-section.
Copied from cross-section 57586
END DESCRIPTION:
XS GIS Cut Line= 6
  2423891.171944  6975170.664819  2423813.803004  6973375.702202
  2423283.754524  6971667.768282  2422175.043815  6969967.177523
   2421923.77332  6969645.988532  2421575.466274  6969488.870408
#Sta/Elev= 30
    2807     462    3307  449.63    3583   453.5 4024.62   446.6 4177.12   450.8
 4739.32   452.8 4903.42   448.2 5756.12   448.4 6006.02   447.1 6029.82   444.3
 6032.72  439.46 6047.22   439.8 6063.82   430.8 6141.52   419.2 6176.42   423.7
 6201.42     421 6237.12  409.88 6278.62   414.1 6303.32     435 6350.22   442.4
 6353.92   442.9 7292.62   439.2 8270.82   441.3 8334.92   436.7 8605.92     440
 8939.92   451.7 8974.52   449.2 9065.82     465 9128.12   469.210587.26  466.36
#Mann= 4 ,-1,0
    2807     .07       0 5756.12    .075       0 6032.72     .05       0
 6353.92    .075       0
#XS Ineff= 2 , 0
            5610     460 9422.26          488.86
Permanent Ineff=
       F       F
Bank Sta=6032.72,6350.22
XS Rating Curve= 0 ,0
Exp/Cntr=0.5,0.3

Type RM Length L Ch R = 1 ,57099   ,565.9,330.56,1.49
BEGIN DESCRIPTION:
Station equation. Downstream RS 56543 + 330.56 = 56873.56. RS 57099 = RS 56874
END DESCRIPTION:
XS GIS Cut Line= 4
  2424273.269605 6971681.3430576 2423303.2695767 6971277.0252966
 2421937.0498682 6969627.2392262 2421608.8579393  6969487.329401
#Sta/Elev= 30
    5910   454.4    6388   448.6    6502   450.1    6573   447.9    6585   442.8
    6609   440.7    6671   434.5    6709   416.2    6714   408.5    6776   409.5
    6828   434.4    6861   434.9    6880   442.9    7017   444.2 7277.32  439.54
 8592.76  441.57 8617.82  440.15 8625.28  436.47 8659.76  443.14 8745.51   440.5
  8862.2  443.33 8918.22  434.57 8946.52  439.05  9188.9  439.63 9209.93  441.51
 9236.77  449.29 9374.14  449.49 9438.74  454.36 9467.34  462.39 9517.71  463.01
#Mann= 4 ,-1,0
    5910    .075       0    6502     .12       0    6609     .05       0
    6880    .075       0
#XS Ineff= 3 ,-1
    5910    6609   440.7    6880 8946.52   442.9 8946.54 9517.73     460
Permanent Ineff=
       F       F       T
Bank Sta=6609,6880
XS Rating Curve= 0 ,0
Exp/Cntr=0.3,0.1

Type RM Length L Ch R = 1 ,56543   ,75.31,64.13,4.46
XS GIS Cut Line= 6
  2424319.861047 6971055.4473277  2423127.152803 6971058.0513251
 2423090.1039926 6971017.6777182 2422431.2434336 6970217.8233468
 2421937.2703402 6969627.0115363 2421609.0898942 6969486.6686412
#Sta/Elev= 30
       0  455.86   275.7  452.98  499.21  442.38  606.36  442.52  624.25  438.01
  649.92  411.86  692.24  409.62  728.64  410.94  755.45  416.63  768.36  429.32
   789.5  435.51  804.26  445.97  984.36  440.27 1200.25  439.59 2488.07  441.68
 2523.43   436.6 2546.44  443.09 2653.93   440.6 2760.53  443.21 2808.54  434.44
 2839.23  438.97 2956.95   437.1 3082.16   439.6 3099.52  440.87 3130.59  449.57
  3203.6  447.34 3267.35   449.5 3334.47   454.8 3356.23   462.1 3410.82  462.98
#Mann= 3 ,0,0
       0    .075       0  606.36     .05       0  804.26    .075       0
#XS Ineff= 2 , 0
                          2954.3             460
Permanent Ineff=
       F       T
Bank Sta=606.36,804.26
XS Rating Curve= 0 ,0
Exp/Cntr=0.3,0.1