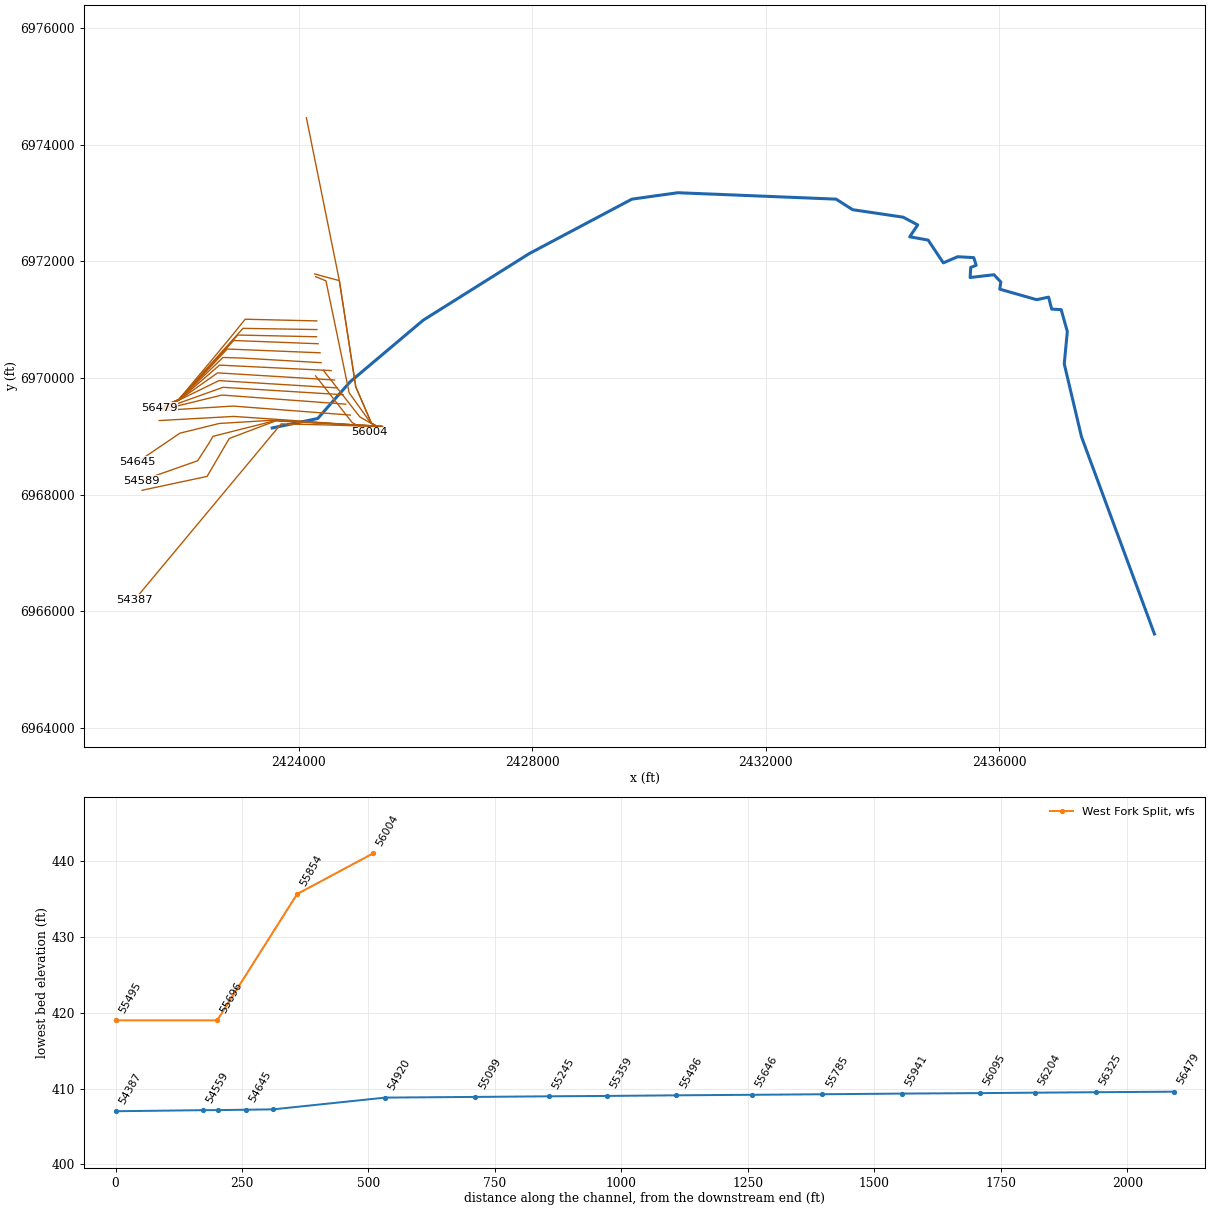
HEC-RAS study CDC_Consolidated_Model.prj: Upper Trinity CDC Consolidated Model

--- CDC_Consolidated_Model.g12 (geometry) --- (continued)

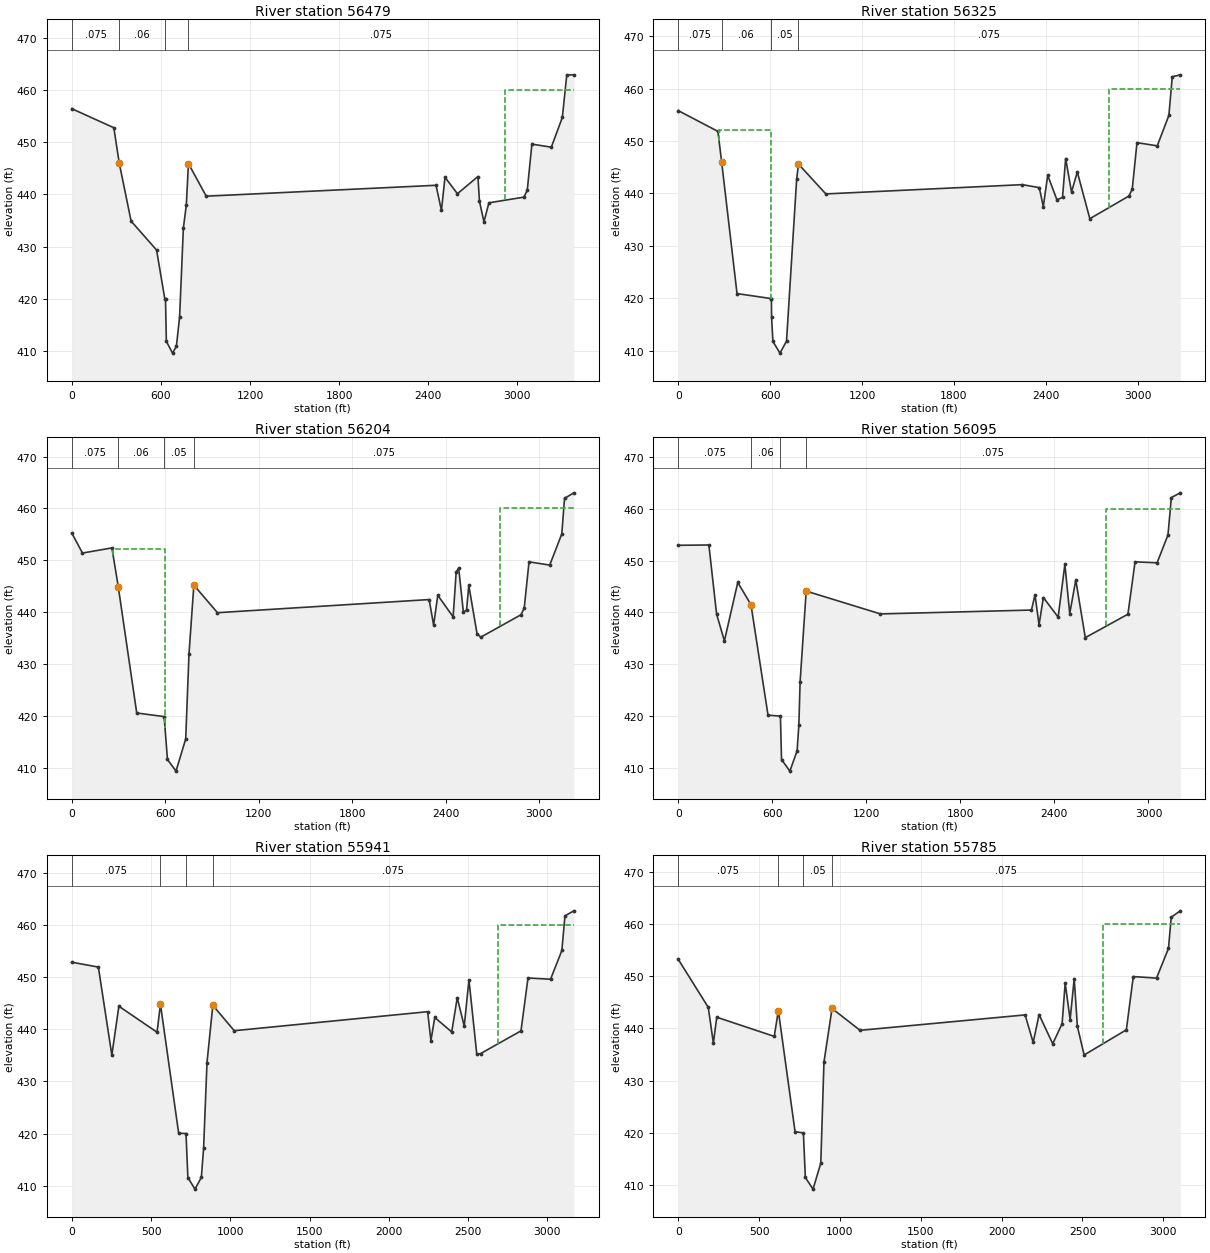
Type RM Length L Ch R = 1 ,56479   ,153.13,154.18,161.09
BEGIN DESCRIPTION:
XS Added for mitigation
END DESCRIPTION:
XS GIS Cut Line= 6
  2424312.048727 6970977.3221559 2423085.4862196  6971005.968096
 2422839.2767383 6970699.7826847 2422437.7142212 6970214.8866729
 2421947.4589681 6969630.7667781 2421608.9281491 6969483.3513906
#Sta/Elev= 30
       0  456.43  283.19  452.78  320.08  445.94  399.64  434.88  571.04  429.34
  626.85  419.94  631.22  419.94  637.04  411.83  678.56  409.58   704.5  410.89
  726.19   416.5  751.58  433.55  771.62  438.01  785.64  445.92  905.53  439.66
 2453.18  441.75 2489.54  436.93 2513.42  443.28 2597.38  440.13 2735.06  443.43
 2745.74  438.65 2775.95  434.73 2809.29  438.39 3045.35  439.48 3067.79  440.83
 3098.69  449.64 3229.57  449.05 3303.72  454.75 3333.57   462.9 3381.22  462.92
#Mann= 4 ,-1,0
       0    .075       0  320.08     .06       0  626.85     .05       0
  785.64    .075       0
#XS Ineff= 2 , 0
                         2918.88             460
Permanent Ineff=
       F       T
Bank Sta=320.08,785.64
XS Rating Curve= 0 ,0
Exp/Cntr=0.3,0.1

Type RM Length L Ch R = 1 ,56325   ,124.93,120.76,118.42
BEGIN DESCRIPTION:
XS Added for mitigation
END DESCRIPTION:
XS GIS Cut Line= 5
  2424313.784616 6970828.8847887 2423048.1598507 6970849.7180804
 2422887.8963917 6970671.8332656 2421950.1115219 6969629.8940765
 2421610.7867412 6969480.2149139
#Sta/Elev= 30
       0  455.82  259.09  451.85   283.6  445.94  383.83  420.88   603.9  419.94
  608.39  419.94  609.37  416.34  618.14  411.74  664.18  409.51  706.91   411.8
  773.22  442.75  785.09   445.6  963.54  439.91  2246.8  441.68 2357.18  441.11
 2383.43  437.48 2412.33  443.47 2472.42  438.78 2508.89  439.25 2529.36  446.67
 2567.67  440.27 2605.41  444.11 2687.11  435.18 2942.51  439.51 2964.09  440.81
 2994.99   449.7 3127.34  449.09 3203.24  454.91 3225.42  462.28 3277.91  462.65
#Mann= 4 ,-1,0
       0    .075       0   283.6     .06       0   603.9     .05       0
  785.09    .075       0
#XS Ineff= 2 ,-1
   266.7  606.47  452.02 2811.85 3277.91     460
Permanent Ineff=
       F       T
Bank Sta=283.6,785.09
XS Rating Curve= 0 ,0
Exp/Cntr=0.3,0.1

Type RM Length L Ch R = 1 ,56204   ,119.99,108.45,100.53
BEGIN DESCRIPTION:
XS Added for mitigation
END DESCRIPTION:
XS GIS Cut Line= 6
  2424308.576293 6970705.6209277 2422959.6180331 6970735.1346481
 2422164.4792034 6969860.1347577 2422058.7011997 6969746.7212707
 2421950.4248415 6969629.0837106 2421607.0269062 6969477.8235145
#Sta/Elev= 30
       0  455.28   68.68  451.42  257.59  452.41  298.36  444.94  416.82  420.64
  592.78  419.94  614.01  411.69  668.73  409.45  731.09  415.63  752.26  432.01
  783.42  445.25   934.9  439.94 2293.11  442.47 2321.96  437.57 2348.66  443.29
 2447.21  439.14  2466.7  447.78 2482.63  448.52 2513.08  440.03 2533.31  440.48
 2547.76   445.2 2600.55   435.9 2624.54  435.23 2882.15  439.54 2903.22   440.8
 2934.15  449.73 3066.99   449.1 3144.49   455.1 3161.96  461.95  3221.8  463.01
#Mann= 4 ,-1,0
       0    .075       0  298.36     .06       0  592.78     .05       0
  783.42    .075       0
#XS Ineff= 2 ,-1
   265.5  598.62 452.289 2749.93  3221.8     460
Permanent Ineff=
       F       T
Bank Sta=298.36,783.42
XS Rating Curve= 0 ,0
Exp/Cntr=0.3,0.1

Type RM Length L Ch R = 1 ,56095   ,158.52,154.24,151.9
BEGIN DESCRIPTION:
XS Added for mitigation
END DESCRIPTION:
XS GIS Cut Line= 6
  2424334.617907 6970585.8291725 2422888.5712591 6970641.1604267
 2422023.1169533 6969702.9109908 2421950.4428861  6969628.309434
 2421644.2331966  6969493.290019 2421606.9576806 6969476.4472049
#Sta/Elev= 30
       0  452.95  195.47  453.01  244.61   439.7  294.47   434.5  379.83  445.79
  464.06  441.49  572.86  420.18     652     420  658.99  411.63   712.3  409.39
   758.4  413.31  769.58  418.26   777.5   426.6  816.33  444.12 1290.35  439.71
 2253.57  440.46 2276.03  443.37 2302.08  437.63 2329.59  442.88 2423.88  439.09
 2466.83  449.27 2497.77  439.77 2536.42  446.27 2597.12  435.14 2869.01  439.66
 2914.54  449.76  3055.1  449.57 3124.51  454.94  3146.1  462.16 3203.27  463.07
#Mann= 4 ,-1,0
       0    .075       0  464.06     .06       0     652     .05       0
  816.33    .075       0
#XS Ineff= 2 , 0
             460     440 2728.52             460
Permanent Ineff=
       T       T
Bank Sta=464.06,816.33
XS Rating Curve= 0 ,0
Exp/Cntr=0.3,0.1

Type RM Length L Ch R = 1 ,55941   ,168.82,156.64,147.12
BEGIN DESCRIPTION:
XS Added for mitigation
END DESCRIPTION:
XS GIS Cut Line= 6
  2424369.340279 6970430.4472654 2422778.1945114 6970495.5514659
 2422202.4473033 6969882.8591217 2422075.1486734 6969751.6090562
 2421951.4628971 6969627.5026771 2421608.7588581 6969473.7103337
#Sta/Elev= 30
       0  452.86   167.7  451.93  252.74  435.04   297.1  444.42  537.86  439.43
  559.35   444.8  674.19  420.06  720.57     420   732.4  411.55  777.04  409.33
  817.36  411.57  831.54  417.17  852.97  433.59  889.69   444.6 1024.78  439.72
 2244.67  443.37 2265.37  437.82  2289.6  442.26  2396.5  439.48 2431.39  446.05
 2475.57   440.6 2505.29  449.49 2554.85  435.18 2578.41  435.33 2833.54  439.69
 2877.72  449.84 3019.85  449.59 3091.35  455.11 3110.82  461.75 3166.93  462.72
#Mann= 4 ,-1,0
       0    .075       0  559.35     .06       0  720.57     .05       0
  889.69    .075       0
#XS Ineff= 2 , 0
          566.85     440  2690.6             460
Permanent Ineff=
       T       T
Bank Sta=559.35,889.69
XS Rating Curve= 0 ,0
Exp/Cntr=0.3,0.1

Type RM Length L Ch R = 1 ,55785   ,135.88,139.03,141.1
BEGIN DESCRIPTION:
Updated for Wildlife Parkway
END DESCRIPTION:
XS GIS Cut Line= 5
  2424386.412751 6970261.3445852 2423044.2481131 6970339.6101767
 2422705.5207722 6970350.4933571 2421950.7194603 6969624.7487456
 2421609.3336601 6969470.8081086
#Sta/Elev= 30
       0  453.22  185.81  444.02  217.27  437.18  238.16  442.14  593.92  438.47
  619.02   443.4  722.45  420.23  774.06     420  786.03  411.47   833.6  409.24
   881.6  414.21   901.2  433.55  951.17  443.81  1124.5  439.63 2145.11  442.58
    2195  437.31 2231.53  442.64 2315.84  437.06 2373.95   440.9 2392.93  448.67
 2423.54  441.69 2448.75  449.53 2468.46  440.38 2510.18  434.91 2771.33  439.73
  2814.1  449.92 2957.81  449.62 3031.74  455.31 3048.77  461.28 3104.94   462.5
#Mann= 4 ,-1,0
       0    .075       0  619.02     .06       0  774.06     .05       0
  951.17    .075       0
#XS Ineff= 2 ,-1
  147.86  620.97     440 2625.05 3104.94     460
Permanent Ineff=
       T       T
Bank Sta=619.02,951.17
XS Rating Curve= 0 ,0
Exp/Cntr=0.3,0.1

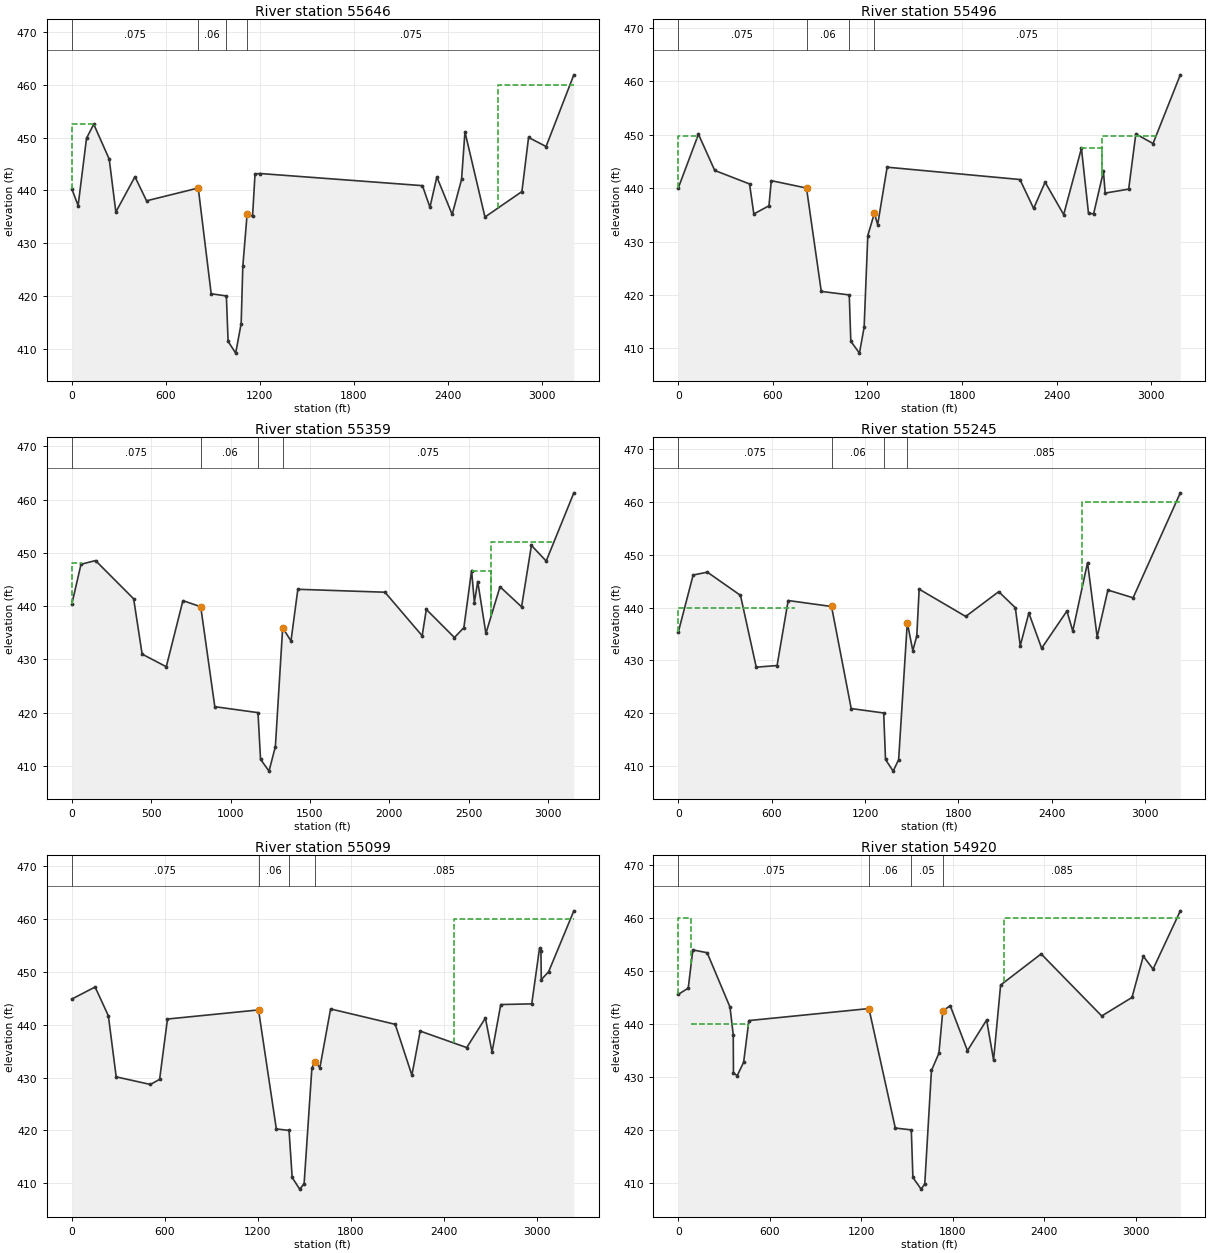
Type RM Length L Ch R = 1 ,55646   ,153.25,149.49,141.974
BEGIN DESCRIPTION:
XS Added for Mitigation Swale
END DESCRIPTION:
XS GIS Cut Line= 6
  2424558.005256 6970125.7418381 2422646.5468088 6970219.4916506
 2421959.4179337 6969627.4390289 2421937.2011146 6969616.9200211
  2421658.041568 6969488.0088616 2421613.1450042 6969467.1161868
#Sta/Elev= 30
       0  440.31   40.53  437.12    94.1  449.87  140.01  452.53  238.77  445.93
  281.12   435.9  403.03  442.58  476.91  438.02  806.69  440.44  889.22  420.41
  986.07     420  997.09   411.4  1045.5  409.17 1080.44  414.78 1090.97  425.62
 1118.42  435.52 1153.05  435.09 1168.91  443.12 1199.95  443.19 2236.72  440.89
 2284.57   436.8 2328.45  442.54 2426.24  435.43 2486.21  442.08  2507.8  451.07
 2635.46  434.95 2871.07  439.77 2913.57  450.02 3025.22   448.3 3202.36  461.88
#Mann= 4 ,-1,0
       0    .075       0  806.69     .06       0  986.07     .05       0
 1118.42    .075       0
#XS Ineff= 3 ,-1
       0     145  452.51     145     416     440 2716.84 3202.36     460
Permanent Ineff=
       T       T       T
Bank Sta=806.69,1118.42
XS Rating Curve= 0 ,0
Exp/Cntr=0.3,0.1

Type RM Length L Ch R = 1 ,55496   ,133.85,137.36,135.3
BEGIN DESCRIPTION:
XS Added for Mitigation Swale
END DESCRIPTION:
XS GIS Cut Line= 4
  2424615.296808 6969964.2834996 2422612.6925458 6970086.6792522
 2421960.7827604 6969625.3077996 2421617.9009002 6969464.7172415
#Sta/Elev= 30
       0  440.02  128.21   450.1  231.41  443.32  452.09  440.79  479.33  435.17
   575.4   436.7  589.94  441.41  813.31  440.02  906.95  420.66 1084.44     420
 1094.32  411.32 1149.07   409.1 1178.71  413.96 1201.99  431.11 1243.47  435.28
 1264.66  433.17 1324.57  443.93 2166.58  441.62 2253.67   436.2 2326.23  441.12
 2444.08  435.05 2556.62  447.46 2601.49  435.29 2633.87  435.19 2696.21  443.13
 2707.18  439.08  2856.2  439.82 2901.53  450.16 3010.58  448.36 3183.62  461.23
#Mann= 4 ,-1,0
       0    .075       0  813.31     .06       0 1084.44     .05       0
 1243.47    .075       0
#XS Ineff= 4 ,-1
       0  116.59  449.77  116.59     589     440 2556.62 2690.12  447.46
 2690.12  3044.6 449.819
Permanent Ineff=
       F       F       T       F
Bank Sta=813.31,1243.47
XS Rating Curve= 0 ,0
Exp/Cntr=0.3,0.1

Type RM Length L Ch R = 1 ,55359   ,128.66,114.69,113.46
BEGIN DESCRIPTION:
XS Added for Mitigation Swale
END DESCRIPTION:
XS GIS Cut Line= 3
  2424662.171714 6969828.8667757  2422636.130163 6969953.8665257
 2421619.2745851 6969456.0797916
#Sta/Elev= 30
       0  440.34    58.2  447.86  149.67  448.55  389.78  441.37  443.06  430.99
  595.25  428.62  700.02  441.03  812.29  439.88  900.78  421.12 1172.85     420
 1188.88  411.25 1242.33  409.02 1282.38  413.64 1328.27  435.95  1380.6  433.45
 1423.82  443.16 1972.44  442.61 2206.79  434.43 2232.95  439.38 2409.91   434.1
 2469.43  435.96 2518.09  446.68 2535.57  440.67 2556.76  444.62 2608.22  434.87
    2697  443.64 2832.79  439.87 2894.95   451.4 2987.86  448.46 3162.05  461.27
#Mann= 4 ,-1,0
       0    .075       0  812.29     .06       0 1172.85     .05       0
 1328.27    .075       0
#XS Ineff= 4 ,-1
       0      60  448.01      60     710     440 2518.09  2642.1  446.68
  2642.1 3045.97     452
Permanent Ineff=
       F       F       T       F
Bank Sta=812.29,1328.27
XS Rating Curve= 0 ,0
Exp/Cntr=0.3,0.1

Type RM Length L Ch R = 1 ,55245   ,246.52,145.26,141.84
BEGIN DESCRIPTION:
Added for Wildlife Parkway - 2009 TNRIS
END DESCRIPTION:
XS GIS Cut Line= 3
  2424763.734175  6969711.679346 2422706.4426864 6969839.2834215
 2421610.4635791 6969445.5673454
#Sta/Elev= 30
       0  435.29   95.81  446.17  187.29  446.71  399.94  442.31  501.15  428.69
  635.07     429  706.26  441.33  984.98   440.2 1111.33  420.84 1320.01     420
 1331.74  411.18 1380.89  408.97 1416.11  411.16 1471.67  437.15 1507.16  431.82
 1532.63  434.61 1547.94  443.49 1846.99  438.31 2059.02  443.01  2165.8  439.97
 2197.48  432.75 2252.68  438.96 2334.81  432.28 2497.22  439.34 2534.82  435.55
 2629.71  448.51 2691.65  434.43 2760.57  443.32 2922.51  441.85  3225.8  461.76
#Mann= 4 ,-1,0
       0    .075       0  984.98     .06       0 1320.01     .05       0
 1471.67    .085       0
#XS Ineff= 2 , 0
          748.31     440 2595.15             460
Permanent Ineff=
       F       T
Bank Sta=984.98,1471.67
XS Rating Curve= 0 ,0
Exp/Cntr=0.3,0.1

Type RM Length L Ch R = 1 ,55099   ,455.52,178.4,181.81
BEGIN DESCRIPTION:
XS added to model mitigation swale
END DESCRIPTION:
XS GIS Cut Line= 3
  2424808.005084 6969550.2210075 2422688.2133921  6969706.470695
 2421607.8293981 6969442.0831004
#Sta/Elev= 30
       0  444.84  150.46  447.13  235.93  441.69  286.45  430.13  507.28  428.69
  566.55  429.66  617.18  441.07 1204.37  442.79  1319.2  420.27 1401.09     420
 1421.41  411.09 1469.75  408.89 1498.31   409.9 1548.57  431.82 1568.11  432.97
 1600.11  431.87 1669.16  442.98 2085.92  440.07 2193.34  430.45 2246.82  438.79
 2546.98  435.67  2667.4  441.25 2710.36  434.82 2766.53  443.81 2966.22  443.94
 3016.54  454.45 3025.68  453.93 3027.88  448.52 3075.19  450.02 3237.81  461.54
#Mann= 4 ,-1,0
       0    .075       0 1204.37     .06       0 1401.09     .05       0
 1568.11    .085       0
#XS Ineff= 2 , 0
             690     440 2467.25             460
Permanent Ineff=
       F       T
Bank Sta=1204.37,1568.11
XS Rating Curve= 0 ,0
Exp/Cntr=0.3,0.1

Type RM Length L Ch R = 1 ,54920   ,347.02,221,186.29
BEGIN DESCRIPTION:
Added for Wildlife Parkway - 2009 TNRIS
END DESCRIPTION:
XS GIS Cut Line= 3
  2424887.485568 6969362.9369332 2422879.5338756 6969517.3972542
 2421605.1929204 6969439.2658488
#Sta/Elev= 30
       0  445.62   65.49   446.8   95.79  454.03  189.55   453.5  339.29  443.22
  360.47     438  361.97  430.77  386.34  430.25  428.55  432.78  463.11  440.67
 1249.83  442.94 1422.65  420.35 1527.57     420 1538.06  411.01 1591.75   408.8
  1615.7  409.78 1659.58  431.23 1708.49  434.49 1734.02  442.53 1782.89  443.47
 1895.53  434.98 2021.19  440.78 2066.71  433.21 2112.88  447.39 2378.44  453.27
  2775.6  441.54 2973.86  445.04 3047.92  452.85 3112.04   450.4 3290.62  461.42
#Mann= 4 ,-1,0
       0    .075       0 1249.83     .06       0 1527.57     .05       0
 1734.02    .085       0
#XS Ineff= 3 ,-1
       0   84.74     460   84.74  458.14     440 2135.82 3290.62     460
Permanent Ineff=
       T       T       T
Bank Sta=1249.83,1734.02
XS Rating Curve= 0 ,0
Exp/Cntr=0.3,0.1

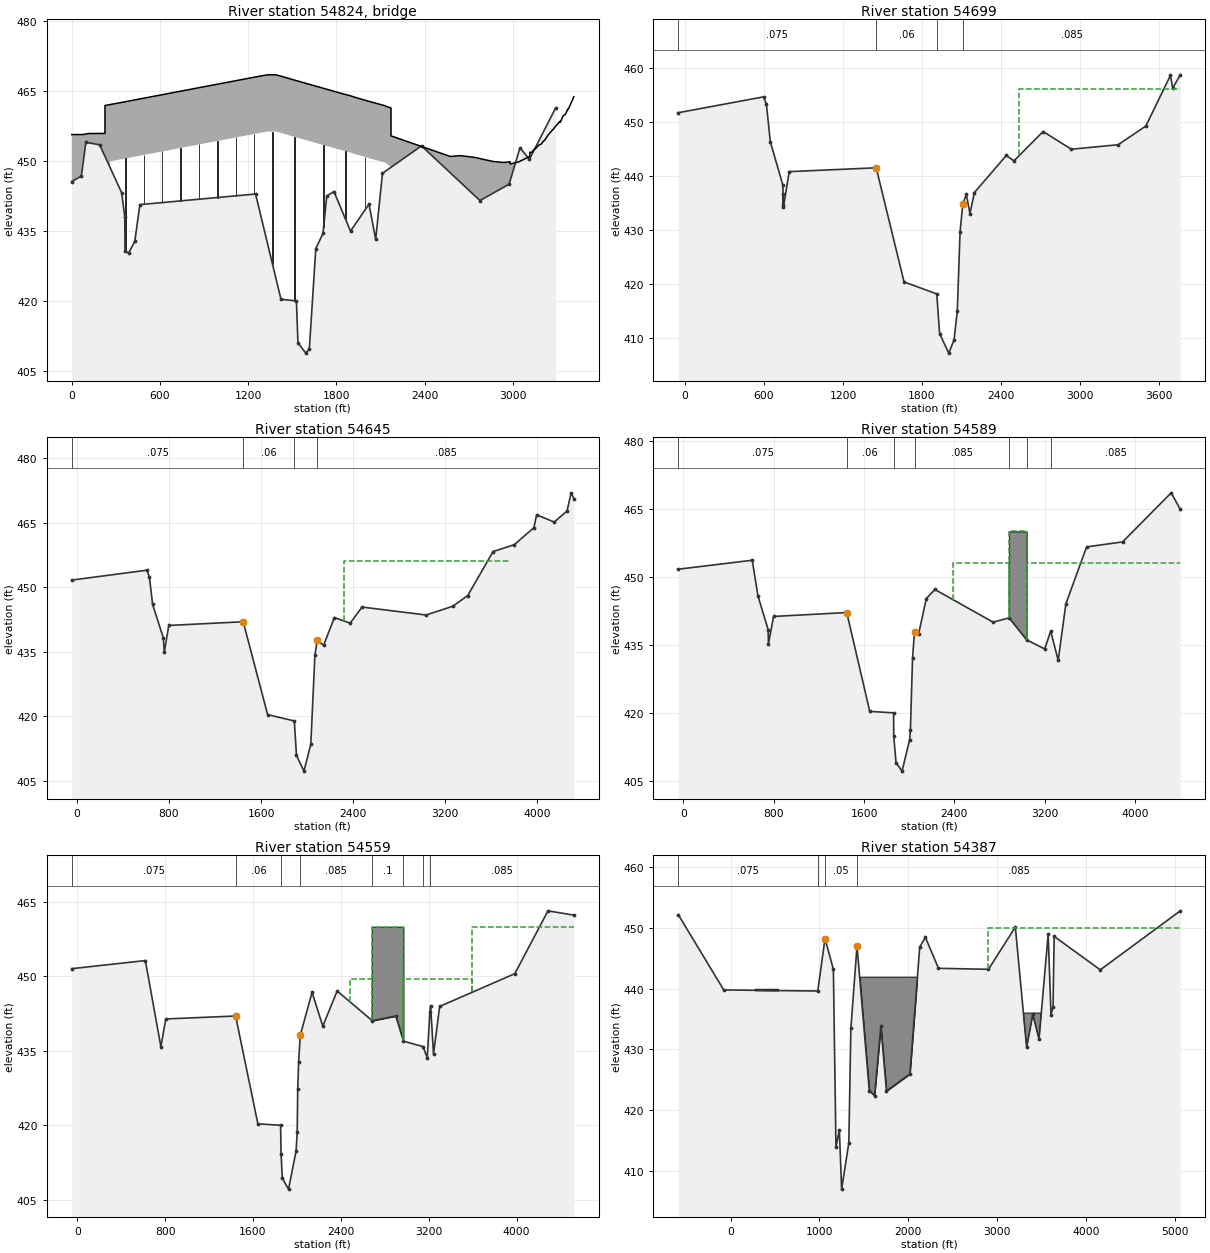
Type RM Length L Ch R = 3 ,54824   ,,,
BEGIN DESCRIPTION:
Wildlife Parkway
END DESCRIPTION:
Bridge Culvert--1,0,-1,-1, 0
Deck Dist Width WeirC Skew NumUp NumDn MinLoCord MaxHiCord MaxSubmerge Is_Ogee
75,110,2.6,0, 101, 101, , , 0.98, 0, 0,0,,
       0   74.93   94.67   99.74  107.56  113.26  225.72  225.82  260.82  328.82
  428.82  528.82  628.82  728.82  828.82  928.82 1028.82 1128.82 1228.82 1328.82
 1385.82 1388.82 1428.82 1528.82 1628.82 1728.82 1828.82 1882.82 1885.82 1928.82
 2028.82 2128.82 2135.82 2170.82 2170.92 2574.26 2595.02 2613.58 2616.38 2639.85
 2649.34 2672.32  2699.4 2717.22 2739.64 2753.26 2785.01 2804.42 2816.27 2827.44
 2834.86 2851.88 2864.52 2869.76 2892.11 2918.49  2939.5 2953.17 2975.01 2980.23
 2980.96 2990.29 3039.45 3101.35 3114.35 3114.64 3116.78 3124.49 3128.37 3135.11
 3146.62 3152.33 3154.73  3157.6 3164.61 3175.04 3176.29 3193.31 3198.81 3210.77
 3214.74 3233.11 3237.82 3266.96 3276.01 3276.73 3287.45 3307.18 3310.12 3315.94
  3319.4 3322.99 3338.21 3342.79 3356.48 3372.15 3372.91 3381.49 3387.14 3403.73
 3414.22
   455.7   455.7  455.82  455.84   455.9  455.92  455.94  461.94  462.14  462.54
  463.14  463.74  464.34  464.94  465.54  466.14  466.74  467.34  467.94  468.52
  468.52  468.52  468.17  467.26  466.37  465.47  464.57  464.12  464.12  463.67
  462.76   461.9  461.78  461.42  455.42     451  451.05  451.11  451.11  451.18
  451.14  451.06  450.95  450.89   450.8  450.71  450.48  450.35  450.26  450.19
  450.13  450.02  449.93  449.91  449.85  449.76   449.7  449.75  449.84  449.88
  449.38  449.45  449.84  450.81  451.01   451.8  451.93  451.85  451.87  452.24
   452.5  452.72  452.87  452.79  453.06  453.41  453.47  453.67  453.99   454.4
  454.41  455.31  455.55  456.62   456.9  456.95  457.39  458.08   458.2  458.39
  458.54  458.37  459.51  459.77  460.01  461.11  461.07  461.44  461.88  463.03
  463.84
                                                                  449.96  450.36
  450.96  451.56  452.16  452.76  453.36  453.96  454.56  455.16  455.76  456.34
  456.34  456.34  455.99  455.08  454.19  453.29  452.39  451.94  451.94  451.49
  450.58  449.72   449.6
     -90  -48.78   -42.8  -33.11   15.53   22.92   38.04   53.23   85.51   94.27
  127.63  133.79  193.16  205.67  242.45   253.9  272.74  291.62  307.54  364.52
  386.75  406.49  411.56  419.38  425.08  628.76  628.86  663.86  731.86  831.86
  931.86 1031.86 1131.86 1231.86 1331.86 1431.86 1531.86 1631.86 1731.86 1788.86
 1791.86 1831.86 1931.86 2031.86 2131.86 2231.86 2285.86 2288.86 2331.86 2431.86
 2531.86 2538.86 2573.86 2573.96 2793.08 2813.84  2832.4  2835.2 2858.67 2868.16
 2891.14 2918.22 2936.04 2958.46 2972.08 3003.83 3023.24 3035.09 3046.26 3053.68
  3070.7 3083.34 3088.58 3110.93 3137.31 3158.32 3171.99 3193.83 3199.05 3199.78
 3209.11 3258.27 3320.17 3333.17 3333.46  3335.6 3343.31 3347.19 3353.93 3365.44
 3371.15 3373.55 3376.42 3383.43 3393.86 3395.11 3412.13 3417.63 3429.59 3433.56
 3686.45
  450.78  451.17  451.23  451.36  451.98  452.61  452.76  452.92  453.22  453.31
  453.68  453.74  454.38   454.5  454.84  454.94  455.05  455.15  455.25  455.61
   455.7  455.82  455.84   455.9  455.92  455.94  461.94  462.14  462.54  463.14
  463.74  464.34  464.94  465.54  466.14  466.74  467.34  467.94  468.52  468.52
  468.52  468.17  467.26  466.37  465.47  464.57  464.12  464.12  463.67  462.76
   461.9  461.78  461.42  455.42     451  451.05  451.11  451.11  451.18  451.14
  451.06  450.95  450.89   450.8  450.71  450.48  450.35  450.26  450.19  450.13
  450.02  449.93  449.91  449.85  449.76   449.7  449.75  449.84  449.88  449.38
  449.45  449.84  450.81  451.01   451.8  451.93  451.85  451.87  452.24   452.5
  452.72  452.87  452.79  453.06  453.41  453.47  453.67  453.99   454.4  454.41
  458.58
                                                          449.96  450.36  450.96
  451.56  452.16  452.76  453.36  453.96  454.56  455.16  455.76  456.34  456.34
  456.34  455.99  455.08  454.19  453.29  452.39  451.94  451.94  451.49  450.58
  449.72   449.6
Pier Skew, UpSta & Num, DnSta & Num=  ,365, 2 ,768, 2 , 0 , 0 , 0 ,,
       3       3
     405     460
       3       3
     405     460
Pier Skew, UpSta & Num, DnSta & Num=  ,490, 2 ,893, 2 , 0 , 0 , 0 ,,
       3       3
     405     460
       3       3
     405     460
Pier Skew, UpSta & Num, DnSta & Num=  ,615, 2 ,1018, 2 , 0 , 0 , 0 ,,
       3       3
     405     460
       3       3
     405     460
Pier Skew, UpSta & Num, DnSta & Num=  ,740, 2 ,1143, 2 , 0 , 0 , 0 ,,
       3       3
     405     460
       3       3
     405     460
Pier Skew, UpSta & Num, DnSta & Num=  ,865, 2 ,1268, 2 , 0 , 0 , 0 ,,
       3       3
     405     460
       3       3
     405     460
Pier Skew, UpSta & Num, DnSta & Num=  ,990, 2 ,1393, 2 , 0 , 0 , 0 ,,
       3       3
     405     460
       3       3
     405     460
Pier Skew, UpSta & Num, DnSta & Num=  ,1115, 2 ,1518, 2 , 0 , 0 , 0 ,,
       3       3
     405     460
       3       3
     405     460
Pier Skew, UpSta & Num, DnSta & Num=  ,1240, 2 ,1643, 2 , 0 , 0 , 0 ,,
       3       3
     405     460
       3       3
     405     460
Pier Skew, UpSta & Num, DnSta & Num=  ,1365, 2 ,1768, 2 , 0 , 0 , 0 ,,
       3       3
     405     460
       3       3
     405     460
Pier Skew, UpSta & Num, DnSta & Num=  ,1514, 2 ,1917, 2 , 0 , 0 , 0 ,,
       3       3
     405     460
       3       3
     405     460
Pier Skew, UpSta & Num, DnSta & Num=  ,1713, 2 ,2116, 2 , 0 , 0 , 0 ,,
       3       3
     405     460
       3       3
     405     460
Pier Skew, UpSta & Num, DnSta & Num=  ,1860, 2 ,2263, 2 , 0 , 0 , 0 ,,
       3       3
     405     460
       3       3
     405     460
Pier Skew, UpSta & Num, DnSta & Num=  ,1995, 2 ,2398, 2 , 0 , 0 , 0 ,,
       3       3
     405     460
       3       3
     405     460
BR Coef=-1 , 0 , 0 ,, 0 ,,,0.8,-1,,0,
WSPro=,,,, 1 ,,,, 0 ,,,, 0 ,,,,-1 ,-1 ,-1 , 0 , 0 , 0 , 0 , 0
BC Design=,, 0 ,, 0 ,,,,,,
BC Use User HTab Curves=0
BC User HTab FreeFlow(D)= 0

Type RM Length L Ch R = 1 ,54699   ,7.91,54,110.52
BEGIN DESCRIPTION:
Added for Wildlife Parkway - 2009 TNRIS
END DESCRIPTION:
XS GIS Cut Line= 5
   2425417.72204 6969171.4750458 2424813.2655725 6969204.8880367
 2423612.1974366 6969291.2631921 2422887.1047266 6969339.8513495
 2421612.2457278 6969268.8925019
#Sta/Elev= 30
     -51  451.68     597  454.61  618.73  453.23  648.03  446.33  744.05  438.24
  744.66  434.56  745.97  436.71   747.9  434.23  791.54  440.79 1452.09   441.5
 1663.67  420.41 1912.01  418.19 1933.76  410.87 2002.94  407.25 2043.21  409.66
 2067.95  415.02 2089.07  429.66 2109.78  434.83 2136.81  436.57 2164.18  433.03
 2197.93  436.93 2440.23  443.78 2498.43  442.79 2719.49   448.2 2934.29  444.93
 3289.23  445.76  3499.8  449.22 3686.45  458.58 3703.74  456.22 3761.42  458.68
#Mann= 4 ,-1,0
     -51    .075       0 1452.09     .06       0 1912.01     .05       0
 2109.78    .085       0
#XS Ineff= 2 ,-1
       0    1450     440 2538.86 3761.42     456
Permanent Ineff=
       T       T
Bank Sta=1452.09,2109.78
XS Rating Curve= 0 ,0
Exp/Cntr=0.3,0.1

Type RM Length L Ch R = 1 ,54645   ,3.86,56,171.74
BEGIN DESCRIPTION:
Added for Wildlife Parkway - 2009 TNRIS
END DESCRIPTION:
XS GIS Cut Line= 6
  2425421.627872 6969170.6272785 2424819.8843256 6969202.3923068
 2423612.4182366 6969277.3481937 2422644.2843461 6969219.8155003
 2421968.3759211  6969052.834207 2421237.9088781 6968557.6130846
#Sta/Elev= 30
     -45  451.67   607.3  453.97   629.4  452.41  657.43     446  750.42  438.22
  758.68  434.88  797.88  441.11 1444.35  441.97 1656.53  420.35 1888.79  418.88
 1907.18  410.84 1972.17   407.2 2031.72  413.42 2067.44  434.27 2087.81  437.62
 2142.95  436.49 2236.75  442.94 2373.17  441.64 2477.31  445.39 3033.09  443.54
 3265.78  445.58 3395.17  448.07 3615.11   458.3 3799.31  459.91 3969.77  463.86
 3993.54  466.86 4146.65  465.18 4257.81  467.74 4293.17  471.98    4317  470.65
#Mann= 4 ,-1,0
     -45    .075       0 1444.35     .06       0 1888.79     .05       0
 2087.81    .085       0
#XS Ineff= 2 ,-1
       0    1445     440 2319.18 3761.42     456
Permanent Ineff=
       T       T
Bank Sta=1444.35,2087.81
XS Rating Curve= 0 ,0
Exp/Cntr=0.3,0.1

Type RM Length L Ch R = 1 ,54589   ,5.14,30,101.47
BEGIN DESCRIPTION:
Added for Wildlife Parkway - 2009 TNRIS
END DESCRIPTION:
XS GIS Cut Line= 6
  2425424.752866 6969169.4120578 2423612.7984852 6969271.1746496
 2422535.2510996  6968999.279196  2422455.961232 6968865.7538725
  2422270.863177 6968579.8118591 2421309.0065049  6968241.209846
#Sta/Elev= 30
     -45  451.66  610.27  453.64  661.13  445.75  751.08  438.35   753.5  435.21
  799.37  441.25 1446.95  442.11 1650.73  420.32  1862.2     420 1862.84  414.89
 1883.43  409.03 1936.68  407.15 2003.75  414.08 2010.43  416.12 2029.48  431.98
  2046.9  437.91  2082.4  437.28  2151.5   445.2  2227.5  447.19 2742.41  439.99
 2884.73  440.93 3040.02  436.07 3200.12  434.08 3252.61  438.03 3319.15  431.56
 3387.04  444.03  3570.6  456.58 3889.46  457.68 4319.55   468.5 4400.36  464.85
#Mann= 7 ,-1,0
     -45    .075       0 1446.95     .06       0  1862.2     .05       0
  2046.9    .085       0 2884.73      .1       0 3040.02    .045       0
 3252.61    .085       0
#XS Ineff= 4 ,-1
  651.48  800.83  439.76 2387.18 2884.73     453 2884.73 3040.02     460
 3040.02 4400.36     453
Permanent Ineff=
       T       F       T       F
#Block Obstruct= 1 ,-1
 2884.73 3040.02     460
Bank Sta=1446.95,2046.9
XS Rating Curve= 0 ,0
Exp/Cntr=0.3,0.1

Type RM Length L Ch R = 1 ,54559   ,43.64,172,476.66
BEGIN DESCRIPTION:
Added for Wildlife Parkway - 2009 TNRIS
---------------------------------------------------------------------
CDC GP090712-1 Race Partners Gas Well Pad Site
Located in ROB.
---------------------------------------------------------------------
END DESCRIPTION:
XS GIS Cut Line= 5
  2425438.815174 6969167.3287287 2423607.6390467 6969263.4082609
 2422813.0979849 6968961.7389167 2422433.5741376 6968312.1562264
 2421320.3066791 6968074.3351797
#Sta/Elev= 30
     -50  451.55  619.93  453.18  761.43  435.83  806.14  441.42 1442.05  442.01
 1644.57  420.29 1851.43     420 1855.74   414.3  1867.2  409.32 1923.74  407.14
 1992.75  414.84 2002.93  418.69 2007.38  427.22  2016.1  432.82 2030.66  438.11
 2138.14  446.79  2235.9  439.96 2366.59  447.06 2686.61  441.06 2900.85  442.01
 2970.46  436.94 3148.43  435.86 3186.86   433.6 3210.62  442.76 3217.74  444.06
 3243.98  434.34 3299.99  443.94 3984.31  450.54 4286.34   463.2 4521.87  462.33
#Mann= 8 ,-1,0
     -50    .075       0 1442.05     .06       0 1855.74     .05       0
 2030.66    .085       0 2686.61      .1       0 2970.46    .045       0
 3148.43    .065       0 3210.62    .085       0
#XS Ineff= 6 ,-1
  652.41  808.69  439.88 2138.14 2366.59     442 2482.22 2681.25  449.51
 2681.25 2970.46     460 2970.46    3597  449.51    3597 4521.87     460
Permanent Ineff=
       T       T       F       T       F       T
#Block Obstruct= 1 ,-1
 2681.25 2970.46     460
Bank Sta=1442.05,2030.66
XS Rating Curve= 0 ,0
Exp/Cntr=0.3,0.1

Type RM Length L Ch R = 1 ,54387   ,0,0,0
BEGIN DESCRIPTION:
55761
END DESCRIPTION:
XS GIS Cut Line= 4
  2425439.534005 6969165.1860164 2424511.6149291 6969193.4940306
 2423701.0840698 6969212.1413031 2421194.7491875 6966200.3034947
#Sta/Elev= 30
 -588.09  452.22  -76.52  439.81  981.15  439.63 1062.37  448.26 1156.52  443.21
 1185.61  413.94 1223.66  416.74 1249.34     407 1330.23   414.6 1353.22  433.46
 1422.27  447.02 1560.34  423.24 1619.31  422.39 1690.44  433.81  1753.8  423.16
  2017.3  425.97 2127.74  446.88  2191.4  448.47  2338.7  443.37 2900.78  443.21
 3202.75  450.17 3329.97  430.34 3399.26  435.78 3469.19  431.71 3571.87  448.99
 3603.85  435.74 3626.83  437.06 3639.38  448.63 4158.02  443.12 5058.02  452.84
#Mann= 4 ,-1,0
 -588.09    .075       0  981.15     .12       0 1062.37     .05       0
 1422.27    .085       0
#XS Ineff= 2 , 0
                            2900             450
Permanent Ineff=
       F       F
#Block Obstruct= 3 ,-1
     271534.0001     440    1457    2098     442    3289    3631     436
Bank Sta=1062.37,1422.27
XS Rating Curve= 0 ,0
Exp/Cntr=0.3,0.1

River Reach=West Fork Split ,wfs
Reach XY= 30
      2423548.65      6969142.43      2424328.33      6969304.48
      2424884.32       6969934.5      2426135.87      6970989.99
      2427952.18      6972131.21      2429709.24      6973064.19
       2430496.5       6973174.4      2433207.03      6973064.51
      2433491.54      6972883.52      2434356.44        6972755.
      2434605.27      6972622.64      2434468.97      6972419.33
      2434784.65      6972362.14       2435043.7      6971972.11
      2435290.33       6972077.3      2435565.25      6972061.98
      2435607.22      6971930.23      2435513.06      6971894.13
      2435503.28      6971720.76      2435911.65      6971768.86
      2436029.27      6971643.43      2436010.53      6971521.14
      2436642.57      6971341.07       2436847.2      6971385.03
      2436899.94      6971179.472437062.405932366971170.73997248
2437168.014923466970795.828054062437115.210427916970241.38085076
  2437410.9156036968989.91430618        2438660.      6965610.97

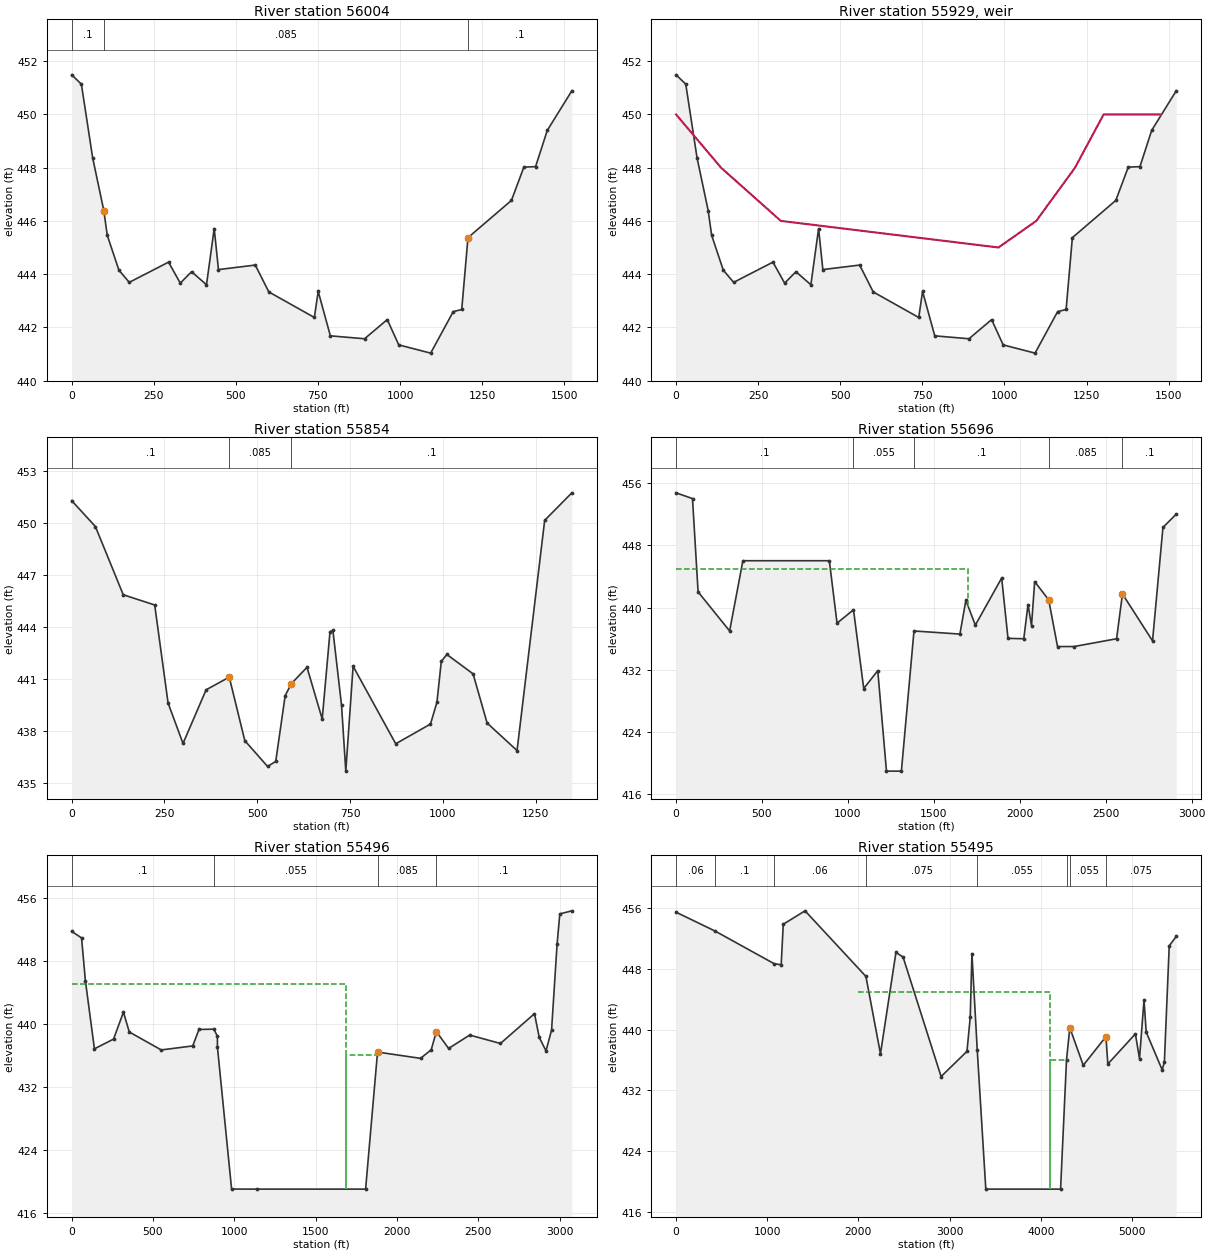
Type RM Length L Ch R = 1 ,56004   ,150,150,150
XS GIS Cut Line= 3
  2424292.359134 6970034.3689893 2424917.0370185 6969236.7600202
 2425214.2270409 6969066.4109515
#Sta/Elev= 30
       0  451.49   29.53  451.14   63.92  448.37    97.8  446.39  108.36  445.46
  143.75  444.15  175.36  443.69  295.04  444.45   330.7  443.66  365.07  444.09
  410.58   443.6  434.04  445.71  447.06  444.17  559.15  444.34  600.43  443.33
  739.05  442.37  750.72  443.35  787.79  441.68  891.94  441.57  961.05  442.29
   996.1  441.34 1093.24  441.03 1162.02  442.59 1187.84  442.67 1206.87  445.37
 1339.25  446.77 1377.03  448.02 1412.76  448.04 1448.34   449.4 1523.22  450.89
#Mann= 3 ,0,0
       0      .1       0    97.8    .085       0 1206.87      .1       0
Bank Sta=97.8,1206.87
XS Rating Curve= 0 ,0
Exp/Cntr=0.3,0.1

Type RM Length L Ch R = 5 ,55929   ,,,
BEGIN DESCRIPTION:
Hardrock Road - Weir
SPLIT FLOW FOR 50YR AND 100 YR
END DESCRIPTION:
Node Name=Hardrock Road -
IW Pilot Flow=0
#Inline Weir SE= 8
       0     450     137     448     319     446     982     445    1097     446
    1215     448    1302     450 1475.74     450
IW Dist,WD,Coef,Skew,MaxSub,Min_El,Is_Ogee,SpillHt,DesHd
40,30,2.6,0,0.95,, 0 ,,,10,10,
Inline Weir Flap Gates= 0
IW Outlet Rating Curve= 0 ,False,,

Type RM Length L Ch R = 1 ,55854   ,248,158,105
XS GIS Cut Line= 3
  2424424.930063 6970129.5279197 2425049.6079476 6969331.9189507
   2425346.79797 6969161.5698819
#Sta/Elev= 30
       0   451.3   63.95   449.8  138.92  445.86  223.62  445.27  259.69   439.6
  299.88  437.27  362.15  440.37  424.42   441.1  466.36  437.43  527.66  435.94
  549.61  436.23  575.04  440.03  591.54  440.72   633.8  441.67  674.79  438.68
  695.76  443.72   703.6   443.8  726.84  439.48  738.33  435.67  758.03  441.73
  872.81  437.25  966.45  438.39  983.84  439.65  995.52  442.01 1010.56  442.41
 1081.17  441.29 1118.92  438.45  1199.6  436.86 1273.99  450.16 1347.21  451.75
#Mann= 3 ,0,0
       0      .1       0  424.42    .085       0  591.54      .1       0
Bank Sta=424.42,591.54
XS Rating Curve= 0 ,0
Exp/Cntr=0.3,0.1

Type RM Length L Ch R = 1 ,55696   ,170,200,112
XS GIS Cut Line= 5
  2424292.896206  6971734.893803  2424469.545459  6971663.307989
  2424867.461986   6969744.00835  2425234.649572  6969231.247892
  2425345.326516   6969165.05872
#Sta/Elev= 30
       0  454.74   95.71     454  128.19  442.02  311.68     437  388.86  446.02
  891.84  446.02   936.7     438 1032.42  439.72 1091.94  429.61 1173.64   431.9
 1224.35     419  1311.1     419 1384.43     437 1651.58   436.6 1686.31  440.93
 1741.45  437.75 1894.64   443.8 1931.41  436.05 2023.32     436 2047.83  440.39
 2068.26   437.7 2086.64  443.34 2168.12     441 2219.65     435 2315.83     435
 2563.17     436 2597.51  441.75 2772.39  435.73 2833.02   450.3 2910.35     452
#Mann= 5 ,-1,0
       0      .1       0 1032.42    .055       0 1384.43      .1       0
 2168.12    .085       0 2597.51      .1       0
#XS Ineff= 2 , 0
            1700     445
Permanent Ineff=
       T       F
Bank Sta=2168.12,2597.51
XS Rating Curve= 0 ,0
Exp/Cntr=0.3,0.1

Type RM Length L Ch R = 1 ,55496   ,1,1,1
BEGIN DESCRIPTION:
Mitigation pond shown from 52592 - 55496
END DESCRIPTION:
XS GIS Cut Line= 5
  2424275.091123 6971782.0498771 2424698.7671138 6971667.3040437
 2424979.7445702  6969848.171199 2425247.1275656 6969226.2967866
   2425349.23891 6969165.3992706
#Sta/Elev= 30
       0  451.74   60.72  450.91   84.31  445.48  139.79  436.82   257.5  438.06
  318.31  441.48  354.23  438.96  550.71  436.68   744.4  437.19  782.56  439.28
  874.26  439.32     896  438.42  896.36     437  983.25  419.01 1139.81     419
 1807.27     419 1880.63  436.41 2145.22  435.61 2210.72  436.71 2242.41  439.01
 2317.69  436.87 2447.17  438.57 2636.52   437.5 2845.75  441.29 2874.83  438.28
 2916.52  436.56 2950.71   439.2 2984.64  450.13 3001.47  453.96 3075.46  454.35
#Mann= 4 ,-1,0
       0      .1       0  874.26    .055       0 1880.63    .085       0
 2242.41      .1       0
#XS Ineff= 2 ,-1
       0    1687     445    1687    1900     436
Permanent Ineff=
       T       T
Bank Sta=1880.63,2242.41
XS Rating Curve= 0 ,0
Exp/Cntr=0.3,0.1

Type RM Length L Ch R = 1 ,55495   ,217,290,214
BEGIN DESCRIPTION:
XS 55205 - 55495 represent Hardrock STA 459 - 1083
Mitigation pond shown from 52592 - 55496
END DESCRIPTION:
XS GIS Cut Line= 5
   2424134.17277 6974459.7964902 2424698.7671138 6971667.3040437
 2424979.7445702  6969848.171199 2425247.1275656 6969226.2967866
   2425349.23891 6969165.3992706
#Sta/Elev= 30
       0  455.48  427.17     453 1075.32   448.7 1152.98  448.55  1175.7  453.89
 1414.61  455.66 2082.29  447.02 2241.74  436.83 2411.55  450.18 2489.61  449.57
 2906.62  433.83 3190.58  437.15 3226.23  441.65 3244.89  450.03 3302.88  437.38
    3397     419    4217     419 4282.12  436.01 4318.27  440.26 4465.71  435.31
 4714.62  439.09 4735.37  435.48 5037.54  439.45 5082.59  436.19 5132.12  443.91
 5156.15  439.69 5331.67   434.7 5355.38  435.76 5408.62  451.05 5485.51  452.28
#Mann= 8 ,-1,0
       0     .06       0  427.17      .1       0 1075.32     .06       0
 2082.29    .075       0 3302.88    .055       0 4282.12    .075       0
 4318.27    .055       0 4714.62    .075       0
#XS Ineff= 3 ,-1
     400    1300     447    2000    4098     445    4098    4300     436
Permanent Ineff=
       F       T       T
Bank Sta=4318.27,4714.62
XS Rating Curve= 0 ,0
Exp/Cntr=0.3,0.1