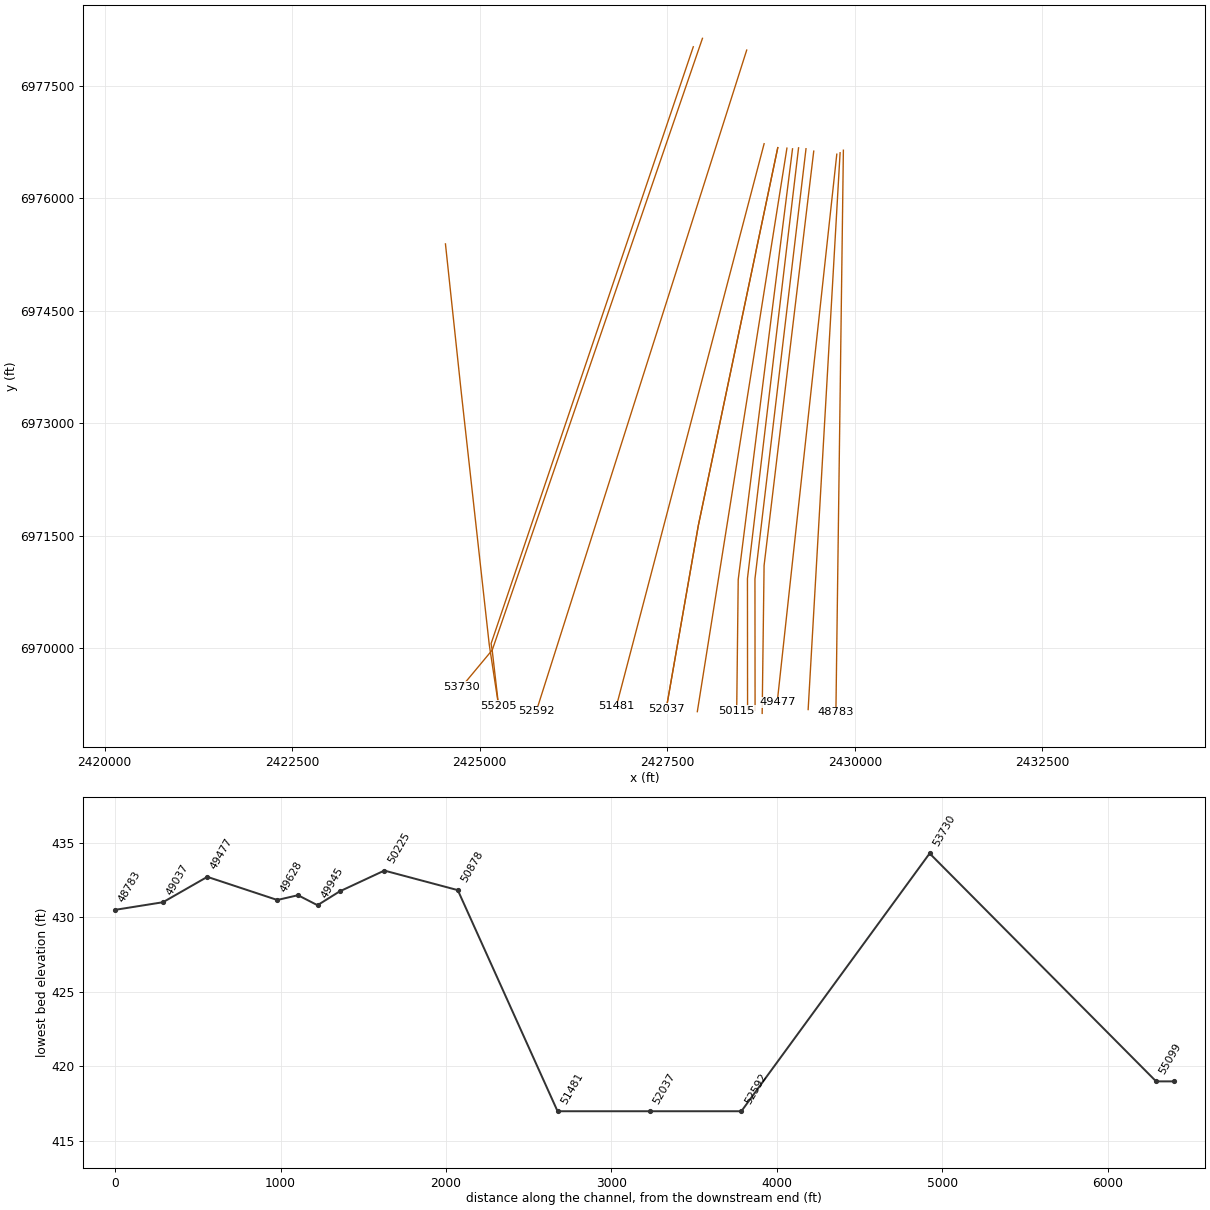
HEC-RAS study CDC_Consolidated_Model.prj: Upper Trinity CDC Consolidated Model

--- CDC_Consolidated_Model.g12 (geometry) --- (continued)

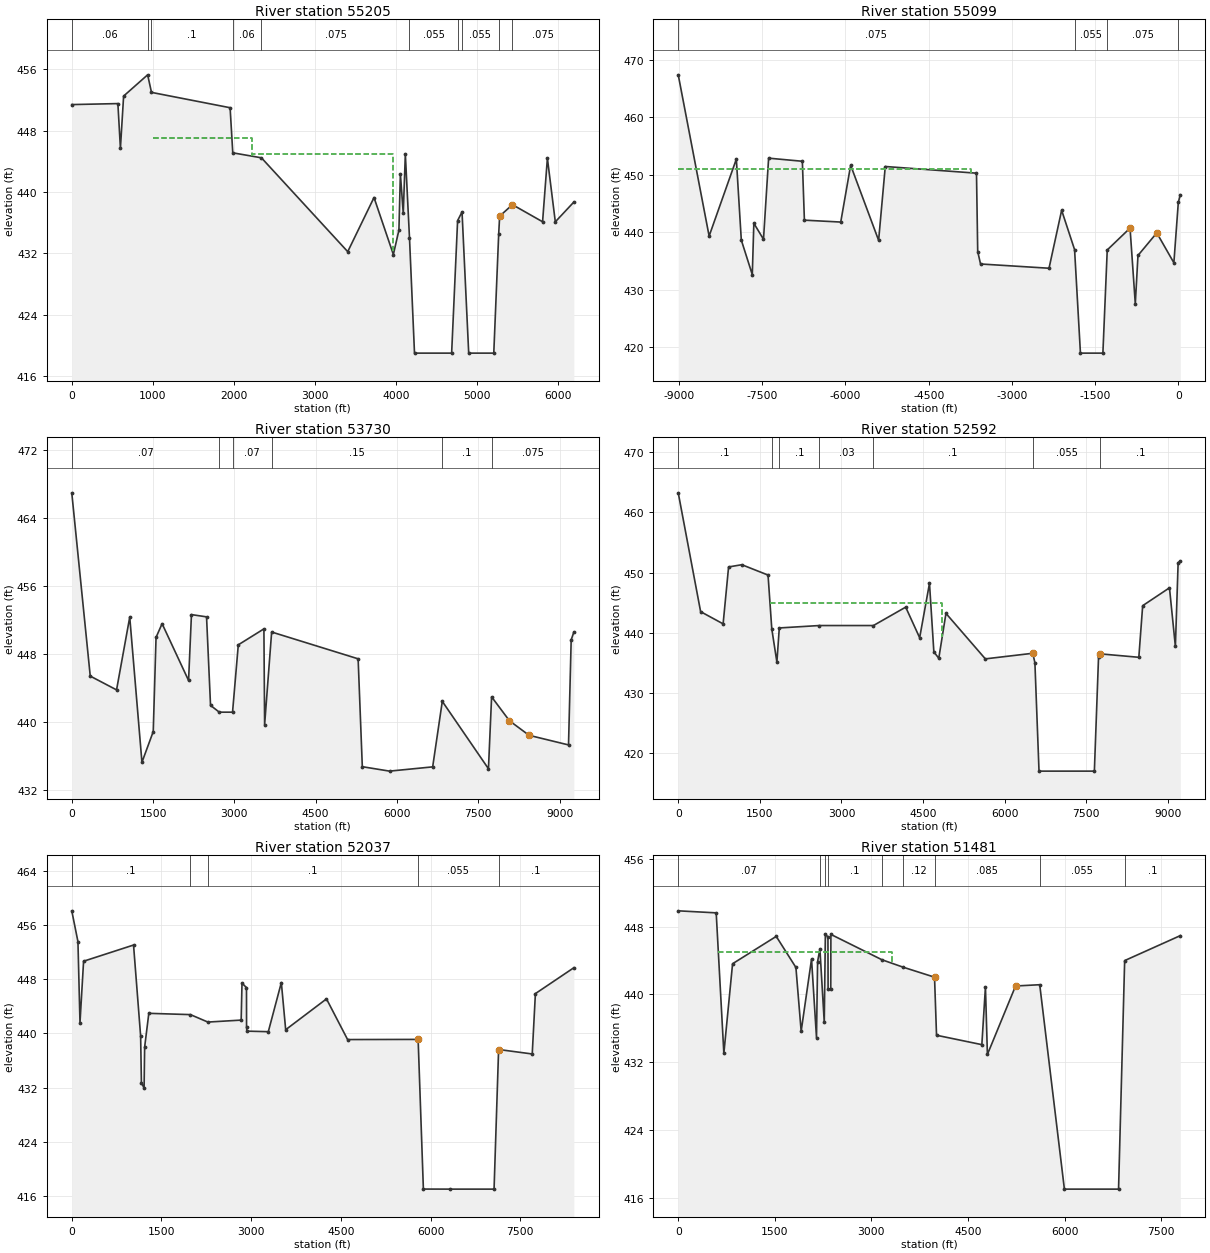
Type RM Length L Ch R = 1 ,55205   ,444,106,44
BEGIN DESCRIPTION:
XS 55205 - 55495 represent Hardrock STA 950 - 1984
Mitigation pond shown from 52592 - 55496
END DESCRIPTION:
XS GIS Cut Line= 4
  2424543.026939 6975388.6158267 2424753.8559144 6973409.7746401
 2425126.6350245 6970048.7429763 2425251.2184367 6969233.8430313
#Sta/Elev= 30
       0  451.41   569.1  451.54  600.34  445.71  639.82  452.52  936.31  455.29
  983.89     453    1954     451 1986.95  445.12  2340.6  444.47 3405.61  432.23
 3729.88  439.29 3968.71  431.86 4037.25  435.04 4055.38  442.39 4090.82  437.22
 4116.59  444.95 4167.84  434.02  4229.6     419 4687.95     419 4761.54  436.28
  4816.2  437.41  4898.5     419    5208     419 5268.82  434.58 5280.48  436.86
 5438.16  438.36 5810.14  436.13 5869.61  444.41 5967.28  436.12 6196.05   438.7
#Mann= 10 ,-1,0
       0     .06       0  936.31     .06       0  983.89      .1       0
 1986.95     .06       0  2340.6    .075       0 4167.84    .055       0
 4761.54    .075       0  4816.2    .055       0 5268.82    .075       0
 5438.16    .075       0
#XS Ineff= 3 ,-1
    1000    2230     447    2230    3967     445    4000    5500     432
Permanent Ineff=
       T       T       T
#Block Obstruct= 2 , 0
             900     450
Bank Sta=5280.48,5438.16
XS Rating Curve= 0 ,0
Exp/Cntr=0.3,0.1

Type RM Length L Ch R = 1 ,55099   ,1369,1369,1399
BEGIN DESCRIPTION:
Mitigation pond shown from 52592 - 55496
END DESCRIPTION:
XS GIS Cut Line= 5
  2427846.699466 6978016.4790093 2427274.6116996 6976327.8524653
 2425151.3869435 6970060.7498421 2425165.2104066 6969980.9452117
 2425251.2184367 6969233.8430313
#Sta/Elev= 30
-9015.15  467.39-8458.27  439.35-7967.69  452.73-7878.18  438.66-7680.03  432.65
-7652.26  441.58 -7478.1   438.8-7385.74   452.9-6777.58  452.36-6740.71  442.12
-6085.49  441.79-5906.95  451.67-5402.73  438.61-5282.81  451.45-3638.43  450.29
-3616.35  436.67-3565.36   434.5-2330.72  433.76-2103.31  443.84-1870.15     437
-1764.39     419-1359.66     419-1281.25  436.94 -870.05  440.74 -775.43  427.57
  -727.2  435.98 -388.11  439.91  -80.02  434.71       0  445.21   36.05  446.54
#Mann= 4 ,-1,0
-9015.15    .075       0-1870.15    .055       0-1281.25    .075       0
       0    .075       0
#XS Ineff= 4 ,-1
-9015.15-3732.15     451-3732.15   -2000  440.19   -2000 -388.11     426
 -388.11248.3604  438.48
Permanent Ineff=
       T       F       T       F
Bank Sta=-870.05,-388.11
XS Rating Curve= 0 ,0
Exp/Cntr=0.3,0.1

Type RM Length L Ch R = 1 ,53730   ,1138,1138,1138
XS GIS Cut Line= 5
     2427968.919     6978128.879      2425166.88     6969975.454
     2424756.705     6969482.786     2424756.705     6969482.786
2424756.082413626969482.03820116
#Sta/Elev= 30
       0  466.98  340.87  445.44  826.31  443.82 1069.55  452.37 1294.81  435.31
 1503.16  438.92 1554.98  449.99 1666.57   451.62155.021444.92282208.091 452.667
2486.711452.40222560.193     4422721.446   441.22966.387   441.23072.528449.1143
3545.061450.9887 3558.14  439.73 3687.83  450.62 5283.42  447.47 5360.69  434.79
 5862.92  434.27 6658.89  434.77 6836.28  442.47 7687.99  434.55 7746.08     443
 8075.38  440.19 8437.37  438.48 9165.09  437.35  9214.4   449.7 9263.51  450.61
#Mann= 6 ,-1,0
       0     .07       02721.446     .03       02966.387     .07       0
 3687.83     .15       0 6836.28      .1       0 7746.08    .075       0
Bank Sta=8075.38,8437.37
XS Rating Curve= 0 ,0
Exp/Cntr=0.3,0.1

Type RM Length L Ch R = 1 ,52592   ,550,555,576
BEGIN DESCRIPTION:
XS 51481 - 52592 represent Wildlife Phase 3 North site
STA 8523 - 9016
XS present in current effective.
CDC GP061422-1 Pollo Regio Warehouse
Cross-sections 52592 - 53730
Proect located in LOB.
END DESCRIPTION:
XS GIS Cut Line= 2
  2428558.675076 6977972.3688613 2425753.1252413 6969156.7234349
#Sta/Elev= 30
       0  463.26  411.38  443.51  824.85  441.48  925.47  450.94 1169.06  451.31
 1650.75  449.59 1719.49  440.64 1813.42  435.12 1857.49   440.82592.978   441.2
3588.077   441.2 4180.93  444.26 4437.64  439.17 4618.21  448.22 4698.63  436.82
 4789.26  435.76 4921.03  443.22 5644.71  435.66 6517.48  436.59 6556.11     435
 6631.65     417 7648.99     417 7725.93     436 7760.53  436.49 8466.27  435.92
 8536.94   444.5 9029.39  447.47  9138.2  437.72 9188.81  451.67 9228.76  451.88
#Mann= 7 ,-1,0
       0      .1       0 1719.49    .065       0 1857.49      .1       0
2592.978     .03       03588.077      .1       0 6517.48    .055       0
 7760.53      .1       0
#XS Ineff= 3 ,-1
 1683.04    4851     445    6500    8000     425    9020    9188     445
Permanent Ineff=
       T       T       T
Bank Sta=6517.48,7760.53
XS Rating Curve= 0 ,0
Exp/Cntr=0.3,0.1

Type RM Length L Ch R = 1 ,52037   ,550,556,550
XS GIS Cut Line= 4
     2428972.806     6976671.722     2427914.523        6971639.
     2427486.631     6969195.005     2427486.631     6969195.005
#Sta/Elev= 30
       0  458.08  103.22  453.54  137.52  441.58  197.58  450.64 1033.15  453.03
 1151.68   439.6 1164.79  432.72 1209.62  431.91 1218.69  437.95 1288.68  442.95
  1984.5  442.76 2276.31  441.66 2833.24  441.95 2847.28  447.41 2922.41  446.74
 2923.26  440.92 2928.88  440.32 3287.17  440.24  3505.2  447.49 3577.78  440.53
 4260.27  445.084613.287 439.078    5793   439.1 5880.87  417.01 6331.65     417
    7063     417 7139.04  437.61 7701.39  436.95 7754.39  445.86 8397.43  449.68
#Mann= 5 ,-1,0
       0      .1       0  1984.5    .065       0 2276.31      .1       0
    5793    .055       0 7139.04      .1       0
#XS Ineff= 2 ,-1
 1088.87 4256.82     445    5800 7640.17     425
Permanent Ineff=
       T       T
Bank Sta=5793,7139.04
XS Rating Curve= 0 ,0
Exp/Cntr=0.3,0.1

Type RM Length L Ch R = 1 ,51481   ,484,603,573
BEGIN DESCRIPTION:
XS 51481 - 52592 represent Wildlife Phase 3 North site STA 6920 - 7751
XS present in current effective.
END DESCRIPTION:
XS GIS Cut Line= 3
  2428790.735635 6976724.1528538 2428779.8052116 6976682.5387638
  2426820.873762 6969224.4336013
#Sta/Elev= 30
       0  449.88  589.71  449.64  708.61  433.04  844.05  443.63  1522.3  446.86
 1827.83  443.19 1909.45  435.65 2070.55  444.18 2147.65  434.89 2164.71  443.88
 2200.56  445.37 2268.28  436.69 2285.34  447.13 2325.41  446.782327.862 440.641
2369.219 440.6252371.287 447.0943163.269 444.102 3493.95  443.22 3980.97  442.04
 4012.05  435.18 4716.01  434.07 4771.79   440.9 4802.25  432.91 5239.74     441
    5615  441.15 5998.25     417 6839.46     417 6934.35     444 7798.73  446.95
#Mann= 9 ,-1,0
       0     .07       0 2200.56     .05       0 2285.34     .07       0
 2325.41      .1       03163.269     .07       0 3493.95     .12       0
 3980.97    .085       0    5615    .055       0 6934.35      .1       0
#XS Ineff= 1 ,-1
  620.18    3320     445
Permanent Ineff=
       T
Bank Sta=3980.97,5239.74
XS Rating Curve= 0 ,0
Exp/Cntr=0.3,0.1

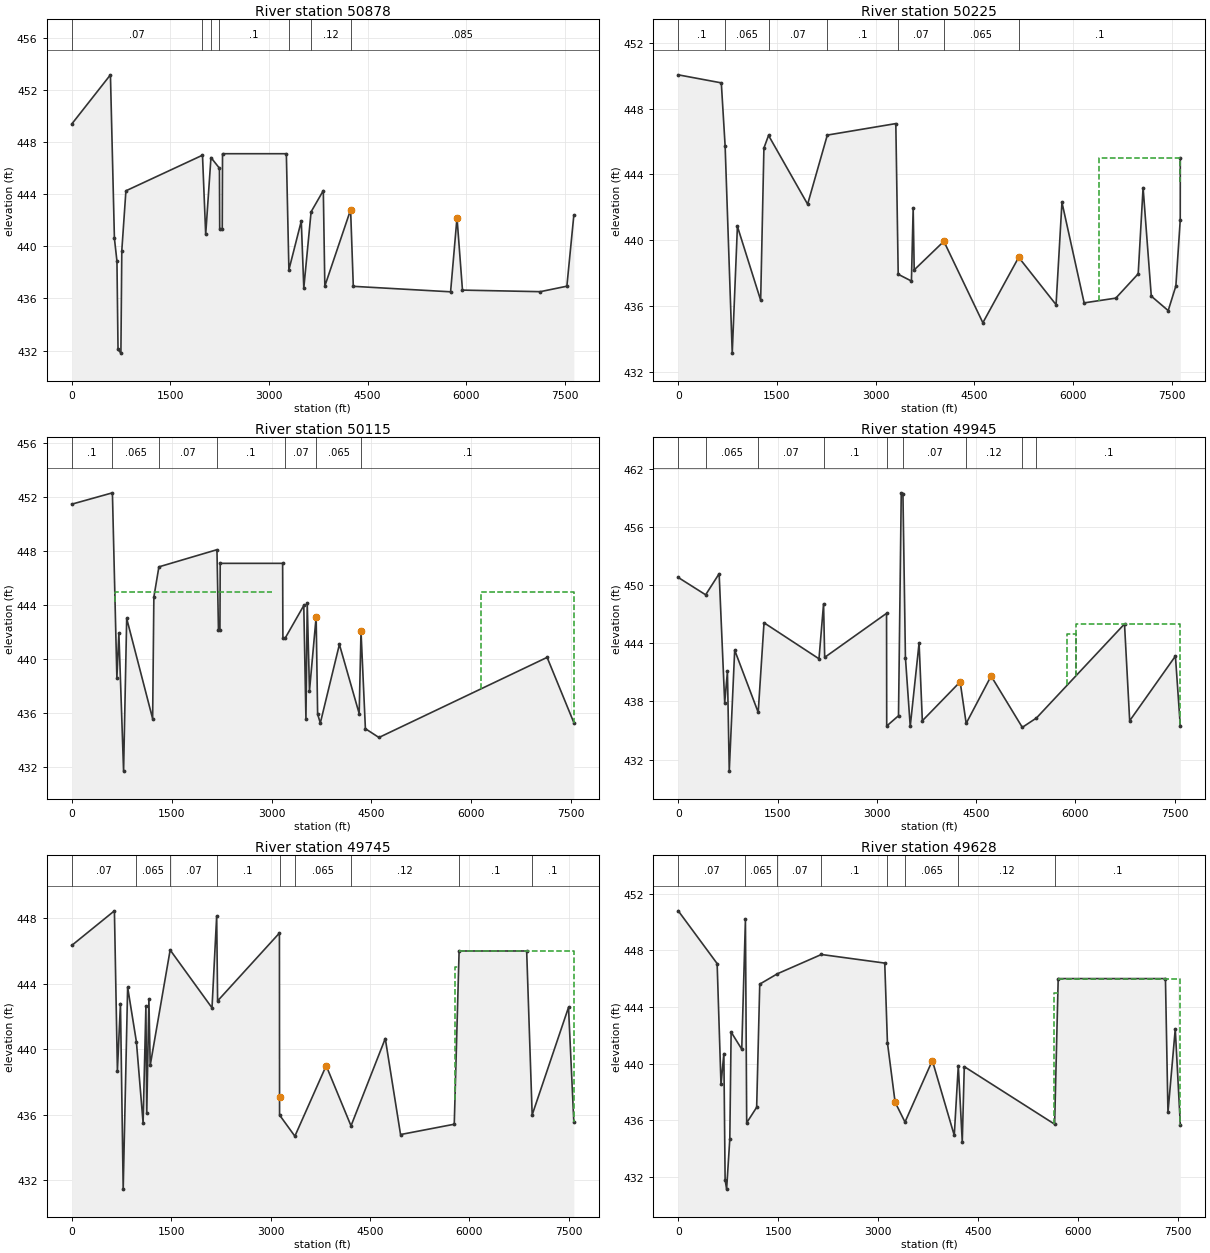
Type RM Length L Ch R = 1 ,50878   ,484,444,493
XS GIS Cut Line= 4
     2428972.806     6976671.722     2427914.523        6971639.
     2427486.631     6969195.005     2427486.631     6969195.005
#Sta/Elev= 30
       0  449.37  588.11  453.14  648.69   440.6  687.16  438.86  703.55  432.09
  747.27  431.81  760.98  439.67  823.54  444.25  1988.3  446.98 2036.97  440.91
 2117.03   446.82245.968 445.9842250.055 441.3132288.885 441.2972292.972 447.094
3263.725 447.0943302.555 438.194 3490.82  441.93 3529.16   436.8 3640.22  442.64
    3826  444.27 3849.12  436.95 4241.11   442.8 4282.08  436.93 5761.85  436.51
 5859.35  442.19  5942.5  436.64 7126.06  436.52  7530.4  436.94 7636.53  442.39
#Mann= 7 ,-1,0
       0     .07       0  1988.3     .05       0 2117.03     .07       0
2245.968      .1       03302.555     .07       0 3640.22     .12       0
 4241.11    .085       0
#XS Ineff= 1 ,-1
  620.18    2400     445
Permanent Ineff=
       T
Bank Sta=4241.11,5859.35
XS Rating Curve= 0 ,0
Exp/Cntr=0.3,0.1

Type RM Length L Ch R = 1 ,50225   ,207,271,328
BEGIN DESCRIPTION:
This cross section corresponds to cross section 50225 of the non-georeferenced CDC model which was the source of this model.
END DESCRIPTION:
XS GIS Cut Line= 3
  2429094.791786 6976665.2737065 2428995.4169851 6976040.3087491
 2427900.3945688  6969153.743454
#Sta/Elev= 30
       0  450.07   654.7  449.58  712.53  445.74  820.76  433.12   899.3  440.84
 1252.62  436.34 1302.23  445.61 1372.33  446.38 1966.47  442.19 2265.69   446.4
3306.666   447.13343.118 437.923 3544.05  437.51 3570.58  441.973586.134 438.189
  4037.1  439.93 4629.69  434.97 5173.36  438.95 5175.31  438.95 5742.18  436.07
 5831.75   442.3 6168.85  436.18 6649.95  436.47  6990.4  437.95 7064.74   443.2
 7189.28  436.59 7446.47  435.71 7562.92  437.21 7629.24  441.22 7630.48     445
#Mann= 7 ,-1,0
       0      .1       0  712.53    .065       0 1372.33     .07       0
 2265.69      .1       03343.118     .07       0  4037.1    .065       0
 5175.31      .1       0
#XS Ineff= 2 ,-1
  712.53    3174     445    6400    7630     445
Permanent Ineff=
       T       T
Bank Sta=4037.1,5173.36
XS Rating Curve= 0 ,0
Exp/Cntr=0.3,0.1

Type RM Length L Ch R = 1 ,50115   ,128,133,158
BEGIN DESCRIPTION:
XS added for Wildlife North CDC
END DESCRIPTION:
XS GIS Cut Line= 3
   2429169.45207 6976655.9065992 2428445.4794366 6970912.8363925
 2428425.2101202 6969162.8799187
#Sta/Elev= 30
       0  451.48   610.2  452.32  677.42  438.61  707.15  441.94  778.02  431.72
  824.62  443.02 1214.16   435.6 1232.62   444.6 1308.27  446.84 2180.01  448.11
2202.541 442.1722224.716 442.1562228.747   447.13166.107   447.13170.139 441.541
 3201.28  441.54 3483.74  443.98 3516.06  435.57 3535.47  444.153569.273 437.672
 3669.32  443.14 3691.42  435.94    3732  435.28 4018.48   441.1 4315.38  435.98
 4342.85  442.07 4408.77  434.86 4612.23  434.21 7137.14  440.14  7538.6  435.31
#Mann= 7 ,-1,0
       0      .1       0   610.2    .065       0 1308.27     .07       0
 2180.01      .1       0 3201.28     .07       0 3669.32    .065       0
 4342.85      .1       0
#XS Ineff= 2 ,-1
     650    3011     445    6152  7538.6     445
Permanent Ineff=
       T       T
Bank Sta=3669.32,4342.85
XS Rating Curve= 0 ,0
Exp/Cntr=0.3,0.1

Type RM Length L Ch R = 1 ,49945   ,111,118,127
BEGIN DESCRIPTION:
Fill in Current effective removed for XS 48783 - 49945. There is no longer a building proposed.
XS present in current effective.
XS added for Wildlife North CDC
END DESCRIPTION:
XS GIS Cut Line= 3
    2429249.8233 6976669.1798666 2428568.5654766 6970928.8862291
 2428570.2157357  6969169.200116
#Sta/Elev= 30
       0   450.8  414.14  449.01  617.85  451.19   701.9  437.86  743.03  441.09
  770.55   430.8  852.62  443.29 1207.82  436.87 1295.62  446.12 2126.08   442.4
 2195.15  448.092211.935 442.5473146.447 447.094  3148.9  435.46 3326.94  436.52
 3368.53  459.54 3393.94  459.47 3431.51  442.53 3504.16  435.423637.872 444.034
 3686.89     436 4258.17  440.02 4349.11  435.73 4725.53  440.62 5196.94  435.32
 5411.11  436.29 6740.57     446 6818.76     436 7509.48  442.68 7583.48  435.43
#Mann= 9 ,-1,0
       0      .1       0  414.14    .065       0 1207.82     .07       0
 2195.15      .1       0  3148.9     .07       0 3393.94     .07       0
 4349.11     .12       0 5196.94    .065       0 5411.11      .1       0
#XS Ineff= 3 ,-1
     550    2940     4455872.584 6010.29     445 6010.29 7583.48     446
Permanent Ineff=
       T       T       T
Bank Sta=4258.17,4725.53
XS Rating Curve= 0 ,0
Exp/Cntr=0.3,0.1

Type RM Length L Ch R = 1 ,49745   ,128,125,120
BEGIN DESCRIPTION:
Fill in Current effective removed for XS 48783 - 49945. There is no longer a building proposed.
XS present in current effective.
XS added for Wildlife North CDC
END DESCRIPTION:
XS GIS Cut Line= 3
  2429349.126579 6976657.3944572  2428668.570854  6970923.019443
 2428670.2138953 6969171.3667783
#Sta/Elev= 30
       0  446.34  643.33  448.45  688.44   438.7   734.5  442.79  775.79  431.47
  842.85  443.79  975.08  440.46 1076.07  435.51 1118.27  442.63  1131.1  436.09
 1163.51  443.08 1183.31  439.02 1484.18  446.06 2115.59  442.532185.969 448.141
2200.067 442.9543132.565 447.0943134.579 437.093 3134.79  435.99 3365.64   434.7
    3838     439 4212.62  435.33 4729.52  440.66  4959.9   434.8 5770.06  435.43
 5843.38     446 6862.54     446 6945.51     436 7493.74  442.56 7574.19  435.54
#Mann= 9 ,-1,0
       0     .07       0  975.08    .065       0 1484.18     .07       0
2185.969      .1       0 3134.79     .07       0 3365.64    .065       0
 4212.62     .12       0 5843.38      .1       0 6945.51      .1       0
#XS Ineff= 3 ,-1
     500    2880     445 5780.13 5843.38     445 5843.38 7574.19     446
Permanent Ineff=
       T       T       T
Bank Sta=3134.579,3838
XS Rating Curve= 0 ,0
Exp/Cntr=0.3,0.1

Type RM Length L Ch R = 1 ,49628   ,432,423,424
BEGIN DESCRIPTION:
Fill in Current effective removed for XS 48783 - 49945. There is no longer a building proposed.
XS present in current effective.
XS added for Wildlife North CDC
CDC GP040122-1 Oakdale Industrial III
Cross-section 49628 - 52592
END DESCRIPTION:
XS GIS Cut Line= 3
  2429452.213971 6976625.4404528 2428790.3215947 6971102.4370631
 2428764.8285355 6969130.8550483
#Sta/Elev= 30
       0  450.78  583.69  447.06  641.68  438.53  684.51  440.71  703.54   431.8
  725.96  431.15  773.91   434.7  793.64  442.23  953.13  441.02 1008.28  450.18
 1027.29  435.83 1176.78  436.92 1223.21  445.61 1487.76  446.34 2147.89   447.7
3098.797 447.0943139.083 441.485 3254.18 437.283 3402.66  435.88 3812.73  440.22
 4142.02  434.94 4202.44  439.86 4262.02  434.49 4292.31  439.79    5648  435.73
 5701.65     446 7310.84     446 7348.64  436.56 7458.21  442.45 7533.96   435.7
#Mann= 8 ,-1,0
       0     .07       0 1008.28    .065       0 1487.76     .07       0
 2147.89      .1       03139.083     .07       0 3402.66    .065       0
 4202.44     .12       0    5648      .1       0
#XS Ineff= 3 ,-1
  511.09    2584     445    5645 5701.65     445 5701.65 7533.96     446
Permanent Ineff=
       T       T       T
Bank Sta=3254.18,3812.73
XS Rating Curve= 0 ,0
Exp/Cntr=0.3,0.1

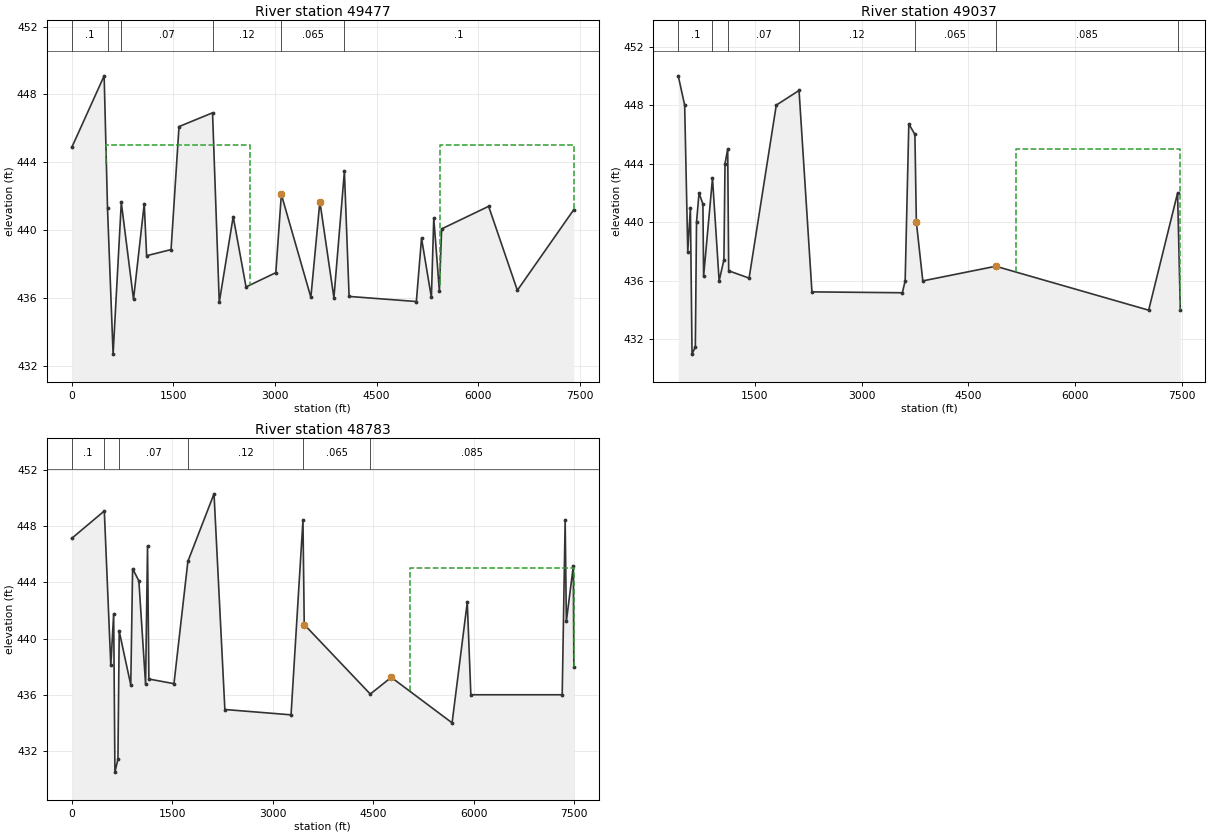
Type RM Length L Ch R = 1 ,49477   ,224,268,297
BEGIN DESCRIPTION:
Fill in Current effective removed for XS 48783 - 49945. There is no longer a building proposed.
XS present in current effective.
END DESCRIPTION:
XS GIS Cut Line= 3
  2429759.458107 6976584.6705212  2429702.395558 6976059.7522797
 2428965.2392239 6969278.6460913
#Sta/Elev= 30
       0  444.88   477.9   449.1  527.69  441.29  610.17   432.7   731.1  441.64
  911.56  435.93 1069.85  441.56 1105.07   438.5 1465.73  438.86 1583.37  446.11
 2078.27  446.92 2177.35  435.75 2383.13   440.8 2572.64  436.66 3012.44   437.5
 3093.81  442.11 3529.77  436.05 3662.61  441.69 3869.88  436.02 4024.67  443.47
 4094.16   436.1 5086.83   435.8 5163.34  439.53 5308.74  436.04 5343.96  440.72
 5426.88  436.42 5460.08  440.08 6153.86  441.41 6577.96  436.46 7411.88  441.22
#Mann= 6 ,-1,0
       0      .1       0  527.69    .065       0   731.1     .07       0
 2078.27     .12       0 3093.81    .065       0 4024.67      .1       0
#XS Ineff= 2 ,-1
  511.09    2634     445    5430 7416.07     445
Permanent Ineff=
       T       T
Bank Sta=3093.81,3662.61
XS Rating Curve= 0 ,0
Exp/Cntr=0.3,0.1

Type RM Length L Ch R = 1 ,49037   ,303,289,281
BEGIN DESCRIPTION:
Fill in Current effective removed for XS 48783 - 49945. There is no longer a building proposed.
XS present in current effective.
END DESCRIPTION:
XS GIS Cut Line= 2
  2429803.466878 6976603.8355092 2429377.6553938 6969181.6072434
#Sta/Elev= 30
  423.38     450  513.83     448  557.45     438  594.26     441  617.46     431
  663.88   431.5  680.33     440   715.7     442  770.36  441.25  779.93  436.32
     905     443  998.37     436 1065.41  437.44 1080.84     444 1118.74     445
 1132.58  436.69 1419.58  436.19 1801.52     448 2121.64     449 2302.97  435.25
  3573.9  435.19 3613.25     436  3664.7  446.71  3750.3     446 3770.89     440
 3861.39     436 4886.71     437 7036.48     434 7442.92     442 7481.24  433.99
#Mann= 7 ,-1,0
  423.38      .1       0     905    .065       0 1118.74     .07       0
 2121.64     .12       0  3750.3    .065       0 4886.71    .085       0
 7442.92      .1       0
#XS Ineff= 2 ,-1
  511.09    2100     445  5174.7 7481.24     445
Permanent Ineff=
       T       T
Bank Sta=3770.89,4886.71
XS Rating Curve= 0 ,0
Exp/Cntr=0.3,0.1

Type RM Length L Ch R = 1 ,48783   ,248,248,252
BEGIN DESCRIPTION:
Fill in Current effective removed for XS 48783 - 49945. There is no longer a building proposed.
XS present in current effective.
Cell C excavation from STA 5902 to 6311
END DESCRIPTION:
XS GIS Cut Line= 2
  2429847.298155 6976637.6179219 2429747.5362157  6969145.617486
#Sta/Elev= 30
       0  447.14  485.64  449.09  582.49  438.09  625.16  441.75  643.94  430.49
  688.97  431.41  708.12  440.52  880.53   436.7  907.92  444.98 1001.19  444.11
 1101.48  436.75 1130.36   446.6 1150.98  437.12 1525.12  436.79 1732.77   445.5
 2122.83  450.31 2284.67  434.95 3272.13  434.57 3450.03  448.43 3469.17     441
 4454.62  436.05 4767.66  437.24 5675.35     434 5902.13  442.59 5955.48     436
 7318.63     436 7362.78  448.43 7380.68  441.23  7484.5  445.17 7492.37     438
#Mann= 6 ,-1,0
       0      .1       0  485.64    .065       0  708.12     .07       0
 1732.77     .12       0 3450.03    .065       0 4454.62    .085       0
#XS Ineff= 2 ,-1
  412.21    2100     445 5044.46 7492.37     445
Permanent Ineff=
       T       T
Bank Sta=3469.17,4767.66
XS Rating Curve= 0 ,0
Exp/Cntr=0.3,0.1