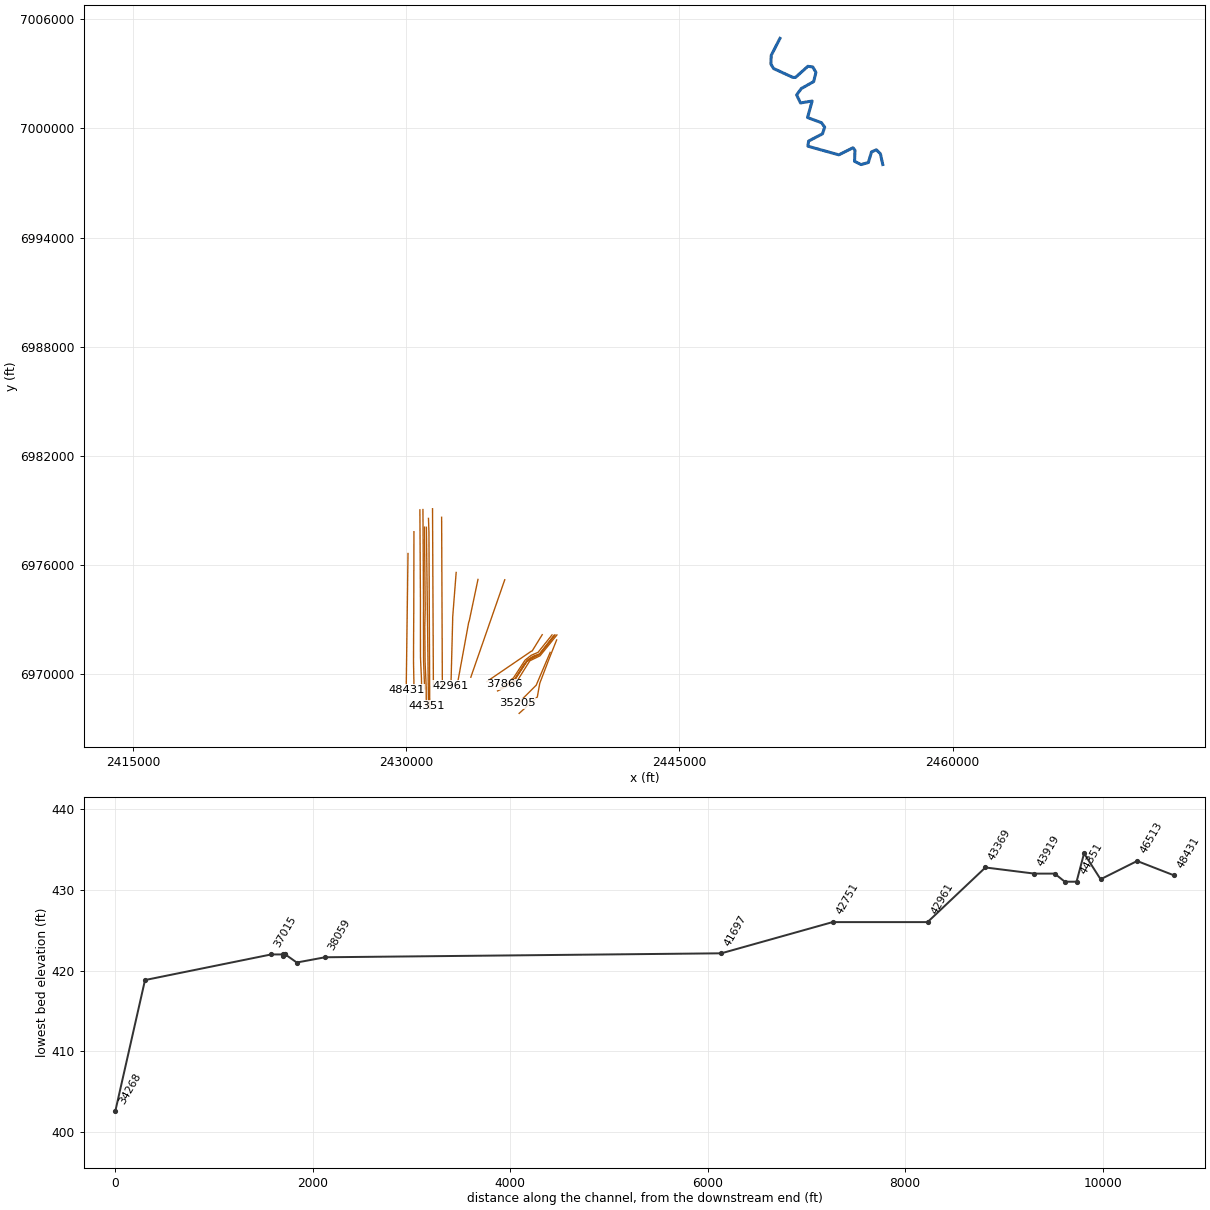
HEC-RAS study CDC_Consolidated_Model.prj: Upper Trinity CDC Consolidated Model

--- CDC_Consolidated_Model.g12 (geometry) --- (continued)

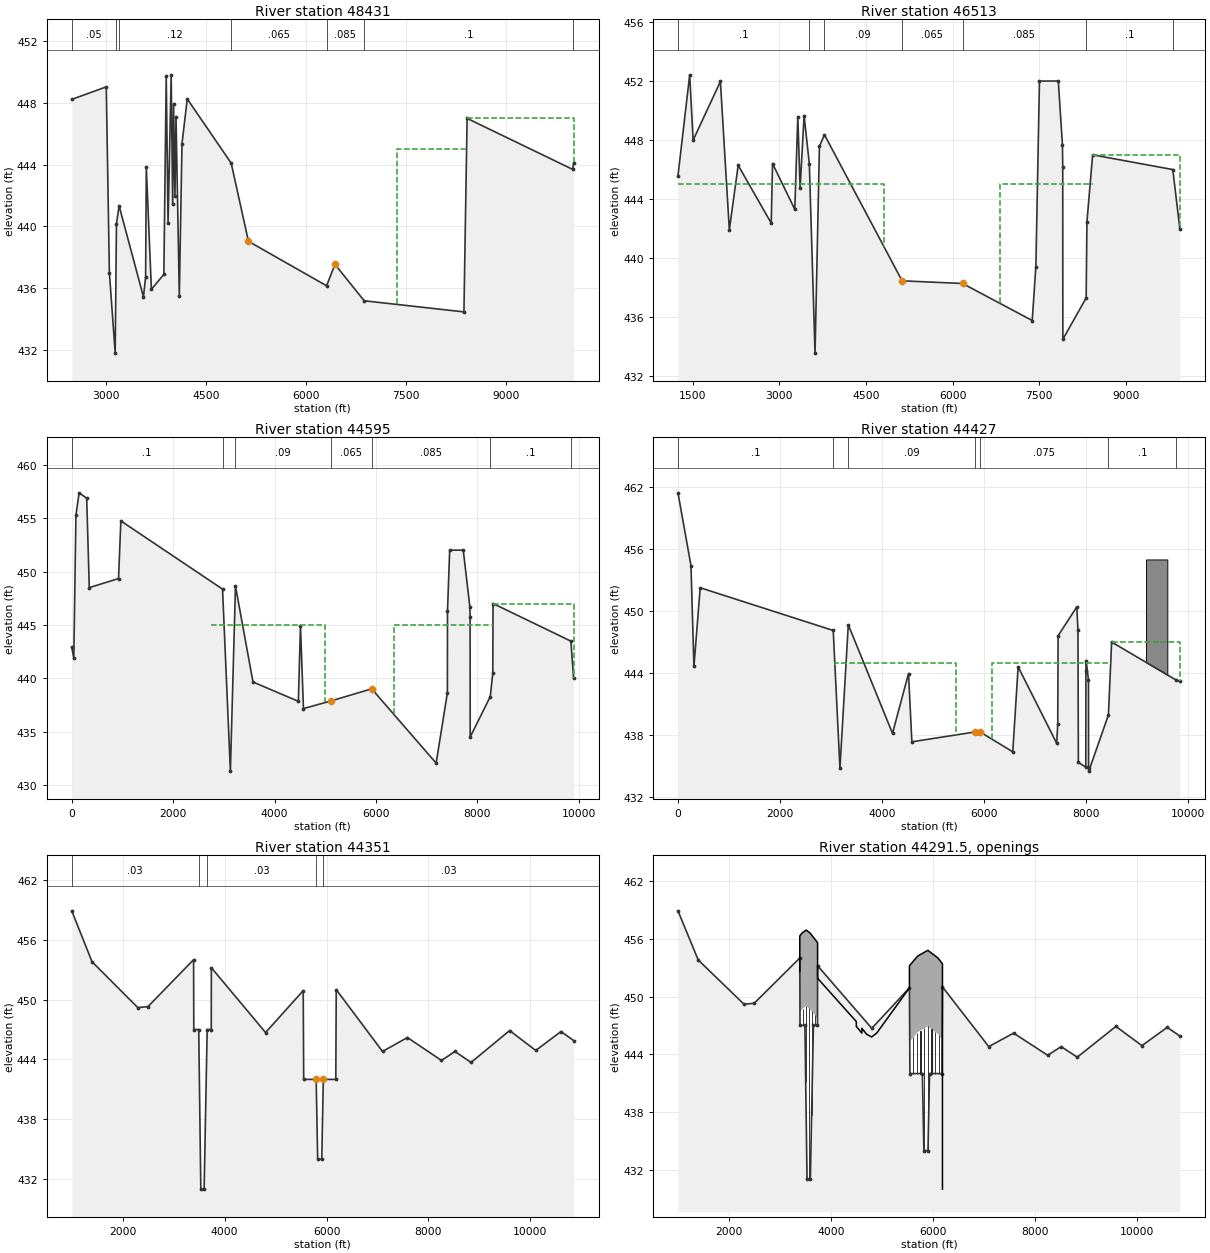
Type RM Length L Ch R = 1 ,48431   ,364.5,370,378.5
BEGIN DESCRIPTION:
XS 44427 - 48431 represent Graff site.
Station 8337 - 9316 represent Graff building 2.
Station 9316 - 9874  represents Graff building 1 from CDC GP 020108
END DESCRIPTION:
XS GIS Cut Line= 2
  2430092.089988 6976641.0900278 2429992.3392038 6969149.9622936
#Sta/Elev= 30
    2490  448.23 3006.64  449.04 3053.64  436.99  3140.5   431.8 3159.35  440.18
 3198.97  441.34 3563.75  435.44 3595.97  436.73 3606.17  443.85 3682.37  435.93
 3869.17   436.9 3904.61  449.72 3932.11  440.24 3978.72  449.82 4001.08  441.44
 4014.74  447.95 4035.13  441.98 4051.26  447.09 4100.64  435.48 4140.54  445.35
 4219.37  448.26  4877.6   444.1 5136.01  439.04 6306.41  436.16 6430.93  437.55
 6868.69  435.19  8362.5  434.47    8410     447 9989.75   443.710004.95   444.1
#Mann= 7 ,-1,0
    2490     .05       0 3159.35     .07       0 3198.97     .12       0
  4877.6    .065       0 6306.41    .085       0 6868.69      .1       0
 9989.75     .08       0
#XS Ineff= 3 ,-1
    2900    4600     445 7360.91    8410     445    841010004.95     447
Permanent Ineff=
       T       T       T
Bank Sta=5136.01,6430.93
XS Rating Curve= 0 ,0
Exp/Cntr=0.3,0.1

Type RM Length L Ch R = 1 ,46513   ,364.5,370,378.5
XS GIS Cut Line= 6
  2430418.026016  6977840.269224 2430408.0765878 6973435.5721033
 2430400.5987082  6972258.601772 2430393.8262717 6970696.1798114
  2430414.562221 6969667.5284091 2430415.2345195 6969167.3856511
#Sta/Elev= 30
    1245  445.58 1448.05  452.42 1507.21  447.99  1979.7  451.97  2134.5  441.91
 2287.56  446.29 2859.95  442.37 2882.29  446.41 3268.08   443.3 3320.06  449.58
  3360.4  444.73 3428.77  449.66 3519.61   446.4 3618.63  433.56 3694.61  447.57
 3781.78  448.36 5126.38  438.46 6173.73  438.28 7379.86  435.77 7443.22  439.43
 7505.22     452 7831.27     452 7903.36  447.69 7908.28  446.18 7910.28   434.5
 8313.94   437.3 8327.67  442.47 8426.17     447 9814.56     446 9936.18  441.99
#Mann= 7 ,-1,0
    1245      .1       0 3519.61    .075       0 3781.78     .09       0
 5126.38    .065       0 6173.73    .085       0 8313.94      .1       0
 9814.56     .08       0
#XS Ineff= 3 ,-1
    1245    4813     445    6815    8425     445    8425 9936.18     447
Permanent Ineff=
       T       T       T
Bank Sta=5126.38,6173.73
XS Rating Curve= 0 ,0
Exp/Cntr=0.3,0.1

Type RM Length L Ch R = 1 ,44595   ,168.22,167.56,170.34
BEGIN DESCRIPTION:
XS 44427 - 48431 represent Graff site.
Station 8267 - 9224 represent Graff building 2.
Station 9224 - 9784 represents Graff building 1 from CDC GP 020108
END DESCRIPTION:
XS GIS Cut Line= 6
  2430743.962044 6979039.4484201  2430774.720185 6974034.3153857
 2430773.3002403 6972696.8931918  2430777.724116 6970921.4741705
 2430831.0330645 6969753.1152867 2430838.1298351 6969184.8090086
#Sta/Elev= 30
       0  442.93   40.19  441.86   82.27  455.29   145.2  457.37  294.47  456.87
  345.67  448.49  922.78  449.34  968.54  454.74 2974.32  448.35 3129.11   431.3
 3229.27  448.64 3575.03  439.65 4470.03  437.84 4511.78  444.94 4570.32  437.16
 5116.75  437.88 5916.52  439.01 7187.93  432.05 7409.74  438.63 7411.74  446.27
 7454.75     452 7722.76     452 7852.77   446.7 7857.77  445.75 7859.77   434.5
 8256.13  438.29 8305.37   440.5    8310     447 9845.21  443.48 9899.54     440
#Mann= 7 ,-1,0
       0      .1       0 2974.32    .075       0 3229.27     .09       0
 5116.75    .065       0 5916.52    .085       0 8256.13      .1       0
 9845.21     .08       0
#XS Ineff= 3 ,-1
 2746.73 5005.23     445    6350    8310     445    8310 9899.54     447
Permanent Ineff=
       T       T       T
#Block Obstruct= 2 , 0
           82.27  455.29
Bank Sta=5116.75,5916.52
XS Rating Curve= 0 ,0
Exp/Cntr=0.3,0.1

Type RM Length L Ch R = 1 ,44427   ,76,76,76
BEGIN DESCRIPTION:
XS 44427 - 48431 represent Graff site.
Station 8278 - 9239 represent Graff building 2.
Station 9239 - 9768 represents Graff building 1 from CDC GP 020108
---------------------------------------------------------------------
CDC GP020108-1 28 Acre Graff Property
Cross-section 44427 - 46329
Located in ROB.
---------------------------------------------------------------------
CDC GP 062623-1 Hopewell Belt Line
END DESCRIPTION:
XS GIS Cut Line= 6
  2430911.496486 6979056.8096058 2430942.2546268 6974051.6765715
 2430940.8346821 6972714.2543776 2430945.2585578 6970938.8353562
 2430947.0479243 6970717.3810747  2431004.688229 6969202.5068079
#Sta/Elev= 30
       0  461.45     255  454.39  312.79  444.64  435.51  452.26 3043.06  448.12
 3174.56  434.79 3338.56  448.67 4205.09  438.16 4519.07  443.95 4584.57  437.34
 5831.08   438.3 5927.27  438.28 6562.21  436.37 6667.58   444.6 7423.18   437.2
 7444.05  439.06  7450.5  447.61 7817.64   450.4 7840.26  448.15 7848.51  435.34
 7993.76  434.89 7995.87  444.23 8001.02  445.21 8046.23  443.31 8048.28  434.83
 8052.24   434.5 8437.38  439.94    8500     447 9768.74  443.31    9837   443.2
#Mann= 7 ,-1,0
       0      .1       0 3043.06    .075       0 3338.56     .09       0
 5831.08    .065       0 5927.27    .075       0 8437.38      .1       0
 9768.74    .075       0
#XS Ineff= 3 ,-1
    3076    5458     445    6158    8500     445    8500    9837     447
Permanent Ineff=
       T       T       T
#Block Obstruct= 1 ,-1
    9175    9592     455
Bank Sta=5831.08,5927.27
XS Rating Curve= 0 ,0
Exp/Cntr=0.5,0.3

Type RM Length L Ch R = 1 ,44351   ,119,119,119
BEGIN DESCRIPTION:
44351
Upstream bounding cross-section of Belt Line Road.
END DESCRIPTION:
XS GIS Cut Line= 6
     2430994.359       6978091.6     2431036.276     6973632.682
     2431013.964     6972628.273     2431028.681     6970697.017
     2431092.855     6969261.942  2431094.302027  6968257.439217
#Sta/Elev= 30
    1000   458.9    1397   453.8    2296   449.2    2496   449.3    3391     454
  3395.2     447    3492     447    3533     431    3598     431    3658     447
  3737.9     447    3740   453.2    4804   446.7    5543   450.9  5552.3     442
    5797     442    5827     434    5907     434    5937     442  6182.3     442
    6191     451    7100   444.8    7587   446.2    8257   443.9    8521   444.8
    8837   443.7    9595   446.9   10107   444.9   10602   446.8   10850   445.9
#Mann= 5 ,-1,0
    1000     .03       0    3492     .05       0    3658     .03       0
    5797     .05       0    5937     .03       0
#XS Ineff= 2 , 0
            3658     447
Permanent Ineff=
       T       F
Bank Sta=5797,5937
XS Rating Curve= 0 ,0
Exp/Cntr=0.5,0.3

Type RM Length L Ch R = 4 ,44291.5 ,,,
BEGIN DESCRIPTION:
Belt Line Road
-------------------------------------------------------
CDC IRV120304-1 Belt Line Road from IH30 to Rock Island
-------------------------------------------------------
END DESCRIPTION:
Node Name=Belt Line Road
Bridge Culvert--1,0,-1,-1, 0
Deck Dist Width WeirC Skew NumUp NumDn MinLoCord MaxHiCord MaxSubmerge Is_Ogee
1,117,2.6,0, 21, 21, , , 0.95, 0, 0,0,,
    3391    3391    3438    3515    3592    3740    3740    4500    4500    4610
    4610    4700    4800    4900    5543    5543    5704    5904    6104    6191
    6191
   452.6   456.3   456.6   456.9   456.6   455.6   451.9   447.4   446.9   446.2
   446.7   446.1   445.8   446.2   450.9   453.2   454.2   454.8     454   453.4
     430
   452.6   448.4   448.7     449   448.7   447.7   451.9   447.4   446.9   446.2
   446.7   446.1   445.8   446.2   450.9   445.3   446.3   446.9   446.1   445.5
     430
    3391    3391    3438    3515    3592    3740    3740    4500    4500    4610
    4610    4700    4800    4900    5543    5543    5704    5904    6104    6191
    6191
   452.6   456.3   456.6   456.9   456.6   455.6   451.9   447.4   446.9   446.2
   446.7   446.1   445.8   446.2   450.9   453.2   454.2   454.8     454   453.4
     430
   452.6   448.4   448.7     449   448.7   447.7   451.9   447.4   446.9   446.2
   446.7   446.1   445.8   446.2   450.9   445.3   446.3   446.9   446.1   445.5
     430
Pier Skew, UpSta & Num, DnSta & Num=  ,3449, 2 ,3449, 2 , 0 , 0 , 0 ,,
     2.5     2.5
     430     450
     2.5     2.5
     430     450
Pier Skew, UpSta & Num, DnSta & Num=  ,3507, 2 ,3507, 2 , 0 , 0 , 0 ,,
     2.5     2.5
     430     450
     2.5     2.5
     430     450
Pier Skew, UpSta & Num, DnSta & Num=  ,3565, 2 ,3565, 2 , 0 , 0 , 0 ,,
     2.5     2.5
     430     450
     2.5     2.5
     430     450
Pier Skew, UpSta & Num, DnSta & Num=  ,3623, 2 ,3623, 2 , 0 , 0 , 0 ,,
     2.5     2.5
     430     450
     2.5     2.5
     430     450
Pier Skew, UpSta & Num, DnSta & Num=  ,3681, 2 ,3681, 2 , 0 , 0 , 0 ,,
     2.5     2.5
     430     450
     2.5     2.5
     430     450
Pier Skew, UpSta & Num, DnSta & Num=  ,5615, 2 ,5615, 2 , 0 , 0 , 0 ,,
     2.5     2.5
     430     450
     2.5     2.5
     430     450
Pier Skew, UpSta & Num, DnSta & Num=  ,5687, 2 ,5687, 2 , 0 , 0 , 0 ,,
     2.5     2.5
     430     450
     2.5     2.5
     430     450
Pier Skew, UpSta & Num, DnSta & Num=  ,5759, 2 ,5759, 2 , 0 , 0 , 0 ,,
     2.5     2.5
     430     450
     2.5     2.5
     430     450
Pier Skew, UpSta & Num, DnSta & Num=  ,5831, 2 ,5831, 2 , 0 , 0 , 0 ,,
     2.5     2.5
     430     450
     2.5     2.5
     430     450
Pier Skew, UpSta & Num, DnSta & Num=  ,5903, 2 ,5903, 2 , 0 , 0 , 0 ,,
     2.5     2.5
     430     450
     2.5     2.5
     430     450
Pier Skew, UpSta & Num, DnSta & Num=  ,5975, 2 ,5975, 2 , 0 , 0 , 0 ,,
     2.5     2.5
     430     450
     2.5     2.5
     430     450
Pier Skew, UpSta & Num, DnSta & Num=  ,6047, 2 ,6047, 2 , 0 , 0 , 0 ,,
     2.5     2.5
     430     450
     2.5     2.5
     430     450
Pier Skew, UpSta & Num, DnSta & Num=  ,6119, 2 ,6119, 2 , 0 , 0 , 0 ,,
     2.5     2.5
     430     450
     2.5     2.5
     430     450
BR Coef= 1 , 1 , 1 ,0.9, 0 ,,,0.8,-1,1.2,0,
WSPro=,,,, 1 ,,,, 0 ,,,, 0 ,,,,-1 ,-1 ,-1 , 0 , 0 , 0 , 0 , 0
BC Mult= 1 ,1000,5543,1000,5543
BC Mult= 3 ,5543,6191,5543,6191
BC Mult= 1 ,6191,10850,6191,10850
BC Design=,, 0 ,, 0 ,,,,,,
BC Use User HTab Curves=0
BC User HTab FreeFlow(D)= 0

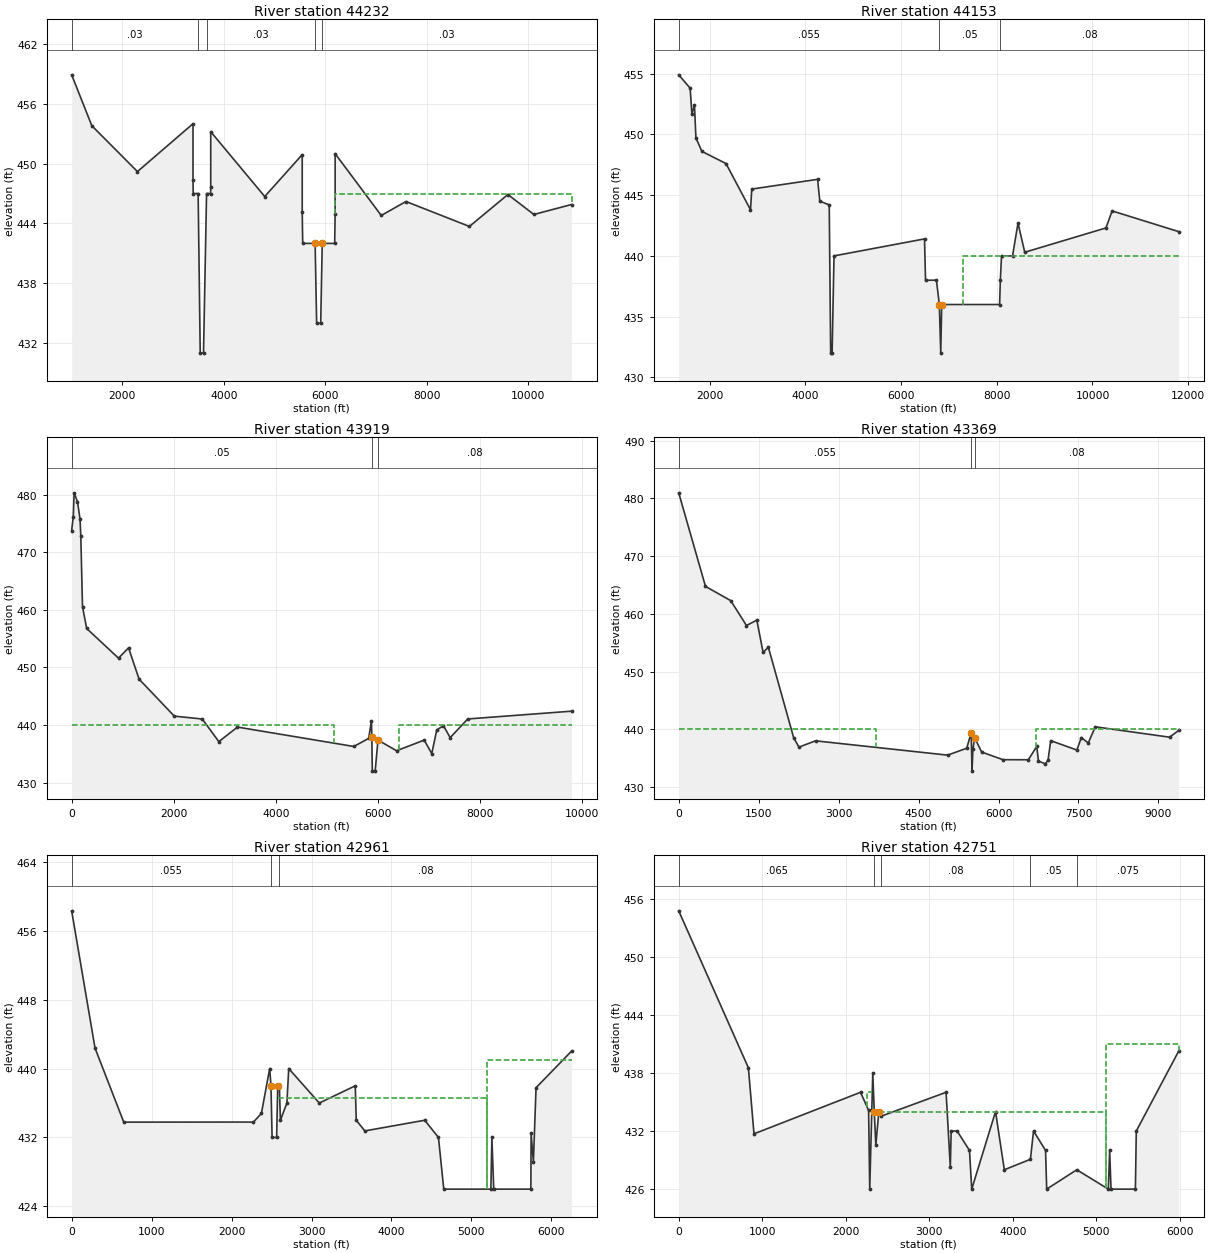
Type RM Length L Ch R = 1 ,44232   ,90,103,114
BEGIN DESCRIPTION:
This cross section corresponds to cross section 44232 of the non-georeferenced CDC model which was the source of this model.
Downstream bounding cross-section of Belt Line Road.
END DESCRIPTION:
XS GIS Cut Line= 2
      2431101.38     6978082.644     2431217.424     6968233.328
#Sta/Elev= 30
    1000   458.9    1397   453.8    2296   449.2    3391     454    3391   448.4
  3395.2     447    3492     447    3533     431    3598     431    3658     447
  3737.9     447    3740   447.7    3740   453.2    4804   446.7    5543   450.9
    5543   445.1  5552.3     442    5797     442    5827     434    5907     434
    5937     442  6182.3     442    6191   444.9    6191     451    7100   444.8
    7587   446.2    8837   443.7    9595   446.9   10107   444.9   10850   445.9
#Mann= 5 ,-1,0
    1000     .03       0    3492     .05       0    3658     .03       0
    5797     .05       0    5937     .03       0
#XS Ineff= 2 , 0
            3658     447    6191             447
Permanent Ineff=
       F       F
Bank Sta=5797,5937
XS Rating Curve= 0 ,0
Exp/Cntr=0.5,0.3

Type RM Length L Ch R = 1 ,44153   ,206,205,205
BEGIN DESCRIPTION:
This cross section corresponds to cross section 44153 of the non-georeferenced CDC model which was the source of this model.
END DESCRIPTION:
XS GIS Cut Line= 4
     2431215.444     6978573.018     2431242.016     6977795.042
     2431273.728     6970715.288     2431285.315     6968128.569
#Sta/Elev= 30
    1355   454.9    1594   453.8    1630   451.7    1684   452.4    1715   449.7
    1840   448.6    2343   447.6    2855   443.8    2882   445.5    4257   446.3
    4303   444.5    4500   444.2    4530     432    4560     432    4600     440
    6491   441.4    6512     438    6740     438    6800     436    6830     432
    6850     436    8060     436    8075     438    8100     440    8330     440
    8444   442.7    8585   440.3   10281   442.3   10411   443.7   11800     442
#Mann= 3 ,-1,0
    1355    .055       0    6800     .05       0    8075     .08       0
#XS Ineff= 2 , 0
            4600     440    7290             440
Permanent Ineff=
       F       F
Bank Sta=6800,6850
XS Rating Curve= 0 ,0
Exp/Cntr=0.3,0.1

Type RM Length L Ch R = 1 ,43919   ,496,496,497
BEGIN DESCRIPTION:
This cross section corresponds to cross section 43919 of the non-georeferenced CDC model which was the source of this model.
END DESCRIPTION:
XS GIS Cut Line= 3
  2431438.531489 6979101.5959484     2431446.466     6977468.662
     2431486.106     6969310.692
#Sta/Elev= 30
       0  473.77   31.81  476.19   48.31  480.33  113.83  478.78  163.34  475.82
  179.34  472.79  212.35  460.54  294.36  456.77  917.49  451.62 1114.53  453.41
 1319.92  447.98 2010.43  441.55 2557.83  441.05 2882.83  437.12 3246.98  439.65
 5526.85  436.28 5816.86  437.69 5871.39  440.76    5879     438    5888     432
    5944     432 5999.58  437.39 6363.42  435.54 6904.43  437.39 7052.44  435.04
 7150.44  439.14 7281.95  439.89 7412.95  437.82 7757.46  441.06 9791.02  442.41
#Mann= 3 ,0,0
       0     .05       0    5879     .05       0 5999.58     .08       0
#XS Ineff= 2 , 0
            5141     440    6410             440
Permanent Ineff=
       F       F
Bank Sta=5879,5999.58
XS Rating Curve= 0 ,0
Exp/Cntr=0.3,0.1

Type RM Length L Ch R = 1 ,43369   ,586,586,586
BEGIN DESCRIPTION:
This cross section corresponds to cross section 43369 of the non-georeferenced CDC model which was the source of this model.
END DESCRIPTION:
XS GIS Cut Line= 3
     2431938.005     6978634.086     2431977.645     6969389.972
 2431978.2203385 6969255.8021068
#Sta/Elev= 30
       0  480.98  502.22  464.77  976.01   462.3 1271.51  457.99 1465.36  458.92
 1583.02  453.33 1681.52  454.23 2157.02  438.54 2255.52  436.92 2567.03  438.01
 5045.22  435.53 5404.05  436.73 5486.05  439.43 5502.55  432.76 5519.05  436.56
 5551.55  438.55 5683.05  436.07 6082.74  434.74 6560.29  434.73 6716.06  437.04
 6749.06  434.51 6880.06  434.01 6929.56  434.72 6978.56  438.04 7470.57  436.41
 7552.57  438.58 7683.57  437.64 7815.07  440.44 9209.08  438.64 9378.37  439.81
#Mann= 3 ,-1,0
       0    .055       0 5486.05     .05       0 5551.55     .08       0
#XS Ineff= 2 , 0
            3700     440    6700             440
Permanent Ineff=
       F       F
Bank Sta=5486.05,5551.55
XS Rating Curve= 0 ,0
Exp/Cntr=0.3,0.1

Type RM Length L Ch R = 1 ,42961   ,962,962,962
BEGIN DESCRIPTION:
This cross section corresponds to cross section 42961 of the non-georeferenced CDC model which was the source of this model.
END DESCRIPTION:
XS GIS Cut Line= 6
   2432736.51784 6975600.7725042  2432709.046948 6975248.0427537
 2432544.5996566 6973136.5186515 2432544.3968499 6973069.1809124
 2432544.1940682 6973001.8435618      2432449.69      6969356.86
#Sta/Elev= 30
       0  458.32  292.11  442.38  651.49  433.78 2273.96  433.79 2373.15  434.79
 2476.65     440 2492.86     438 2493.22  437.83 2506.86     432 2563.56     432
 2577.46     438 2597.63     438 2610.92     434  2691.9     436 2715.02     440
 3097.27     436 3547.19     438 3559.42     434 3666.42  432.76 4415.79     434
 4587.63     432 4653.95     426 5243.23     426 5255.71     432 5278.95     426
 5743.17     426 5746.48  432.47 5774.92  429.14 5808.16  437.78  6252.6  442.03
#Mann= 3 ,-1,0
       0    .055       0 2493.22     .05       0 2597.63     .08       0
#XS Ineff= 3 ,-1
       0 2492.86  436.55 2577.46    5200  436.55    5200  6252.6     441
Permanent Ineff=
       F       F       T
Bank Sta=2492.86,2577.46
XS Rating Curve= 0 ,0
Exp/Cntr=0.3,0.1

Type RM Length L Ch R = 1 ,42751   ,1127,1127,1127
BEGIN DESCRIPTION:
This cross section corresponds to cross section 42751 of the non-georeferenced CDC model which was the source of this model.
END DESCRIPTION:
XS GIS Cut Line= 6
  2433934.769512 6975217.1339607  2433838.578477 6974760.6145949
 2433455.9546781 6972944.6951202 2433439.7403547 6972899.8482442
 2433423.5261743 6972855.0017698      2432781.89      6969344.55
#Sta/Elev= 30
       0  454.74  834.39  438.53  901.57  431.71 2177.29     436 2273.93  434.13
 2287.45     426 2323.98     438 2341.81     434 2360.39  430.53 2396.43     434
 2421.07  433.52 3201.68     436 3252.41  428.27 3262.69     432 3333.79     432
 3481.86     430 3508.86     426 3793.85     434 3899.09     428 4211.51  429.08
 4249.03     432 4392.77     430 4406.55     426 4766.46     428 5144.56     426
 5160.45     430 5176.79     426 5468.73     426 5479.32     432 5986.32  440.24
#Mann= 5 ,-1,0
       0    .065       0 2341.81     .05       0 2421.07     .08       0
 4211.51     .05       0 4766.46    .075       0
#XS Ineff= 4 ,-1
       0 2258.31     434 2258.31 2318.75     436 2396.43    5120     434
    5120 5986.32     441
Permanent Ineff=
       F       T       F       T
Bank Sta=2341.81,2396.43
XS Rating Curve= 0 ,0
Exp/Cntr=0.3,0.1

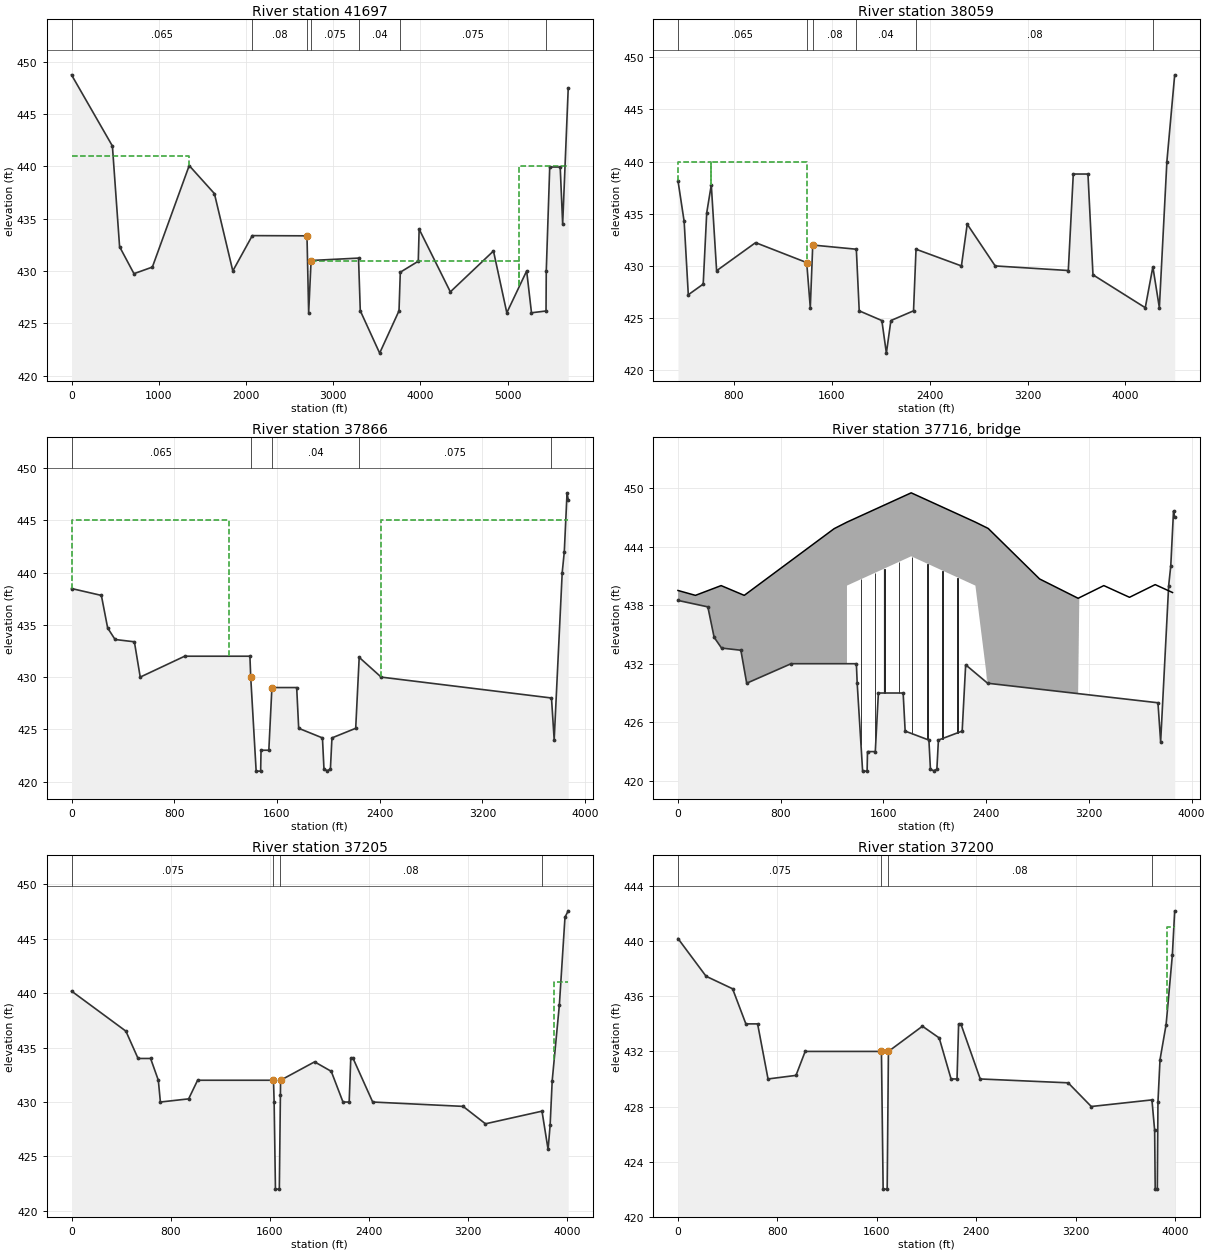
Type RM Length L Ch R = 1 ,41697   ,4013,4013,4013
BEGIN DESCRIPTION:
This cross section corresponds to cross section 41697 of the non-georeferenced CDC model which was the source of this model.
END DESCRIPTION:
XS GIS Cut Line= 2
       2435404.4      6975198.83 2433541.6216335 6969844.3813059
#Sta/Elev= 30
       0  448.76     469  441.95  551.35  432.32  716.11  429.74  927.09  430.37
  1349.4  440.08 1638.44   437.4 1849.46     430 2072.76  433.38 2699.91  433.36
    2719     426    2747     431 3290.84  431.23    3311  426.19    3533  422.14
    3755  426.19 3769.76  429.88 3975.81  430.93 3985.76     434 4343.53     428
 4837.96  431.91 4990.93     426 5218.54     430  5273.8     426 5440.53  426.17
 5443.24     430    5483  439.94    5603  439.94 5631.28  434.48 5695.09   447.5
#Mann= 7 ,-1,0
       0    .065       0 2072.76     .08       0 2699.91     .05       0
    2747    .075       0 3290.84     .04       0 3769.76    .075       0
 5443.24    .035       0
#XS Ineff= 4 ,-1
       0  1349.4     441  1349.4 2699.91  433.36    2747    5135     431
    5135 5695.09     440
Permanent Ineff=
       F       F       F       T
Bank Sta=2699.91,2747
XS Rating Curve= 0 ,0
Exp/Cntr=0.3,0.1

Type RM Length L Ch R = 1 ,38059   ,287,287,287
BEGIN DESCRIPTION:
This cross section corresponds to cross section 38059 of the non-georeferenced CDC model which was the source of this model.
END DESCRIPTION:
XS GIS Cut Line= 6
     2437462.207     6972180.118      2436909.76     6971284.273
     2436886.013     6971277.738     2436862.266     6971271.202
     2434837.975     6969889.821 2434418.0830975 6969603.2857656
#Sta/Elev= 30
  342.25  438.17  392.79  434.26  426.76  427.24   548.6  428.26  577.25  435.08
  614.67  437.76  658.13  429.54  976.75  432.23 1394.74  430.32    1424     426
    1444     432  1800.4   431.6    1824   425.7    2009  424.77    2046  421.65
    2083  424.77    2268   425.7  2288.4   431.6 2659.54     430 2706.86     434
 2935.56     430 3533.25  429.56    3574   438.8    3694   438.8 3734.96  429.15
 4162.51     426 4224.56  429.91 4277.66     426 4339.22     440 4403.05   448.3
#Mann= 6 ,-1,0
  342.25    .065       0 1394.74     .05       0    1444     .08       0
  1800.4     .04       0  2288.4     .08       0 4224.56    .035       0
#XS Ineff= 4 ,-1
  342.25  614.67     440  614.67 1394.74     440    1444    3574     432
    3574 4403.05   438.8
Permanent Ineff=
       T       F       F       F
Bank Sta=1394.74,1444
XS Rating Curve= 0 ,0
Exp/Cntr=0.5,0.3

Type RM Length L Ch R = 1 ,37866   ,116,116,116
BEGIN DESCRIPTION:
This cross section corresponds to cross section 37866 of the non-georeferenced CDC model which was the source of this model.
END DESCRIPTION:
XS GIS Cut Line= 6
2438001.955963576972170.09145247     2437235.092     6971210.511
     2436857.991     6971047.683     2436524.658     6970786.572
     2435878.043     6969798.638      2435379.71      6969447.85
#Sta/Elev= 30
       0  438.48  232.59  437.82  281.59   434.7  339.36   433.6   489.7  433.38
  535.16     430  881.16     432 1389.31     432  1395.6     430 1437.89     421
 1472.89     421 1475.89     423  1536.6     423  1560.6     429  1753.5     429
  1769.1   425.1  1954.1  424.18  1966.1  421.18  1991.1  421.05  2016.1  421.18
  2028.1  424.18  2213.1   425.1 2240.28  431.89 2411.33     430 3737.69     428
 3758.65     424 3821.13     440 3837.42     442 3858.86  447.64 3868.05  446.99
#Mann= 5 ,-1,0
       0    .065       0  1395.6     .05       0  1560.6     .04       0
 2240.28    .075       0 3737.69    .035       0
#XS Ineff= 2 , 0
            1224     445    2408             445
Permanent Ineff=
       F       F
Bank Sta=1395.6,1560.6
XS Rating Curve= 0 ,0
Exp/Cntr=0.5,0.3

Type RM Length L Ch R = 3 ,37716   ,,,
BEGIN DESCRIPTION:
Hunter-Ferrell Road
END DESCRIPTION:
Node Name=Hunter-Ferrell R
Bridge Culvert--1,0,-1,-1, 0
Deck Dist Width WeirC Skew NumUp NumDn MinLoCord MaxHiCord MaxSubmerge Is_Ogee
0.5,115,2.6,0, 17, 17, , , 0.95, 0, 0,0,,
       0     136     336   516.1  1216.1  1316.1  1316.1  1816.1  2316.1  2316.1
  2416.1  2816.1  3116.1  3316.1  3516.1  3716.1  3851.1
   439.5     439     440     439  445.83   446.5   446.5   449.5   446.5   446.5
  445.85  440.68   438.7     440   438.8   440.1  439.29
                                                     440     443     440
       0     136     336  642.15 1342.15 1442.15 1442.15 1942.15 2442.15 2442.15
 2542.15 2942.15 3242.15 3442.15 3642.15 3842.15 3977.15
   439.5     439     440     439  445.83   446.5   446.5   449.5   446.5   446.5
  445.85  440.68   438.7     440   438.8   440.1  439.29
                                                     440     443     440
Pier Skew, UpSta & Num, DnSta & Num=  ,1425.1, 2 ,1529.5, 2 , 0 , 0 , 0 ,,
       3       3
     415     443
       3       3
     415     443
Pier Skew, UpSta & Num, DnSta & Num=  ,1535.1, 2 ,1639.5, 2 , 0 , 0 , 0 ,,
       3       3
     415     443
       3       3
     415     443
Pier Skew, UpSta & Num, DnSta & Num=  ,1607.26, 2 ,1711.66, 2 , 0 , 0 , 0 ,,
       3       3
     415     443
       3       3
     415     443
Pier Skew, UpSta & Num, DnSta & Num=  ,1721.26, 2 ,1825.66, 2 , 0 , 0 , 0 ,,
       3       3
     415     443
       3       3
     415     443
Pier Skew, UpSta & Num, DnSta & Num=  ,1824, 2 ,1928.4, 2 , 0 , 0 , 0 ,,
       3       3
     415     443
       3       3
     415     443
Pier Skew, UpSta & Num, DnSta & Num=  ,1942, 2 ,2046.4, 2 , 0 , 0 , 0 ,,
       3       3
     415     443
       3       3
     415     443
Pier Skew, UpSta & Num, DnSta & Num=  ,2060, 2 ,2164.4, 2 , 0 , 0 , 0 ,,
       3       3
     415     443
       3       3
     415     443
Pier Skew, UpSta & Num, DnSta & Num=  ,2178, 2 ,2282.4, 2 , 0 , 0 , 0 ,,
       3       3
     415     443
       3       3
     415     443
Abutment Skew #Up #Dn= , 2 , 2
  1316.1  1396.1
     440     420
 1442.15 1522.15
     440     420
Abutment Skew #Up #Dn= , 2 , 2
    2236  2316.1
     420     440
 2362.15 2442.15
     420     440
BR Coef=-1 , 0 , 0 ,, 0 ,,,0.8,0,1.2,0,
WSPro=,,,, 1 ,,,, 0 ,,,, 0 ,,,,-1 ,-1 ,-1 , 0 , 0 , 0 , 0 , 0
BC Design=,, 0 ,, 0 ,,,,,,
BC Use User HTab Curves=0
BC User HTab FreeFlow(D)= 0

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
Type RM Length L Ch R = 1 ,37205   ,5,5,5
BEGIN DESCRIPTION:
This cross section corresponds to cross section 37205 of the non-georeferenced CDC model which was the source of this model.
END DESCRIPTION:
XS GIS Cut Line= 6
     2438129.305      6972158.44     2437314.462     6971118.336
     2436964.201       6970996.2     2436653.066     6970780.107
     2435961.396     6969746.143 2435412.1959663 6969342.6171283
#Sta/Elev= 30
       0  440.19  438.89  436.51  537.09     434  638.33     434  700.65     432
  717.24     430  945.29  430.29 1017.54     432 1629.99     432 1635.15     430
 1645.77     422  1677.1     422 1685.73   430.6 1687.17     432 1961.67  433.69
    2096  432.82 2190.72     430 2240.73     430 2253.48     434 2272.59     434
 2430.49     430 3159.93   429.6 3340.37     428 3796.67  429.16 3845.86  425.64
 3862.42  427.89 3878.98  431.96 3937.04  438.95 3982.21  446.98 4008.36  447.56
#Mann= 4 ,-1,0
       0    .075       0 1629.99     .05       0 1685.73     .08       0
 3796.67    .065       0
#XS Ineff= 3 ,-1
       0 1629.99     432 1687.17    3895     432    3895 4008.36     441
Permanent Ineff=
       F       F       F
Bank Sta=1629.99,1687.17
XS Rating Curve= 0 ,0
Exp/Cntr=0.5,0.3

Type RM Length L Ch R = 1 ,37200   ,16,16,16
BEGIN DESCRIPTION:
This cross section corresponds to cross section 37200 of the non-georeferenced CDC model which was the source of this model.
END DESCRIPTION:
XS GIS Cut Line= 6
     2438112.111     6972134.421     2437316.845     6971115.044
     2436713.219     6970827.393     2436472.594     6970568.279
     2435961.917     6969740.675 2435401.2794095 6969333.1200994
#Sta/Elev= 30
       0   440.2  225.84  437.46  439.17  436.55  546.08     434   640.4     434
  724.22     430  949.05  430.26 1022.92     432 1636.05     432  1649.8     422
 1682.31     422 1692.24     432 1965.76  433.83 2100.51  432.98 2195.98     430
 2243.95     430 2256.66     434 2274.68     434 2430.49     430 3137.48  429.72
 3323.48     428 3811.27  428.48    3833  426.27  3837.5     422  3854.5     422
 3859.65  428.34 3876.16   431.4 3925.18  433.95 3975.37  438.99 3994.22  442.21
#Mann= 4 ,-1,0
       0    .075       0 1636.05     .05       0 1692.24     .08       0
 3811.27    .065       0
#XS Ineff= 3 ,-1
       0 1636.05     432 1692.24    3936     432    3936 3994.22     441
Permanent Ineff=
       F       F       T
Bank Sta=1636.05,1692.24
XS Rating Curve= 0 ,0
Exp/Cntr=0.5,0.3

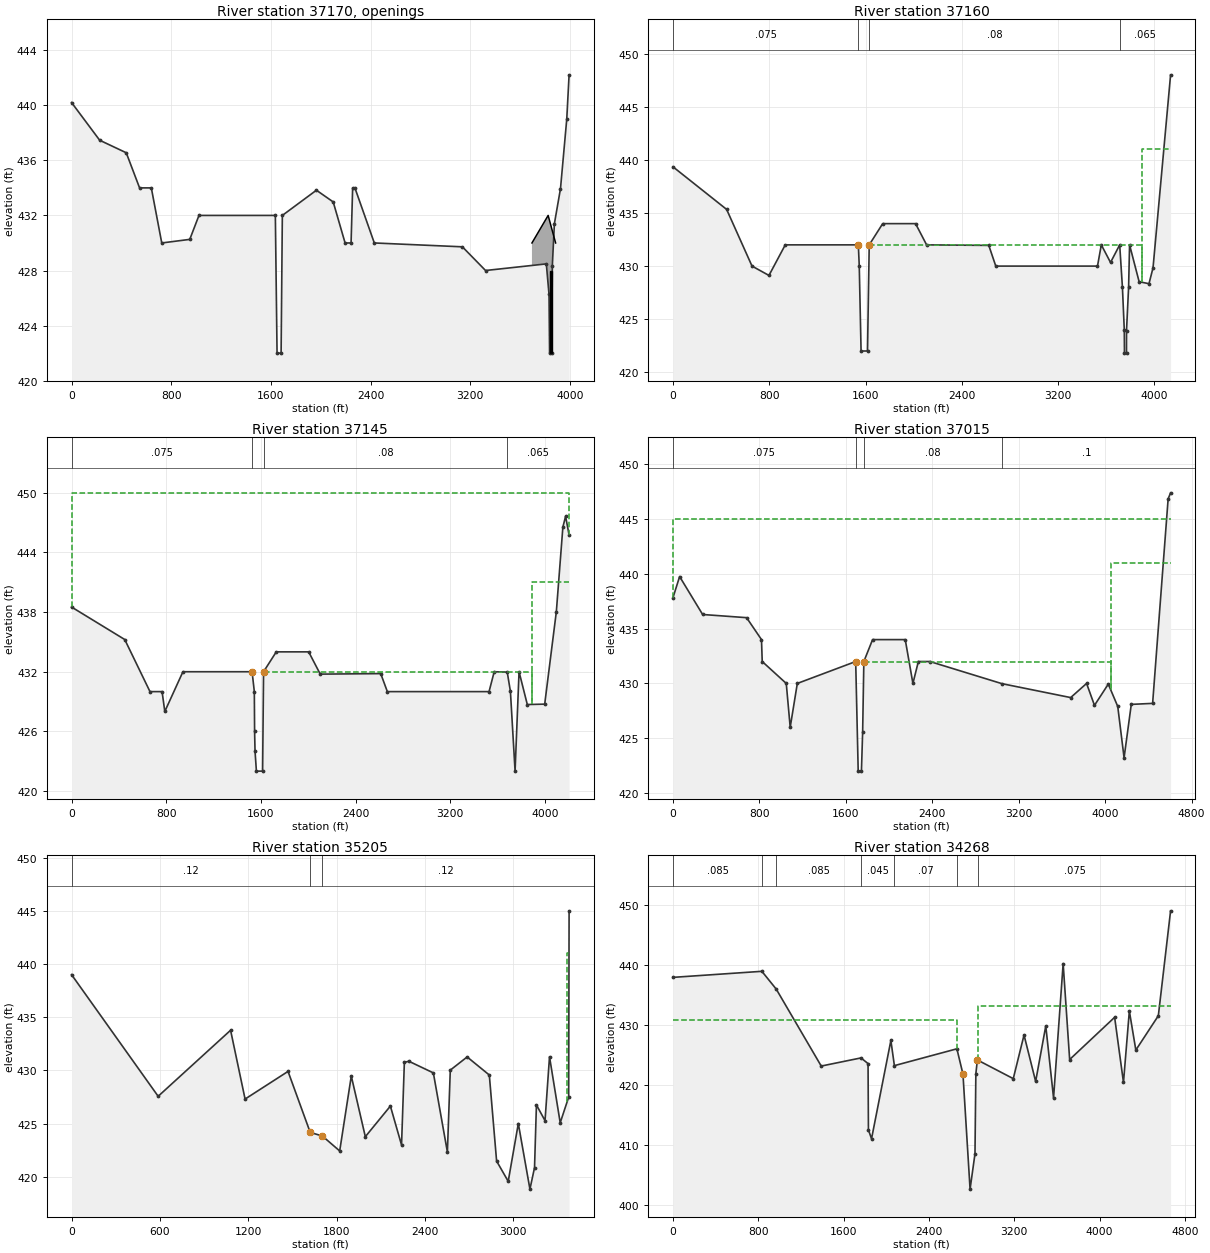
Type RM Length L Ch R = 4 ,37170   ,,,
BEGIN DESCRIPTION:
Lone Star Road
END DESCRIPTION:
Node Name=Lone Star Road
Bridge Culvert--1,0,-1,-1, 0
Deck Dist Width WeirC Skew NumUp NumDn MinLoCord MaxHiCord MaxSubmerge Is_Ogee
0.5,15,2.6,0, 3, 3, , , 0.95, 0, 0,0,,
    3696    3826    3886
     430     432     430
     420     420     420
 3665.42 3759.47 3804.72
     432     432     432
     420     420     420
BR Coef=-1 , 0 , 0 ,, 0 ,,,0.8,-1,,0,
WSPro=,,,, 1 ,,,, 0 ,,,, 0 ,,,,-1 ,-1 ,-1 , 0 , 0 , 0 , 0 , 0
Culvert=2,6,8,15,0.02,0.4,1,8,1,422,3841.5,421.8,3755.5,Culvert #1  , 2 ,0.5
  3841.5  3755.5
BC Culvert Barrel=1,,0
Culvert Bottom n=0.035
Culvert Bottom Depth=4
Culvert=2,6,8,15,0.02,0.4,1,8,1,422,3850.5,421.8,3764.5,Culvert #2  , 2 ,0.5
  3850.5  3764.5
BC Culvert Barrel=1,,0
Culvert Bottom n=0.035
Culvert Bottom Depth=4
BC Mult= 1 ,0,3696,0,3711
BC Mult= 2 ,3696,3867,3711,3800
BC Mult= 1 ,3867,3994.25,3800,4135
BC Design=,, 0 ,, 0 ,,,,,,
BC Use User HTab Curves=0
BC User HTab FreeFlow(D)= 0

Type RM Length L Ch R = 1 ,37160   ,6,5,4
BEGIN DESCRIPTION:
This cross section corresponds to cross section 37160 of the non-georeferenced CDC model which was the source of this model.
END DESCRIPTION:
XS GIS Cut Line= 6
  2438076.356879 6972055.3186637     2437318.921     6971099.418
     2436600.288     6970699.421     2435972.684     6969737.442
      2435586.63     6969419.731     2435192.997      6969255.15
#Sta/Elev= 30
       0  439.35  445.48  435.34  656.39     430  797.16  429.12  932.62     432
 1539.93     432 1547.58     430 1562.68     422 1616.13     422 1630.39     432
 1742.44     434 2015.54     434 2107.22     432 2623.97  431.95  2682.2     430
 3527.41     430 3559.21     432 3635.76  430.34 3711.92     432 3734.66     428
 3750.06     424  3751.5   421.8  3768.5   421.8 3768.61  423.91 3785.91     428
 3794.04     432 3873.32  428.53 3955.38  428.34 3988.95  429.84 4134.93  448.02
#Mann= 4 ,-1,0
       0    .075       0 1539.93     .05       0 1630.39     .08       0
 3711.92    .065       0
#XS Ineff= 3 ,-1
       0 1539.93     432 1630.39    3895     432    3895 4134.93     441
Permanent Ineff=
       F       F       F
Bank Sta=1539.93,1630.39
XS Rating Curve= 0 ,0
Exp/Cntr=0.5,0.3

Type RM Length L Ch R = 1 ,37145   ,128,117,137
BEGIN DESCRIPTION:
This cross section corresponds to cross section 37145 of the non-georeferenced CDC model which was the source of this model.
END DESCRIPTION:
XS GIS Cut Line= 6
     2438172.046     6972160.877     2437322.567     6971094.731
     2436914.872      6970942.65     2436607.511     6970695.619
     2435977.302     6969732.077 2435269.7170945  6969269.416903
#Sta/Elev= 30
       0  438.51  449.68  435.24  662.88     430   765.2     430  788.16     428
  941.38     432 1525.72     432 1544.71     430    1547     426 1550.71     424
  1562.3     422 1614.66     422 1622.87     432  1730.1     434    2004     434
 2101.82  431.76 2612.84  431.81 2668.87     430 3528.38     430 3571.93     432
 3682.11  431.96 3708.94  430.02 3748.32     422  3781.9     432 3851.64   428.7
 3998.67  428.74 4097.05  438.04 4152.26  446.55 4175.27  447.64 4204.86  445.75
#Mann= 4 ,-1,0
       0    .075       0 1525.72     .05       0 1622.87     .08       0
 3682.11    .065       0
#XS Ineff= 4 ,-1
      -1       0     450       0 1525.72     432 1622.87    3892     432
    3892 4204.86     441
Permanent Ineff=
       F       F       F       T
Bank Sta=1525.72,1622.87
XS Rating Curve= 0 ,0
Exp/Cntr=0.3,0.1

Type RM Length L Ch R = 1 ,37015   ,468,1278,431
BEGIN DESCRIPTION:
This cross section corresponds to cross section 37015 of the non-georeferenced CDC model which was the source of this model.
END DESCRIPTION:
XS GIS Cut Line= 6
  2438270.869671  6972166.103442     2437343.318     6971022.182
     2436779.516     6970743.536     2436128.474     6969705.775
     2435401.912     6969279.994     2435009.985     6969088.588
#Sta/Elev= 30
       0  437.84    60.9  439.75  273.92  436.29  680.82     436  818.63     434
  825.41     432 1047.95     430 1084.36     426 1150.21     430  1690.5     432
 1713.73     422 1743.65     422 1754.89  425.58 1766.01     432 1846.89     434
  2149.1     434  2220.1     430 2270.46     432 2377.27     432    3044  429.98
 3680.22  428.71  3827.5     430 3900.53     428 4028.45  429.94 4115.86   427.9
 4174.51  423.22 4241.18  428.09 4438.65  428.18 4582.29  446.84    4605  447.39
#Mann= 4 ,-1,0
       0    .075       0  1690.5     .05       0 1766.01     .08       0
    3044      .1       0
#XS Ineff= 4 ,-1
      -1       0     445       0  1690.5     432 1766.01    4050     432
    4050    4605     441
Permanent Ineff=
       F       F       F       T
Bank Sta=1690.5,1766.01
XS Rating Curve= 0 ,0
Exp/Cntr=0.3,0.1

Type RM Length L Ch R = 1 ,35205   ,129,301,244
BEGIN DESCRIPTION:
This cross section corresponds to cross section 35205 of the non-georeferenced CDC model which was the source of this model.
END DESCRIPTION:
XS GIS Cut Line= 6
  2437898.976521 6971206.3681057      2437870.31      6971139.06
  2437665.112985 6970657.2637635     2437130.719       6969401.1
      2436224.67      6968500.42 2436125.0245927 6968401.3650643
#Sta/Elev= 30
       0     439  588.39  427.56 1080.39  433.77 1178.89   427.3 1470.69   429.9
 1621.39  424.16 1703.39  423.83 1821.58  422.42 1900.39  429.46 1995.72  423.76
 2165.97  426.64 2241.73  422.98 2260.89  430.74 2290.73  430.86 2457.89  429.76
 2553.24  422.32 2572.89  430.02 2687.39  431.26 2838.03  429.56 2887.53  421.47
 2966.39  419.56 3035.02     425 3113.89  418.83 3145.18  420.85 3158.07  426.75
 3216.47  425.27 3246.96  431.28 3319.62  425.07 3377.08  427.48    3380     445
#Mann= 3 ,0,0
       0     .12       0 1621.39    .055       0 1703.39     .12       0
#XS Ineff= 3 ,-1
       0 1621.39  424.16 1703.39    3367  423.83    3367    3380     441
Permanent Ineff=
       F       F       T
Bank Sta=1621.39,1703.39
XS Rating Curve= 0 ,0
Exp/Cntr=0.3,0.1

Type RM Length L Ch R = 1 ,34268   ,0,0,0
BEGIN DESCRIPTION:
This cross section corresponds to cross section 34268 of the non-georeferenced CDC model which was the source of this model.
Ineffective flow between sta 4411 - 4640 due to upstream GPMURD levee.
END DESCRIPTION:
XS GIS Cut Line= 6
2438254.781357796971891.68573763 2438216.9886835 6971797.0167254
      2437842.34     6970858.538     2437328.451     6969511.316
     2437193.035     6968757.844      2436195.15      6967855.86
#Sta/Elev= 30
       0  437.96  832.86  438.97   967.5     436 1389.42  423.15  1762.4  424.51
  1828.4  423.56    1832   412.5    1861     411 2042.39  427.42 2075.38  423.22
 2661.29  426.03 2718.25  421.81    2785   402.6    2831   408.5 2839.17  421.87
 2853.16  424.11 2862.16  424.09 3189.94  421.05 3290.87  428.33  3399.8  420.58
 3494.74  429.85 3567.69  417.82 3657.63  440.26 3718.59  424.24 4140.31  431.29
 4223.26  420.42 4278.23  432.34  4339.2  425.82 4550.08  431.55 4665.01  449.07
#Mann= 7 ,-1,0
       0    .085       0  832.86      .1       0   967.5    .085       0
  1762.4    .045       0 2075.38     .07       0 2661.29    .065       0
 2862.16    .075       0
#XS Ineff= 2 , 0
         2661.29   430.8 2862.16           433.1
Permanent Ineff=
       F       F
Bank Sta=2718.25,2853.16
XS Rating Curve= 0 ,0
Exp/Cntr=0.3,0.1

River Reach=Elm Fork        ,ef2
Reach XY= 30
      2450520.46       7004955.1      2450040.61      7004024.28
      2450018.53      7003545.57      2450168.87       7003295.4
      2451221.41      7002811.55      2451369.25      7002805.75
      2452052.98      7003418.35      2452321.02      7003381.17
      2452494.32      7003085.47      2452369.57      7002578.95
      2451688.22      7002193.92      2451436.24      7001846.74
      2451646.96      7001404.06       2452285.3      7001509.56
      2452034.22      7000601.65      2452798.22      7000318.05
      2452973.76      7000073.06       2452854.9       6999707.6
      2452092.82      6999309.74      2452051.57      6999026.75
      2453751.72      6998551.56      2454526.25      6998940.04
      2454637.52      6998806.28      2454616.17      6998195.55
      2454971.66       6998016.3      2455375.66       6998133.3
      2455546.25      6998715.68      2455813.03      6998828.34
      2456033.98      6998609.09      2456164.29      6998018.92