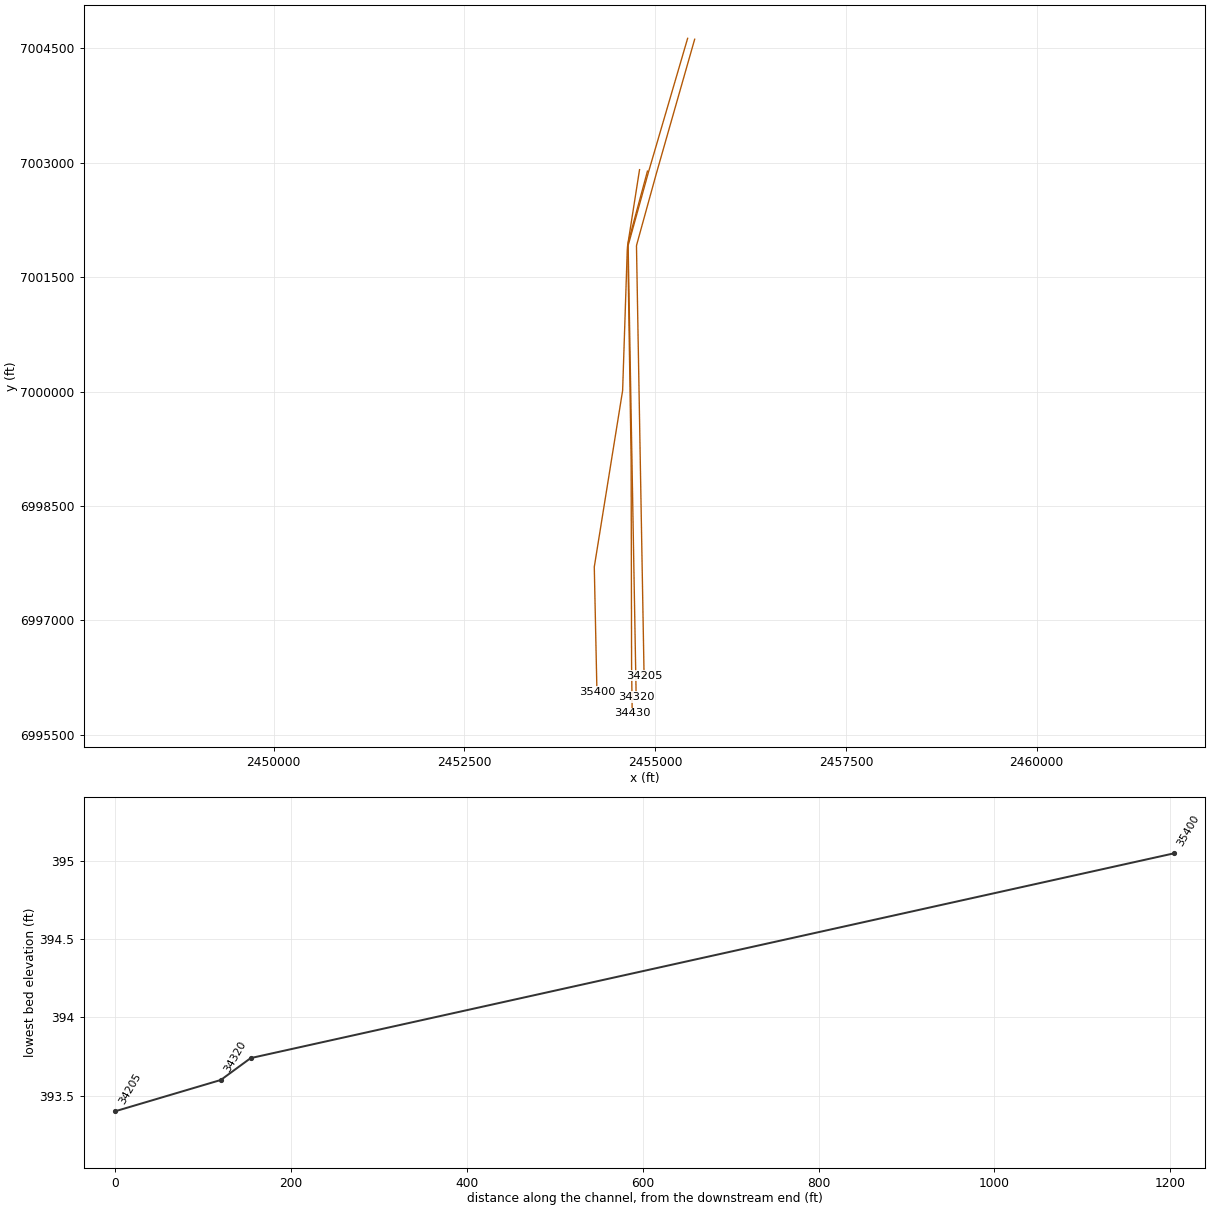
HEC-RAS study CDC_Consolidated_Model.prj: Upper Trinity CDC Consolidated Model

--- CDC_Consolidated_Model.g12 (geometry) --- (continued)

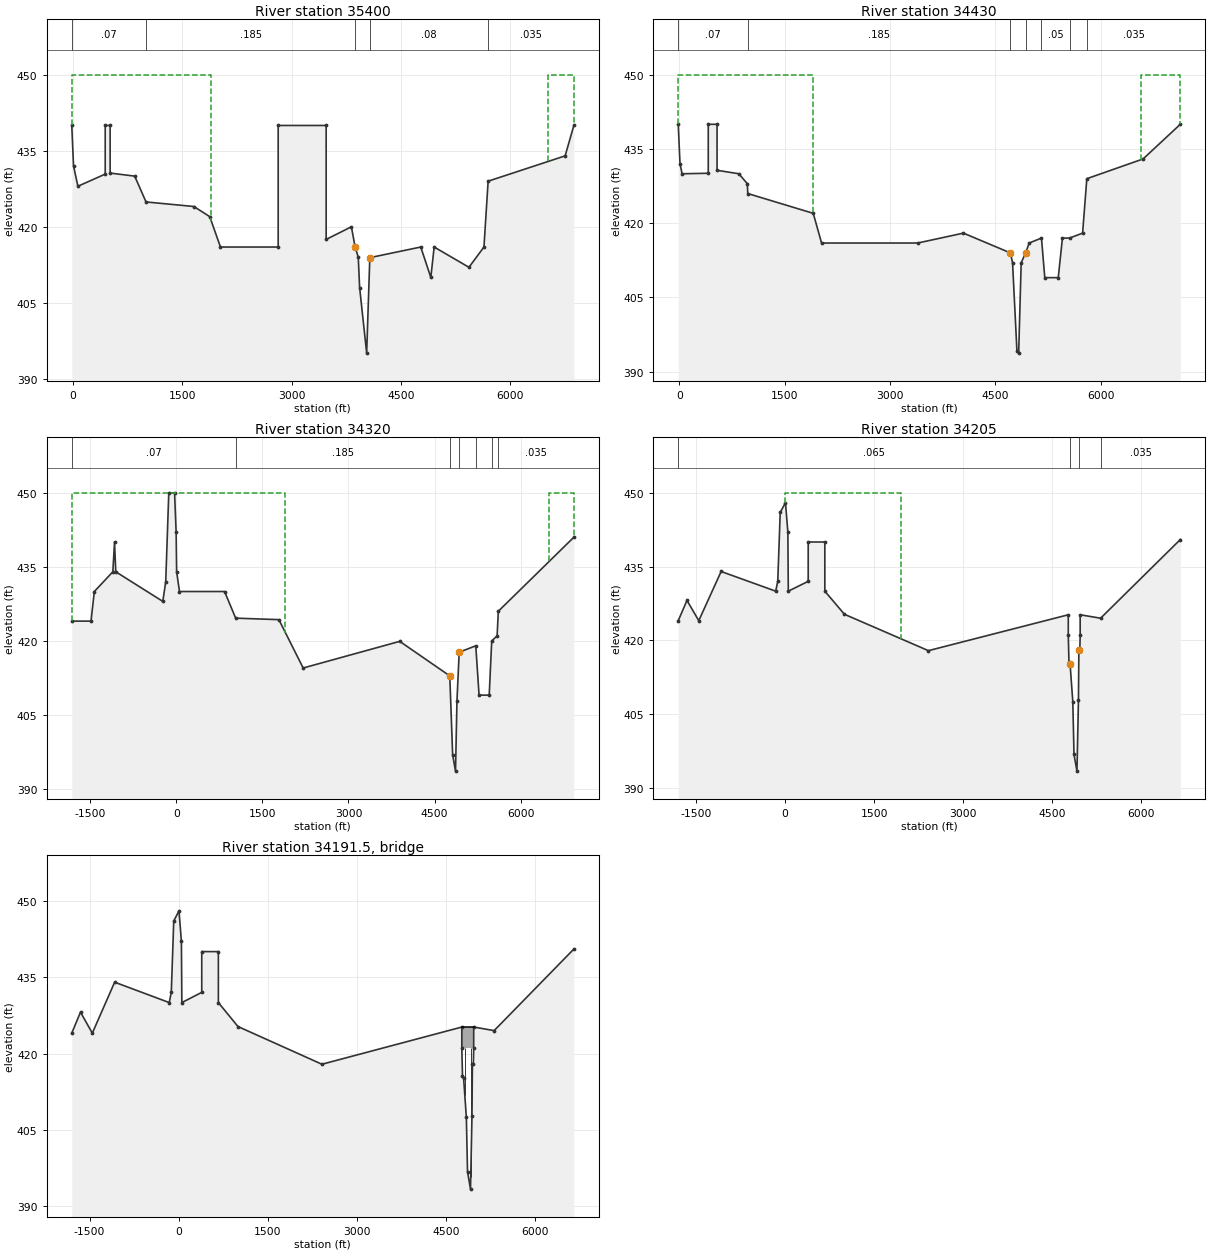
Type RM Length L Ch R = 1 ,35400   ,314,1050,195
BEGIN DESCRIPTION:
This cross section corresponds to cross section 35400 of the non-georeferenced CDC model which was the source of this model.
STA 354+00  New X-section
---------------------------------------------------------------------
CDC IRV082109-1 NORTHWEST LEVEE SEEPAGE CONTROL
CROSS-SECTION 13293 - 55400
UPSTREAM END
---------------------------------------------------------------------
END DESCRIPTION:
XS GIS Cut Line= 6
 2454794.62948517002909.716705222454637.936885097001911.17605138
2454633.30369225 7001849.90616082454572.889114927000012.10799913
2454201.420369686997699.429553632454236.189985196996065.33177197
#Sta/Elev= 30
   -18.7     440     5.4     432    65.4     428   440.1   430.4   440.1     440
   507.6     440   507.6   430.6   844.5     430    1000   424.9  1656.8     424
    1874     422  2021.1     416    2813     416    2813     440  3471.3     440
  3471.3   417.5  3817.6     420  3868.4     416  3911.5     414  3930.4     408
    4027  395.05  4070.2   413.9  4768.9     416  4907.2     410  4952.9     416
  5430.1     412    5636     416 5693.44     429 6749.83     434 6869.23     440
#Mann= 5 ,-1,0
   -18.7     .07       0    1000    .185       0  3868.4     .05       0
  4070.2     .08       0 5693.44    .035       0
#XS Ineff= 4 ,-1
   -18.7    1896     450    1896  3868.4     416  4070.2    6520   413.9
    6520 6869.23     450
Permanent Ineff=
       F       F       F       F
Bank Sta=3868.4,4070.2
XS Rating Curve= 0 ,0
Exp/Cntr=0.3,0.1

Type RM Length L Ch R = 1 ,34430   ,15,34,43
BEGIN DESCRIPTION:
This cross section corresponds to cross section 34430 of the non-georeferenced CDC model which was the source of this model.
STA 344+30  New X-section
END DESCRIPTION:
XS GIS Cut Line= 6
    2454898.32587002890.412609962454651.234102587001975.48563404
2454640.112733757001901.505467042454684.47156891 6999091.0475053
2454690.305874826996401.708067722454698.22777501 6995778.5521618
#Sta/Elev= 30
   -14.1     440    11.1     432    40.9     430   413.3   430.1   413.3     440
   538.3     440   538.3   430.7   848.6     430     969     428   975.7     426
  1907.1     422  2025.8     416  3394.6     416  4044.7     418  4713.2     414
 4743.91     412    4806  394.24    4831  393.74  4866.7     412  4929.3     414
    4981     416 5155.58     417 5202.36     409 5394.21     409 5453.74     417
  5554.8     417  5740.8     418  5800.8     429 6602.11     433 7131.39     440
#Mann= 7 ,-1,0
   -14.1     .07       0   975.7    .185       0  4713.2     .05       0
  4929.3     .08       0 5155.58     .05       0  5554.8     .08       0
  5800.8    .035       0
#XS Ineff= 4 ,-1
  -14.41    1900     450    1900  4713.2     414  4929.3    6578     414
    6578 7131.39     450
Permanent Ineff=
       F       F       F       F
Bank Sta=4713.2,4929.3
XS Rating Curve= 0 ,0
Exp/Cntr=0.3,0.1

Type RM Length L Ch R = 1 ,34320   ,120,120,120
BEGIN DESCRIPTION:
This cross section corresponds to cross section 34320 of the non-georeferenced CDC model which was the source of this model.
Cross-section EF051.  116 feet upstream of Wildwood Drive.  Stemmons North Industrial District in LOB.  Effective flow limit set at sta 1900 in LOB, at sta 6500 in ROB.
Channel data from COD Elm Fork channel survey.
END DESCRIPTION:
XS GIS Cut Line= 4
2455424.882489687004631.867788462454908.776566517002867.75747155
2454645.024141257001914.231163382454750.396633926995993.25678489
#Sta/Elev= 30
 -1822.3     424 -1486.8     424 -1429.2     430 -1106.3     434 -1077.2     440
 -1055.5     434    -236     428  -184.9     432  -131.6     450   -30.8     450
    -3.4     442       5     434      55     430     840     430    1034   424.6
    1787   424.3    2210   414.5    3893   419.9    4765   412.9    4815   396.9
    4865   393.6    4890   407.8    4929   417.7    5218     419 5275.34     409
    5452     409    5496     420    5590     421  5610.7     426    6927     441
#Mann= 7 ,-1,0
 -1822.3     .07       0    1034    .185       0    4765     .05       0
    4929     .08       0    5218     .05       0    5496     .08       0
  5610.7    .035       0
#XS Ineff= 4 ,-1
 -1822.3    1900     450    1900    4765   412.9    4929    6500   417.7
    6500    6967     450
Permanent Ineff=
       F       F       F       F
Bank Sta=4765,4929
XS Rating Curve= 0 ,0
Exp/Cntr=0.3,0.1

Type RM Length L Ch R = 1 ,34205   ,25,25,25
BEGIN DESCRIPTION:
This cross section corresponds to cross section 34205 of the non-georeferenced CDC model which was the source of this model.
One-foot upstream of Wildwood Drive.  Stemmons North Industrial District in LOB.
Channel data from COD Elm Fork channel survey.
END DESCRIPTION:
XS GIS Cut Line= 5
2455517.159536097004620.04596172 2455013.12117417002852.50717397
2454756.784416417001922.592695222454754.500300267001905.58682372
2454854.076872776996271.02460206
#Sta/Elev= 30
 -1798.8     424 -1651.7  428.12   -1453     424 -1076.4     434  -157.4     430
  -122.8     432   -81.4     446     6.8     448    47.5     442      55     430
     390     432     390     440     670     440     670     430    1000   425.3
    2414   417.9    4770   425.2    4770     421    4781   415.6    4800   415.2
    4846   407.5    4866   396.8    4916   393.4    4941   407.8    4948     418
    4964     418    4970     421    4970   425.2    5314   424.5  6656.4   440.5
#Mann= 4 ,-1,0
 -1798.8    .065       0    4800     .05       0    4948    .065       0
    5314    .035       0
#XS Ineff= 3 ,-1
       0    1960     450    1960    4800     415    4948    6656     418
Permanent Ineff=
       F       F       F
Bank Sta=4800,4948
XS Rating Curve= 0 ,0
Exp/Cntr=0.5,0.3

Type RM Length L Ch R = 3 ,34191.5 ,,,
BEGIN DESCRIPTION:
Wildwood Drive
END DESCRIPTION:
Node Name=Wildwood Drive
Bridge Culvert--1,0,-1,-1, 0
Deck Dist Width WeirC Skew NumUp NumDn MinLoCord MaxHiCord MaxSubmerge Is_Ogee
2,22,2.6,0, 6, 6, , , 0.95, 0, ,,,
    4770  4818.5  4821.5  4918.5  4921.5    4970
   425.2   425.2   425.2   425.2   425.2   425.2
     421     421     421     421     421     421
    4770  4818.5  4821.5  4918.5  4921.5    4970
   425.2   425.2   425.2   425.2   425.2   425.2
     421     421     421     421     421     421
Pier Skew, UpSta & Num, DnSta & Num=  ,4820, 2 ,4820, 2 , 0 , 0 , 0 ,,
       3       3
     390     424
       3       3
     390     424
Pier Skew, UpSta & Num, DnSta & Num=  ,4920, 2 ,4920, 2 , 0 , 0 , 0 ,,
       3       3
     390     424
       3       3
     390     424
BR Coef= 1 , 0 , 0 ,1.05, 0 ,,,0.8,-1,0.5,1,
WSPro=,,,, 1 ,,,, 0 ,,,, 0 ,,,,-1 ,-1 ,-1 , 0 , 0 , 0 , 0 , 0
BC Design=,, 0 ,, 0 ,,,,,,
BC HTab HWMax=446
BC Use User HTab Curves=0
BC User HTab FreeFlow(D)= 0