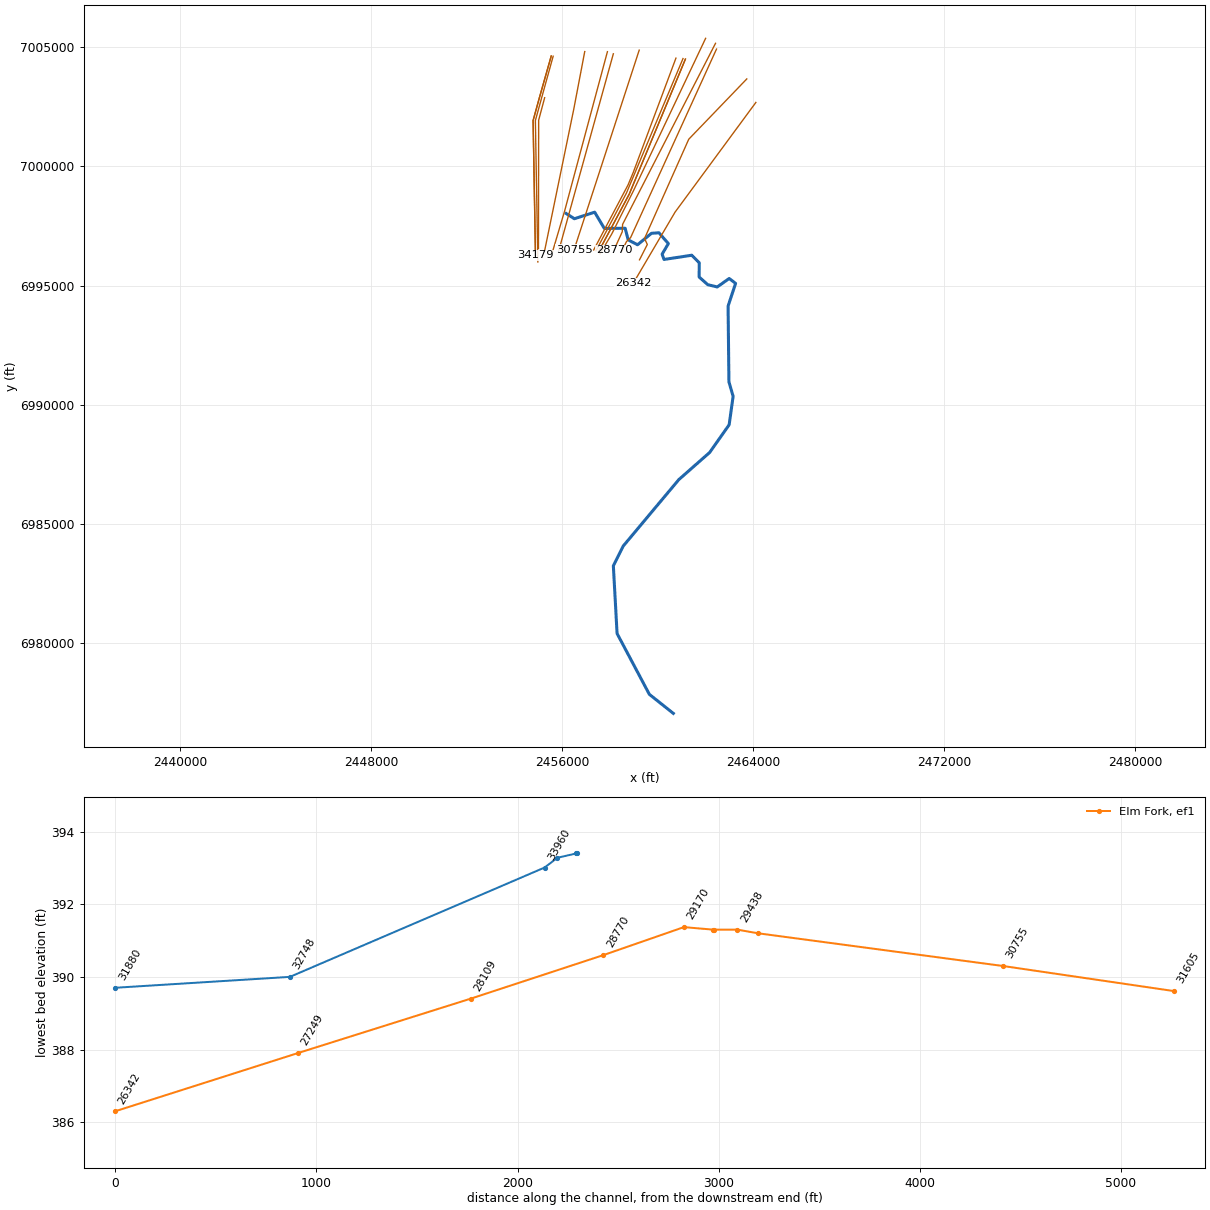
HEC-RAS study CDC_Consolidated_Model.prj: Upper Trinity CDC Consolidated Model

--- CDC_Consolidated_Model.g12 (geometry) --- (continued)

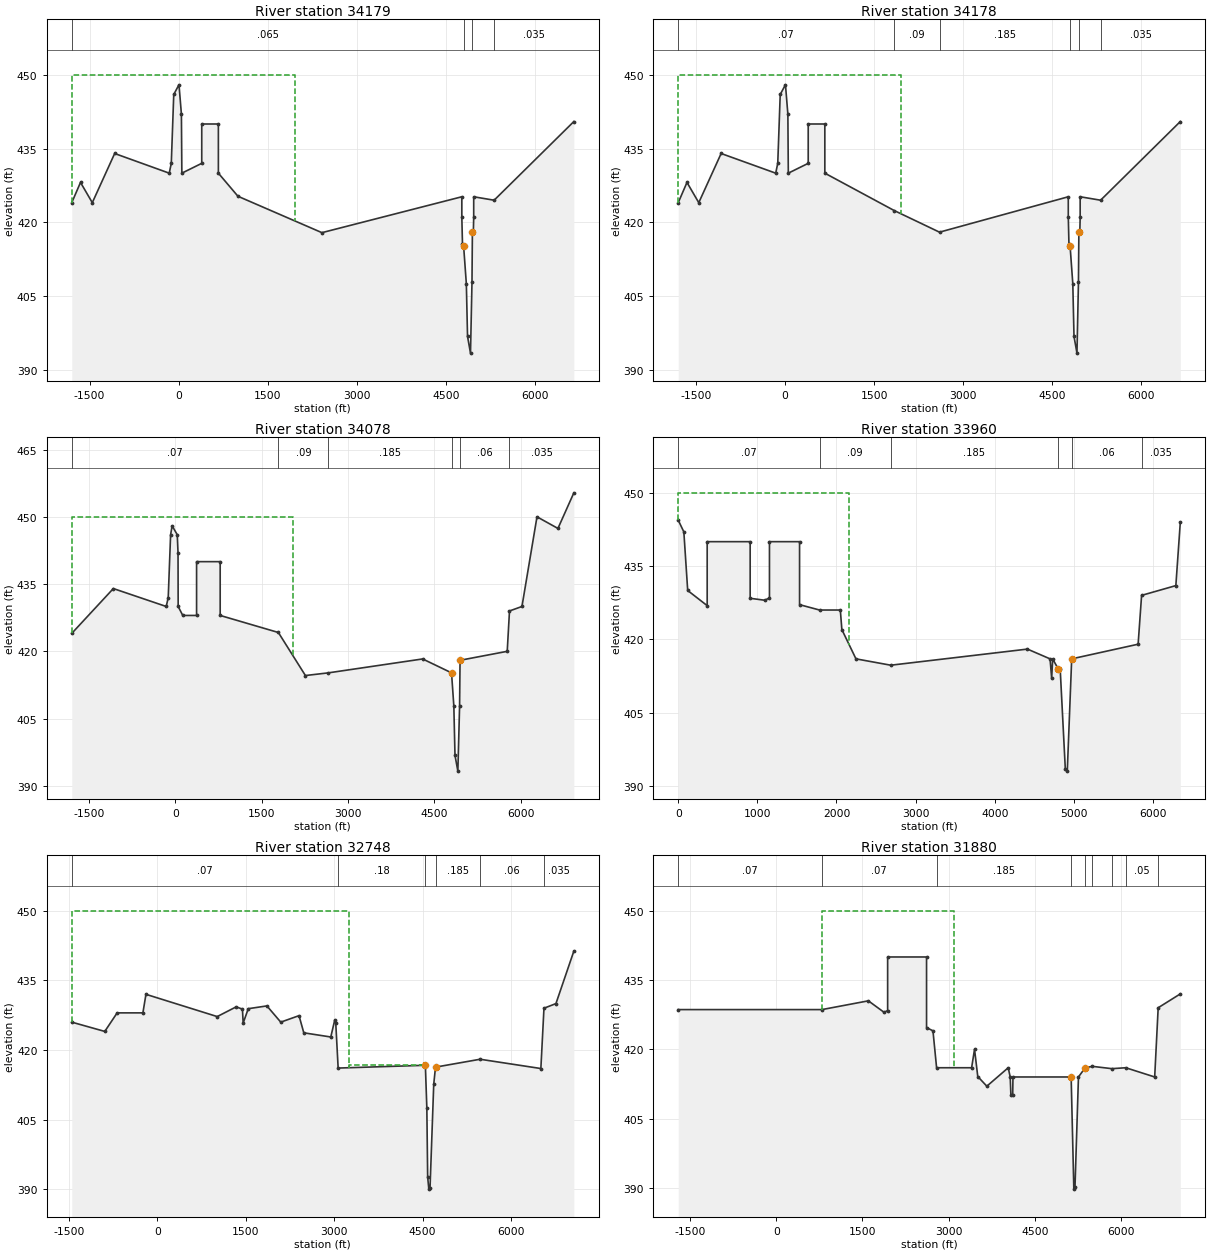
Type RM Length L Ch R = 1 ,34179   ,1,1,1
BEGIN DESCRIPTION:
This cross section corresponds to cross section 34179 of the non-georeferenced CDC model which was the source of this model.
END DESCRIPTION:
XS GIS Cut Line= 5
2455538.244467687004618.132579712455037.095535587002850.36938296
2454781.011074017001920.719011312454779.250906917001903.66359922
2454878.685747416996268.18996204
#Sta/Elev= 30
 -1798.8     424 -1651.7  428.12   -1453     424 -1076.4     434  -157.4     430
  -122.8     432   -81.4     446     6.8     448    47.5     442      55     430
     390     432     390     440     670     440     670     430    1000   425.3
    2414   417.9    4770   425.2    4770     421    4781   415.6    4800   415.2
    4846   407.5    4866   396.8    4916   393.4    4941   407.8    4948     418
    4964     418    4970     421    4970   425.2    5314   424.5  6656.4   440.5
#Mann= 4 ,-1,0
 -1798.8    .065       0    4800     .05       0    4948    .065       0
    5314    .035       0
#XS Ineff= 3 ,-1
 -1798.8    1960     450    1960    4800     415    4948    6656     418
Permanent Ineff=
       F       F       F
Bank Sta=4800,4948
XS Rating Curve= 0 ,0
Exp/Cntr=0.5,0.3

Type RM Length L Ch R = 1 ,34178   ,95,95,95
BEGIN DESCRIPTION:
This cross section corresponds to cross section 34178 of the non-georeferenced CDC model which was the source of this model.
One-foot downstream of Wildwood Drive.  Stemmons North Industrial District in  LOB.  Effective flow limit set at sta 1960 in LOB.
Channel data from COD Elm Fork channel survey.
END DESCRIPTION:
XS GIS Cut Line= 5
 2455539.05516167004618.059089052455038.017777837002850.28736213
2454781.943158757001920.648473382454780.203004757001903.58978046
2454879.631939776996268.08169454
#Sta/Elev= 30
 -1798.8     424 -1651.7  428.12   -1453     424 -1076.4     434  -157.4     430
  -122.8     432   -81.4     446     6.8     448    47.5     442      55     430
     390     432     390     440     670     440     670     430    1838   422.4
    2601     418    4770   425.2    4770     421    4781   415.6    4800   415.2
    4846   407.5    4866   396.8    4916   393.4    4941   407.8    4948     418
    4964     418    4970     421    4970   425.2    5314   424.5  6656.4   440.5
#Mann= 6 ,-1,0
 -1798.8     .07       0    1838     .09       0    2601    .185       0
    4800     .05       0    4948    .075       0    5314    .035       0
#XS Ineff= 3 ,-1
 -1798.8    1960     450    1960    4800     415    4948    6656     418
Permanent Ineff=
       F       F       F
Bank Sta=4800,4948
XS Rating Curve= 0 ,0
Exp/Cntr=0.3,0.1

Type RM Length L Ch R = 1 ,34078   ,64,64,64
BEGIN DESCRIPTION:
This cross section corresponds to cross section 34078 of the non-georeferenced CDC model which was the source of this model.
Right Overbank updated with 2007 levee topo.
Cross-section EF049.  101 feet downstream of Wildwood Drive.  Effective flow limit set at sta 2050 in LOB.  Stemmons North Industrial District in LOB. Channel data from COD Elm Fork channel survey - cross-section EF#049 surveyed February 1994.
END DESCRIPTION:
XS GIS Cut Line= 4
2455620.150471847004610.700507972455127.401129257002831.86515488
2454875.096843847001913.347963052454978.987712176995988.55961581
#Sta/Elev= 30
 -1798.8     424 -1076.4     434  -157.4     430  -122.8     432   -81.4     446
   -54.9     448    34.2     446    47.5     442      50     430     130     428
     370     428     370     440     780     440     780     428    1791   424.2
    2261   414.6    2661   415.2    4298   418.3    4800   415.2    4840   407.8
    4860   396.8    4910  393.28    4940   407.8    4948     418  5767.6     420
    5807     429  6023.7     430 6284.87     450 6649.01  447.41 6925.26  455.35
#Mann= 6 ,-1,0
 -1798.8     .07       0    1791     .09       0    2661    .185       0
    4800     .05       0    4948     .06       0    5807    .035       0
#XS Ineff= 3 ,-1
 -1798.8    2050     450    2050    4800   415.2    4948 6925.26     418
Permanent Ineff=
       F       F       F
Bank Sta=4800,4948
XS Rating Curve= 0 ,0
Exp/Cntr=0.3,0.1

Type RM Length L Ch R = 1 ,33960   ,752,1266,533
BEGIN DESCRIPTION:
This cross section corresponds to cross section 33960 of the non-georeferenced CDC model which was the source of this model.
STA 339+60  New X-section
END DESCRIPTION:
XS GIS Cut Line= 3
2455264.355907837002871.339485382455012.740597437001931.38795322
2455004.753408676996558.94036479
#Sta/Elev= 30
       0   444.4    70.9     442   119.6     430   365.8   426.9   365.8     440
   909.1     440   909.1   428.4  1096.1     428  1153.1   428.5  1153.1     440
  1533.4     440  1533.4   427.1    1786     426  2048.5     426    2068     422
  2246.1     416  2686.1   414.7  4413.4     418  4699.3     416  4719.6     412
  4732.3     416  4800.2     414  4827.1     414    4892  393.47    4917  393.01
  4972.7     416 5812.31     419 5856.16     429  6289.1     431  6345.5     444
#Mann= 6 ,-1,0
       0     .07       0    1786     .09       0  2686.1    .185       0
  4800.2     .05       0  4972.7     .06       0 5856.16    .035       0
#XS Ineff= 3 ,-1
       0    2160     450    2160  4800.2     414  4972.7    6345     416
Permanent Ineff=
       F       F       F
Bank Sta=4800.2,4972.7
XS Rating Curve= 0 ,0
Exp/Cntr=0.3,0.1

Type RM Length L Ch R = 1 ,32748   ,620,868,430
BEGIN DESCRIPTION:
This cross section corresponds to cross section 32748 of the non-georeferenced CDC model which was the source of this model.
Right Overbank updated with 2007 levee topo
Halff updated mitigation section for UofD
Cross-section EF048.  Effective flow limit set at sta 3250 in LOB. Effective flow limit set at end of Irving Flood Control District No. 1 Levee (Northwest Levee) in ROB.  Stemmons North Industrial District in LOB.
Channel data from COD Elm Fork channel survey.
END DESCRIPTION:
XS GIS Cut Line= 3
2456942.421121277004805.130893382456482.853142777002390.61210038
2455261.452370356996452.72502606
#Sta/Elev= 30
 -1453.4     426  -893.5     424 -683.27     428  -246.2     428  -194.6     432
    1015   427.2    1337   429.3    1443   428.8    1455   425.8    1542   428.9
    1858   429.5    2093     426    2403   427.4    2484   423.7    2942   422.8
    3010   426.5    3026   425.9    3067   416.1    4547   416.7    4572   407.5
    4586   392.6    4606     390    4626   390.2    4689   412.6    4719   416.3
    5476     418    6507     416  6559.7     429  6762.7     430 7066.67  441.31
#Mann= 6 ,-1,0
 -1453.4     .07       0    3067     .18       0    4547     .05       0
    4719    .185       0    5476     .06       0  6559.7    .035       0
#XS Ineff= 3 ,-1
 -1453.4    3250     450    3250    4547   416.7    4719 7066.67   416.3
Permanent Ineff=
       F       F       F
Bank Sta=4547,4719
XS Rating Curve= 0 ,0
Exp/Cntr=0.3,0.1

Type RM Length L Ch R = 1 ,31880   ,0,0,0
BEGIN DESCRIPTION:
This cross section corresponds to cross section 31880 of the non-georeferenced CDC model which was the source of this model.
STA 318+80  New X-section
END DESCRIPTION:
XS GIS Cut Line= 4
2457892.258667017004800.988710142457244.051751587002386.48514013
2456102.621947836998134.777436212455581.752910856996378.02766888
#Sta/Elev= 30
 -1704.2   428.6   795.8   428.6  1603.4   430.5  1877.7     428  1938.9   428.4
  1938.9     440  2615.7     440  2615.7   424.7  2727.4     424  2790.4     416
  3399.8     416  3450.5     420  3506.7   414.1  3664.4     412  4036.6     416
    4071     414  4083.3     410  4114.3     410  4119.1     414  5131.3     414
    5178   389.7    5198   390.1  5258.5     414  5375.5     416    5502   416.3
  5840.1   415.8 6081.62     416 6584.64     414 6645.38     429  7030.4     432
#Mann= 9 ,-1,0
 -1704.2     .07       0   795.8     .07       0  2790.4    .185       0
  5131.3     .05       0  5375.5    .185       0    5502     .06       0
  5840.1      .1       0 6081.62     .05       0 6645.38    .035       0
#XS Ineff= 3 ,-1
   795.8    3100     450    3100  5131.3     414  5375.57030.397     416
Permanent Ineff=
       F       F       F
Bank Sta=5131.3,5375.5
XS Rating Curve= 0 ,0
Exp/Cntr=0.3,0.1

River Reach=Elm Fork        ,ef1
Reach XY= 30
      2456164.29      6998018.92      2456508.51       6997799.9
      2457358.35      6998074.71      2457760.56      6997394.95
      2458634.58      6997399.94      2458762.76      6996913.44
      2459151.98      6996708.01      2459737.97      6997188.49
      2460049.87      6997211.53      2460444.67       6996757.1
      2460182.54      6996315.64      2460262.81      6996093.07
      2461424.38      6996270.13      2461738.29      6995952.87
      2461732.81      6995358.08      2462093.57      6995035.75
      2462490.85      6994940.93      2462991.68      6995295.05
      2463259.53      6995089.58      2462945.39      6994137.61
      2462980.12      6990964.45      2463155.51      6990359.08
      2462990.63      6989165.68      2462172.98      6988003.76
      2460879.68      6986864.71      2458557.35      6984087.07
      2458140.49       6983253.5      2458296.43      6980416.59
     2459648.204     6977868.474       2460651.9      6977070.51

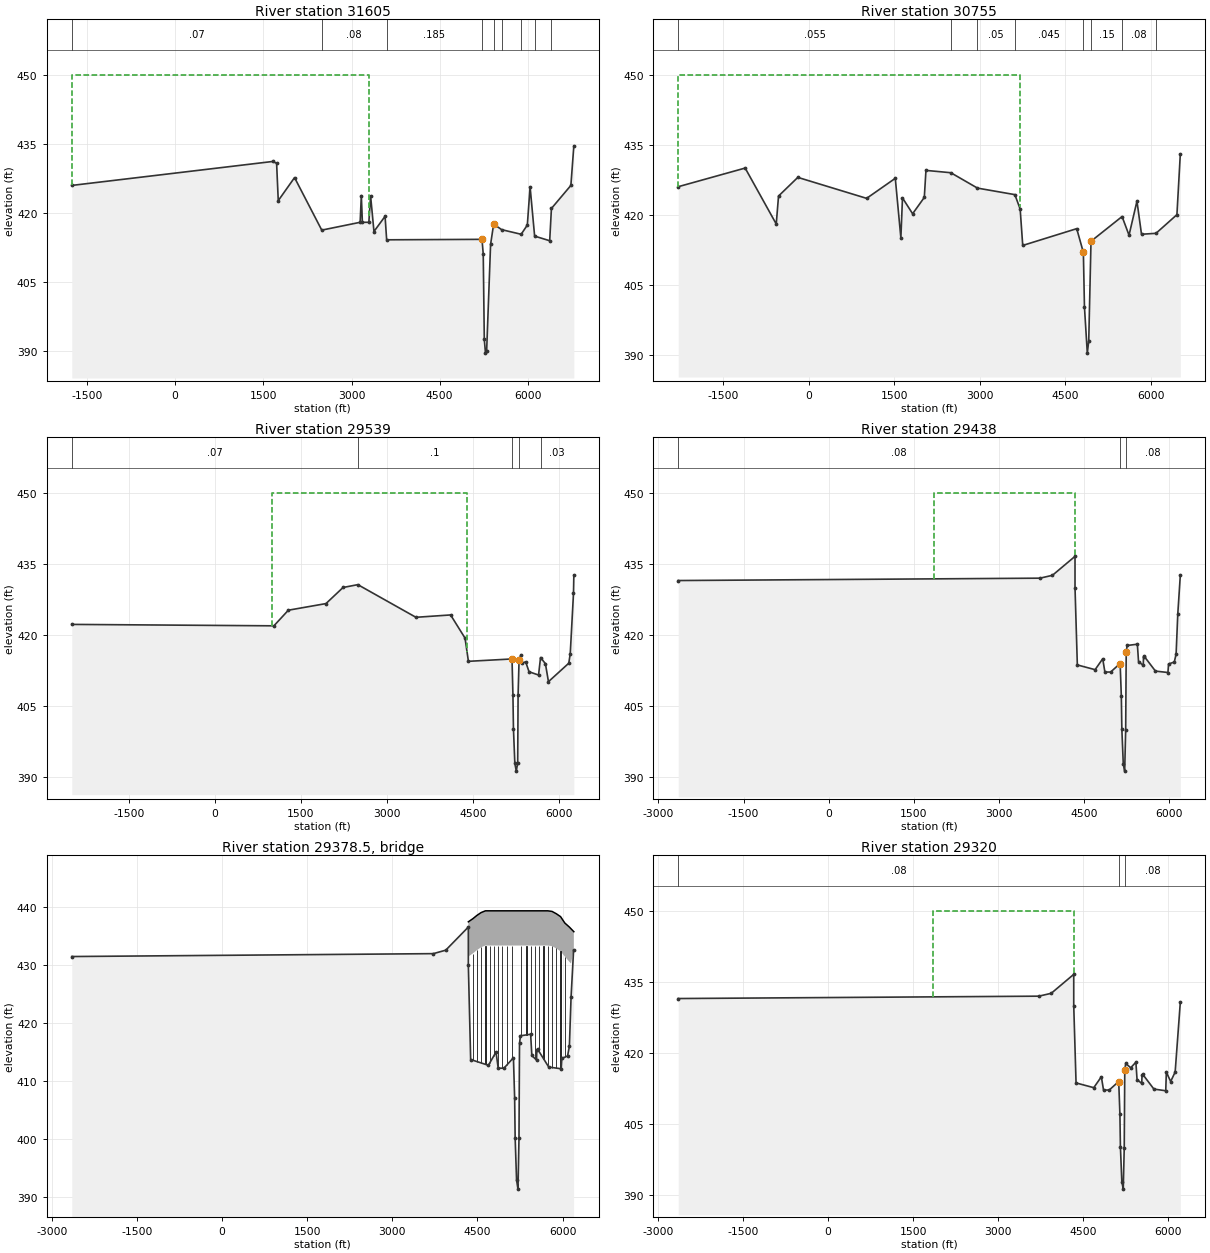
Type RM Length L Ch R = 1 ,31605   ,739,849,649
BEGIN DESCRIPTION:
This cross section corresponds to cross section 31605 of the non-georeferenced CDC model which was the source of this model.
Right Overbank updated with 2007 levee topo.
------------------------------------
CDC IRV050301-1 University of Dallas
Cross-section 31605 - 35400
Located in ROB.
----------------------------------
CDC IRV012607-1 Widening of SH114
Cross-section 31605 - 35400
Located in ROB.
----------------------------------
Cross-section EF047.  Effective flow limit set at sta 3300 in LOB
END DESCRIPTION:
XS GIS Cut Line= 2
 2458140.08736117004712.652075722455859.869480586996481.62555879
#Sta/Elev= 30
 -1758.7     426    1661   431.2    1726   430.8    1754   422.7    2031   427.7
    2494   416.3    3147     418    3167   423.8    3185     418    3295     418
    3325   423.7    3382     416    3571   419.3    3598   414.2    5220   414.3
    5241   411.1    5259   392.6    5279  389.61    5299   390.1    5366   413.2
    5418   417.6    5555   416.4    5886   415.4    5991   417.4    6038   425.7
 6115.18     415  6371.6     414  6400.9     421 6731.81     426 6782.33   434.6
#Mann= 9 ,-1,0
 -1758.7     .07       0    2494     .08       0    3598    .185       0
    5220     .05       0    5418     .13       0    5555     .06       0
    5886     .13       0 6115.18     .05       06400.897     .13       0
#XS Ineff= 3 ,-1
 -1758.7    3300     450    3300    5220   414.3    5418 6782.33   417.6
Permanent Ineff=
       F       F       F
Bank Sta=5220,5418
XS Rating Curve= 0 ,0
Exp/Cntr=0.3,0.1

Type RM Length L Ch R = 1 ,30755   ,1091,1217,901
BEGIN DESCRIPTION:
This cross section corresponds to cross section 30755 of the non-georeferenced CDC model which was the source of this model.
Right Overbank updated with 2007 levee topo.
Cross-section EF046.  Effective flow limit set at sta 3700 in LOB.  Effective flow limit at Irving Flood Control District No.1 Levee (Northwest Levee) in ROB.  Stemmons North Industrial District in LOB.
END DESCRIPTION:
XS GIS Cut Line= 2
2459223.183948167004865.41456546 2456492.74616766996490.03006954
#Sta/Elev= 30
 -2288.4     426 -1114.3     430  -568.7     418  -528.6     424  -190.3     428
    1017   423.5    1520   427.8    1618     415    1646   423.6    1824   420.2
    2029   423.7    2058   429.5    2494     429    2962   425.7    3618   424.3
    3711   421.2    3756   413.4    4703     417    4820   411.9    4839   400.2
    4889   390.3    4914   392.9    4954   414.3    5499   419.6    5621   415.6
    5760   422.9    5840   415.8    6094     416 6461.37     420 6520.82     433
#Mann= 8 ,-1,0
 -2288.4    .055       0    2494     .06       0    2962     .05       0
    3618    .045       0    4820     .05       0    4954     .15       0
    5499     .08       0    6094     .12       0
#XS Ineff= 3 ,-1
 -2288.4    3700     450    3700    4820   411.9    4954 6520.82   414.3
Permanent Ineff=
       F       F       F
Bank Sta=4820,4954
XS Rating Curve= 0 ,0
Exp/Cntr=0.3,0.1

Type RM Length L Ch R = 1 ,29539   ,103,103,103
BEGIN DESCRIPTION:
This cross section corresponds to cross section 29539 of the non-georeferenced CDC model which was the source of this model.
Right Overbank updated with 2007 levee topo.
Cross-section EF045.  102 feet upstream of Loop 12.  Effective flow limit set at sta 4400 in LOB, in ROB at Irving Flood Control District No.1 Levee (Northwest Levee).  Stemmons North Industrial District in LOB.
Channel data from COD Elm Fork channel survey.
END DESCRIPTION:
XS GIS Cut Line= 5
2460761.552754427004531.063646032459537.779775687001251.98150364
2458974.645075176999743.070151392458755.869922166999217.50099255
2457317.215975346996490.42869081
#Sta/Elev= 30
   -2500   422.2    1028   421.9    1280   425.2    1937   426.6    2235     430
    2493   430.6    3507   423.7    4112   424.2    4364   419.3    4423   414.4
    5184   414.9    5200   407.3    5209   400.2    5233   392.9    5258   391.2
    5283   392.9    5290   407.3    5307   414.6    5339   415.8    5357     414
    5422   414.3    5481   412.2    5647   411.5    5682   415.2    5767   413.9
    5820   410.1 6174.93     414 6200.25     416 6257.05  428.77 6263.14   432.6
#Mann= 5 ,-1,0
   -2500     .07       0    2493      .1       0    5184     .05       0
    5307      .1       0    5682     .03       0
#XS Ineff= 3 ,-1
    1000    4400     450    4400    5184   414.9    53076263.141   414.6
Permanent Ineff=
       F       F       F
Bank Sta=5184,5307
XS Rating Curve= 0 ,0
Exp/Cntr=0.3,0.1

Type RM Length L Ch R = 1 ,29438   ,118,118,118
BEGIN DESCRIPTION:
This cross section corresponds to cross section 29438 of the non-georeferenced CDC model which was the source of this model.
One-foot upstream of Loop 12.
END DESCRIPTION:
XS GIS Cut Line= 5
2461057.618049797004512.107408382459313.870774697000363.69259781
2458687.587250356998873.749711542457872.600035166997323.13339022
2457413.172804426996460.78668971
#Sta/Elev= 30
   -2650   431.5    3723     432    3942   432.6    4340   436.6    4340     430
    4381   413.7    4694   412.7    4828     415  4866.5   412.2    4967   412.2
    5135     414    5156   407.1    5165   400.2    5190   392.9    5215   391.3
 5232.66  400.08    5242   416.5    5259   417.8  5438.5  418.07    5459   414.4
    5542   413.6    5547   415.4    5560   415.5    5757   412.4    5977   412.1
  5988.1   413.9 6089.21  414.31 6121.02     416 6150.63  424.47 6195.06   432.6
#Mann= 3 ,0,0
   -2650     .08       0    5135     .05       0    5242     .08       0
#XS Ineff= 3 ,-1
    1850    4340     450    4340    5135     414    52426223.561   416.5
Permanent Ineff=
       F       F       F
Bank Sta=5135,5242
XS Rating Curve= 0 ,0
Exp/Cntr=0.5,0.3

Type RM Length L Ch R = 3 ,29378.5 ,,,
BEGIN DESCRIPTION:
Loop 12/Walton Walker Boulevard
END DESCRIPTION:
Node Name=Loop 12
Bridge Culvert--1,0,-1,-1, 0
Deck Dist Width WeirC Skew NumUp NumDn MinLoCord MaxHiCord MaxSubmerge Is_Ogee
2,115,2.6,0, 45, 45, , , 0.95, 0, ,,,
    4340 4413.75 4416.25 4488.75 4491.25  4563.5  4566.5  4638.5  4641.5  4713.5
  4716.5  4788.5  4791.5  4863.5  4866.5  4938.5  4941.5  5013.5  5016.5  5113.5
  5116.5  5263.5  5266.5  5363.5  5366.5  5438.5  5441.5  5513.5  5516.5  5588.5
  5591.5  5663.5  5666.5 5738.75 5741.25 5813.75 5816.25 5888.75 5891.25 5963.75
 5966.25 6038.75 6041.25    6120 6199.69
   437.5     438  438.01  438.59 438.608  439.09 439.106 439.394   439.4   439.4
   439.4   439.4   439.4   439.4   439.4   439.4   439.4   439.4   439.4   439.4
   439.4   439.4   439.4   439.4   439.4   439.4   439.4   439.4   439.4   439.4
   439.4   439.4   439.4   439.4   439.4 439.302 439.293 438.907 438.892 438.408
 438.387 437.318 437.288   436.6  435.79
   431.5     432  432.01  432.59 432.608  433.09 433.106 433.394   433.4   433.4
   433.4   433.4   433.4   433.4   433.4   433.4   433.4   433.4   433.4   433.4
   433.4   433.4   433.4   433.4   433.4   433.4   433.4   433.4   433.4   433.4
   433.4   433.4   433.4   433.4   433.4 433.302 433.293 432.907 432.892 432.408
 432.387 431.521 431.491   430.6  429.79
    4340 4413.75 4416.25 4488.75 4491.25  4563.5  4566.5  4638.5  4641.5  4713.5
  4716.5  4788.5  4791.5  4863.5  4866.5  4938.5  4941.5  5013.5  5016.5  5113.5
  5116.5  5263.5  5266.5  5363.5  5366.5  5438.5  5441.5  5513.5  5516.5  5588.5
  5591.5  5663.5  5666.5 5738.75 5741.25 5813.75 5816.25 5888.75 5891.25 5963.75
 5966.25 6038.75 6041.25    6120 6225.87
   437.5     438  438.01  438.59 438.608  439.09 439.106 439.394   439.4   439.4
   439.4   439.4   439.4   439.4   439.4   439.4   439.4   439.4   439.4   439.4
   439.4   439.4   439.4   439.4   439.4   439.4   439.4   439.4   439.4   439.4
   439.4   439.4   439.4   439.4   439.4 439.302 439.293 438.907 438.892 438.408
 438.387 437.318 437.288   436.6  435.79
   431.5     432  432.01  432.59 432.608  433.09 433.106 433.394   433.4   433.4
   433.4   433.4   433.4   433.4   433.4   433.4   433.4   433.4   433.4   433.4
   433.4   433.4   433.4   433.4   433.4   433.4   433.4   433.4   433.4   433.4
   433.4   433.4   433.4   433.4   433.4 433.302 433.293 432.907 432.892 432.408
 432.387 431.521 431.491   430.6  429.79
Pier Skew, UpSta & Num, DnSta & Num=  ,4415, 2 ,4415, 2 , 0 , 0 , 0 ,,
     2.5     2.5
     390     444
     2.5     2.5
     390     444
Pier Skew, UpSta & Num, DnSta & Num=  ,4490, 2 ,4490, 2 , 0 , 0 , 0 ,,
     2.5     2.5
     390     444
     2.5     2.5
     390     444
Pier Skew, UpSta & Num, DnSta & Num=  ,4565, 2 ,4565, 2 , 0 , 0 , 0 ,,
       3       3
     390     444
       3       3
     390     444
Pier Skew, UpSta & Num, DnSta & Num=  ,4641, 2 ,4641, 2 , 0 , 0 , 0 ,,
       3       3
     390     444
       3       3
     390     444
Pier Skew, UpSta & Num, DnSta & Num=  ,4715, 2 ,4715, 2 , 0 , 0 , 0 ,,
       3       3
     390     444
       3       3
     390     444
Pier Skew, UpSta & Num, DnSta & Num=  ,4790, 2 ,4790, 2 , 0 , 0 , 0 ,,
       3       3
     390     444
       3       3
     390     444
Pier Skew, UpSta & Num, DnSta & Num=  ,4865, 2 ,4865, 2 , 0 , 0 , 0 ,,
       3       3
     390     444
       3       3
     390     444
Pier Skew, UpSta & Num, DnSta & Num=  ,4940, 2 ,4940, 2 , 0 , 0 , 0 ,,
       3       3
     390     444
       3       3
     390     444
Pier Skew, UpSta & Num, DnSta & Num=  ,5015, 2 ,5015, 2 , 0 , 0 , 0 ,,
       3       3
     390     444
       3       3
     390     444
Pier Skew, UpSta & Num, DnSta & Num=  ,5115, 2 ,5115, 2 , 0 , 0 , 0 ,,
       3       3
     390     444
       3       3
     390     444
Pier Skew, UpSta & Num, DnSta & Num=  ,5265, 2 ,5265, 2 , 0 , 0 , 0 ,,
       3       3
     390     444
       3       3
     390     444
Pier Skew, UpSta & Num, DnSta & Num=  ,5365, 2 ,5365, 2 , 0 , 0 , 0 ,,
       3       3
     390     444
       3       3
     390     444
Pier Skew, UpSta & Num, DnSta & Num=  ,5440, 2 ,5440, 2 , 0 , 0 , 0 ,,
       3       3
     390     444
       3       3
     390     444
Pier Skew, UpSta & Num, DnSta & Num=  ,5515, 2 ,5515, 2 , 0 , 0 , 0 ,,
       3       3
     390     444
       3       3
     390     444
Pier Skew, UpSta & Num, DnSta & Num=  ,5590, 2 ,5590, 2 , 0 , 0 , 0 ,,
       3       3
     390     444
       3       3
     390     444
Pier Skew, UpSta & Num, DnSta & Num=  ,5665, 2 ,5665, 2 , 0 , 0 , 0 ,,
       3       3
     390     444
       3       3
     390     444
Pier Skew, UpSta & Num, DnSta & Num=  ,5740, 2 ,5740, 2 , 0 , 0 , 0 ,,
     2.5     2.5
     390     444
     2.5     2.5
     390     444
Pier Skew, UpSta & Num, DnSta & Num=  ,5815, 2 ,5815, 2 , 0 , 0 , 0 ,,
     2.5     2.5
     390     444
     2.5     2.5
     390     444
Pier Skew, UpSta & Num, DnSta & Num=  ,5890, 2 ,5890, 2 , 0 , 0 , 0 ,,
     2.5     2.5
     390     444
     2.5     2.5
     390     444
Pier Skew, UpSta & Num, DnSta & Num=  ,5965, 2 ,5965, 2 , 0 , 0 , 0 ,,
     2.5     2.5
     390     444
     2.5     2.5
     390     444
Pier Skew, UpSta & Num, DnSta & Num=  ,6040, 2 ,6040, 2 , 0 , 0 , 0 ,,
     2.5     2.5
     390     444
     2.5     2.5
     390     444
BR Coef= 1 , 0 , 0 ,1.05, 0 ,,,0.8,-1,0.5,1,
WSPro=,,,, 1 ,,,, 0 ,,,, 0 ,,,,-1 ,-1 ,-1 , 0 , 0 , 0 , 0 , 0
BC Design=,, 0 ,, 0 ,,,,,,
BC HTab HWMax=436.6
BC Use User HTab Curves=0
BC User HTab FreeFlow(D)= 0

Type RM Length L Ch R = 1 ,29320   ,1,1,1
BEGIN DESCRIPTION:
This cross section corresponds to cross section 29320 of the non-georeferenced CDC model which was the source of this model.
END DESCRIPTION:
XS GIS Cut Line= 4
2461157.621579477004488.838138672459429.567721757000333.86162071
2458803.524354436998828.587072222457515.645368526996406.39703472
#Sta/Elev= 30
   -2650   431.5    3723     432    3942   432.6    4340   436.6    4340     430
    4381   413.7    4694   412.7    4828     415  4866.5   412.2    4967   412.2
    5135     414    5156   407.1    5165   400.2    5190   392.9    5215   391.3
 5232.66  400.08    5242   416.5    5259   417.8    5347   416.9  5438.5  418.07
    5459   414.4    5542   413.6    5547   415.4    5560   415.5    5757   412.4
 5966.25  412.05 5976.57  415.98 6053.09     414 6132.41     416 6223.56   430.7
#Mann= 3 ,0,0
   -2650     .08       0    5135     .05       0    5242     .08       0
#XS Ineff= 3 ,-1
    1850    4340     450    4340    5135     414    52426223.561   416.5
Permanent Ineff=
       F       F       F
Bank Sta=5135,5242
XS Rating Curve= 0 ,0
Exp/Cntr=0.5,0.3

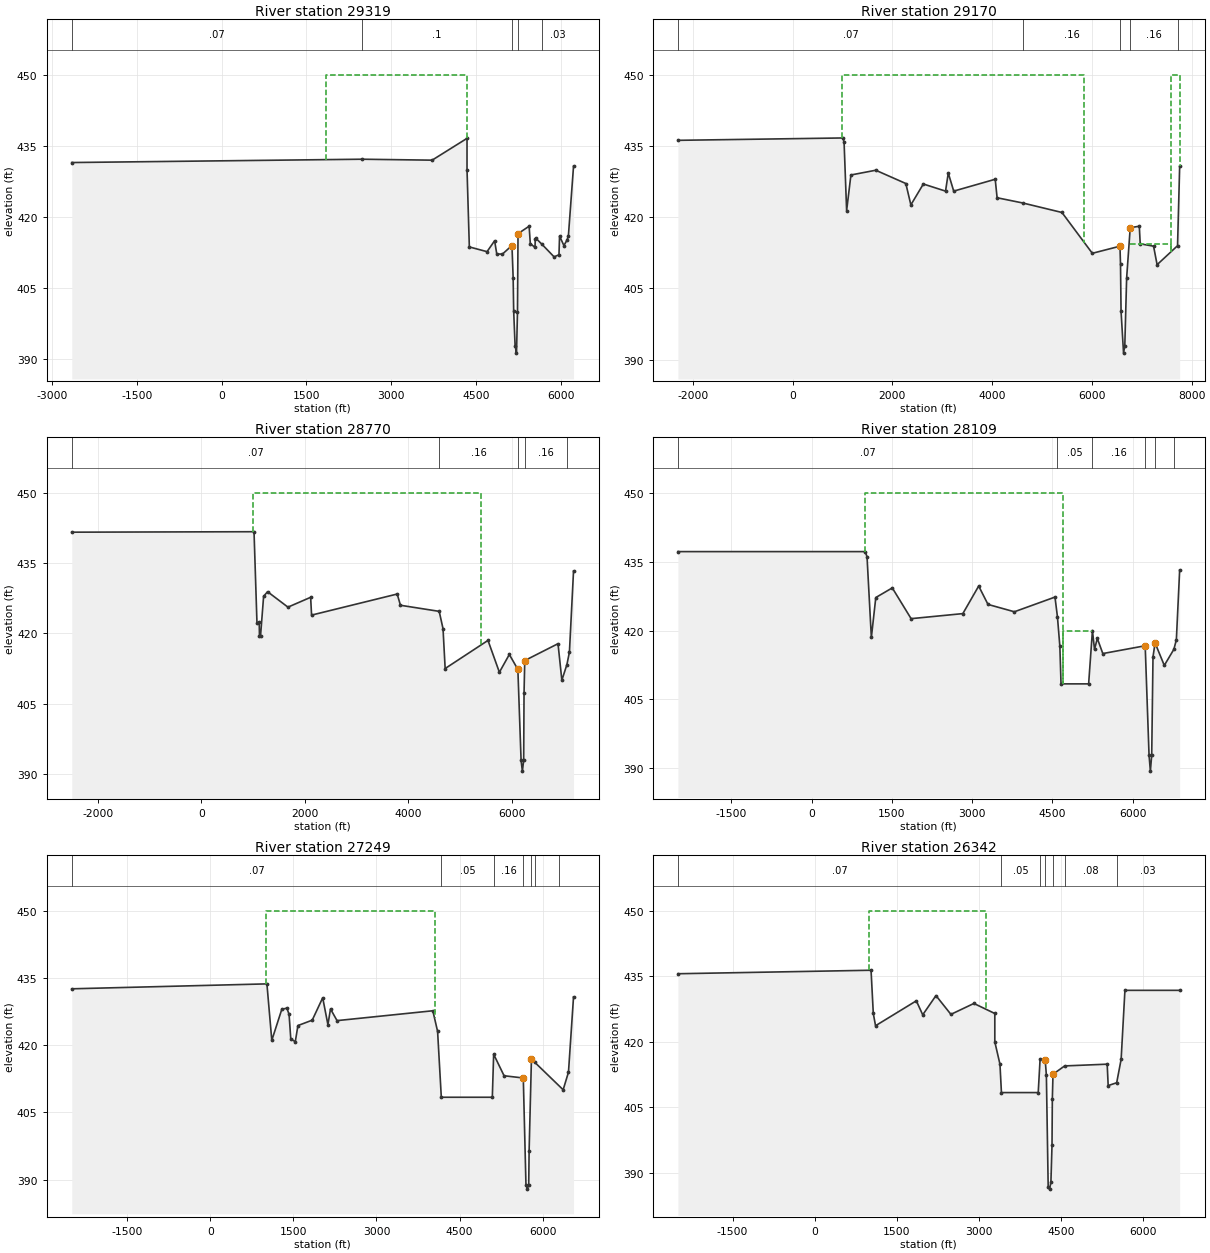
Type RM Length L Ch R = 1 ,29319   ,147,147,147
BEGIN DESCRIPTION:
This cross section corresponds to cross section 29319 of the non-georeferenced CDC model which was the source of this model.
One-foot downstream of Loop 12.
END DESCRIPTION:
XS GIS Cut Line= 4
2461158.115553377004488.565110742459431.03294191 7000333.1847848
2458805.454468676998828.035892222457516.453437756996406.10897756
#Sta/Elev= 30
   -2650   431.5    2484   432.2    3723     432    4340   436.6    4340     430
    4381   413.7    4694   412.7    4828     415  4866.5   412.2    4967   412.2
    5135     414    5156   407.1    5165   400.2    5190   392.9    5215   391.3
 5232.66  400.08    5242   416.5  5438.5  418.07    5459   414.4    5542   413.6
    5547   415.4    5560   415.5  5666.5  414.24    5880   411.6 5966.25  412.05
 5976.57  415.98 6053.09     414 6108.63  415.14 6132.41     416 6223.56   430.7
#Mann= 5 ,-1,0
   -2650     .07       0    2484      .1       0    5135     .05       0
    5242      .1       0  5666.5     .03       0
#XS Ineff= 3 ,-1
    1850    4340     450    4340    5135     414    52426223.561   416.5
Permanent Ineff=
       F       F       F
Bank Sta=5135,5242
XS Rating Curve= 0 ,0
Exp/Cntr=0.3,0.1

Type RM Length L Ch R = 1 ,29170   ,230,400,390
BEGIN DESCRIPTION:
This cross section corresponds to cross section 29170 of the non-georeferenced CDC model which was the source of this model.
Right Overbank updated with 2007 levee topo.
Cross-section EF043.  150 feet downstream of Loop 12.  Effective flow limit set at sta 5850 in LOB, at sta 7580 in ROB near Irving Flood Control District No. 1 Levee (Northwest Levee) in ROB.  Conveyance removed in low areas in ROB.  High ground removed in ROB.  Ineffective flow from sta 5400 - 5850.
Channel data from COD Elm Fork chann
END DESCRIPTION:
XS GIS Cut Line= 5
2462004.206311217005359.590957262460593.016182247002376.54848021
  2458981.7388936998970.552011392458068.408042526997150.21805364
 2457580.91131416996328.34961863
#Sta/Elev= 30
   -2300   436.2    1010   436.7    1032   435.8    1083   421.4    1169   428.9
    1667   429.9    2270   427.1    2371   422.6    2621     427    3066   425.5
    3121   429.3    3230   425.5    4062     428    4100   424.1    4615     423
    5400     421    6009   412.4    6563   413.9    6574   410.1    6585   400.2
    6635  391.37    6660   392.9    6697   407.2    6769   417.8    6951   418.1
    6969   414.4    7237   413.9 7307.77     410 7717.67     414 7760.08   430.7
#Mann= 5 ,-1,0
   -2300     .07       0    4615     .16       0    6563     .05       0
    6769     .16       0 7717.67     .03       0
#XS Ineff= 4 ,-1
    1000    5850     450    5850    6563   413.9    6769    7580   414.4
    7580 7760.08     450
Permanent Ineff=
       F       F       F       F
Bank Sta=6563,6769
XS Rating Curve= 0 ,0
Exp/Cntr=0.3,0.1

Type RM Length L Ch R = 1 ,28770   ,529,660,339
BEGIN DESCRIPTION:
This cross section corresponds to cross section 28770 of the non-georeferenced CDC model which was the source of this model.
Right Overbank updated with 2007 levee topo.
Cross-section EF042.  Effective flow limit set at sta 5400 in LOB, at Irving Flood Control District No. 1 (Northwest Levee) in ROB.  Conveyance removed in low areas in ROB.
Channel data from COD Elm Fork channel survey.
END DESCRIPTION:
XS GIS Cut Line= 5
2462419.249360357005151.46204691 2460821.65483267002037.35033971
2458527.822149936997566.09615888  2458512.9760516997250.61516255
2458162.704113756996480.13179538
#Sta/Elev= 30
   -2500   441.6    1019   441.7    1076   422.2    1119   422.4    1124   419.5
    1145   419.5    1204   427.9    1280   428.9    1674   425.6    2112   427.7
    2130   423.9    3783   428.4    3846     426    4594   424.7    4668     421
    4709   412.5    5536   418.5    5756   411.7    5948   415.5    6113   412.3
    6175   392.9    6200   390.6    6225   392.9    6232   407.2    6246   414.2
    6888   417.8 6962.14     410 7059.91  413.35 7108.28     416 7187.51   433.3
#Mann= 5 ,-1,0
   -2500     .07       0    4594     .16       0    6113     .05       0
    6246     .16       0 7059.91     .03       0
#XS Ineff= 3 ,-1
    1000    5400     450    5400    6113   412.3    6246 7187.51   414.2
Permanent Ineff=
       F       F       F
Bank Sta=6113,6246
XS Rating Curve= 0 ,0
Exp/Cntr=0.3,0.1

Type RM Length L Ch R = 1 ,28109   ,550,860,840
BEGIN DESCRIPTION:
This cross section corresponds to cross section 28109 of the non-georeferenced CDC model which was the source of this model.
Right Overbank updated with 2007 levee topo.
Cross-section EF041.  Effective flow limit set at sta 4700 in LOB, at Irving Flood Control District No. 1 (Northwest Levee) in ROB.  Conveyance of pond in LOB removed below elev. 420.0.  Conveyance removed in low areas in ROB.
Channel data from COD Elm Fork channel survey.
END DESCRIPTION:
XS GIS Cut Line= 5
 2462460.44887437004910.22740512 2461010.26830057001724.79551864
2458861.859867666997005.653054042458687.417959336996838.63403113
2458491.851749426996431.53838864
#Sta/Elev= 30
   -2500   437.2    1000   437.2    1035   436.1    1116   418.5    1199   427.2
    1507   429.3    1859   422.6    2826   423.7    3122   429.7    3296   425.7
    3789   424.1    4548   427.3    4594     423    4639   416.6    4661   408.4
    5177   408.4    5248     420    5287   415.9    5339   418.3    5442     415
    6234   416.7    6306   392.9    6331   389.4    6356   392.9    6380   414.3
    6419   417.3  6591.2  412.42 6770.37  415.93 6816.63     418 6878.35   433.2
#Mann= 6 ,-1,0
   -2500     .07       0    4594     .05       0    5248     .16       0
    6234     .05       0    6419     .16       0 6770.37     .03       0
#XS Ineff= 4 ,-1
    1000    4700     450    4700    5248     420    5248    6234   416.7
    6419    6851   417.3
Permanent Ineff=
       F       T       F       F
Bank Sta=6234,6419
XS Rating Curve= 0 ,0
Exp/Cntr=0.3,0.1

Type RM Length L Ch R = 1 ,27249   ,700,907,400
BEGIN DESCRIPTION:
This cross section corresponds to cross section 27249 of the non-georeferenced CDC model which was the source of this model.
Right Overbank updated with 2007 levee topo.
Cross-section EF040.  Effective flow limit set at sta 4050 in LOB, at Irving Flood Control District No. 1 (Northwest Levee) in ROB.  Conveyance of pond in LOB removed below elev. 418.0.  Conveyance removed in low areas in ROB.
Channel data from COD Elm Fork channel survey.
END DESCRIPTION:
XS GIS Cut Line= 6
 2463729.0261799 7003658.81911182461302.577755247001136.44958247
2461297.64797509 7001131.32492082459446.397084426996971.78402729
2459563.31089258 6996721.25500082459236.204919526996078.32124729
#Sta/Elev= 30
   -2500   432.6    1023   433.7    1111   421.1    1291     428    1383   428.3
    1423   426.9    1454   421.4    1535   420.8    1583   424.4    1841   425.6
    2030   430.6    2124   424.6    2171   428.1    2289   425.5    4018   427.7
    4104   423.1    4171   408.4    5092   408.4    5116     418    5304   413.2
    5651   412.7    5699   388.9    5724   387.9    5749   388.9    5756   396.4
    5798     417    5858   416.2 6370.72  410.07 6466.67     414 6557.84   430.8
#Mann= 7 ,-1,0
   -2500     .07       0    4171     .05       0    5116     .16       0
    5651     .05       0    5798     .16       0    5858     .08       0
6303.859     .03       0
#XS Ineff= 4 ,-1
    1000    4050     450    4104    5116     418    5126    5651   412.7
    5798    6552   414.1
Permanent Ineff=
       F       T       F       F
Bank Sta=5651,5798
XS Rating Curve= 0 ,0
Exp/Cntr=0.3,0.1

Type RM Length L Ch R = 1 ,26342   ,859,1093,450
BEGIN DESCRIPTION:
This cross section corresponds to cross section 26342 of the non-georeferenced CDC model which was the source of this model.
Right Overbank updated with 2007 levee topo.
-------------------------------------
CDC DAL050901-1 B&B Lakes Office Site
Cross-section 26342 - 27249
Located in LOB.
-------------------------------------
Cross-section EF039.  Effective flow limit set at sta 3130 in LOB, at Irving Flood Control District No. 1 (Northwest Levee) in ROB. Conveyance of pond in LOB removed below elev.
END DESCRIPTION:
XS GIS Cut Line= 5
2464108.811545847002673.554848022462033.922093096999854.89669938
2460723.404044846998074.607937132459479.393737586995956.42746222
2458972.972018566995094.14152211
#Sta/Elev= 30
   -2500   435.6    1029   436.4    1070   426.5    1111   423.7    1856   429.4
    1973   426.2    2215   430.6    2488   426.3    2908   428.8    3290   426.5
    3290     420    3384   414.9    3411   408.4    4083   408.4    4117     416
    4211   415.8    4232   412.4    4265   386.9    4290   386.3    4315   387.9
    4335   396.4    4341   406.9    4353   412.6    4566   414.5    5343   414.9
 5361.11     410 5516.57  410.65 5597.79     416 5667.13   431.8 6667.13   431.8
#Mann= 7 ,-1,0
   -2500     .07       0    3411     .05       0    4117     .16       0
    4211     .05       0    4353     .16       0    4566     .08       0
 5516.57     .03       0
#XS Ineff= 4 ,-1
    1000    3130     450    3339    4117     416    4117    4211   415.8
    4353    5657   412.6
Permanent Ineff=
       F       T       F       F
Bank Sta=4211,4353
XS Rating Curve= 0 ,0
Exp/Cntr=0.3,0.1