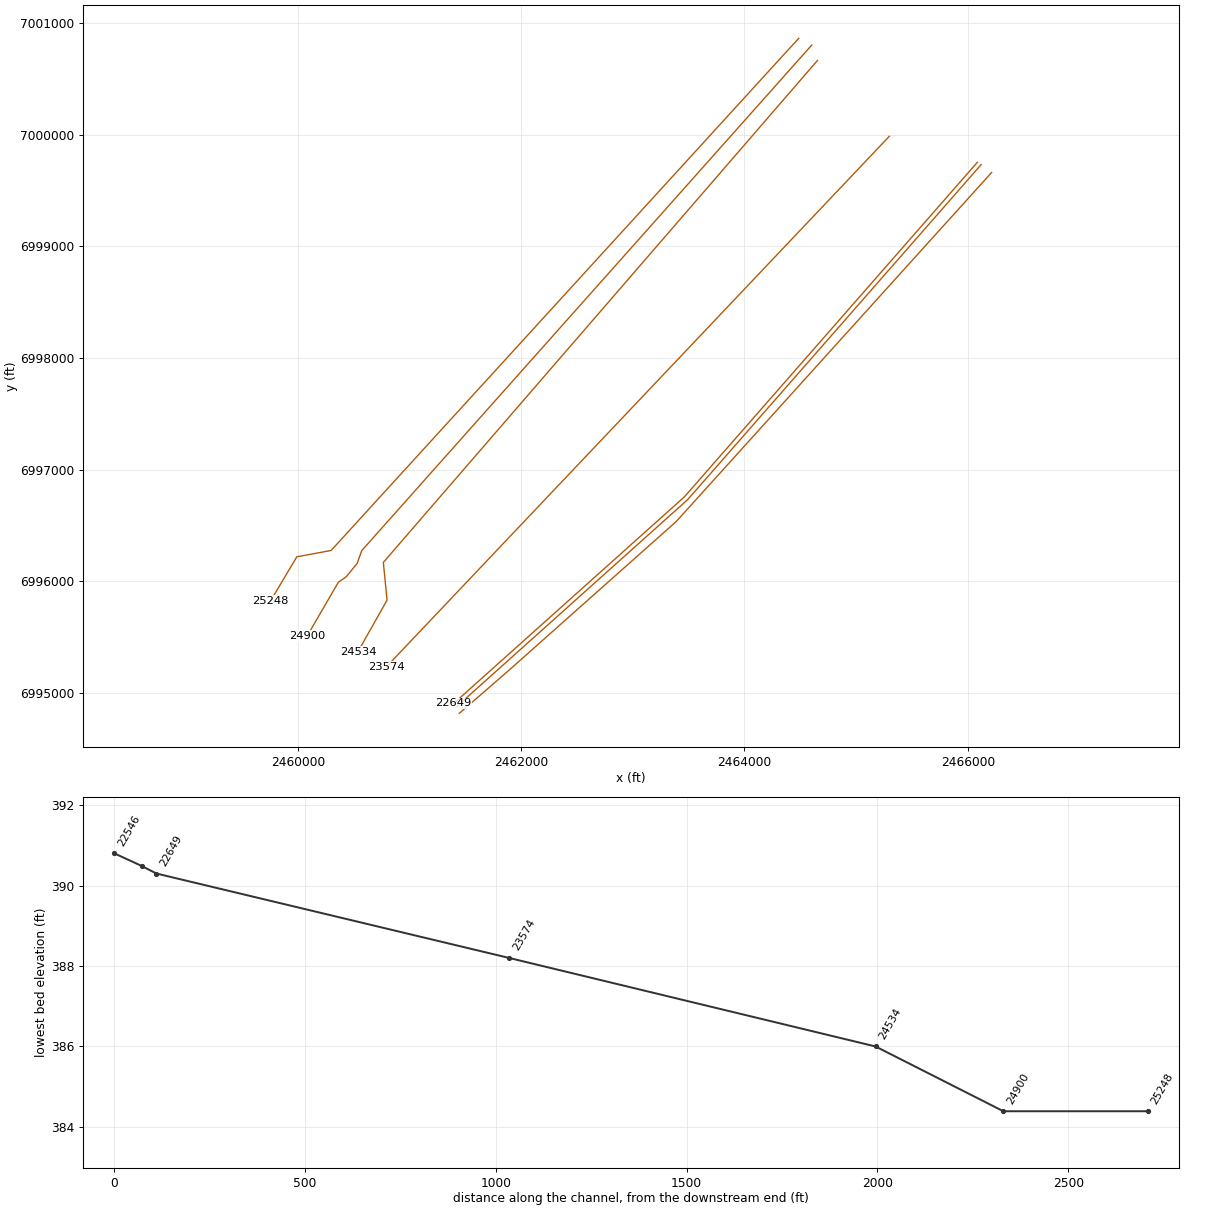
HEC-RAS study CDC_Consolidated_Model.prj: Upper Trinity CDC Consolidated Model

--- CDC_Consolidated_Model.g12 (geometry) --- (continued)

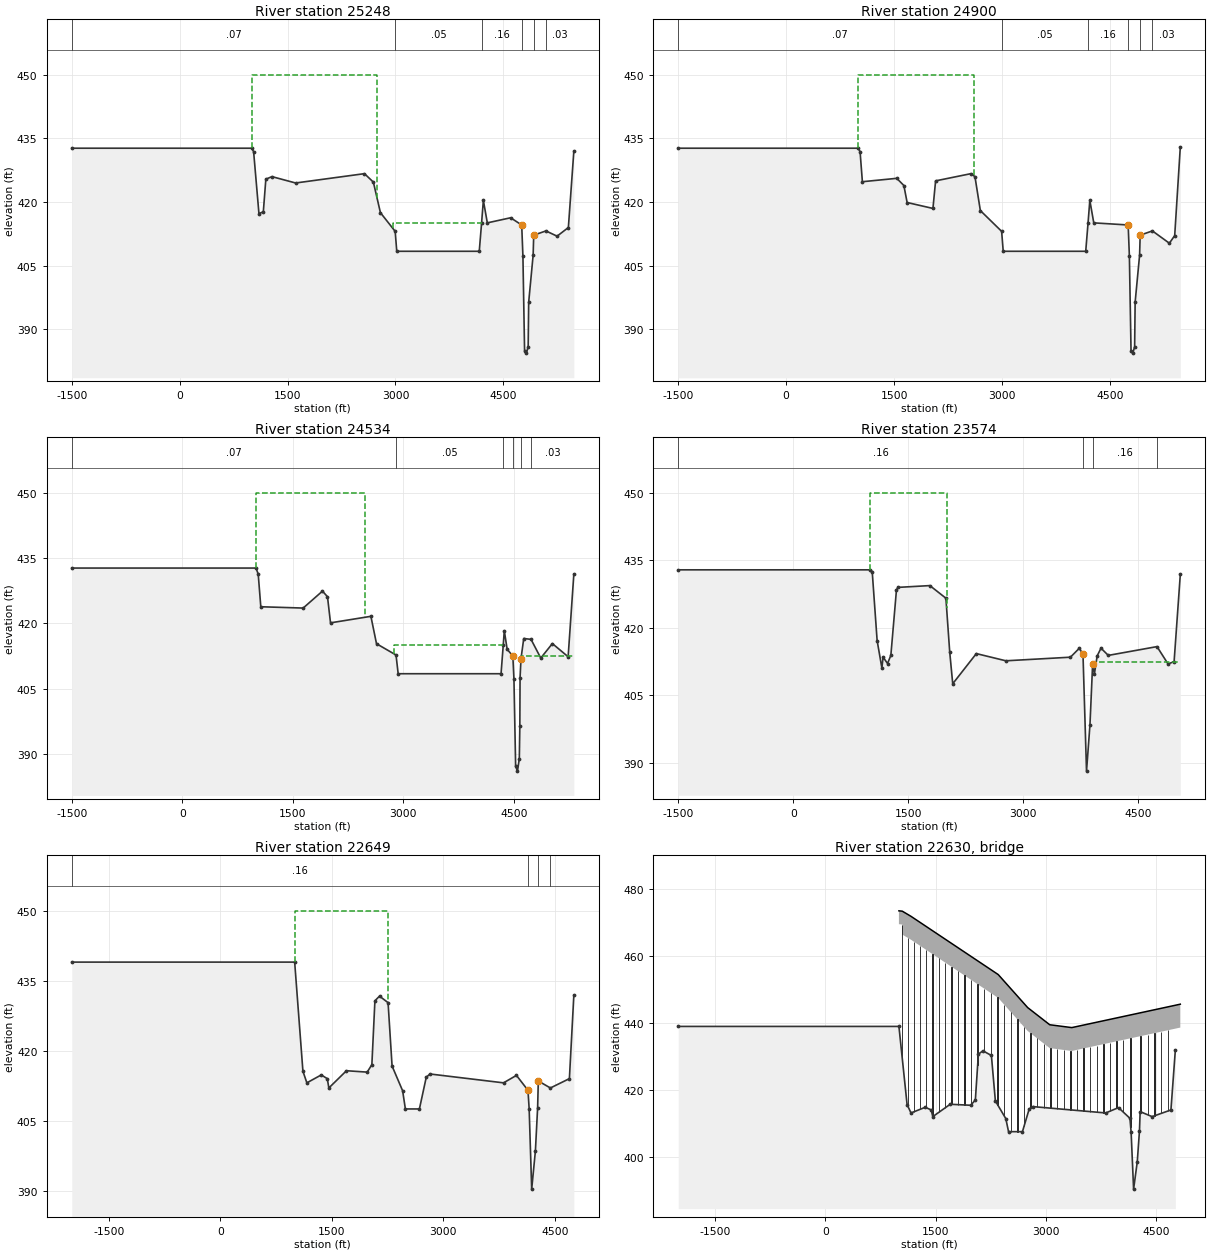
Type RM Length L Ch R = 1 ,25248   ,207,379,483
BEGIN DESCRIPTION:
This cross section corresponds to cross section 25248 of the non-georeferenced CDC model which was the source of this model.
Right Overbank updated with 2007 levee topo.
Cross-section EF038.  Effective flow limit set at sta 2750 in LOB, at Irving Flood Control District No. 1 (Northwest Levee) in ROB.  Daniels Creek removed from conveyance in LOB.  Conveyance of pond in LOB removed below elev. 415.0.  Conveyance removed from low areas in ROB.
Channel data from COD Elm Fork channel survey - cross-section E
END DESCRIPTION:
XS GIS Cut Line= 5
2464485.704832587000863.586858992462800.08821169 6999017.3212748
2460298.195905756996276.984235792459990.87991935 6996220.1969478
2459757.472249696995827.64720796
#Sta/Elev= 30
   -1500   432.7    1000   432.7    1028   431.9    1102   417.3    1163   417.7
    1198   425.4    1283     426    1612   424.5    2569   426.7    2693   424.7
    2791   417.5    2996   413.1    3018   408.4    4165   408.4    4197     415
    4222   420.4    4277   415.1    4601   416.3    4755   414.6    4772   407.2
    4795   384.9    4820  384.39    4845   385.9    4852   396.4    4914   407.5
    4922   412.2    5092   413.2 5246.85  411.96 5403.73     414 5479.87     432
#Mann= 6 ,-1,0
   -1500     .07       0    2996     .05       0    4197     .16       0
    4755     .05       0    4922     .16       0    5092     .03       0
#XS Ineff= 4 ,-1
    1000    2750     450    2959    4197     415    4197    4755   414.6
    4922    5480   412.2
Permanent Ineff=
       F       T       F       F
Bank Sta=4755,4922
XS Rating Curve= 0 ,0
Exp/Cntr=0.3,0.1

Type RM Length L Ch R = 1 ,24900   ,219,335,370
BEGIN DESCRIPTION:
This cross section corresponds to cross section 24900 of the non-georeferenced CDC model which was the source of this model.
END DESCRIPTION:
XS GIS Cut Line= 6
2464602.615385677000803.267097522460572.26064634 6996275.4212468
2460532.298784026996162.557627382460432.175952766996040.07952589
2460363.263032856995992.982179142460084.030323596995511.23478305
#Sta/Elev= 30
   -1500   432.7    1000   432.7    1028   431.9    1060   424.8    1538   425.6
    1637   423.9    1682   419.9    2041   418.5    2078     425    2569   426.7
    2625     426    2700     418    2996   413.1    3018   408.4    4165   408.4
    4197     415    4222   420.4    4277   415.1    4755   414.6    4772   407.2
    4795   384.9    4820  384.39    4845   385.9    4852   396.4    4914   407.5
    4922   412.2    5092   413.2    5328   410.3    5402   412.1    5480     433
#Mann= 6 ,-1,0
   -1500     .07       0    2996     .05       0    4197     .16       0
    4755     .05       0    4922     .16       0    5092     .03       0
#XS Ineff= 4 ,-1
    1000    2615     450    2615    4197     415    4197    4755   414.6
    4922    5480   412.2
Permanent Ineff=
       F       T       F       F
Bank Sta=4755,4922
XS Rating Curve= 0 ,0
Exp/Cntr=0.3,0.1

Type RM Length L Ch R = 1 ,24534   ,740,960,400
BEGIN DESCRIPTION:
This cross section corresponds to cross section 24534 of the non-georeferenced CDC model which was the source of this model.
Right Overbank updated with 2007 levee topo.
---------------------------------------------------------------------
CDC DAL021800-1 DEA Laboratory
Cross-section 24534 - 25248
Located in LOB.
---------------------------------------------------------------------
END DESCRIPTION:
XS GIS Cut Line= 5
2464654.130596817000665.476740062463018.658968756998774.64820372
2460765.848841856996170.092061132460799.252974516995832.71314272
2460538.997917596995370.85087746
#Sta/Elev= 30
   -1500   432.7    1000   432.7    1030   431.3    1065   423.8    1640   423.5
    1902   427.4    1970   426.1    2011   420.1    2559   421.6    2635   415.3
    2900   412.7    2929   408.4    4325   408.4    4355     415    4369   418.3
    4408     414    4485   412.5    4500   407.2    4523   387.1    4548     386
    4573   388.9    4580   396.4    4583   407.5    4596   411.9    4633   416.5
    4732   416.3    4864     412 5021.38  415.33 5235.34   412.3 5312.84  431.32
#Mann= 6 ,-1,0
   -1500     .07       0    2900     .05       0    4355     .16       0
    4485     .05       0    4596     .16       0    4732     .03       0
#XS Ineff= 3 ,-1
    1000    2480     450    2868    4355     415    4596    5307   412.5
Permanent Ineff=
       F       T       F
Bank Sta=4485,4596
XS Rating Curve= 0 ,0
Exp/Cntr=0.3,0.1

Type RM Length L Ch R = 1 ,23574   ,840,925,700
BEGIN DESCRIPTION:
This cross section corresponds to cross section 23574 of the non-georeferenced CDC model which was the source of this model.
Right Overbank updated with 2007 levee topo.
Cross-section EF036.  Approx. 300 feet downstream of right bank of Daniels Creek.  Effective flow limit set at sta 2000 in LOB, at Irving Flood Control District No. 1 Levee (Northwest Levee) in ROB.
Channel data from COD Elm Fork channel survey.
END DESCRIPTION:
XS GIS Cut Line= 3
2465297.408271936999986.549689572463577.522352346998172.16482863
2460792.483631076995234.10246331
#Sta/Elev= 30
   -1500   432.9    1000   432.9    1030   432.5    1094   417.2    1156   411.1
    1172   413.5    1230   412.1    1273   413.9    1346   428.4    1364     429
    1782   429.4    1991   426.6    2041   414.6    2080   407.6    2388   414.3
    2773   412.7    3615   413.5    3732   415.5    3779   414.1    3825   388.2
    3870   398.5    3905   412.1    3928   409.8    3964   413.8    4014   415.5
    4109   413.9  4744.3  415.85 4888.25     412 4967.28  412.51 5048.29   431.9
#Mann= 4 ,-1,0
   -1500     .16       0    3779     .05       0    3905     .16       0
  4744.3     .03       0
#XS Ineff= 3 ,-1
    1000    2000     450    2000    3779   414.1    3905 5048.29   412.5
Permanent Ineff=
       F       F       F
Bank Sta=3779,3905
XS Rating Curve= 0 ,0
Exp/Cntr=0.3,0.1

Type RM Length L Ch R = 1 ,22649   ,39,39,39
BEGIN DESCRIPTION:
This cross section corresponds to cross section 22649 of the non-georeferenced CDC model which was the source of this model.
Right Overbank updated with 2007 levee topo.
Cross-section EF035.  104 feet upstream of S.H. 482/Storey Lane.  Effective
flow limit set at sta 2250 in LOB, at Irving Flood Control District No. 1 Levee (Northwest Levee) in ROB.  Conveyance of pond in LOB removed below
elev. 414.3.
Channel data from COD Elm Fork channel survey.
END DESCRIPTION:
XS GIS Cut Line= 5
2466086.676240926999754.437743742465757.277602466999378.27748935
2464110.284410186997497.476217392463461.233871016996756.28609872
2461396.079208676994906.93809138
#Sta/Elev= 30
   -2000     439    1000     439    1111   415.6    1164   413.1    1358   414.8
    1439     414    1460     412    1697   415.7    1976   415.4    2039     417
    2080   430.7    2142   431.7    2257   430.3    2311   416.7    2453   411.4
    2490   407.5    2679   407.5    2771   414.3    2821     415    3811   413.1
    3985   414.7    4140   411.5    4156   407.5    4190   390.3    4240   398.5
    4270   407.8    4279   413.5 4441.62     412 4697.54     414 4757.38   431.9
#Mann= 4 ,-1,0
   -2000     .16       0    4140     .05       0    4279     .16       0
 4441.62     .03       0
#XS Ineff= 4 ,-1
    1000    2250     450    2250    2771   414.3    2771    4140   411.5
    4279    4766   413.5
Permanent Ineff=
       F       T       F       F
Bank Sta=4140,4279
XS Rating Curve= 0 ,0
Exp/Cntr=0.3,0.1

Type RM Length L Ch R = 3 ,22630   ,,,
BEGIN DESCRIPTION:
DART Northwest Transit Line
END DESCRIPTION:
Node Name=DART Line
Bridge Culvert--1,0,-1,-1, 0
Deck Dist Width WeirC Skew NumUp NumDn MinLoCord MaxHiCord MaxSubmerge Is_Ogee
3,25,2.6,0, 13, 13, , , 0.98, 0, 0,0,,
    1000    1045    1045    1165    1980    2250    2350    2450    2750    3050
    3350    4750    4825
   473.6   473.5   473.5  471.94  459.96  455.99  454.52  452.05  444.64   439.5
  438.65   445.3  445.66
   469.6   469.5   466.5  464.94  452.96  448.99  447.52  445.05  437.64   432.5
  431.65   438.3  438.66
    1000    1045    1045    1165    1980    2250    2350    2450    2750    3050
    3350    4750    4825
   473.6   473.5   473.5  471.94  459.96  455.99  454.52  452.05  444.64   439.5
  438.65   445.3  445.66
   469.6   469.5   466.5  464.94  452.96  448.99  447.52  445.05  437.64   432.5
  431.65   438.3  438.66
Pier Skew, UpSta & Num, DnSta & Num=  ,1045, 2 ,1045, 2 , 0 , 0 , 0 ,,
       5       5
     400     470
       5       5
     400     470
Pier Skew, UpSta & Num, DnSta & Num=  ,1125, 2 ,1125, 2 , 0 , 0 , 0 ,,
       5       5
     400     470
       5       5
     400     470
Pier Skew, UpSta & Num, DnSta & Num=  ,1205, 2 ,1205, 2 , 0 , 0 , 0 ,,
       5       5
     400     465
       5       5
     400     465
Pier Skew, UpSta & Num, DnSta & Num=  ,1285, 2 ,1285, 2 , 0 , 0 , 0 ,,
       5       5
     400     465
       5       5
     400     465
Pier Skew, UpSta & Num, DnSta & Num=  ,1365, 2 ,1365, 2 , 0 , 0 , 0 ,,
       5       5
     400     465
       5       5
     400     465
Pier Skew, UpSta & Num, DnSta & Num=  ,1455, 2 ,1455, 2 , 0 , 0 , 0 ,,
       5       5
     400     465
       5       5
     400     465
Pier Skew, UpSta & Num, DnSta & Num=  ,1545, 2 ,1545, 2 , 0 , 0 , 0 ,,
       5       5
     400     463
       5       5
     400     463
Pier Skew, UpSta & Num, DnSta & Num=  ,1630, 2 ,1630, 2 , 0 , 0 , 0 ,,
       5       5
     400     460
       5       5
     400     460
Pier Skew, UpSta & Num, DnSta & Num=  ,1715, 2 ,1715, 2 , 0 , 0 , 0 ,,
       5       5
     400     460
       5       5
     400     460
Pier Skew, UpSta & Num, DnSta & Num=  ,1800, 2 ,1800, 2 , 0 , 0 , 0 ,,
       5       5
     400     460
       5       5
     400     460
Pier Skew, UpSta & Num, DnSta & Num=  ,1890, 2 ,1890, 2 , 0 , 0 , 0 ,,
       5       5
     400     458
       5       5
     400     458
Pier Skew, UpSta & Num, DnSta & Num=  ,1980, 2 ,1980, 2 , 0 , 0 , 0 ,,
       5       5
     400     455
       5       5
     400     455
Pier Skew, UpSta & Num, DnSta & Num=  ,2070, 2 ,2070, 2 , 0 , 0 , 0 ,,
       5       5
     400     455
       5       5
     400     455
Pier Skew, UpSta & Num, DnSta & Num=  ,2160, 2 ,2160, 2 , 0 , 0 , 0 ,,
       5       5
     400   454.3
       5       5
     400   454.3
Pier Skew, UpSta & Num, DnSta & Num=  ,2250, 2 ,2250, 2 , 0 , 0 , 0 ,,
       5       5
     400   454.3
       5       5
     400   454.3
Pier Skew, UpSta & Num, DnSta & Num=  ,2340, 2 ,2340, 2 , 0 , 0 , 0 ,,
       5       5
     400   454.3
       5       5
     400   454.3
Pier Skew, UpSta & Num, DnSta & Num=  ,2430, 2 ,2430, 2 , 0 , 0 , 0 ,,
       5       5
     400   454.3
       5       5
     400   454.3
Pier Skew, UpSta & Num, DnSta & Num=  ,2520, 2 ,2520, 2 , 0 , 0 , 0 ,,
       5       5
     400   454.3
       5       5
     400   454.3
Pier Skew, UpSta & Num, DnSta & Num=  ,2610, 2 ,2610, 2 , 0 , 0 , 0 ,,
       5       5
     400   454.3
       5       5
     400   454.3
Pier Skew, UpSta & Num, DnSta & Num=  ,2700, 2 ,2700, 2 , 0 , 0 , 0 ,,
       5       5
     400   454.3
       5       5
     400   454.3
Pier Skew, UpSta & Num, DnSta & Num=  ,2790, 2 ,2790, 2 , 0 , 0 , 0 ,,
       5       5
     400   454.3
       5       5
     400   454.3
Pier Skew, UpSta & Num, DnSta & Num=  ,2880, 2 ,2880, 2 , 0 , 0 , 0 ,,
       5       5
     400   454.3
       5       5
     400   454.3
Pier Skew, UpSta & Num, DnSta & Num=  ,2970, 2 ,2970, 2 , 0 , 0 , 0 ,,
       5       5
     400   454.3
       5       5
     400   454.3
Pier Skew, UpSta & Num, DnSta & Num=  ,3060, 2 ,3060, 2 , 0 , 0 , 0 ,,
       5       5
     400   454.3
       5       5
     400   454.3
Pier Skew, UpSta & Num, DnSta & Num=  ,3150, 2 ,3150, 2 , 0 , 0 , 0 ,,
       5       5
     400   454.3
       5       5
     400   454.3
Pier Skew, UpSta & Num, DnSta & Num=  ,3240, 2 ,3240, 2 , 0 , 0 , 0 ,,
       5       5
     400   454.3
       5       5
     400   454.3
Pier Skew, UpSta & Num, DnSta & Num=  ,3330, 2 ,3330, 2 , 0 , 0 , 0 ,,
       5       5
     400   454.3
       5       5
     400   454.3
Pier Skew, UpSta & Num, DnSta & Num=  ,3420, 2 ,3420, 2 , 0 , 0 , 0 ,,
       5       5
     400   454.3
       5       5
     400   454.3
Pier Skew, UpSta & Num, DnSta & Num=  ,3510, 2 ,3510, 2 , 0 , 0 , 0 ,,
       5       5
     400   454.3
       5       5
     400   454.3
Pier Skew, UpSta & Num, DnSta & Num=  ,3600, 2 ,3600, 2 , 0 , 0 , 0 ,,
       5       5
     400   454.3
       5       5
     400   454.3
Pier Skew, UpSta & Num, DnSta & Num=  ,3690, 2 ,3690, 2 , 0 , 0 , 0 ,,
       5       5
     400   454.3
       5       5
     400   454.3
Pier Skew, UpSta & Num, DnSta & Num=  ,3780, 2 ,3780, 2 , 0 , 0 , 0 ,,
       5       5
     400   454.3
       5       5
     400   454.3
Pier Skew, UpSta & Num, DnSta & Num=  ,3870, 2 ,3870, 2 , 0 , 0 , 0 ,,
       5       5
     400   454.3
       5       5
     400   454.3
Pier Skew, UpSta & Num, DnSta & Num=  ,3960, 2 ,3960, 2 , 0 , 0 , 0 ,,
       5       5
     400   454.3
       5       5
     400   454.3
Pier Skew, UpSta & Num, DnSta & Num=  ,4050, 2 ,4050, 2 , 0 , 0 , 0 ,,
       5       5
     400   454.3
       5       5
     400   454.3
Pier Skew, UpSta & Num, DnSta & Num=  ,4150, 2 ,4150, 2 , 0 , 0 , 0 ,,
       5       5
     400   454.3
       5       5
     400   454.3
Pier Skew, UpSta & Num, DnSta & Num=  ,4285, 2 ,4285, 2 , 0 , 0 , 0 ,,
       5       5
     400   454.3
       5       5
     400   454.3
Pier Skew, UpSta & Num, DnSta & Num=  ,4385, 2 ,4385, 2 , 0 , 0 , 0 ,,
       5       5
     400   454.3
       5       5
     400   454.3
Pier Skew, UpSta & Num, DnSta & Num=  ,4475, 2 ,4475, 2 , 0 , 0 , 0 ,,
       5       5
     400   454.3
       5       5
     400   454.3
Pier Skew, UpSta & Num, DnSta & Num=  ,4565, 2 ,4565, 2 , 0 , 0 , 0 ,,
       5       5
     400   454.3
       5       5
     400   454.3
Pier Skew, UpSta & Num, DnSta & Num=  ,4655, 2 ,4655, 2 , 0 , 0 , 0 ,,
       6       6
     400   454.3
       6       6
     400   454.3
BR Coef=-1 , 0 , 0 ,1.05, 0 ,,,0.8,-1,0.5,0,
WSPro=,,,, 1 ,,,, 0 ,,,, 0 ,,,,-1 ,-1 ,-1 , 0 , 0 , 0 , 0 , 0
BC Design=,, 0 ,, 0 ,,,,,,
BC Use User HTab Curves=0
BC User HTab FreeFlow(D)= 0

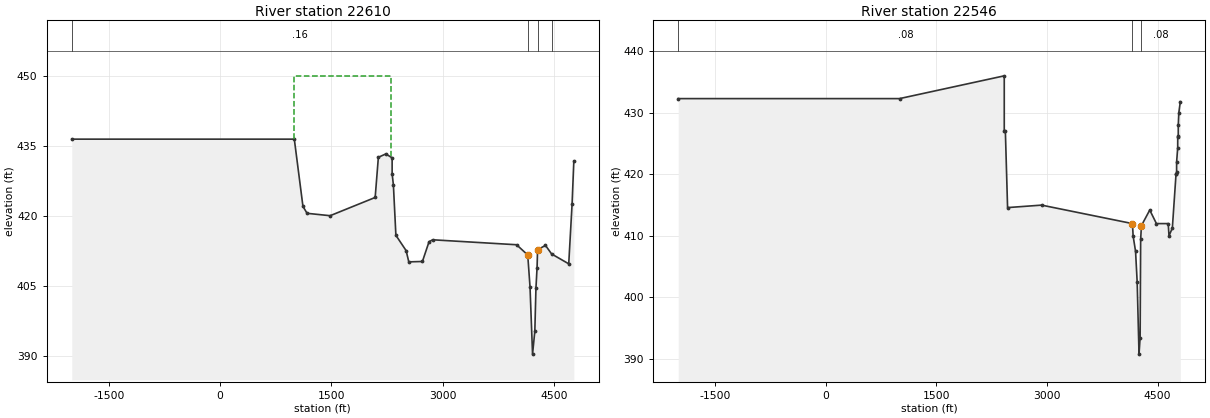
Type RM Length L Ch R = 1 ,22610   ,71,71,71
BEGIN DESCRIPTION:
This cross section corresponds to cross section 22610 of the non-georeferenced CDC model which was the source of this model.
---------------------------------------------------------------------
CDC IRV110308-01 DART Northwest Corridor Light Rail Transit Line
Cross-section 22610 - 22649
---------------------------------------------------------------------
Interpolated cross-section.
END DESCRIPTION:
XS GIS Cut Line= 5
2466120.054379636999733.089409342465790.594566196999356.98273388
  2464143.2954996997476.449356562463492.124229166996733.08142072
2461421.602779696994877.96209946
#Sta/Elev= 30
   -2000  436.46    1000  436.46 1116.45  422.08 1172.05   420.6 1482.59  420.09
 2090.01  423.99 2133.03  432.58 2233.74   433.3 2318.72  432.46 2318.72  429.05
 2335.58   426.7 2369.31   415.9 2507.31  412.62 2543.27  410.22 2726.95   410.3
 2816.36  414.53 2864.95  414.94 3996.18  413.88 4146.82  411.69 4177.38  404.88
 4211.58  390.49 4242.44  395.43 4257.43  404.61 4272.51  409.01 4279.36  412.81
 4386.06  413.74 4468.68  411.91 4699.39   409.8 4744.46  422.56 4768.27  431.82
#Mann= 4 ,-1,0
   -2000     .16       0 4146.82     .05       0 4279.36     .16       0
 4468.68     .03       0
#XS Ineff= 4 ,-1
    1000    2310     450    2310    3000   414.3    3000 4146.82   411.5
 4279.36    4720   412.8
Permanent Ineff=
       F       T       F       F
Bank Sta=4146.82,4279.36
XS Rating Curve= 0 ,0
Exp/Cntr=0.3,0.1

Type RM Length L Ch R = 1 ,22546   ,89,89,89
BEGIN DESCRIPTION:
This cross section corresponds to cross section 22546 of the non-georeferenced CDC model which was the source of this model.
One-foot upstream of SH 82/Storey Lane.
END DESCRIPTION:
XS GIS Cut Line= 6
2466213.721526016999662.195220132465878.501442316999291.21342073
2464202.401023836997436.304423722463389.522072176996536.70648538
2461876.051345836995191.109439052461446.075827846994818.12560497
#Sta/Elev= 30
   -2000   432.3    1000   432.3    2420     436    2420     427    2435     427
    2465   414.6  2926.5     415    4158     412    4167     410    4200   407.5
    4222   402.5    4247   390.8    4262   393.5 4269.29 409.451 4279.95  411.68
  4392.5   414.2    4483     412 4643.02     412 4653.38     410 4698.89  411.28
  4748.5     420 4754.97     420 4756.57  420.43 4756.78     422 4771.52  424.33
  4771.8     426 4779.01  426.21 4779.25     428 4786.48     430 4806.81   431.8
#Mann= 3 ,0,0
   -2000     .08       0    4158     .05       0 4279.95     .08       0
#XS Ineff= 2 , 0
            4158     412 4279.95          411.68
Permanent Ineff=
       F       F
Bank Sta=4158,4279.95
XS Rating Curve= 0 ,0
Exp/Cntr=0.5,0.3