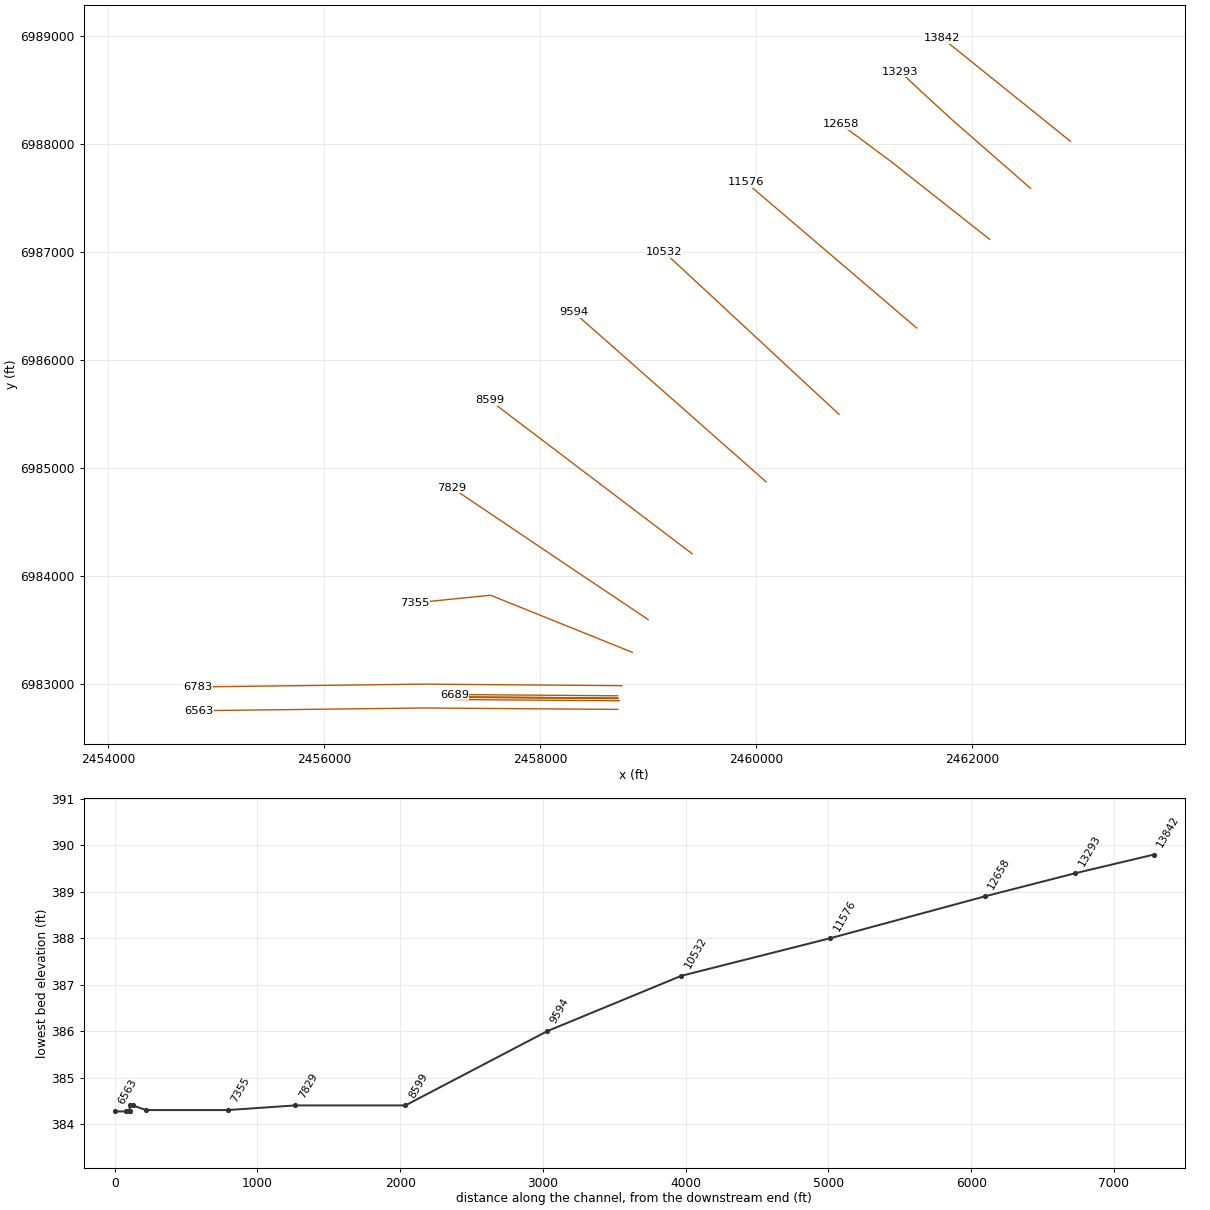
HEC-RAS study CDC_Consolidated_Model.prj: Upper Trinity CDC Consolidated Model

--- CDC_Consolidated_Model.g12 (geometry) --- (continued)

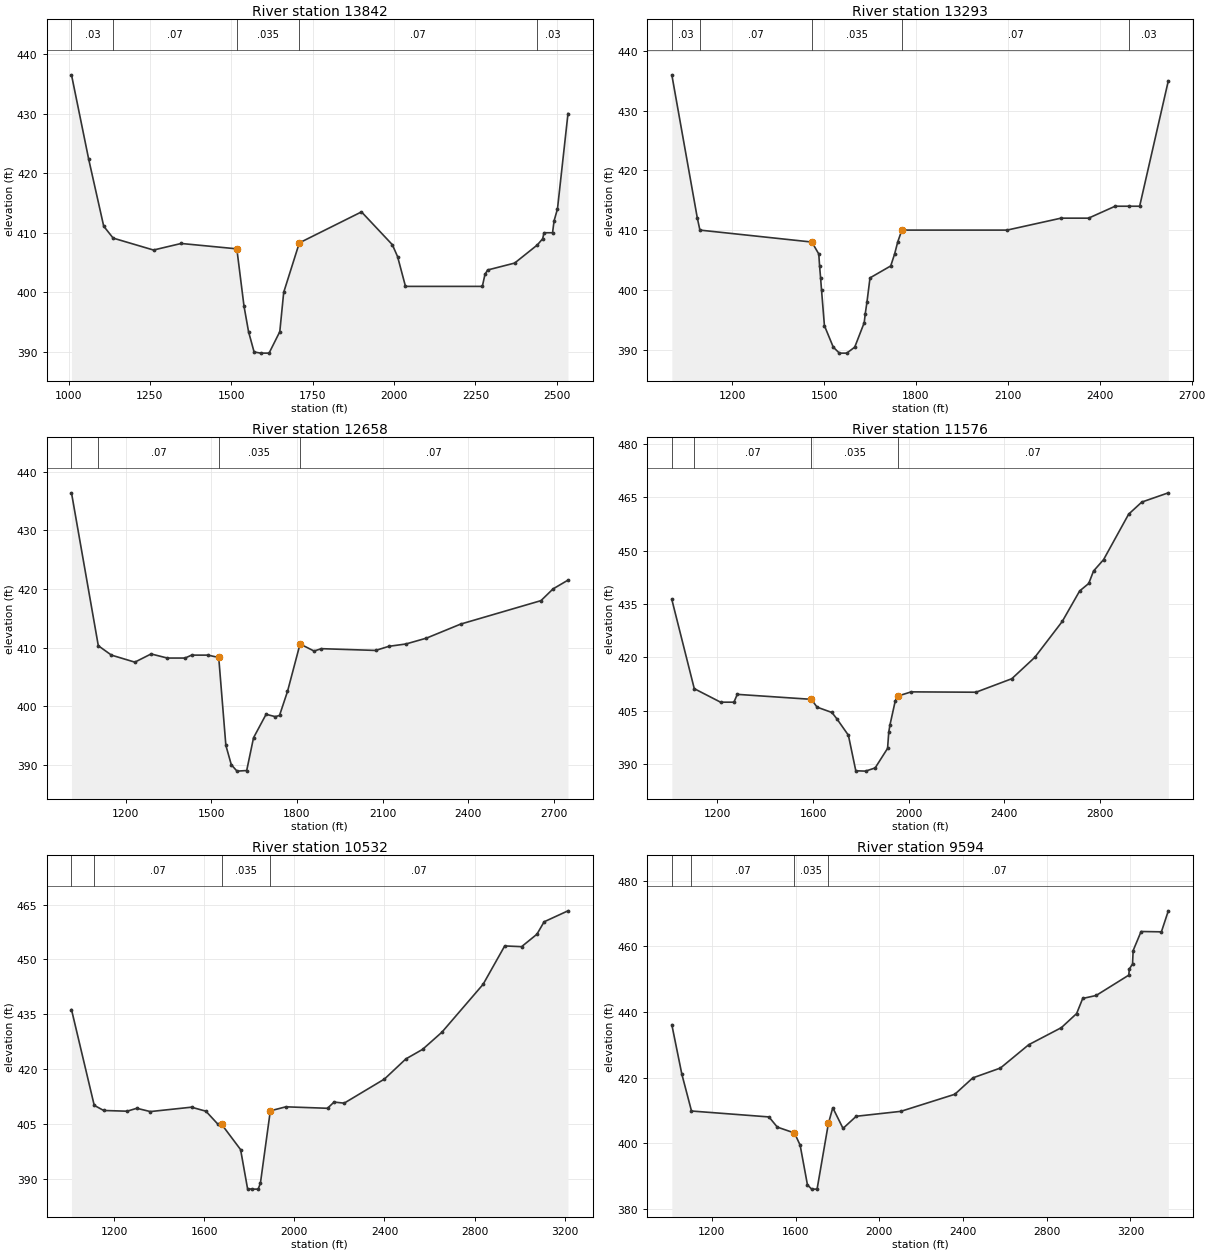
Type RM Length L Ch R = 1 ,13842   ,549,549,549
BEGIN DESCRIPTION:
This cross section corresponds to cross section 13842 of the non-georeferenced CDC model which was the source of this model.
Proposed grading for borrow pit and levee overbank.
Right Overbank updated with 2007 levee topo and borrow pit topography.
Cross-section EF018.  Effective flow limit set at East Levee in LOB, at Irving Flood Control District No. 1 Levee (Northwest Levee) in ROB. Ground points from sta 1932 - 2523 generated from topographic file.
Channel data from COD Elm Fork channel survey.
END DESCRIPTION:
XS GIS Cut Line= 3
2462910.786153026988022.569970382461838.411001186988885.75492381
2461721.155330186988977.40172213
#Sta/Elev= 30
    1009   436.5    1062   422.3    1108   411.1    1137   409.1    1261   407.1
    1346   408.2    1517   407.3    1539   397.7    1553   393.4    1570     390
    1590   389.8    1616   389.8    1649   393.4    1661     400    1709   408.3
    1900   413.5 1994.69     408 2010.86     406 2035.18     401 2271.31     401
 2279.31     403 2287.52  403.75 2370.51  404.91 2439.99  407.94 2456.71     409
 2460.72     410    2487     410 2491.72     412 2502.14     414 2534.44     430
#Mann= 5 ,-1,0
    1009     .03       0    1137     .07       0    1517    .035       0
    1709     .07       0 2439.99     .03       0
#XS Ineff= 2 , 0
            1517   407.3    1709           408.3
Permanent Ineff=
       F       F
Bank Sta=1517,1709
XS Rating Curve= 0 ,0
Exp/Cntr=0.3,0.1

Type RM Length L Ch R = 1 ,13293   ,600,635,650
BEGIN DESCRIPTION:
This cross section corresponds to cross section 13293 of the non-georeferenced CDC model which was the source of this model.
Proposed grading  levee tie-in overbank.
Right Overbank updated with 2007 levee topo.
---------------------------------------------------
CDC IRVING 082109-1 NORTHWEST LEVEE SEEPAGE CONTROL
CROSS-SECTION 13293 - 55400  DOWNSTREAM END
---------------------------------------------------
Cross-section generated from topographic file.  Effective flow limit set at East Levee in LO
END DESCRIPTION:
XS GIS Cut Line= 4
2462540.637615086987587.919592962461807.831009846988228.12894246
 2461524.97199556988488.02901322  2461332.8680496988668.20056888
#Sta/Elev= 28
    1003     436  1086.3     412  1094.7     410    1460     408  1482.7     406
  1485.3     404  1488.6     402  1491.6     400  1501.1     394    1530   390.4
    1550   389.4    1574   389.4    1600   390.4    1631   394.5  1634.4     396
  1640.1     398  1649.9     402  1717.5     404  1730.2     406  1740.3     408
  1753.8     410  2097.3     410  2273.3     412  2363.2     412    2450     414
  2495.3     414 2530.02     414 2623.58     435
#Mann= 5 ,-1,0
    1003     .03       0  1094.7     .07       0    1460    .035       0
  1753.8     .07       0  2495.3     .03       0
#XS Ineff= 2 , 0
            1460     408  1753.8             410
Permanent Ineff=
       F       F
Bank Sta=1460,1753.8
XS Rating Curve= 0 ,0
Exp/Cntr=0.3,0.1

Type RM Length L Ch R = 1 ,12658   ,1050,1082,1010
BEGIN DESCRIPTION:
This cross section corresponds to cross section 12658 of the non-georeferenced CDC model which was the source of this model.
Cross-section EF017.  Effective flow limit set at East Levee in LOB, at sta 2750 in ROB.  Ground points from sta 2166 - 2750 generated from topographic file.
Channel data from COD Elm Fork channel survey.
END DESCRIPTION:
XS GIS Cut Line= 3
2462161.249594336987116.51174313  2461254.5060016987831.98898672
2460785.060417596988181.00370863
#Sta/Elev= 30
    1010   436.4    1104   410.3    1150   408.7    1232   407.5    1289   408.9
    1346   408.2    1408   408.2    1431   408.7    1488   408.7    1526   408.3
    1551   393.3    1570     390    1590   388.9    1624     389    1648   394.6
    1692   398.6    1724   398.2    1739   398.4    1767   402.5    1811   410.6
    1860   409.4    1886   409.8    2076   409.5    2122   410.2    2182   410.6
    2254   411.6  2374.1     414  2655.3     418  2697.6     420    2750   421.5
#Mann= 4 ,-1,0
    1010     .03       0    1104     .07       0    1526    .035       0
    1811     .07       0
#XS Ineff= 2 , 0
            1526   408.3    1811           410.6
Permanent Ineff=
       F       F
Bank Sta=1526,1811
XS Rating Curve= 0 ,0
Exp/Cntr=0.3,0.1

Type RM Length L Ch R = 1 ,11576   ,1050,1044,1030
BEGIN DESCRIPTION:
This cross section corresponds to cross section 11576 of the non-georeferenced CDC model which was the source of this model.
Cross-section EF016.  Effective flow limit set at East Levee in LOB. Channel data from COD Elm Fork channel survey.
END DESCRIPTION:
XS GIS Cut Line= 2
2461487.142018686986294.703347382459906.435206326987643.57335305
#Sta/Elev= 30
    1009   436.3    1103   411.2    1213   407.4    1269   407.4    1283   409.6
    1593   408.2    1617     406    1679   404.5    1700   402.7    1748   398.1
    1779   388.1    1820     388    1860   388.9    1912   394.4    1917     399
    1922     401    1944   407.7    1954   409.1    2011   410.3    2282   410.2
    2432     414    2528     420    2643   430.1    2716   438.7    2754   440.8
    2774   444.3    2816   447.5    2921   460.3    2976   463.7    3087   466.3
#Mann= 4 ,-1,0
    1009     .03       0    1103     .07       0    1593    .035       0
    1954     .07       0
#XS Ineff= 2 , 0
            1593   408.2    1954           409.1
Permanent Ineff=
       F       F
Bank Sta=1593,1954
XS Rating Curve= 0 ,0
Exp/Cntr=0.3,0.1

Type RM Length L Ch R = 1 ,10532   ,920,938,940
BEGIN DESCRIPTION:
This cross section corresponds to cross section 10532 of the non-georeferenced CDC model which was the source of this model.
Cross-section EF015.  Effective flow limit set at East Levee in LOB. Channel data from COD Elm Fork channel survey - cross-section EF#015 surveyed February 1994.
END DESCRIPTION:
XS GIS Cut Line= 2
2460767.921344256985495.784669642459151.808106666986995.85253564
#Sta/Elev= 30
    1010   436.3    1111   410.1    1153   408.7    1257   408.5    1300   409.3
    1360   408.4    1543   409.6    1607   408.5    1661   404.9    1677   404.9
    1761     398    1792   387.3    1812  387.19    1839  387.19    1849   388.8
    1893   408.6    1962   409.7    2147   409.3    2176     411    2221   410.7
    2400   417.3    2495   422.8    2569   425.4    2655   430.1    2838   443.2
    2934   453.7    3009   453.5    3077   456.9    3109   460.3    3215   463.3
#Mann= 4 ,-1,0
    1010     .03       0    1111     .07       0    1677    .035       0
    1893     .07       0
#XS Ineff= 2 , 0
            1677   404.9    1893           408.6
Permanent Ineff=
       F       F
Bank Sta=1677,1893
XS Rating Curve= 0 ,0
Exp/Cntr=0.3,0.1

Type RM Length L Ch R = 1 ,9594    ,960,995,1010
BEGIN DESCRIPTION:
This cross section corresponds to cross section 9594 of the non-georeferenced CDC model which was the source of this model.
Cross-section EF014.  Effective flow limit set at East Levee in LOB. Channel data from COD Elm Fork channel survey.
END DESCRIPTION:
XS GIS Cut Line= 2
2460092.000123926984872.393856052458312.975794856986441.29688622
#Sta/Elev= 30
    1009   436.1    1057     421    1103   409.8    1473     408    1513   404.9
    1595   403.1    1622   399.4    1657   387.3    1677     386    1703     386
    1757     406    1778   410.8    1827   404.5    1890   408.2    2103   409.7
    2361   414.9    2447   419.9    2579   422.9    2714     430    2870   435.2
    2943   439.5    2972   444.1    3036     445    3192   451.2    3195   453.1
    3210   454.6    3213   458.7    3251   464.5    3348   464.4    3381   470.8
#Mann= 4 ,-1,0
    1009     .03       0    1103     .07       0    1595    .035       0
    1757     .07       0
#XS Ineff= 2 , 0
            1595   403.1    1757             406
Permanent Ineff=
       F       F
Bank Sta=1595,1757
XS Rating Curve= 0 ,0
Exp/Cntr=0.3,0.1

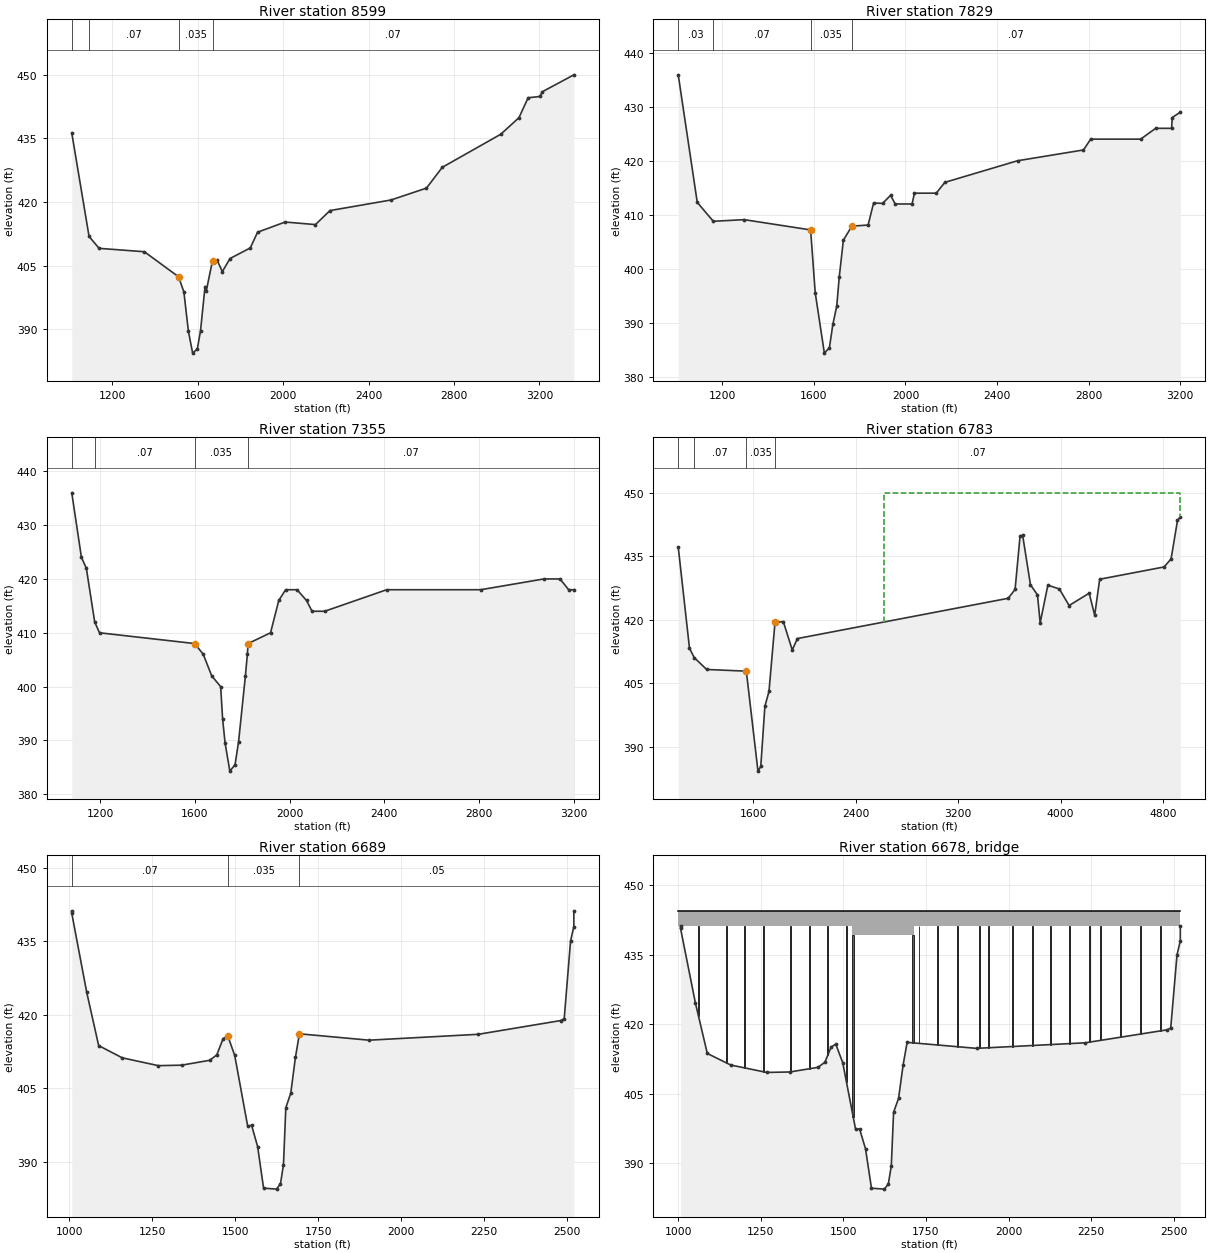
Type RM Length L Ch R = 1 ,8599    ,771,771,781
BEGIN DESCRIPTION:
This cross section corresponds to cross section 8599 of the non-georeferenced CDC model which was the source of this model.
Cross-section EF013.  Effective flow limit set at East Levee in LOB. Channel data from COD Elm Fork channel survey - cross-section EF#013 surveyed February 1994.
END DESCRIPTION:
XS GIS Cut Line= 2
2459408.411924186984205.746239222457535.091851926985626.25914621
#Sta/Elev= 30
    1010   436.3    1091   411.9    1138   409.1    1350   408.3    1510   402.4
    1535   398.8    1556   389.6    1576   384.4    1598   385.4    1613   389.7
    1634   400.1    1640   399.1    1669   406.2    1690   406.4    1715   403.6
    1751   406.7    1846   409.2    1880   412.9    2009   415.3    2151   414.7
    2219     418    2505   420.5    2671   423.3    2745   428.2    3019     436
    3104   439.9    3147   444.6    3203   444.9    3213     446    3361     450
#Mann= 4 ,-1,0
    1010     .03       0    1091     .07       0    1510    .035       0
    1669     .07       0
#XS Ineff= 2 , 0
            1510   402.4    1669           406.2
Permanent Ineff=
       F       F
Bank Sta=1510,1669
XS Rating Curve= 0 ,0
Exp/Cntr=0.3,0.1

Type RM Length L Ch R = 1 ,7829    ,400,474,550
BEGIN DESCRIPTION:
This cross section corresponds to cross section 7829 of the non-georeferenced CDC model which was the source of this model.
Cross-section EF012.  Effective flow limit set at East Levee in LOB, at sta 3200 in ROB.  Ground points from sta 1890 - 3200 generated from topographic file.  Trib in ROB removed from conveyance.
Channel data from COD Elm Fork channel survey.
END DESCRIPTION:
XS GIS Cut Line= 3
 2459001.38485116983596.003364222458263.860079416984090.38918647
2457182.069592096984818.68530205
#Sta/Elev= 30
    1008   435.9    1091   412.3    1161   408.8    1296   409.1    1586   407.2
    1606   395.6    1646   384.4    1668   385.4    1683   389.7    1700   393.1
    1711   398.5    1729   405.3    1766   407.9    1837   408.1    1861   412.2
    1900   412.1    1935   413.6  1955.4     412  2028.8     412  2039.3     414
  2134.3     414    2172     416  2489.4     420  2777.3     422  2808.8     424
  3026.8     424  3092.4     426  3161.9     426  3164.9     428    3200     429
#Mann= 4 ,-1,0
    1008     .03       0    1161     .07       0    1586    .035       0
    1766     .07       0
#XS Ineff= 2 , 0
            1586   407.2    1766           407.9
Permanent Ineff=
       F       F
Bank Sta=1586,1766
XS Rating Curve= 0 ,0
Exp/Cntr=0.3,0.1

Type RM Length L Ch R = 1 ,7355    ,459,571,659
BEGIN DESCRIPTION:
This cross section corresponds to cross section 7355 of the non-georeferenced CDC model which was the source of this model.
Cross-section generated from topographic file.  Effective flow limit set at East Levee in LOB, at sta 3200 in ROB.
Channel data from COD Elm Fork channel survey.
END DESCRIPTION:
XS GIS Cut Line= 3
2458855.041311746983293.112237722457542.564934076983821.59313613
2456841.794025936983750.99124321
#Sta/Elev= 30
  1080.8     436  1121.6     424  1142.3     422  1177.6     412  1197.9     410
  1599.4     408  1635.8     406  1671.5     402  1709.2     400  1717.5     394
    1728   389.5    1748   384.3    1770   385.5    1785   389.8  1813.7     402
  1821.9     406  1825.1     408  1919.8     410  1954.5     416  1983.5     418
  2031.6     418  2071.6     416    2095     414  2148.4     414    2410     418
    2807     418  3073.2     420  3141.9     420    3178     418    3200     418
#Mann= 4 ,-1,0
  1080.8     .03       0  1177.6     .07       0  1599.4    .035       0
  1825.1     .07       0
#XS Ineff= 2 , 0
          1599.4     408  1825.1             408
Permanent Ineff=
       F       F
Bank Sta=1599.4,1825.1
XS Rating Curve= 0 ,0
Exp/Cntr=0.3,0.1

Type RM Length L Ch R = 1 ,6783    ,94,94,94
BEGIN DESCRIPTION:
This cross section corresponds to cross section 6783 of the non-georeferenced CDC model which was the source of this model.
Cross-section EF011.  95 feet upstream of Chicago, Rock Island, and Pacific Railroad.  Effective flow limit set at East Levee in LOB, at sta 2620 in ROB. Trinity View Park in ROB.  Channel data from COD Elm Fork channel survey.
END DESCRIPTION:
XS GIS Cut Line= 3
   2458757.294466982984.653865132456925.549107766982998.84707822
2454834.508670426982973.04332405
#Sta/Elev= 30
    1012   437.2    1100   413.3    1137   411.1    1234   408.3    1544   407.9
    1635   384.3    1657   385.4    1689   399.6    1721   403.1    1768   419.4
    1833   419.6    1903   412.9    1943   415.6    3590   425.1    3644   427.2
    3683   439.8    3703     440    3764   428.3    3819   425.9    3840   419.3
    3900   428.2    3990   427.3    4066   423.4    4223   426.3    4266   421.1
    4305   429.6    4808   432.5    4863   434.4    4913   443.5    4935   444.2
#Mann= 4 ,-1,0
    1012     .03       0    1137     .07       0    1544    .035       0
    1768     .07       0
#XS Ineff= 3 ,-1
    1012    1544   407.9    1768    2620   419.4    2620    4935     450
Permanent Ineff=
       F       F       F
Bank Sta=1544,1768
XS Rating Curve= 0 ,0
Exp/Cntr=0.3,0.1

Type RM Length L Ch R = 1 ,6689    ,21,21,21
BEGIN DESCRIPTION:
This cross section corresponds to cross section 6689 of the non-georeferenced CDC model which was the source of this model.
END DESCRIPTION:
XS GIS Cut Line= 2
2458719.499916176982890.94670346 2457206.54756156982902.34070955
#Sta/Elev= 30
    1007   441.2    1007   440.7    1052  424.59    1088   413.7    1159   411.2
    1268   409.6    1338   409.7    1423   410.7    1444   411.8    1463   415.1
    1477   415.7    1498   411.7    1537   397.3    1549   397.4    1567   393.1
    1585   384.6    1624   384.4    1636   385.5    1645   389.4    1652     401
    1667     404    1681   411.3    1693   416.1    1903   414.8    2232     416
    2480   418.8    2491   419.2    2510     435    2520     438    2520   441.2
#Mann= 3 ,0,0
    1007     .07       0    1477    .035       0    1693     .05       0
#XS Ineff= 2 , 0
            1477   415.7    1693           416.1
Permanent Ineff=
       F       F
Bank Sta=1477,1693
XS Rating Curve= 0 ,0
Exp/Cntr=0.5,0.3

Type RM Length L Ch R = 3 ,6678    ,,,
BEGIN DESCRIPTION:
Burlington Northern Sante Fe Railroad
END DESCRIPTION:
Node Name=BNSF RR
Bridge Culvert--1,0,-1,-1, 0
Deck Dist Width WeirC Skew NumUp NumDn MinLoCord MaxHiCord MaxSubmerge Is_Ogee
1,19,2.6,0, 52, 52, , , 0.95, 0, 0,0,,
    1000    1048    1052    1146    1154    1296    1304    1348    1352    1398
    1402    1448    1452  1489.5  1490.5  1519.5  1526.5  1526.5  1533.5    1620
  1706.5  1713.5  1713.5  1724.5  1725.5  1739.5  1740.5    1788    1792    1848
    1852    1898    1902    1958    1962    1998    2002    2048    2052    2148
    2152    2256    2264    2298    2302    2426    2434    2468    2472    2489
    2491    2520
   444.5   444.5   444.5   444.5   444.5   444.5   444.5   444.5   444.5   444.5
   444.5   444.5   444.5   444.5   444.5   444.5   444.5   444.5   444.5   444.5
   444.5   444.5   444.5   444.5   444.5   444.5   444.5   444.5   444.5   444.5
   444.5   444.5   444.5   444.5   444.5   444.5   444.5   444.5   444.5   444.5
   444.5   444.5   444.5   444.5   444.5   444.5   444.5   444.5   444.5   444.5
   444.5   444.5
   441.2   441.2   441.2   441.2   441.2   441.2   441.2   441.2   441.2   441.2
   441.2   441.2   441.2   441.2   441.2   441.2   441.2   439.3   439.3   439.3
   439.3   439.3   441.2   441.2   441.2   441.2   441.2   441.2   441.2   441.2
   441.2   441.2   441.2   441.2   441.2   441.2   441.2   441.2   441.2   441.2
   441.2   441.2   441.2   441.2   441.2   441.2   441.2   441.2   441.2   441.2
   441.2   441.2
    1000    1048    1052    1146    1154    1296    1304    1348    1352    1398
    1402    1448    1452  1489.5  1490.5  1519.5  1526.5  1526.5  1533.5    1620
  1706.5  1713.5  1713.5  1724.5  1725.5  1739.5  1740.5    1788    1792    1848
    1852    1898    1902    1958    1962    1998    2002    2048    2052    2148
    2152    2256    2264    2298    2302    2426    2434    2468    2472    2489
    2491    2520
   444.5   444.5   444.5   444.5   444.5   444.5   444.5   444.5   444.5   444.5
   444.5   444.5   444.5   444.5   444.5   444.5   444.5   444.5   444.5   444.5
   444.5   444.5   444.5   444.5   444.5   444.5   444.5   444.5   444.5   444.5
   444.5   444.5   444.5   444.5   444.5   444.5   444.5   444.5   444.5   444.5
   444.5   444.5   444.5   444.5   444.5   444.5   444.5   444.5   444.5   444.5
   444.5   444.5
   441.2   441.2   441.2   441.2   441.2   441.2   441.2   441.2   441.2   441.2
   441.2   441.2   441.2   441.2   441.2   441.2   441.2   439.3   439.3   439.3
   439.3   439.3   441.2   441.2   441.2   441.2   441.2   441.2   441.2   441.2
   441.2   441.2   441.2   441.2   441.2   441.2   441.2   441.2   441.2   441.2
   441.2   441.2   441.2   441.2   441.2   441.2   441.2   441.2   441.2   441.2
   441.2   441.2
Pier Skew, UpSta & Num, DnSta & Num=  ,1061, 2 ,1061, 2 , 0 , 0 , 0 ,,
     3.5     3.5
       0     442
     3.5     3.5
       0     442
Pier Skew, UpSta & Num, DnSta & Num=  ,1145, 2 ,1145, 2 , 0 , 0 , 0 ,,
     3.5     3.5
       0     442
     3.5     3.5
       0     442
Pier Skew, UpSta & Num, DnSta & Num=  ,1201, 2 ,1201, 2 , 0 , 0 , 0 ,,
    2.34    2.34
       0     442
    2.34    2.34
       0     442
Pier Skew, UpSta & Num, DnSta & Num=  ,1257, 2 ,1257, 2 , 0 , 0 , 0 ,,
     3.5     3.5
       0     442
     3.5     3.5
       0     442
Pier Skew, UpSta & Num, DnSta & Num=  ,1341, 2 ,1341, 2 , 0 , 0 , 0 ,,
     3.5     3.5
       0     442
     3.5     3.5
       0     442
Pier Skew, UpSta & Num, DnSta & Num=  ,1397, 2 ,1397, 2 , 0 , 0 , 0 ,,
    2.34    2.34
       0     442
    2.34    2.34
       0     442
Pier Skew, UpSta & Num, DnSta & Num=  ,1453, 2 ,1453, 2 , 0 , 0 , 0 ,,
     3.5     3.5
       0     442
     3.5     3.5
       0     442
Pier Skew, UpSta & Num, DnSta & Num=  ,1509, 2 ,1509, 2 , 0 , 0 , 0 ,,
    1.17    1.17
       0     442
    1.17    1.17
       0     442
Pier Skew, UpSta & Num, DnSta & Num=  ,1530, 2 ,1530, 2 , 0 , 0 , 0 ,,
       7       7
       0     442
       7       7
       0     442
Pier Skew, UpSta & Num, DnSta & Num=  ,1710, 2 ,1710, 2 , 0 , 0 , 0 ,,
       7       7
       0     442
       7       7
       0     442
Pier Skew, UpSta & Num, DnSta & Num=  ,1728, 2 ,1728, 2 , 0 , 0 , 0 ,,
    1.17    1.17
       0     442
    1.17    1.17
       0     442
Pier Skew, UpSta & Num, DnSta & Num=  ,1784, 2 ,1784, 2 , 0 , 0 , 0 ,,
     3.5     3.5
       0     442
     3.5     3.5
       0     442
Pier Skew, UpSta & Num, DnSta & Num=  ,1845, 2 ,1845, 2 , 0 , 0 , 0 ,,
    2.34    2.34
       0     442
    2.34    2.34
       0     442
Pier Skew, UpSta & Num, DnSta & Num=  ,1911, 2 ,1911, 2 , 0 , 0 , 0 ,,
    2.34    2.34
       0     442
    2.34    2.34
       0     442
Pier Skew, UpSta & Num, DnSta & Num=  ,1939, 2 ,1939, 2 , 0 , 0 , 0 ,,
    2.34    2.34
       0     442
    2.34    2.34
       0     442
Pier Skew, UpSta & Num, DnSta & Num=  ,2011, 2 ,2011, 2 , 0 , 0 , 0 ,,
    2.34    2.34
       0     442
    2.34    2.34
       0     442
Pier Skew, UpSta & Num, DnSta & Num=  ,2072, 2 ,2072, 2 , 0 , 0 , 0 ,,
     3.5     3.5
       0     442
     3.5     3.5
       0     442
Pier Skew, UpSta & Num, DnSta & Num=  ,2128, 2 ,2128, 2 , 0 , 0 , 0 ,,
    2.34    2.34
       0     442
    2.34    2.34
       0     442
Pier Skew, UpSta & Num, DnSta & Num=  ,2184, 2 ,2184, 2 , 0 , 0 , 0 ,,
    2.34    2.34
       0     442
    2.34    2.34
       0     442
Pier Skew, UpSta & Num, DnSta & Num=  ,2245, 2 ,2245, 2 , 0 , 0 , 0 ,,
    2.34    2.34
       0     442
    2.34    2.34
       0     442
Pier Skew, UpSta & Num, DnSta & Num=  ,2278, 2 ,2278, 2 , 0 , 0 , 0 ,,
    2.34    2.34
       0     442
    2.34    2.34
       0     442
Pier Skew, UpSta & Num, DnSta & Num=  ,2339, 2 ,2339, 2 , 0 , 0 , 0 ,,
    2.34    2.34
       0     442
    2.34    2.34
       0     442
Pier Skew, UpSta & Num, DnSta & Num=  ,2400, 2 ,2400, 2 , 0 , 0 , 0 ,,
    2.34    2.34
       0     442
    2.34    2.34
       0     442
Pier Skew, UpSta & Num, DnSta & Num=  ,2461, 2 ,2461, 2 , 0 , 0 , 0 ,,
     3.5     3.5
       0     442
     3.5     3.5
       0     442
BR Coef=-1 , 0 , 0 ,1.05, 0 ,,,0.8,-1,0.5,0,
WSPro=,,,, 1 ,,,, 0 ,,,, 0 ,,,,-1 ,-1 ,-1 , 0 , 0 , 0 , 0 , 0
BC Design=,, 0 ,, 0 ,,,,,,
BC Use User HTab Curves=0
BC User HTab FreeFlow(D)= 0

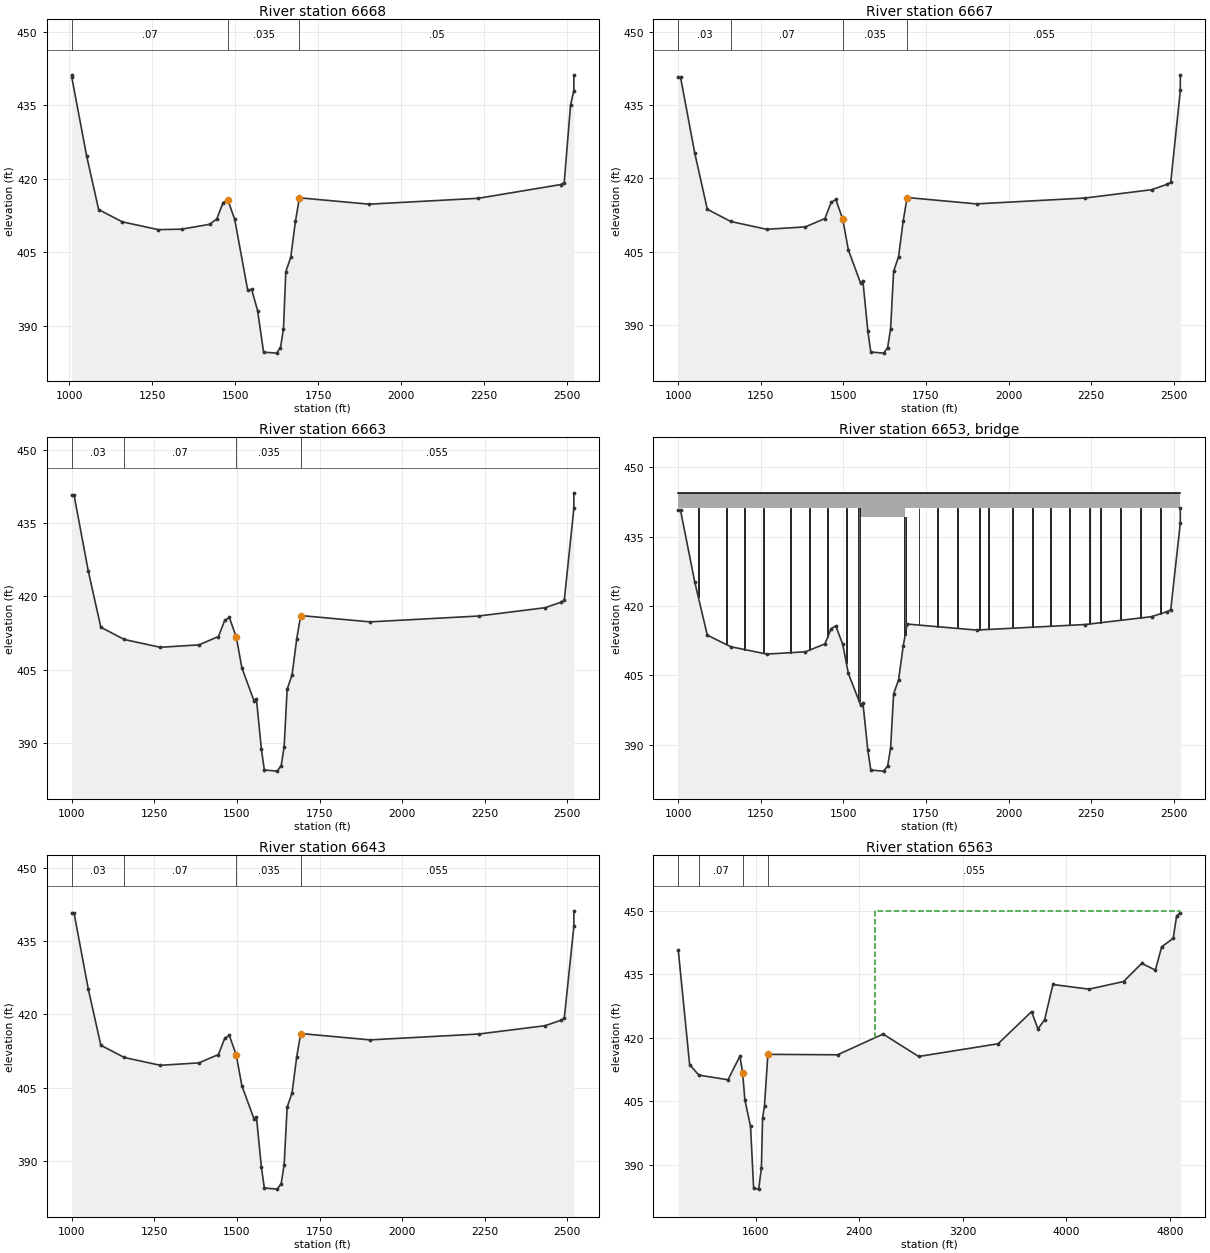
Type RM Length L Ch R = 1 ,6668    ,1,1,1
BEGIN DESCRIPTION:
This cross section corresponds to cross section 6668 of the non-georeferenced CDC model which was the source of this model.
END DESCRIPTION:
XS GIS Cut Line= 2
  2458714.850319 6982869.9821785   2457201.76622    6982881.3002
#Sta/Elev= 30
    1007   441.2    1007   440.7    1052  424.59    1088   413.7    1159   411.2
    1268   409.6    1338   409.7    1423   410.7    1444   411.8    1463   415.1
    1477   415.7    1498   411.7    1537   397.3    1549   397.4    1567   393.1
    1585   384.6    1624   384.4    1636   385.5    1645   389.4    1652     401
    1667     404    1681   411.3    1693   416.1    1903   414.8    2232     416
    2480   418.8    2491   419.2    2510     435    2520     438    2520   441.2
#Mann= 3 ,0,0
    1007     .07       0    1477    .035       0    1693     .05       0
#XS Ineff= 2 , 0
            1477   415.7    1693           416.1
Permanent Ineff=
       F       F
Bank Sta=1477,1693
XS Rating Curve= 0 ,0
Exp/Cntr=0.5,0.3

Type RM Length L Ch R = 1 ,6667    ,4,4,4
BEGIN DESCRIPTION:
This cross section corresponds to cross section 6667 of the non-georeferenced CDC model which was the source of this model.
END DESCRIPTION:
XS GIS Cut Line= 2
 2458721.95791656982868.929030972457201.95144209 6982880.2807143
#Sta/Elev= 30
    1000   440.8    1007   440.7    1050   425.2    1088   413.7    1159   411.2
    1268   409.6    1385   410.1    1444   411.8    1463   415.1    1477   415.7
    1498   411.7    1515   405.4    1552   398.6    1559   399.1    1574   388.8
    1583   384.5    1622  384.27    1634   385.4    1643   389.3    1652     401
    1667     404    1681   411.3    1693   416.1    1903   414.8    2232     416
    2433   417.7    2480   418.8    2491   419.2    2520     438    2520   441.2
#Mann= 4 ,-1,0
    1000     .03       0    1159     .07       0    1498    .035       0
    1693    .055       0
#XS Ineff= 2 , 0
            1498   411.7    1693           416.1
Permanent Ineff=
       F       F
Bank Sta=1498,1693
XS Rating Curve= 0 ,0
Exp/Cntr=0.3,0.1

Type RM Length L Ch R = 1 ,6663    ,20,20,20
BEGIN DESCRIPTION:
This cross section corresponds to cross section 6663 of the non-georeferenced CDC model which was the source of this model.
END DESCRIPTION:
XS GIS Cut Line= 2
2458721.842103096982864.93166363 2457201.89435566982876.24299271
#Sta/Elev= 30
    1000   440.8    1007   440.7    1050   425.2    1088   413.7    1159   411.2
    1268   409.6    1385   410.1    1444   411.8    1463   415.1    1477   415.7
    1498   411.7    1515   405.4    1552   398.6    1559   399.1    1574   388.8
    1583   384.5    1622  384.27    1634   385.4    1643   389.3    1652     401
    1667     404    1681   411.3    1693   416.1    1903   414.8    2232     416
    2433   417.7    2480   418.8    2491   419.2    2520     438    2520   441.2
#Mann= 4 ,-1,0
    1000     .03       0    1159     .07       0    1498    .035       0
    1693    .055       0
Bank Sta=1498,1693
XS Rating Curve= 0 ,0
Exp/Cntr=0.5,0.3

Type RM Length L Ch R = 3 ,6653    ,,,
BEGIN DESCRIPTION:
Burlington Northern Sante Fe Railroad
END DESCRIPTION:
Node Name=BNSF RR
Bridge Culvert--1,0,-1,-1, 0
Deck Dist Width WeirC Skew NumUp NumDn MinLoCord MaxHiCord MaxSubmerge Is_Ogee
0.5,19,2.6,0, 52, 52, , , 0.95, 0, 0,0,,
    1000    1048    1052    1146    1154    1296    1304    1348    1352    1398
    1402    1448    1452  1489.5  1490.5  1519.5  1520.5  1526.5    1547    1547
    1617    1687    1687  1724.5  1725.5  1739.5  1740.5    1788    1792    1848
    1852    1898    1902    1958    1962    1998    2002    2048    2052    2148
    2152    2256    2264    2298    2302    2426    2434    2468    2472    2489
    2491    2520
   444.5   444.5   444.5   444.5   444.5   444.5   444.5   444.5   444.5   444.5
   444.5   444.5   444.5   444.5   444.5   444.5   444.5   444.5   444.5   444.5
   444.5   444.5   444.5   444.5   444.5   444.5   444.5   444.5   444.5   444.5
   444.5   444.5   444.5   444.5   444.5   444.5   444.5   444.5   444.5   444.5
   444.5   444.5   444.5   444.5   444.5   444.5   444.5   444.5   444.5   444.5
   444.5   444.5
   441.2   441.2   441.2   441.2   441.2   441.2   441.2   441.2   441.2   441.2
   441.2   441.2   441.2   441.2   441.2   441.2   441.2   441.2   441.2   439.3
   439.3   439.3   441.2   441.2   441.2   441.2   441.2   441.2   441.2   441.2
   441.2   441.2   441.2   441.2   441.2   441.2   441.2   441.2   441.2   441.2
   441.2   441.2   441.2   441.2   441.2   441.2   441.2   441.2   441.2   441.2
   441.2   441.2
    1000    1048    1052    1146    1154    1296    1304    1348    1352    1398
    1402    1448    1452  1489.5  1490.5  1519.5  1520.5  1526.5    1547    1547
    1617    1687    1687  1724.5  1725.5  1739.5  1740.5    1788    1792    1848
    1852    1898    1902    1958    1962    1998    2002    2048    2052    2148
    2152    2256    2264    2298    2302    2426    2434    2468    2472    2489
    2491    2520
   444.5   444.5   444.5   444.5   444.5   444.5   444.5   444.5   444.5   444.5
   444.5   444.5   444.5   444.5   444.5   444.5   444.5   444.5   444.5   444.5
   444.5   444.5   444.5   444.5   444.5   444.5   444.5   444.5   444.5   444.5
   444.5   444.5   444.5   444.5   444.5   444.5   444.5   444.5   444.5   444.5
   444.5   444.5   444.5   444.5   444.5   444.5   444.5   444.5   444.5   444.5
   444.5   444.5
   441.2   441.2   441.2   441.2   441.2   441.2   441.2   441.2   441.2   441.2
   441.2   441.2   441.2   441.2   441.2   441.2   441.2   441.2   441.2   439.3
   439.3   439.3   441.2   441.2   441.2   441.2   441.2   441.2   441.2   441.2
   441.2   441.2   441.2   441.2   441.2   441.2   441.2   441.2   441.2   441.2
   441.2   441.2   441.2   441.2   441.2   441.2   441.2   441.2   441.2   441.2
   441.2   441.2
Pier Skew, UpSta & Num, DnSta & Num=  ,1061, 2 ,1061, 2 , 0 , 0 , 0 ,,
     3.5     3.5
       0     442
     3.5     3.5
       0     442
Pier Skew, UpSta & Num, DnSta & Num=  ,1145, 2 ,1145, 2 , 0 , 0 , 0 ,,
     3.5     3.5
       0     442
     3.5     3.5
       0     442
Pier Skew, UpSta & Num, DnSta & Num=  ,1201, 2 ,1201, 2 , 0 , 0 , 0 ,,
    2.34    2.34
       0     442
    2.34    2.34
       0     442
Pier Skew, UpSta & Num, DnSta & Num=  ,1257, 2 ,1257, 2 , 0 , 0 , 0 ,,
     3.5     3.5
       0     442
     3.5     3.5
       0     442
Pier Skew, UpSta & Num, DnSta & Num=  ,1341, 2 ,1341, 2 , 0 , 0 , 0 ,,
     3.5     3.5
       0     442
     3.5     3.5
       0     442
Pier Skew, UpSta & Num, DnSta & Num=  ,1397, 2 ,1397, 2 , 0 , 0 , 0 ,,
    2.34    2.34
       0     442
    2.34    2.34
       0     442
Pier Skew, UpSta & Num, DnSta & Num=  ,1453, 2 ,1453, 2 , 0 , 0 , 0 ,,
     3.5     3.5
       0     442
     3.5     3.5
       0     442
Pier Skew, UpSta & Num, DnSta & Num=  ,1509, 2 ,1509, 2 , 0 , 0 , 0 ,,
    1.17    1.17
       0     442
    1.17    1.17
       0     442
Pier Skew, UpSta & Num, DnSta & Num=  ,1547, 2 ,1547, 2 , 0 , 0 , 0 ,,
       6       6
       0     442
       6       6
       0     442
Pier Skew, UpSta & Num, DnSta & Num=  ,1687, 2 ,1687, 2 , 0 , 0 , 0 ,,
       6       6
       0     442
       6       6
       0     442
Pier Skew, UpSta & Num, DnSta & Num=  ,1728, 2 ,1728, 2 , 0 , 0 , 0 ,,
    1.17    1.17
       0     442
    1.17    1.17
       0     442
Pier Skew, UpSta & Num, DnSta & Num=  ,1784, 2 ,1784, 2 , 0 , 0 , 0 ,,
     3.5     3.5
       0     442
     3.5     3.5
       0     442
Pier Skew, UpSta & Num, DnSta & Num=  ,1845, 2 ,1845, 2 , 0 , 0 , 0 ,,
    2.34    2.34
       0     442
    2.34    2.34
       0     442
Pier Skew, UpSta & Num, DnSta & Num=  ,1911, 2 ,1911, 2 , 0 , 0 , 0 ,,
    2.34    2.34
       0     442
    2.34    2.34
       0     442
Pier Skew, UpSta & Num, DnSta & Num=  ,1939, 2 ,1939, 2 , 0 , 0 , 0 ,,
    2.34    2.34
       0     442
    2.34    2.34
       0     442
Pier Skew, UpSta & Num, DnSta & Num=  ,2011, 2 ,2011, 2 , 0 , 0 , 0 ,,
    2.34    2.34
       0     442
    2.34    2.34
       0     442
Pier Skew, UpSta & Num, DnSta & Num=  ,2072, 2 ,2072, 2 , 0 , 0 , 0 ,,
     3.5     3.5
       0     442
     3.5     3.5
       0     442
Pier Skew, UpSta & Num, DnSta & Num=  ,2128, 2 ,2128, 2 , 0 , 0 , 0 ,,
    2.34    2.34
       0     442
    2.34    2.34
       0     442
Pier Skew, UpSta & Num, DnSta & Num=  ,2184, 2 ,2184, 2 , 0 , 0 , 0 ,,
    2.34    2.34
       0     442
    2.34    2.34
       0     442
Pier Skew, UpSta & Num, DnSta & Num=  ,2245, 2 ,2245, 2 , 0 , 0 , 0 ,,
    2.34    2.34
       0     442
    2.34    2.34
       0     442
Pier Skew, UpSta & Num, DnSta & Num=  ,2278, 2 ,2278, 2 , 0 , 0 , 0 ,,
    2.34    2.34
       0     442
    2.34    2.34
       0     442
Pier Skew, UpSta & Num, DnSta & Num=  ,2339, 2 ,2339, 2 , 0 , 0 , 0 ,,
    2.34    2.34
       0     442
    2.34    2.34
       0     442
Pier Skew, UpSta & Num, DnSta & Num=  ,2400, 2 ,2400, 2 , 0 , 0 , 0 ,,
    2.34    2.34
       0     442
    2.34    2.34
       0     442
Pier Skew, UpSta & Num, DnSta & Num=  ,2461, 2 ,2461, 2 , 0 , 0 , 0 ,,
     3.5     3.5
       0     442
     3.5     3.5
       0     442
BR Coef=-1 , 0 , 0 ,1.05, 0 ,,,0.8,-1,0.5,0,
WSPro=,,,, 1 ,,,, 0 ,,,, 0 ,,,,-1 ,-1 ,-1 , 0 , 0 , 0 , 0 , 0
BC Design=,, 0 ,, 0 ,,,,,,
BC Use User HTab Curves=0
BC User HTab FreeFlow(D)= 0

Type RM Length L Ch R = 1 ,6643    ,80,80,80
BEGIN DESCRIPTION:
This cross section corresponds to cross section 6643 of the non-georeferenced CDC model which was the source of this model.
---------------------------------------------------------------------
CDC IRV092399-1 BNSF Bridge
CROSS-SECTION 6643 - 6689
---------------------------------------------------------------------
END DESCRIPTION:
XS GIS Cut Line= 2
2458733.769572686982844.843121132457213.812966916982856.12689121
#Sta/Elev= 30
    1000   440.8    1007   440.7    1050   425.2    1088   413.7    1159   411.2
    1268   409.6    1385   410.1    1444   411.8    1463   415.1    1477   415.7
    1498   411.7    1515   405.4    1552   398.6    1559   399.1    1574   388.8
    1583   384.5    1622  384.27    1634   385.4    1643   389.3    1652     401
    1667     404    1681   411.3    1693   416.1    1903   414.8    2232     416
    2433   417.7    2480   418.8    2491   419.2    2520     438    2520   441.2
#Mann= 4 ,-1,0
    1000     .03       0    1159     .07       0    1498    .035       0
    1693    .055       0
Bank Sta=1498,1693
XS Rating Curve= 0 ,0
Exp/Cntr=0.5,0.3

Type RM Length L Ch R = 1 ,6563    ,598,598,598
BEGIN DESCRIPTION:
This cross section corresponds to cross section 6563 of the non-georeferenced CDC model which was the source of this model.
Cross-section EF009.  105 feet downstream of Chicago, Rock Island, and Pacific Railroad.  Effective flow limit set at East Levee in LOB, at sta 2520 in ROB.  Trinity View Park in ROB.  High peak adjacent to channel in ROB removed.
Channel data from COD Elm Fork channel survey - cross-section EF#009 surveyed
* February 1994.
END DESCRIPTION:
XS GIS Cut Line= 3
2458720.327014276982764.951220562456926.186901756982777.93413422
2454838.522770026982753.02407905
#Sta/Elev= 30
    1000   440.8    1088   413.7    1159   411.2    1385   410.1    1477   415.7
    1498   411.7    1515   405.4    1559   399.1    1583   384.5    1622  384.27
    1643   389.3    1652     401    1667     404    1693   416.1    2232     416
    2584   420.9    2859   415.6    3473   418.6    3732   426.2    3781   422.1
    3833   424.3    3897   432.6    4176   431.5    4443   433.3    4584   437.6
    4689     436    4738   441.5    4827   443.5    4853   448.7    4882   449.6
#Mann= 4 ,-1,0
    1000     .03       0    1159     .07       0    1498    .035       0
    1693    .055       0
#XS Ineff= 3 ,-1
    1000    1498   411.7    1693    2520   416.1    2520    4882     450
Permanent Ineff=
       F       F       F
Bank Sta=1498,1693
XS Rating Curve= 0 ,0
Exp/Cntr=0.3,0.1