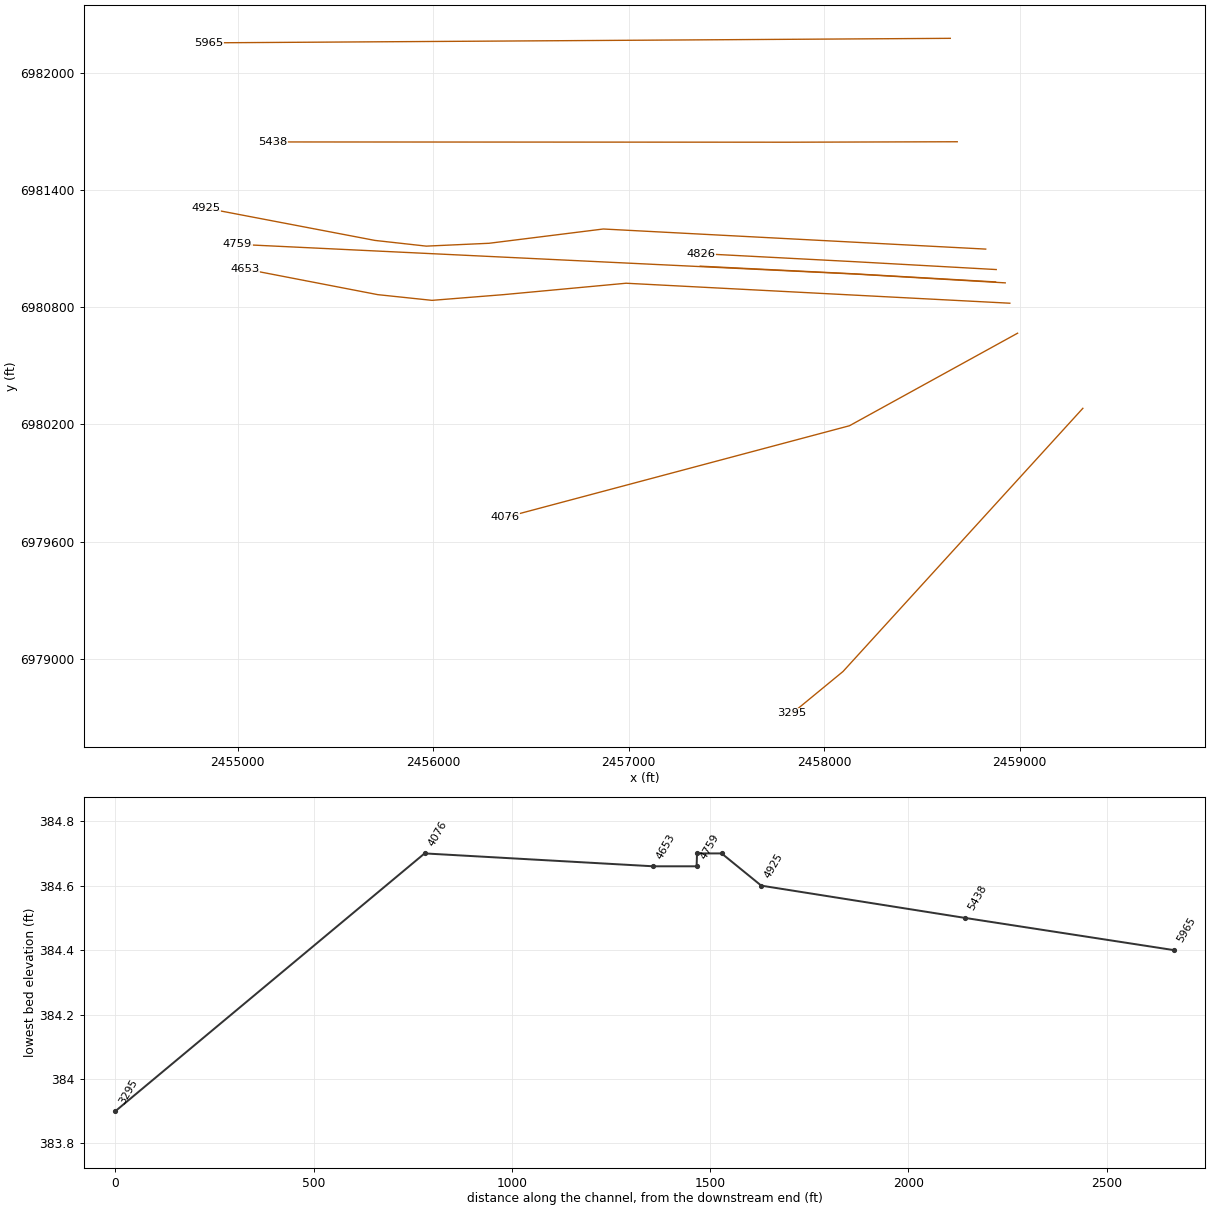
HEC-RAS study CDC_Consolidated_Model.prj: Upper Trinity CDC Consolidated Model

--- CDC_Consolidated_Model.g12 (geometry) --- (continued)

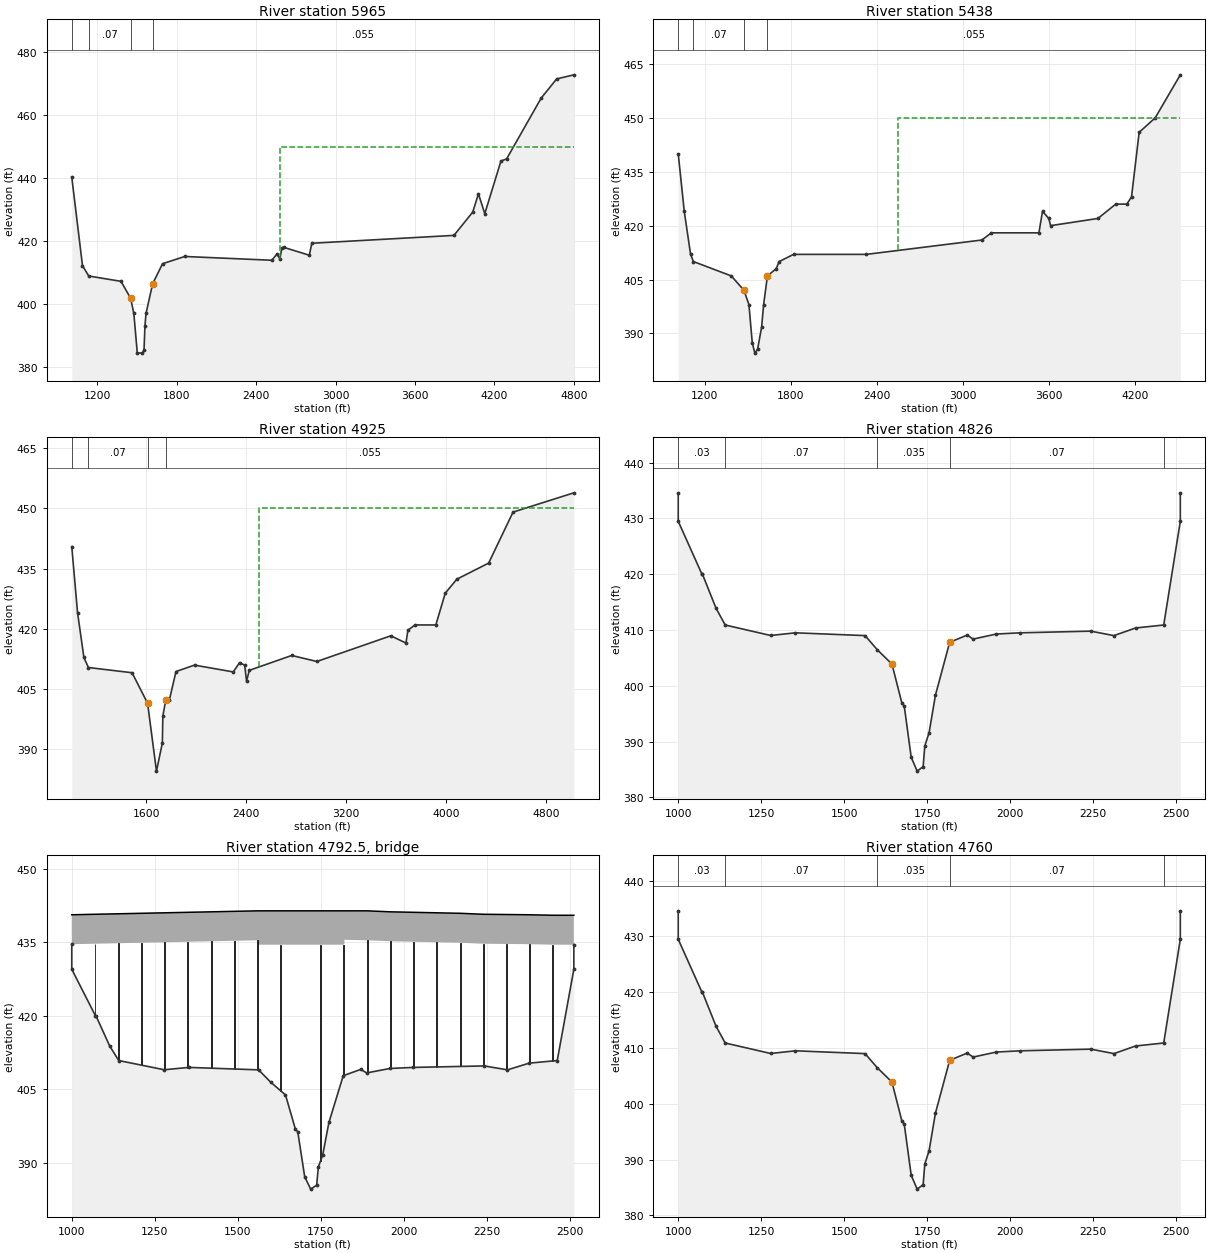
Type RM Length L Ch R = 1 ,5965    ,527,527,527
BEGIN DESCRIPTION:
This cross section corresponds to cross section 5965 of the non-georeferenced CDC model which was the source of this model.
 Cross-section EF008.  Effective flow limit set at East Levee in LOB, at sta 2580 in ROB.  Trinity View Park in ROB.
Channel data from COD Elm Fork channel survey.
END DESCRIPTION:
XS GIS Cut Line= 2
2458645.244159166982174.781797222454851.314083016982151.77790621
#Sta/Elev= 30
    1007   440.3    1088   412.2    1135   408.9    1379   407.2    1452   401.8
    1476     397    1502   384.5    1541   384.4    1553   385.4    1560   393.1
    1568     397    1618   406.4    1693   412.8    1861   415.1    2519   413.9
    2558   415.9    2580   414.3    2594   417.8    2609     418    2802   415.5
    2821   419.3    3895   421.8    4037   429.2    4080     435    4128   428.7
    4250   445.4    4293   446.1    4554   465.4    4671   471.5    4801   472.8
#Mann= 4 ,-1,0
    1007     .03       0    1135     .07       0    1452    .035       0
    1618    .055       0
#XS Ineff= 3 ,-1
    1007    1452   401.8    1618    2580   406.4    2580    4801     450
Permanent Ineff=
       F       F       F
Bank Sta=1452,1618
XS Rating Curve= 0 ,0
Exp/Cntr=0.3,0.1

Type RM Length L Ch R = 1 ,5438    ,513,513,513
BEGIN DESCRIPTION:
This cross section corresponds to cross section 5438 of the non-georeferenced CDC model which was the source of this model.
Cross-section generated from topographic file.  Effective flow limit set at East Levee in LOB, at sta 2550 in ROB.
Channel data from COD Elm Fork channel survey.
END DESCRIPTION:
XS GIS Cut Line= 3
2458680.768366346981645.731346132457814.093918596981643.43902788
2455179.271432346981644.76120372
#Sta/Elev= 30
  1016.6     440  1058.6     424  1102.8     412  1122.4     410  1386.6     406
  1474.9     402  1509.7     398    1533   387.3    1551   384.5    1570   385.6
    1598   391.7    1612     398  1638.7     406  1699.4     408  1720.4     410
  1821.3     412  2328.6     412  3134.5     416  3200.3     418    3532     418
    3557     424  3600.7     422  3613.6     420  3943.5     422    4068     426
  4144.9     426  4177.8     428  4231.2     446  4342.6     450  4518.1     462
#Mann= 4 ,-1,0
  1016.6     .03       0  1122.4     .07       0  1474.9    .035       0
  1638.7    .055       0
#XS Ineff= 3 ,-1
  1016.6  1474.9     402  1638.7    2550     406    2550    4518     450
Permanent Ineff=
       F       F       F
Bank Sta=1474.9,1638.7
XS Rating Curve= 0 ,0
Exp/Cntr=0.3,0.1

Type RM Length L Ch R = 1 ,4925    ,100,100,100
BEGIN DESCRIPTION:
This cross section corresponds to cross section 4925 of the non-georeferenced CDC model which was the source of this model.
Cross-section EF007.  100 feet upstream of SH 356/Irving Boulevard.  Effective flow limit set at East Levee in LOB, at sta 2500 in ROB.  Trinity View Park in ROB.
Channel data from COD Elm Fork channel survey.
END DESCRIPTION:
XS GIS Cut Line= 6
2458826.461316446981096.603179312456870.079074356981199.42416789
2456286.012985266981126.415127552455964.778063426981111.81410688
2455701.947880426981141.01713246 2454838.2396341 6981305.8271703
#Sta/Elev= 30
    1006   440.5    1052   424.1    1103   412.9    1139   410.4    1488   409.1
    1612   401.5    1683   384.6    1730   391.6    1734   398.3    1757   402.3
    1786   402.3    1839   409.4    1987     411    2297   409.3    2347   411.6
    2388     411    2403     407    2425   409.7    2764   413.4    2965   411.9
    3556   418.3    3677   416.5    3693   419.7    3750     421    3916     421
    3991   428.9    4084   432.4    4338   436.4    4533   449.1    5019   453.9
#Mann= 4 ,-1,0
    1006     .03       0    1139     .07       0    1612    .035       0
    1757    .055       0
#XS Ineff= 3 ,-1
    1006    1612   401.5    1757    2500   402.3    2500    5019     450
Permanent Ineff=
       F       F       F
Bank Sta=1612,1757
XS Rating Curve= 0 ,0
Exp/Cntr=0.3,0.1

Type RM Length L Ch R = 1 ,4826    ,62,62,62
BEGIN DESCRIPTION:
This cross section corresponds to cross section 4826 of the non-georeferenced CDC model which was the source of this model.
END DESCRIPTION:
XS GIS Cut Line= 3
2458880.24992275 6980991.97149882458152.950196276981032.34608996
2457369.44356117 6981073.3768478
#Sta/Elev= 30
    1000   434.6    1000   429.5  1071.5     420    1073     420    1114   413.9
  1141.5   410.9  1278.5 409.022    1353   409.5    1563     409 1599.77 406.469
    1644   403.9    1674   396.9    1681   396.4    1702   387.2    1720   384.7
    1738   385.5    1743   389.2    1756   391.6    1775   398.3    1818   407.8
    1871   409.1  1888.5 408.375  1958.5  409.28  2028.5 409.496    2243   409.8
    2313     409  2378.5 410.369    2463   410.9    2513   429.5    2513   434.5
#Mann= 5 ,-1,0
    1000     .03       0  1141.5     .07       0 1599.77    .035       0
    1818     .07       0    2463     .03       0
#XS Ineff= 2 , 0
            1644   403.9    1818           407.8
Permanent Ineff=
       F       F
Bank Sta=1644,1818
XS Rating Curve= 0 ,0
Exp/Cntr=0.5,0.3

Type RM Length L Ch R = 3 ,4792.5  ,,,
BEGIN DESCRIPTION:
SH 356/Irving Boulevard
END DESCRIPTION:
Node Name=SH 356/Irving Bl
Bridge Culvert--1,0,-1,-1, 0
Deck Dist Width WeirC Skew NumUp NumDn MinLoCord MaxHiCord MaxSubmerge Is_Ogee
2,59,2.6,0, 44, 44, , , 0.95, 0, ,,,
    1000  1068.5  1071.5  1138.5  1141.5  1208.5  1211.5  1278.5  1281.5  1348.5
  1351.5  1418.5  1421.5  1488.5  1491.5  1558.5  1561.5  1561.5 1628.25 1631.75
 1748.25 1751.75  1818.5  1821.5  1821.5  1888.5  1891.5  1958.5  1961.5  2028.5
  2031.5  2098.5  2101.5  2168.5  2171.5  2238.5  2241.5  2308.5  2311.5  2378.5
  2381.5  2448.5  2451.5    2513
   440.6 440.698 440.702 440.798 440.802 440.898 440.902 440.998 441.002 441.098
 441.102 441.198 441.202 441.298 441.302 441.398   441.4   441.4   441.4   441.4
   441.4   441.4   441.4   441.4   441.4 441.402 441.396 441.204 441.198 441.102
 441.098 441.002 440.998 440.902 440.896 440.704 440.699 440.651 440.649 440.601
 440.598 440.502   440.5   440.5
   434.6 434.698 434.702 434.798 434.802 434.898 434.902 434.998 435.002 435.098
 435.102 435.198 435.202 435.298 435.302 435.398   435.4   434.5   434.5   434.5
   434.5   434.5   434.5  434.52   435.5 435.402 435.396 435.204 435.198 435.102
 435.098 435.002 434.998 434.902 434.896 434.704 434.699 434.651 434.649 434.601
 434.598 434.502   434.5   434.5
    1000  1068.5  1071.5  1138.5  1141.5  1208.5  1211.5  1278.5  1281.5  1348.5
  1351.5  1418.5  1421.5  1488.5  1491.5  1558.5  1561.5  1561.5 1628.25 1631.75
 1748.25 1751.75  1818.5  1821.5  1821.5  1888.5  1891.5  1958.5  1961.5  2028.5
  2031.5  2098.5  2101.5  2168.5  2171.5  2238.5  2241.5  2308.5  2311.5  2378.5
  2381.5  2448.5  2451.5    2513
   440.6 440.698 440.702 440.798 440.802 440.898 440.902 440.998 441.002 441.098
 441.102 441.198 441.202 441.298 441.302 441.398   441.4   441.4   441.4   441.4
   441.4   441.4   441.4   441.4   441.4 441.402 441.396 441.204 441.198 441.102
 441.098 441.002 440.998 440.902 440.896 440.704 440.699 440.651 440.649 440.601
 440.598 440.502   440.5   440.5
   434.6 434.698 434.702 434.798 434.802 434.898 434.902 434.998 435.002 435.098
 435.102 435.198 435.202 435.298 435.302 435.398   435.4   434.5   434.5   434.5
   434.5   434.5   434.5  434.52   435.5 435.402 435.396 435.204 435.198 435.102
 435.098 435.002 434.998 434.902 434.896 434.704 434.699 434.651 434.649 434.601
 434.598 434.502   434.5   434.5
Pier Skew, UpSta & Num, DnSta & Num=  ,1070, 2 ,1070, 2 , 0 , 0 , 0 ,,
       3       3
       0     440
       3       3
       0     440
Pier Skew, UpSta & Num, DnSta & Num=  ,1140, 2 ,1140, 2 , 0 , 0 , 0 ,,
       3       3
       0     440
       3       3
       0     440
Pier Skew, UpSta & Num, DnSta & Num=  ,1210, 2 ,1210, 2 , 0 , 0 , 0 ,,
       3       3
       0     440
       3       3
       0     440
Pier Skew, UpSta & Num, DnSta & Num=  ,1280, 2 ,1280, 2 , 0 , 0 , 0 ,,
       3       3
       0     440
       3       3
       0     440
Pier Skew, UpSta & Num, DnSta & Num=  ,1350, 2 ,1350, 2 , 0 , 0 , 0 ,,
       3       3
       0     440
       3       3
       0     440
Pier Skew, UpSta & Num, DnSta & Num=  ,1420, 2 ,1420, 2 , 0 , 0 , 0 ,,
       3       3
       0     440
       3       3
       0     440
Pier Skew, UpSta & Num, DnSta & Num=  ,1490, 2 ,1490, 2 , 0 , 0 , 0 ,,
       3       3
       0     440
       3       3
       0     440
Pier Skew, UpSta & Num, DnSta & Num=  ,1560, 2 ,1560, 2 , 0 , 0 , 0 ,,
       3       3
       0     440
       3       3
       0     440
Pier Skew, UpSta & Num, DnSta & Num=  ,1630, 2 ,1630, 2 , 0 , 0 , 0 ,,
       3       3
       0     440
       3       3
       0     440
Pier Skew, UpSta & Num, DnSta & Num=  ,1750, 2 ,1750, 2 , 0 , 0 , 0 ,,
       3       3
       0     440
       3       3
       0     440
Pier Skew, UpSta & Num, DnSta & Num=  ,1820, 2 ,1820, 2 , 0 , 0 , 0 ,,
       3       3
       0     440
       3       3
       0     440
Pier Skew, UpSta & Num, DnSta & Num=  ,1890, 2 ,1890, 2 , 0 , 0 , 0 ,,
       3       3
       0     440
       3       3
       0     440
Pier Skew, UpSta & Num, DnSta & Num=  ,1960, 2 ,1960, 2 , 0 , 0 , 0 ,,
       3       3
       0     440
       3       3
       0     440
Pier Skew, UpSta & Num, DnSta & Num=  ,2030, 2 ,2030, 2 , 0 , 0 , 0 ,,
       3       3
       0     440
       3       3
       0     440
Pier Skew, UpSta & Num, DnSta & Num=  ,2100, 2 ,2100, 2 , 0 , 0 , 0 ,,
       3       3
       0     440
       3       3
       0     440
Pier Skew, UpSta & Num, DnSta & Num=  ,2170, 2 ,2170, 2 , 0 , 0 , 0 ,,
       3       3
       0     440
       3       3
       0     440
Pier Skew, UpSta & Num, DnSta & Num=  ,2240, 2 ,2240, 2 , 0 , 0 , 0 ,,
       3       3
       0     440
       3       3
       0     440
Pier Skew, UpSta & Num, DnSta & Num=  ,2310, 2 ,2310, 2 , 0 , 0 , 0 ,,
       3       3
       0     440
       3       3
       0     440
Pier Skew, UpSta & Num, DnSta & Num=  ,2380, 2 ,2380, 2 , 0 , 0 , 0 ,,
       3       3
       3     440
       3       3
       3     440
Pier Skew, UpSta & Num, DnSta & Num=  ,2450, 2 ,2450, 2 , 0 , 0 , 0 ,,
       3       3
       3     440
       3       3
       3     440
BR Coef= 1 , 0 , 0 ,1.05, 0 ,,,0.8,-1,0.5,1,
WSPro=,,,, 1 ,,,, 0 ,,,, 0 ,,,,-1 ,-1 ,-1 , 0 , 0 , 0 , 0 , 0
BC Design=,, 0 ,, 0 ,,,,,,
BC HTab HWMax=434.6
BC Use User HTab Curves=0
BC User HTab FreeFlow(D)= 0

Type RM Length L Ch R = 1 ,4760    ,1,1,1
BEGIN DESCRIPTION:
This cross section corresponds to cross section 4760 of the non-georeferenced CDC model which was the source of this model.
END DESCRIPTION:
XS GIS Cut Line= 3
2458876.860493846980928.674053222458155.764167016980970.02731697
2457366.022308176981009.31956121
#Sta/Elev= 30
    1000   434.6    1000   429.5  1071.5     420    1073     420    1114   413.9
  1141.5   410.9  1278.5 409.022    1353   409.5    1563     409 1599.77 406.469
    1644   403.9    1674   396.9    1681   396.4    1702   387.2    1720   384.7
    1738   385.5    1743   389.2    1756   391.6    1775   398.3    1818   407.8
    1871   409.1  1888.5 408.375  1958.5  409.28  2028.5 409.496    2243   409.8
    2313     409  2378.5 410.369    2463   410.9    2513   429.5    2513   434.5
#Mann= 5 ,-1,0
    1000     .03       0  1141.5     .07       0 1599.77    .035       0
    1818     .07       0    2463     .03       0
#XS Ineff= 2 , 0
            1644   403.9    1818           407.8
Permanent Ineff=
       F       F
Bank Sta=1644,1818
XS Rating Curve= 0 ,0
Exp/Cntr=0.5,0.3

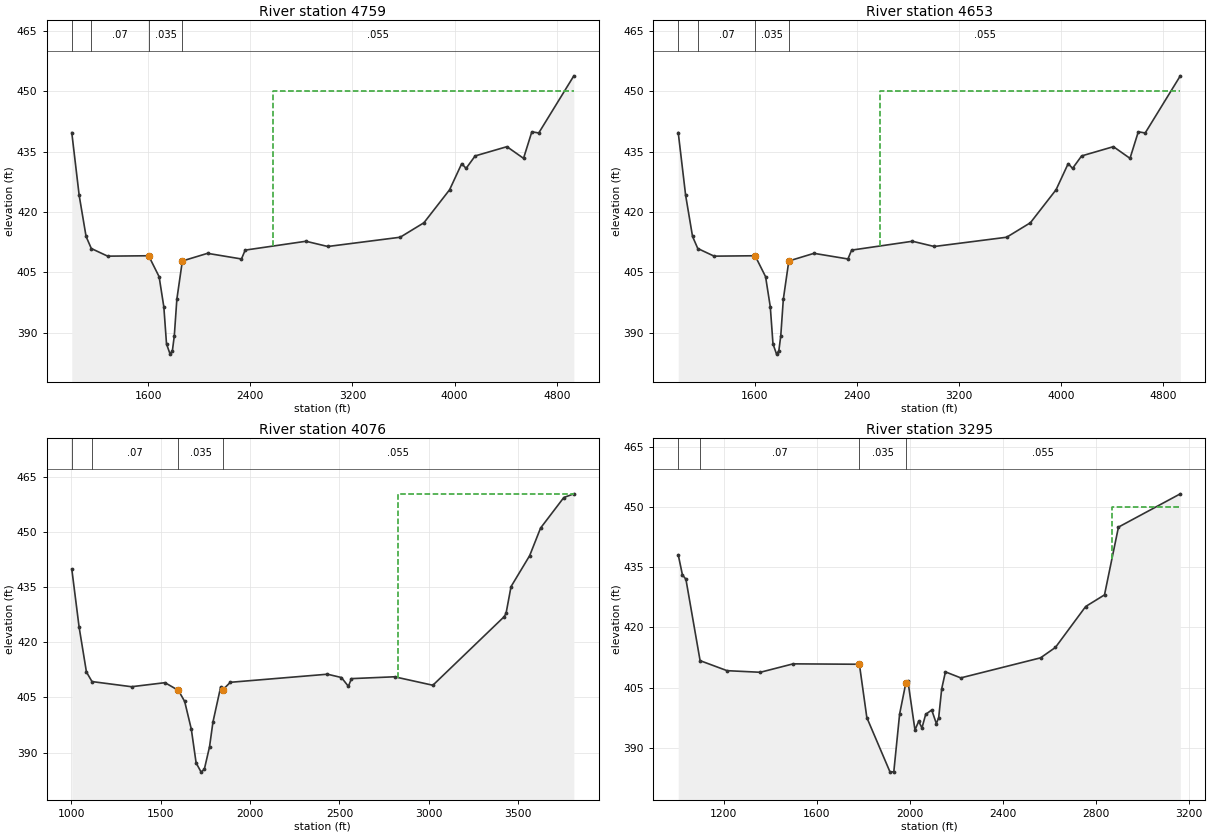
Type RM Length L Ch R = 1 ,4759    ,109,109,109
BEGIN DESCRIPTION:
This cross section corresponds to cross section 4759 of the non-georeferenced CDC model which was the source of this model.
One-foot downstream of SH 356/Irving Boulevard.  Duplication of cross-section 4653 (EF005).
END DESCRIPTION:
XS GIS Cut Line= 3
2458926.217350516980923.890270132458155.827815186980969.03191213
2454999.197973586981121.06605688
#Sta/Elev= 30
    1002   439.7    1060   424.1    1114   413.9    1155   410.9    1283     409
    1604   409.1    1686   403.9    1723   396.4    1744   387.2    1772  384.66
    1790   385.5    1805   389.2    1825   398.3    1868   407.8    2065   409.7
    2331   408.3    2360   410.5    2836   412.7    3007   411.4    3574   413.7
    3760   417.3    3961   425.5    4056     432    4090   430.8    4161   433.9
    4410   436.2    4540   433.3    4605   439.9    4659   439.6    4934   453.8
#Mann= 4 ,-1,0
    1002     .03       0    1155     .07       0    1604    .035       0
    1868    .055       0
#XS Ineff= 3 ,-1
    1002    1604   409.1    1868    2580   407.8    2580    4934     450
Permanent Ineff=
       F       F       F
Bank Sta=1604,1868
XS Rating Curve= 0 ,0
Exp/Cntr=0.3,0.1

Type RM Length L Ch R = 1 ,4653    ,400,577,750
BEGIN DESCRIPTION:
This cross section corresponds to cross section 4653 of the non-georeferenced CDC model which was the source of this model.
Cross-section EF005.  107 feet downstream of SH 356/Irving Boulevard.
Effective flow limit set at East Levee in LOB, at sta 2580 in ROB.  Trinity View Park in ROB.
Channel data from COD Elm Fork channel survey - cross-section EF#005 surveyed February 1994.
END DESCRIPTION:
XS GIS Cut Line= 6
2458949.899717846980819.760885222456986.891832836980921.99296422
2456359.02202559 6980863.5859288  2455993.981089 6980834.3832313
2455716.54988533 6980863.58592882455038.489233586980994.48560138
#Sta/Elev= 30
    1002   439.7    1060   424.1    1114   413.9    1155   410.9    1283     409
    1604   409.1    1686   403.9    1723   396.4    1744   387.2    1772  384.66
    1790   385.5    1805   389.2    1825   398.3    1868   407.8    2065   409.7
    2331   408.3    2360   410.5    2836   412.7    3007   411.4    3574   413.7
    3760   417.3    3961   425.5    4056     432    4090   430.8    4161   433.9
    4410   436.2    4540   433.3    4605   439.9    4659   439.6    4934   453.8
#Mann= 4 ,-1,0
    1002     .03       0    1155     .07       0    1604    .035       0
    1868    .055       0
#XS Ineff= 3 ,-1
    1002    1604   409.1    1868    2580   407.8    2580    4934     450
Permanent Ineff=
       F       F       F
Bank Sta=1604,1868
XS Rating Curve= 0 ,0
Exp/Cntr=0.3,0.1

Type RM Length L Ch R = 1 ,4076    ,649,780,899
BEGIN DESCRIPTION:
This cross section corresponds to cross section 4076 of the non-georeferenced CDC model which was the source of this model.
Cross-section EF004.  Effective flow limit set at East Levee in LOB, at sta 2830 in ROB.  Trinity View Park in ROB.
Channel data from COD Elm Fork channel survey.
END DESCRIPTION:
XS GIS Cut Line= 3
2458989.484284346980666.39045705 2458129.34492856980192.91896304
2456366.581721756979723.64660764
#Sta/Elev= 30
    1004   439.9    1045   424.1    1086   411.9    1117   409.3    1338   407.9
    1525     409    1600   406.9    1635   403.9    1672   396.4    1699   387.2
    1727   384.7    1745   385.5    1774   391.6    1793   398.3    1836   407.8
    1849   407.1    1890   409.1    2433   411.3    2511   410.4    2550     408
    2567   410.1    2808   410.6    3022   408.3    3420   426.9    3431   427.8
    3459   435.1    3563   443.5    3624     451    3754   459.3    3810   460.3
#Mann= 4 ,-1,0
    1004     .03       0    1117     .07       0    1600    .035       0
    1849    .055       0
#XS Ineff= 3 ,-1
    1004    1600   406.9    1849    2830   407.1    2830    3810   460.3
Permanent Ineff=
       F       F       F
Bank Sta=1600,1849
XS Rating Curve= 0 ,0
Exp/Cntr=0.3,0.1

Type RM Length L Ch R = 1 ,3295    ,111,111,111
BEGIN DESCRIPTION:
This cross section corresponds to cross section 3295 of the non-georeferenced CDC model which was the source of this model.
Cross-section EF003.  106 feet upstream of Shady Grove Road. Effective flow limit set at East Levee in LOB, at sta 2870 in ROB.  Trib in ROB removed from conveyance at sta 1993. Channel data from COD Elm Fork channel survey.
END DESCRIPTION:
XS GIS Cut Line= 3
2459323.422264756980282.218653222458096.318091666978935.65802613
2457835.823862026978721.56363805
#Sta/Elev= 30
    1005   438.1    1023   433.1    1038     432    1099   411.7    1215   409.2
    1358   408.8    1499   410.9    1784   410.8    1816   397.5    1916   383.9
    1932     384    1957   398.4    1984   406.2    1993   406.5    2023   394.4
    2039   396.6    2053   394.9    2069   398.3    2095   399.4    2115     396
    2125   397.5    2138   404.7    2154   408.9    2220   407.4    2563   412.4
    2627     415    2757   425.2    2838   428.1    2898     445    3164   453.3
#Mann= 4 ,-1,0
    1005     .03       0    1099     .07       0    1784    .035       0
    1984    .055       0
#XS Ineff= 3 ,-1
    1005    1784   410.8    1993    2870   406.5    2870    3164     450
Permanent Ineff=
       F       T       F
Bank Sta=1784,1984
XS Rating Curve= 0 ,0
Exp/Cntr=0.3,0.1