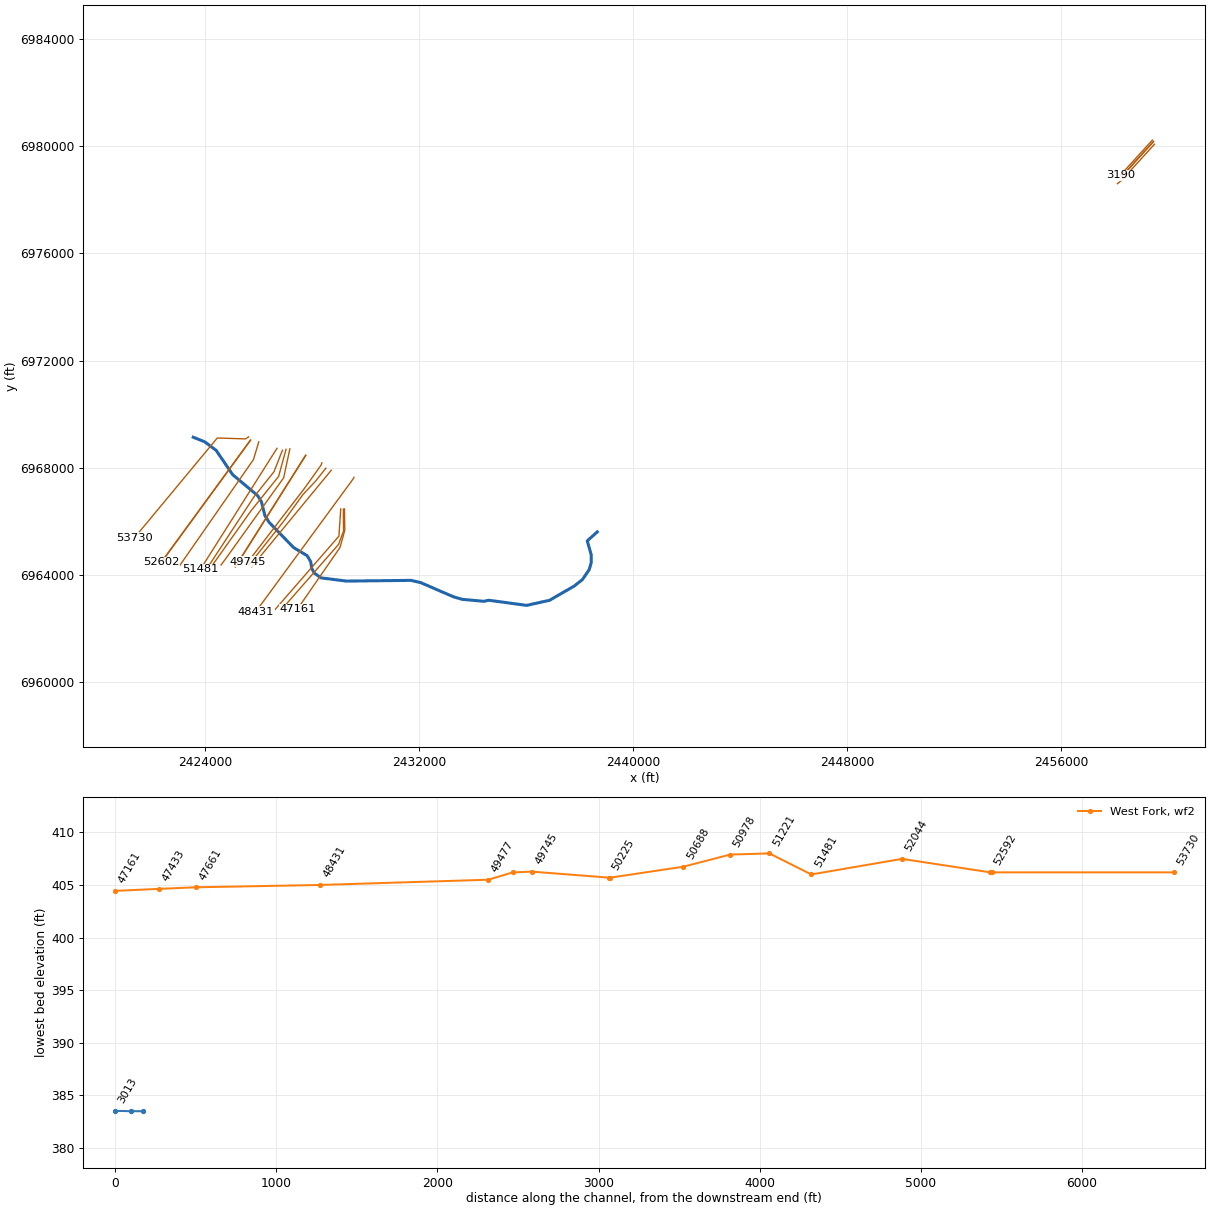
HEC-RAS study CDC_Consolidated_Model.prj: Upper Trinity CDC Consolidated Model

--- CDC_Consolidated_Model.g12 (geometry) --- (continued)

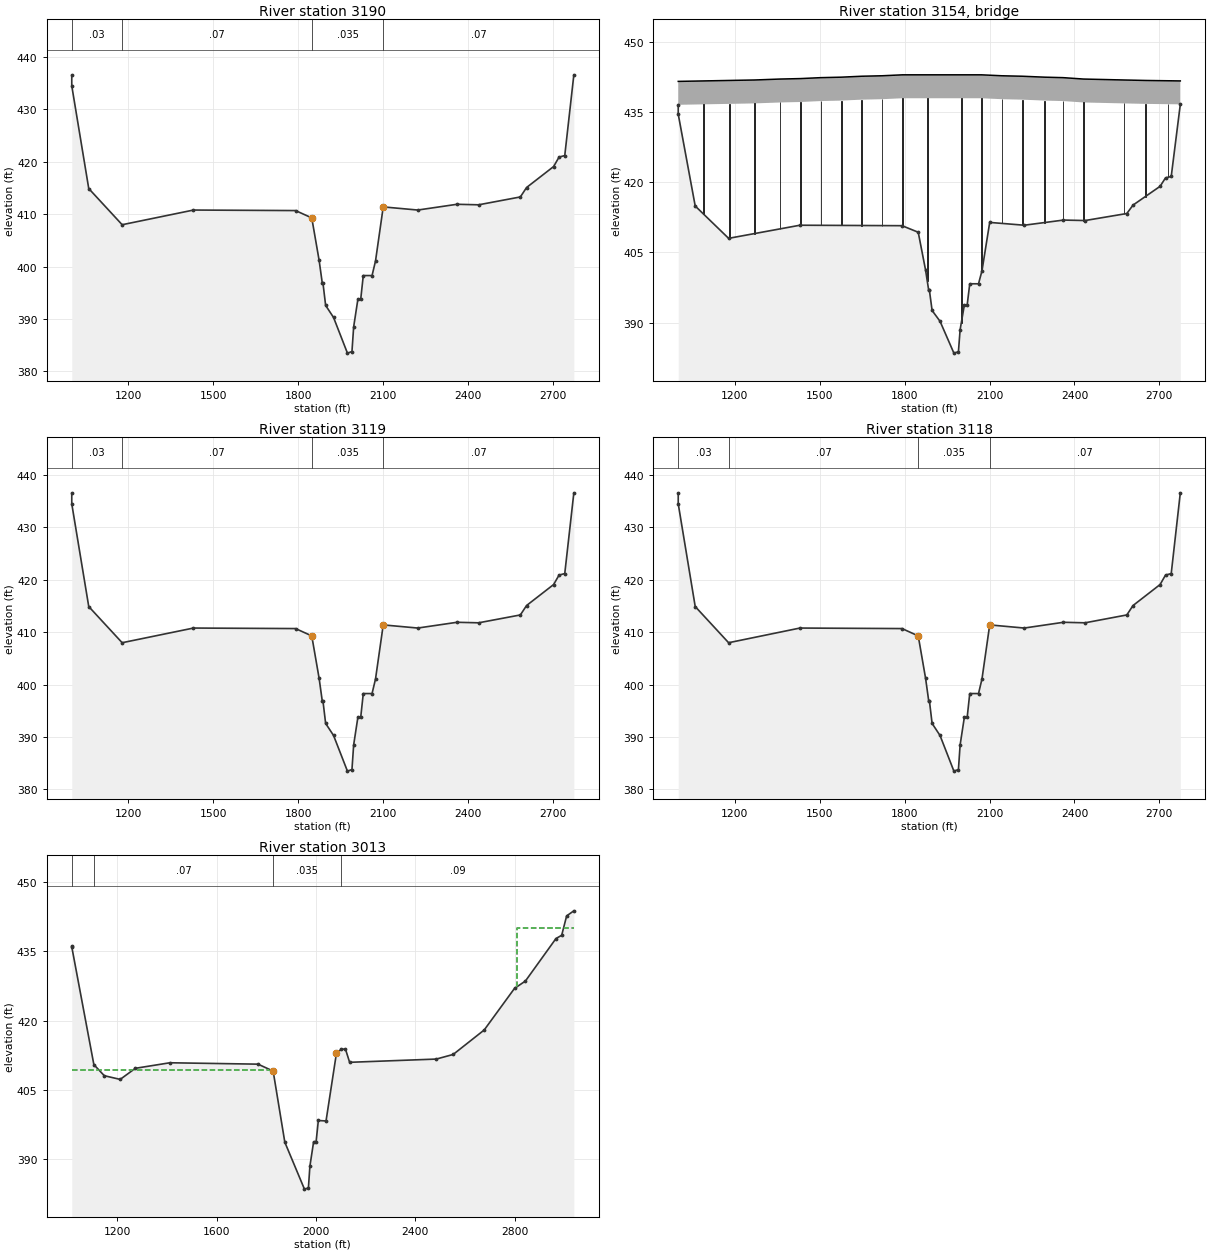
Type RM Length L Ch R = 1 ,3190    ,71,71,71
BEGIN DESCRIPTION:
This cross section corresponds to cross section 3190 of the non-georeferenced CDC model which was the source of this model.
One-foot upstream of Shady Grove Road.  East Levee at LOB.  Channel data from COD Elm Fork channel survey.
END DESCRIPTION:
XS GIS Cut Line= 3
2459425.753424916980231.53830838 2458789.85541856979535.99278347
2458230.308309266978920.82012931
#Sta/Elev= 30
    1000   436.5    1000   434.5    1060   414.9    1178     408    1430   410.8
 1790.75   410.7    1848   409.3    1874   401.2    1885   396.9  1887.5   396.9
    1897   392.6    1925   390.3    1974   383.5    1990   383.8    1996   388.5
    2011   393.8    2021   393.8    2030   398.3    2061   398.3 2073.25 401.084
  2100.5   411.4  2222.5   410.8 2361.25   411.9  2437.5   411.8    2585   413.3
    2607   415.1  2702.5   419.1  2721.7   420.9  2741.9   421.2    2774   436.6
#Mann= 4 ,-1,0
    1000     .03       0    1178     .07       0    1848    .035       0
  2100.5     .07       0
#XS Ineff= 2 , 0
            1848   409.3  2100.5           411.4
Permanent Ineff=
       F       F
Bank Sta=1848,2100.5
XS Rating Curve= 0 ,0
Exp/Cntr=0.5,0.3

Type RM Length L Ch R = 3 ,3154    ,,,
BEGIN DESCRIPTION:
Shady Grove Road
END DESCRIPTION:
Node Name=Shady Grove Road
Bridge Culvert--1,0,-1,-1, 0
Deck Dist Width WeirC Skew NumUp NumDn MinLoCord MaxHiCord MaxSubmerge Is_Ogee
2,68,2.6,0, 46, 46, , , 0.95, 0, ,,,
    1000  1088.5 1088.75 1091.25  1091.5 1178.75 1181.25 1268.75 1271.25 1358.75
 1361.25 1430.75 1433.25 1502.75 1505.25 1574.75 1577.25 1646.75 1649.25 1718.75
 1721.25 1790.75 1793.25 1878.75 1881.25 1998.75 2001.25 2070.75 2073.25 2142.75
 2145.25 2214.75 2217.25 2293.75 2296.25 2358.75 2361.25 2430.75 2433.25 2573.75
 2576.25 2648.75 2651.25 2728.75 2731.25    2774
   441.5 441.598 441.599 441.601 441.602 441.699 441.701 441.799 441.803 441.997
 442.002 442.098 442.103 442.297 442.302 442.398 442.404 442.596 442.602 442.698
 442.703 442.897   442.9   442.9   442.9   442.9   442.9   442.9 442.897 442.703
 442.698 442.602 442.597 442.403 442.398 442.302 442.295 442.005 441.998 441.802
 441.798 441.702 441.698 441.636 441.634   441.6
   436.5 436.598 436.599 436.601 436.602 436.699 436.701 436.799 436.803 436.997
 437.002 437.098 437.103 437.297 437.302 437.398 437.404 437.596 437.602 437.698
 437.703 437.897   437.9   437.9   437.9   437.9   437.9   437.9 437.897 437.703
 437.698 437.602 437.597 437.403 437.398 437.302 437.295 437.005 436.998 436.802
 436.798 436.702 436.698 436.636 436.634   436.6
    1000  1088.5 1088.75 1091.25  1091.5 1178.75 1181.25 1268.75 1271.25 1358.75
 1361.25 1430.75 1433.25 1502.75 1505.25 1574.75 1577.25 1646.75 1649.25 1718.75
 1721.25 1790.75 1793.25 1878.75 1881.25 1998.75 2001.25 2070.75 2073.25 2142.75
 2145.25 2214.75 2217.25 2293.75 2296.25 2358.75 2361.25 2430.75 2433.25 2573.75
 2576.25 2648.75 2651.25 2728.75 2731.25    2774
   441.5 441.598 441.599 441.601 441.602 441.699 441.701 441.799 441.803 441.997
 442.002 442.098 442.103 442.297 442.302 442.398 442.404 442.596 442.602 442.698
 442.703 442.897   442.9   442.9   442.9   442.9   442.9   442.9 442.897 442.703
 442.698 442.602 442.597 442.403 442.398 442.302 442.295 442.005 441.998 441.802
 441.798 441.702 441.698 441.636 441.634   441.6
   436.5 436.598 436.599 436.601 436.602 436.699 436.701 436.799 436.803 436.997
 437.002 437.098 437.103 437.297 437.302 437.398 437.404 437.596 437.602 437.698
 437.703 437.897   437.9   437.9   437.9   437.9   437.9   437.9 437.897 437.703
 437.698 437.602 437.597 437.403 437.398 437.302 437.295 437.005 436.998 436.802
 436.798 436.702 436.698 436.636 436.634   436.6
Pier Skew, UpSta & Num, DnSta & Num=  ,1090, 2 ,1090, 2 , 0 , 0 , 0 ,,
     2.5     2.5
       0     440
     2.5     2.5
       0     440
Pier Skew, UpSta & Num, DnSta & Num=  ,1180, 2 ,1180, 2 , 0 , 0 , 0 ,,
     2.5     2.5
       0     440
     2.5     2.5
       0     440
Pier Skew, UpSta & Num, DnSta & Num=  ,1270, 2 ,1270, 2 , 0 , 0 , 0 ,,
     2.5     2.5
       0     440
     2.5     2.5
       0     440
Pier Skew, UpSta & Num, DnSta & Num=  ,1360, 2 ,1360, 2 , 0 , 0 , 0 ,,
     2.5     2.5
       0     440
     2.5     2.5
       0     440
Pier Skew, UpSta & Num, DnSta & Num=  ,1432, 2 ,1432, 2 , 0 , 0 , 0 ,,
     2.5     2.5
       0     440
     2.5     2.5
       0     440
Pier Skew, UpSta & Num, DnSta & Num=  ,1504, 2 ,1504, 2 , 0 , 0 , 0 ,,
     2.5     2.5
       0     440
     2.5     2.5
       0     440
Pier Skew, UpSta & Num, DnSta & Num=  ,1576, 2 ,1576, 2 , 0 , 0 , 0 ,,
     2.5     2.5
       0     440
     2.5     2.5
       0     440
Pier Skew, UpSta & Num, DnSta & Num=  ,1648, 2 ,1648, 2 , 0 , 0 , 0 ,,
     2.5     2.5
       0     440
     2.5     2.5
       0     440
Pier Skew, UpSta & Num, DnSta & Num=  ,1720, 2 ,1720, 2 , 0 , 0 , 0 ,,
     2.5     2.5
       0     440
     2.5     2.5
       0     440
Pier Skew, UpSta & Num, DnSta & Num=  ,1792, 2 ,1792, 2 , 0 , 0 , 0 ,,
     2.5     2.5
       0     440
     2.5     2.5
       0     440
Pier Skew, UpSta & Num, DnSta & Num=  ,1880, 2 ,1880, 2 , 0 , 0 , 0 ,,
     2.5     2.5
       0     440
     2.5     2.5
       0     440
Pier Skew, UpSta & Num, DnSta & Num=  ,2000, 2 ,2000, 2 , 0 , 0 , 0 ,,
     2.5     2.5
       0     440
     2.5     2.5
       0     440
Pier Skew, UpSta & Num, DnSta & Num=  ,2072, 2 ,2072, 2 , 0 , 0 , 0 ,,
     2.5     2.5
       0     440
     2.5     2.5
       0     440
Pier Skew, UpSta & Num, DnSta & Num=  ,2144, 2 ,2144, 2 , 0 , 0 , 0 ,,
     2.5     2.5
       0     440
     2.5     2.5
       0     440
Pier Skew, UpSta & Num, DnSta & Num=  ,2216, 2 ,2216, 2 , 0 , 0 , 0 ,,
     2.5     2.5
       0     440
     2.5     2.5
       0     440
Pier Skew, UpSta & Num, DnSta & Num=  ,2295, 2 ,2295, 2 , 0 , 0 , 0 ,,
     2.5     2.5
       0     440
     2.5     2.5
       0     440
Pier Skew, UpSta & Num, DnSta & Num=  ,2360, 2 ,2360, 2 , 0 , 0 , 0 ,,
     2.5     2.5
       0     440
     2.5     2.5
       0     440
Pier Skew, UpSta & Num, DnSta & Num=  ,2432, 2 ,2432, 2 , 0 , 0 , 0 ,,
     2.5     2.5
       0     440
     2.5     2.5
       0     440
Pier Skew, UpSta & Num, DnSta & Num=  ,2575, 2 ,2575, 2 , 0 , 0 , 0 ,,
     2.5     2.5
       0     440
     2.5     2.5
       0     440
Pier Skew, UpSta & Num, DnSta & Num=  ,2650, 2 ,2650, 2 , 0 , 0 , 0 ,,
     2.5     2.5
       0     440
     2.5     2.5
       0     440
Pier Skew, UpSta & Num, DnSta & Num=  ,2730, 2 ,2730, 2 , 0 , 0 , 0 ,,
     2.5     2.5
       0     440
     2.5     2.5
       0     440
BR Coef= 1 , 0 , 0 ,1.05, 0 ,,,0.8,-1,0.5,1,
WSPro=,,,, 1 ,,,, 0 ,,,, 0 ,,,,-1 ,-1 ,-1 , 0 , 0 , 0 , 0 , 0
BC Design=,, 0 ,, 0 ,,,,,,
BC HTab HWMax=436.6
BC Use User HTab Curves=0
BC User HTab FreeFlow(D)= 0

Type RM Length L Ch R = 1 ,3119    ,1,1,1
BEGIN DESCRIPTION:
This cross section corresponds to cross section 3119 of the non-georeferenced CDC model which was the source of this model.
END DESCRIPTION:
XS GIS Cut Line= 3
2459466.637857596980178.474438132458826.652588996979475.10839079
2458275.535909096978863.81269738
#Sta/Elev= 30
    1000   436.5    1000   434.5    1060   414.9    1178     408    1430   410.8
 1790.75   410.7    1848   409.3    1874   401.2    1885   396.9  1887.5   396.9
    1897   392.6    1925   390.3    1974   383.5    1990   383.8    1996   388.5
    2011   393.8    2021   393.8    2030   398.3    2061   398.3 2073.25 401.084
  2100.5   411.4  2222.5   410.8 2361.25   411.9  2437.5   411.8    2585   413.3
    2607   415.1  2702.5   419.1  2721.7   420.9  2741.9   421.2    2774   436.6
#Mann= 4 ,-1,0
    1000     .03       0    1178     .07       0    1848    .035       0
  2100.5     .07       0
Bank Sta=1848,2100.5
XS Rating Curve= 0 ,0
Exp/Cntr=0.5,0.3

Type RM Length L Ch R = 1 ,3118    ,99,99,99
BEGIN DESCRIPTION:
This cross section corresponds to cross section 3118 of the non-georeferenced CDC model which was the source of this model.
One-foot downstream of Shady Grove Road.  Duplication of following bridge cross-section (3119) without bridge piers.  Channel data from COD Elm Fork channel survey.
END DESCRIPTION:
XS GIS Cut Line= 3
2459467.939364176980177.220831722458827.149635266979474.23831379
2458276.238335526978863.11223947
#Sta/Elev= 30
    1000   436.5    1000   434.5    1060   414.9    1178     408    1430   410.8
 1790.75   410.7    1848   409.3    1874   401.2    1885   396.9  1887.5   396.9
    1897   392.6    1925   390.3    1974   383.5    1990   383.8    1996   388.5
    2011   393.8    2021   393.8    2030   398.3    2061   398.3 2073.25 401.084
  2100.5   411.4  2222.5   410.8 2361.25   411.9  2437.5   411.8    2585   413.3
    2607   415.1  2702.5   419.1  2721.7   420.9  2741.9   421.2    2774   436.6
#Mann= 4 ,-1,0
    1000     .03       0    1178     .07       0    1848    .035       0
  2100.5     .07       0
#XS Ineff= 2 , 0
            1848   409.3  2100.5           411.4
Permanent Ineff=
       F       F
Bank Sta=1848,2100.5
XS Rating Curve= 0 ,0
Exp/Cntr=0.3,0.1

Type RM Length L Ch R = 1 ,3013    ,0,0,0
BEGIN DESCRIPTION:
This cross section corresponds to cross section 3013 of the non-georeferenced CDC model which was the source of this model.
Cross-section EF001.  3013 feet upstream of West Fork/Elm Fork confluence.
106 feet downstream of Shady Grove Road.  McPeeter's property in ROB downstream to West Fork/Elm Fork confluence.  Effective flow limit set at East Levee in LOB, at sta 2810 in ROB.  Channel data from COD Elm Fork channel survey - cross-section EF#001 surveyed February 1994.
END DESCRIPTION:
XS GIS Cut Line= 3
2459501.03050533 6980073.93002782458285.60905167 6978741.9130068
2458116.621856846978602.92345539
#Sta/Elev= 30
    1017   436.1    1017     436    1106   410.5    1148   408.1    1212   407.3
    1273   409.7    1412   410.9    1767   410.6    1828   409.1    1875   393.7
    1954  383.54    1970   383.8    1976   388.5    1991   393.8    2001   393.8
    2010   398.4    2041   398.3    2083     413    2102   413.8    2119   413.9
    2136     411    2485   411.7    2553   412.7    2678     418    2800     427
    2844   428.6    2967   437.8    2990   438.5    3010   442.7    3039   443.8
#Mann= 4 ,-1,0
    1017     .03       0    1106     .07       0    1828    .035       0
    2102     .09       0
#XS Ineff= 3 ,-1
    1000    1828   409.3    2083    2810     411    2810    3039     440
Permanent Ineff=
       F       F       F
Bank Sta=1828,2083
XS Rating Curve= 0 ,0
Exp/Cntr=0.3,0.1

River Reach=West Fork       ,wf2
Reach XY= 30
      2423548.65      6969142.43      2423976.25      6968970.81
      2424403.02      6968655.85      2425023.17      6967744.39
      2425959.14      6966962.71      2426098.85       6966734.7
      2426227.36      6966224.62      2426380.15      6965972.72
       2427305.8      6965022.61      2427810.75      6964721.15
      2427940.56      6964501.17      2427981.58      6964249.07
      2428077.14      6964069.59      2428334.72      6963893.06
      2429276.94      6963774.78      2431694.52      6963801.24
       2432063.1      6963714.52      2433284.44      6963187.31
      2433611.14      6963093.15      2434417.15      6963019.71
      2434599.32      6963059.56      2436019.26      6962867.72
      2436877.34      6963058.67      2437797.07      6963587.52
      2438107.52       6963832.5      2438354.79      6964195.56
      2438435.95      6964465.48      2438436.94      6964747.33
      2438287.28      6965275.21        2438660.      6965610.97

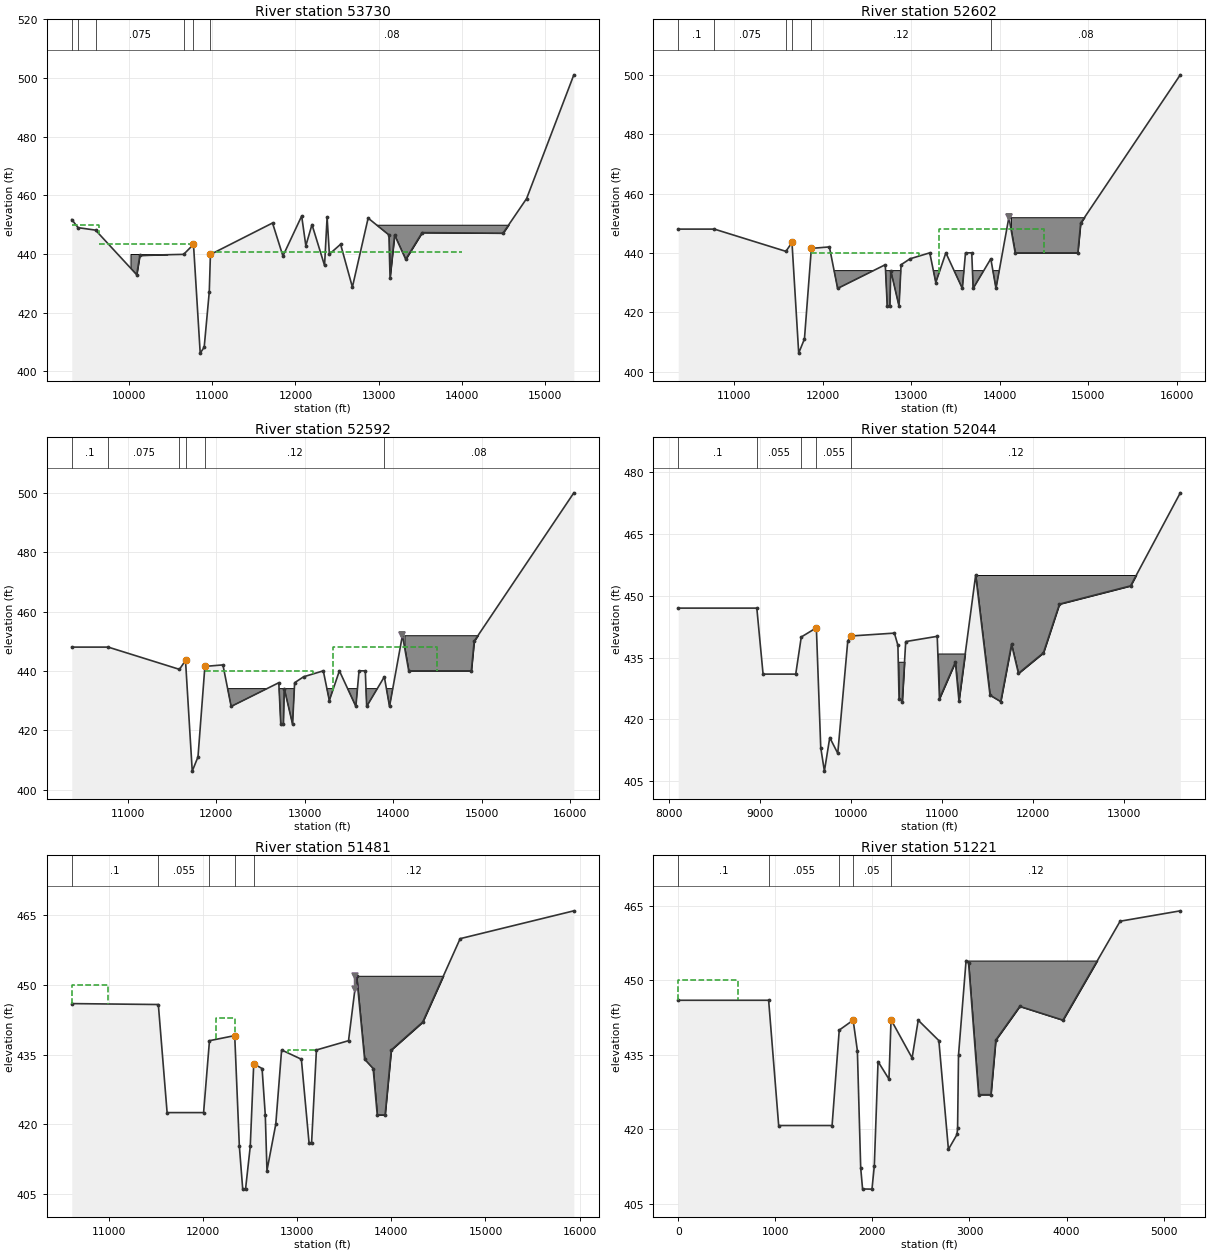
Type RM Length L Ch R = 1 ,53730   ,1050,1128,1160
BEGIN DESCRIPTION:
XS 49628 - 53730 represent Wildlife Phase 3 South STA 9371 - 9594
53730
Adjusted for Wildlife Parkway
W.U.S MITIGATION MODELED ON THE LEFT OVERBANK
---------------------------------------------------------------------
CDC GP 121713-1 Wildlife Parkway Extension
Cross-section 53730 - 57303
---------------------------------------------------------------------
END DESCRIPTION:
XS GIS Cut Line= 4
  2425618.181613 6969154.5383999 2425503.5053337 6969080.5890727
 2424447.2065933 6969113.7399251 2421347.8049837 6965388.1781505
#Sta/Elev= 30
  9308.5  451.77    9384     449 9594.43  448.1510089.92  432.9410127.66  439.54
10654.59  439.8910773.27  443.28   10854   406.210902.07  408.2210963.26  427.17
10976.92  439.8411724.21  450.5811849.28  439.3312074.96  452.9612125.07  442.84
12199.08  450.04 12350.3  436.0912380.95  452.5412408.42  439.9512543.23  443.33
12685.31  428.7112874.73  452.2513124.42  446.5313138.41  431.9913193.28  446.47
13326.78   438.213524.51   447.314497.79  447.11 14781.7  458.9215350.08  501.12
#Mann= 6 ,-1,0
  9308.5    .075       0    9384      .1       0 9594.43    .075       0
10654.59     .12       010773.27     .05       010976.92     .08       0
#XS Ineff= 3 ,-1
    9308    9640     450    964010773.27   443.510976.92   14000   440.6
Permanent Ineff=
       F       F       F
#Block Obstruct= 2 ,-1
   1001510457.41     440   12874 15295.7     450
Bank Sta=10773.27,10976.92
XS Rating Curve= 0 ,0
Exp/Cntr=0.3,0.1

Type RM Length L Ch R = 1 ,52602   ,10,10,10
BEGIN DESCRIPTION:
XS 49628 - 53730 represent Wildlife Phase 3 South STA 10367 - 10839
END DESCRIPTION:
XS GIS Cut Line= 2
  2425688.329439 6969039.7886294 2422343.5021393 6964470.8673211
#Sta/Elev= 30
10367.73     44810775.81     44811584.67   440.5   11653   443.5   11729   406.2
   11794     411   11872   441.512075.93     44212168.78     428 12707.3     436
12729.57     42212759.63     42212769.36     43412862.76     42212886.07     436
12987.36     438   13210     44013278.05     43013391.88     44013578.09     428
13613.85     44013684.46     44013700.16     42813899.75     43813958.43     428
 14104.3     45214175.25     440 14882.8     44014915.02     45016041.12     500
#Mann= 6 ,-1,0
10367.73      .1       010775.81    .075       011584.67     .11       0
   11653     .05       0   11872     .12       013899.75     .08       0
Levee=0,,,-1,14104,452,,
#XS Ineff= 3 ,-1
   10839   11653   443.5   11872   13091     440   13315   14500     448
Permanent Ineff=
       F       F       F
#Block Obstruct= 2 ,-1
   12000 14126.7     434 14126.7   15500     452
Bank Sta=11653,11872
XS Rating Curve= 0 ,0
Exp/Cntr=0.3,0.1

Type RM Length L Ch R = 1 ,52592   ,534,548,564
BEGIN DESCRIPTION:
XS 49628 - 53730 represent Wildlife Phase 3 South STA 10367 -  10839
END DESCRIPTION:
XS GIS Cut Line= 2
  2425696.419974 6969033.9110165 2422351.5710208 6964464.9601806
#Sta/Elev= 30
10367.73     44810779.81     44811584.67   440.5   11653   443.5   11729   406.2
   11794     411   11872   441.512075.93     44212168.78     428 12707.3     436
12729.57     42212759.63     42212769.36     43412862.76     42212886.07     436
12987.36     438   13210     44013278.05     43013391.88     44013578.09     428
13613.85     44013684.46     44013700.16     42813899.75     43813958.43     428
 14104.3     45214175.25     440 14882.8     44014915.02     45016041.12     500
#Mann= 6 ,-1,0
10367.73      .1       010779.81    .075       011584.67     .11       0
   11653     .05       0   11872     .12       013899.75     .08       0
Levee=0,,,-1,14104,452,,
#XS Ineff= 3 ,-1
   10839   11653     443   11872   13091     440   13315   14500     448
Permanent Ineff=
       F       F       F
#Block Obstruct= 2 ,-1
   12000 14126.7     434 14126.7   15500     452
Bank Sta=11653,11872
XS Rating Curve= 0 ,0
Exp/Cntr=0.3,0.1

Type RM Length L Ch R = 1 ,52044   ,536,563,656
BEGIN DESCRIPTION:
XS 49628 - 53730 represent Wildlife Phase 3 South STA 8099 - 8614
END DESCRIPTION:
XS GIS Cut Line= 3
  2425998.536167 6968969.3504501 2425800.2350552 6968309.3835941
  2423039.818332 6964351.0499754
#Sta/Elev= 30
  8098.9     447 8962.47     447 9031.15     431    9390     431  9450.9     440
 9616.73  442.22 9664.85  413.19 9704.95  407.48 9763.92  415.61 9851.93   411.8
 9962.03  439.0710000.92  440.2510474.42  440.94 10512.8  437.9810525.28  425.08
10560.14  424.3110598.62  438.8910944.88  440.1610969.28  425.0411143.93  433.89
 11183.9  424.5311367.29  455.0211524.82   425.911642.61  424.3411761.55  438.22
11837.22  431.1812112.17  436.1612288.03  447.97 13069.6  452.3913616.08  474.95
#Mann= 5 ,-1,0
  8098.9      .1       0 8962.47    .055       0  9450.9    .075       0
 9616.73    .055       010000.92     .12       0
#XS Ineff= 1 ,-1
    8800    9500     438
Permanent Ineff=
       T
#Block Obstruct= 3 ,-1
   10500   10600     434   10940   11350     43611367.29   13200  455.02
Bank Sta=9616.73,10000.92
XS Rating Curve= 0 ,0
Exp/Cntr=0.3,0.1

Type RM Length L Ch R = 1 ,51481   ,300,260,245
BEGIN DESCRIPTION:
This cross section corresponds to cross section 51481 of the non-georeferenced CDC model which was the source of this model.
END DESCRIPTION:
XS GIS Cut Line= 3
  2426680.862887  6968729.680654  2426607.379766  6968613.564416
  2423813.765931  6964208.897044
#Sta/Elev= 30
 10603.2     446 11523.2   445.8 11616.4   422.5 12004.2   422.512066.64     438
   12335   439.1   12384   415.3   12420     406   12450     406   12500   415.2
   12537     43312625.72     43212659.76     42212677.68     41012771.27     420
12833.26     43613043.35     43413124.76     41613151.95     416 13203.2     436
13544.49     43813630.45     45213715.48     43413806.11     43213849.61     422
13933.19     42213998.85     43614332.45     442 14730.7     46015939.03     466
#Mann= 5 ,-1,0
 10603.2      .1       0 11523.2    .055       012066.64     .09       0
   12335    .055       0   12537     .12       0
Levee=0,,,-1,13612.76,452,,
#XS Ineff= 5 ,-1
 10603.2   10983     450   11470   12134   437.8   12134   12335     443
   12600   12900     432   12900   13205     436
Permanent Ineff=
       F       T       F       T       T
#Block Obstruct= 1 ,-1
13630.4514601.83     452
Bank Sta=12335,12537
XS Rating Curve= 0 ,0
Exp/Cntr=0.3,0.1

Type RM Length L Ch R = 1 ,51221   ,236,243,229
XS GIS Cut Line= 4
  2426884.356247  6968657.180471  2426570.119998  6967857.267372
  2425817.515861  6966914.558956   2424111.78666  6964318.204897
#Sta/Elev= 30
       0     446  931.31     446 1034.66   420.8 1584.94   420.8 1658.54     440
 1801.86     442 1845.37  435.87 1879.65  412.28 1898.99  408.03 1995.92     408
 2019.97   412.7  2058.4  433.67 2170.93  430.13  2192.3  442.08 2409.23  434.39
 2472.28  441.99 2684.78  437.89 2783.37     416 2871.91     419 2877.83  420.26
 2887.26  434.96 2965.24     454 2990.75  453.55 3094.46     427 3221.29     427
 3271.54     438 3518.37  444.77 3963.29     442 4552.42  461.91 5172.24     464
#Mann= 5 ,-1,0
       0      .1       0  931.31    .055       0 1658.54     .09       0
 1801.86     .05       0  2192.3     .12       0
#XS Ineff= 2 ,-1
       0     620     450    2600    3000     436
Permanent Ineff=
       F       T
#Block Obstruct= 1 ,-1
    2980    4400     454
Bank Sta=1801.86,2192.3
XS Rating Curve= 0 ,0
Exp/Cntr=0.3,0.1

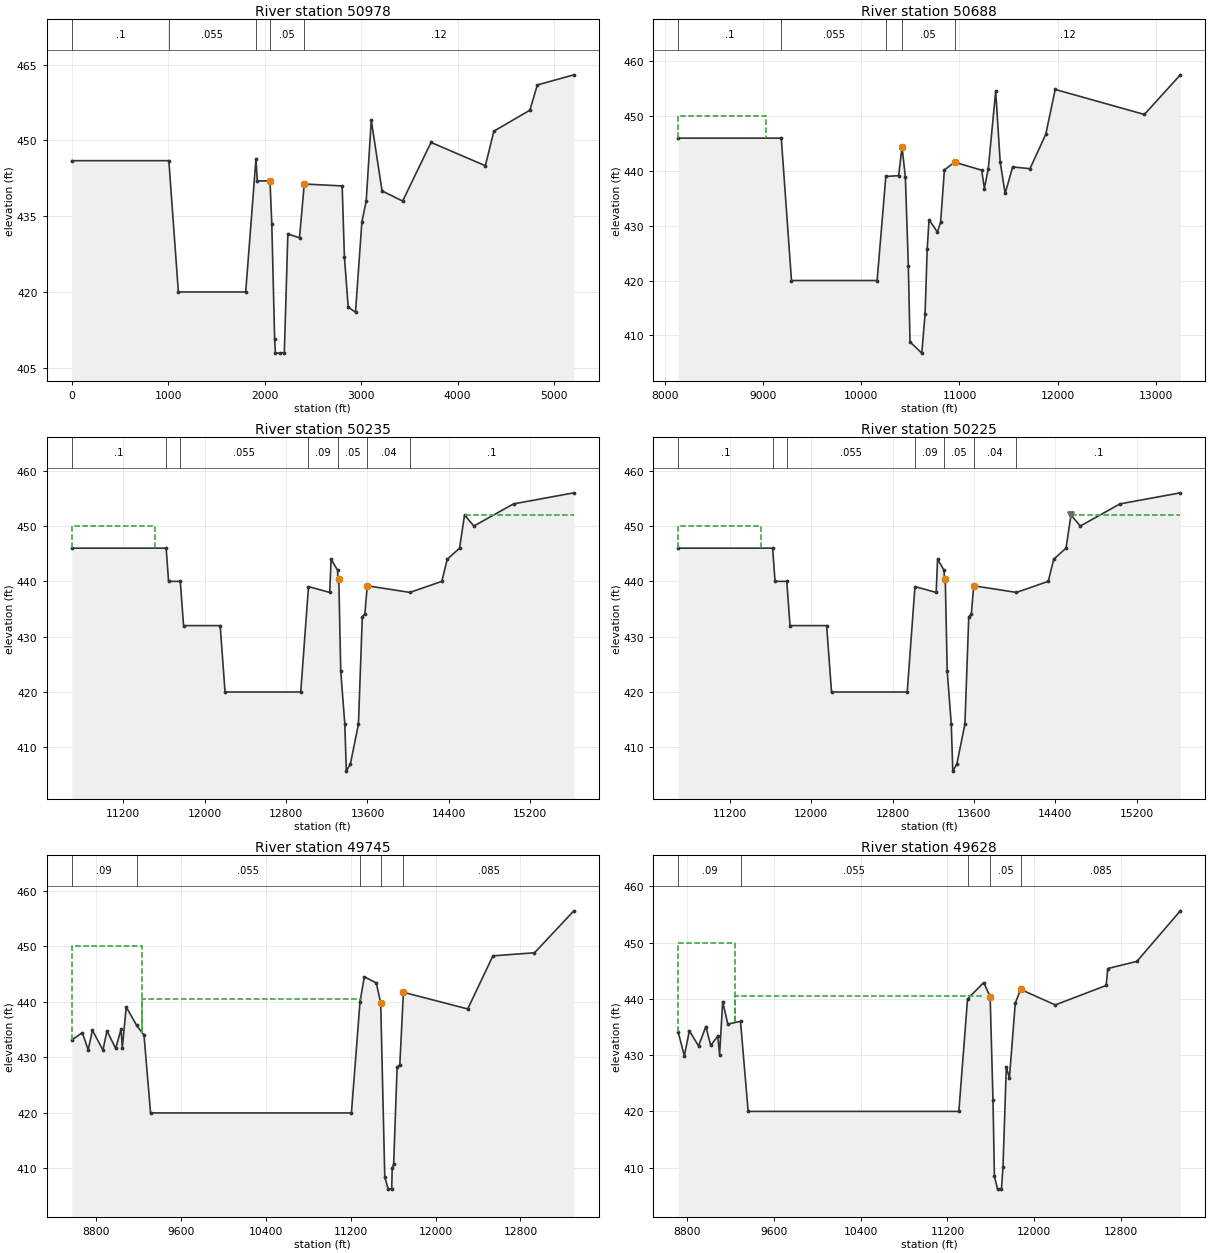
Type RM Length L Ch R = 1 ,50978   ,198,290,275
XS GIS Cut Line= 4
2427019.852038556968692.508812142426742.074378896967682.09186973
2425694.548258726966377.187327312424254.44418356 6964353.9669643
#Sta/Elev= 30
       0     446 1006.21     446    1105     420    1803     420  1909.5  446.37
 1922.77     442 2054.83     442  2073.6  433.46 2102.92  410.75 2110.88  407.93
 2157.76  407.89 2203.45  408.01    2240  431.48 2360.85  430.73 2410.01  441.38
 2803.04     441 2826.12     427 2865.55     417 2941.28     416 3007.18  433.82
 3052.12     438 3104.84     454 3216.45  440.01 3429.73     438 3724.06  449.62
 4287.47     445 4375.68  451.84 4748.94     456 4826.34     461 5204.66     463
#Mann= 5 ,-1,0
       0      .1       0 1006.21    .055       0  1909.5     .09       0
 2054.83     .05       0 2410.01     .12       0
#XS Ineff= 1 ,-1
    2600    3200     436
Permanent Ineff=
       T
#Block Obstruct= 2 , 0
                            3124             454
Bank Sta=2054.83,2410.01
XS Rating Curve= 0 ,0
Exp/Cntr=0.3,0.1

Type RM Length L Ch R = 1 ,50688   ,363,453,371
BEGIN DESCRIPTION:
XS 49628 - 53730 represent Wildlife Phase 3 South STA 8132 - 9072
END DESCRIPTION:
XS GIS Cut Line= 4
  2427162.778261 6968710.1993936 2426930.0277431 6967628.3400087
 2424758.2190946 6964603.6980922 2424586.2775094 6964373.1316242
#Sta/Elev= 30
 8132.15     446 9182.97     446 9286.97     42010160.22     42010249.17     439
10380.04  439.1510414.26  444.4110448.36  438.8510478.64  422.6810495.47   408.8
10615.85  406.7410649.35   413.910670.83  425.7110689.73   431.110775.29  428.84
10807.93  430.67 10846.3   440.210949.96   441.611226.48  440.1511254.01  436.79
11293.58   440.411369.47  454.5811415.09  441.6611465.78  435.8911542.32  440.74
11719.02  440.4211879.97   446.711976.23  454.8912885.48  450.32   13252  457.56
#Mann= 5 ,-1,0
 8132.15      .1       0 9182.97    .055       010249.17     .09       0
10414.26     .05       010949.96     .12       0
#XS Ineff= 2 ,-1
 8132.15    9024     450    9150   10400     442
Permanent Ineff=
       T       F
#Block Obstruct= 2 , 0
                        11369.47          454.58
Bank Sta=10414.26,10949.96
XS Rating Curve= 0 ,0
Exp/Cntr=0.3,0.1

Type RM Length L Ch R = 1 ,50235   ,10,10,10
BEGIN DESCRIPTION:
XS 49628 - 53730 represent Wildlife Phase 3 South STA 10693 - 11607
END DESCRIPTION:
XS GIS Cut Line= 3
  2427752.276098 6968474.3071488 2425336.6391976 6964655.9870296
 2425114.4431197 6964314.3597601
#Sta/Elev= 30
 10693.3     44611620.95     44611644.94     440   11760     440   11792     432
   12152     432   12200     420   12944     420   13020  439.0513228.79     438
13242.36     44413306.29     44213309.57     440   13318   440.5   13337   423.8
   13377   414.2   13392   405.7   13432     407   13511   414.2   13549   433.6
   13574   434.1   13598   439.214017.33     43814330.51     44014383.82     444
14504.97     44614553.74     45214645.33     45015035.22     45415628.24     456
#Mann= 7 ,-1,0
 10693.3      .1       011620.95     .09       0   11760    .055       0
   13020     .09       013306.29     .05       0   13598     .04       0
14017.33      .1       0
#XS Ineff= 3 ,-1
 10693.3   11508     450   11578   13242   440.5 14553.715628.24     452
Permanent Ineff=
       T       F       F
Bank Sta=13318,13598
XS Rating Curve= 0 ,0
Exp/Cntr=0.3,0.1

Type RM Length L Ch R = 1 ,50225   ,557,480,415
BEGIN DESCRIPTION:
XS 49628 - 53730 represent Wildlife Phase 3 South STA 10693 - 11607
END DESCRIPTION:
XS GIS Cut Line= 2
  2427755.454898 6968460.6270581 2425127.0477533 6964302.6084712
#Sta/Elev= 30
 10693.3     44611620.95     44611644.94     440   11760     440   11792     432
   12152     432   12200     420   12944     420   13020  439.0513228.79     438
13242.36     44413306.29     44213309.57     440   13318   440.5   13337   423.8
   13377   414.2   13392   405.7   13432     407   13511   414.2   13549   433.6
   13574   434.1   13598   439.214017.33     43814330.51     44014383.82     444
14504.97     44614553.74     45214645.33     45015035.22     45415628.24     456
#Mann= 7 ,-1,0
 10693.3      .1       011620.95    .085       0   11760    .055       0
   13020     .09       013306.29     .05       0   13598     .04       0
14017.33      .1       0
Levee=0,,,-1,14553.7,452,,
#XS Ineff= 3 ,-1
 10693.3   11508     450   11578   13242   440.5 14553.715628.24     452
Permanent Ineff=
       T       F       F
Bank Sta=13318,13598
XS Rating Curve= 0 ,0
Exp/Cntr=0.3,0.1

Type RM Length L Ch R = 1 ,49745   ,145,118,103
BEGIN DESCRIPTION:
XS 49628 - 53730 represent Wildlife Phase 3 South STA 9090 - 9248
END DESCRIPTION:
XS GIS Cut Line= 4
  2428358.817208 6968186.4875145 2428327.5751449 6968097.6822459
 2427692.2112581 6967213.1712197 2425602.5632065 6964503.1097107
#Sta/Elev= 30
 8567.36  433.15 8667.32  434.47 8722.16  431.35 8762.13   434.9  8861.6  431.32
 8899.18   434.8 8981.77  431.62 9032.92  435.13  9043.9  431.67  9081.1   439.1
 9179.15  435.79 9248.89     434  9310.8     420 11205.8     42011286.62     440
 11327.3  444.5311440.04  443.4311481.94  439.8211520.39  408.4511552.84  406.27
 11585.9  406.3211590.55   410.111603.98  410.7111636.75  428.2411662.41  428.72
11696.17  441.7412302.97  438.7412540.89  448.3112932.94  448.8613304.18  456.42
#Mann= 5 ,-1,0
 8567.36     .09       0 9179.15    .055       011286.62     .09       0
11481.94     .05       011696.17    .085       0
#XS Ineff= 2 ,-1
 8567.36 9233.44     450 9233.4411307.44   440.5
Permanent Ineff=
       T       F
Bank Sta=11481.94,11696.17
XS Rating Curve= 0 ,0
Exp/Cntr=0.3,0.1

Type RM Length L Ch R = 1 ,49628   ,158,150,142
BEGIN DESCRIPTION:
XS 49628 - 53730 represent Wildlife Phase 3 South STA 9072 - 9257.
Wildlife North downstream bounding cross-section but is superceded by Wildlife Phase 3 Project (CDC GP 032919-01)
CDC Wildlife North GP 071217-01
Cross-section 49628 - 53730
Located in LOB
END DESCRIPTION:
XS GIS Cut Line= 5
  2428508.318221 6967986.8032026 2428127.0594698 6967507.9704988
 2427650.6335854 6967001.6083226 2426924.2994081 6965998.6451054
 2425629.9916293 6964371.8379916
#Sta/Elev= 30
 8720.83  434.04 8777.49  429.89 8823.49  434.33 8907.73  431.64 8975.28  435.08
 9019.76  431.73 9085.02  433.37  9101.7  430.09 9130.31  439.52 9177.19  435.52
 9294.39     436 9364.82     42011305.61     42011385.63     44011534.53  442.89
11593.84  440.3811620.06  421.9411633.19  408.4411662.56  406.1911698.27   406.3
11712.22   410.211742.65  427.9611770.95  425.8811825.14  439.2211874.03  441.68
12193.46  438.9212662.53  442.3812677.53  445.3912945.55  446.6613345.39  455.64
#Mann= 5 ,-1,0
 8720.83     .09       0 9294.39    .055       011385.63     .09       0
11593.84     .05       011874.03    .085       0
#XS Ineff= 2 ,-1
 8720.83 9247.19     450 9247.1911515.37   440.5
Permanent Ineff=
       T       F
Bank Sta=11593.84,11874.03
XS Rating Curve= 0 ,0
Exp/Cntr=0.3,0.1

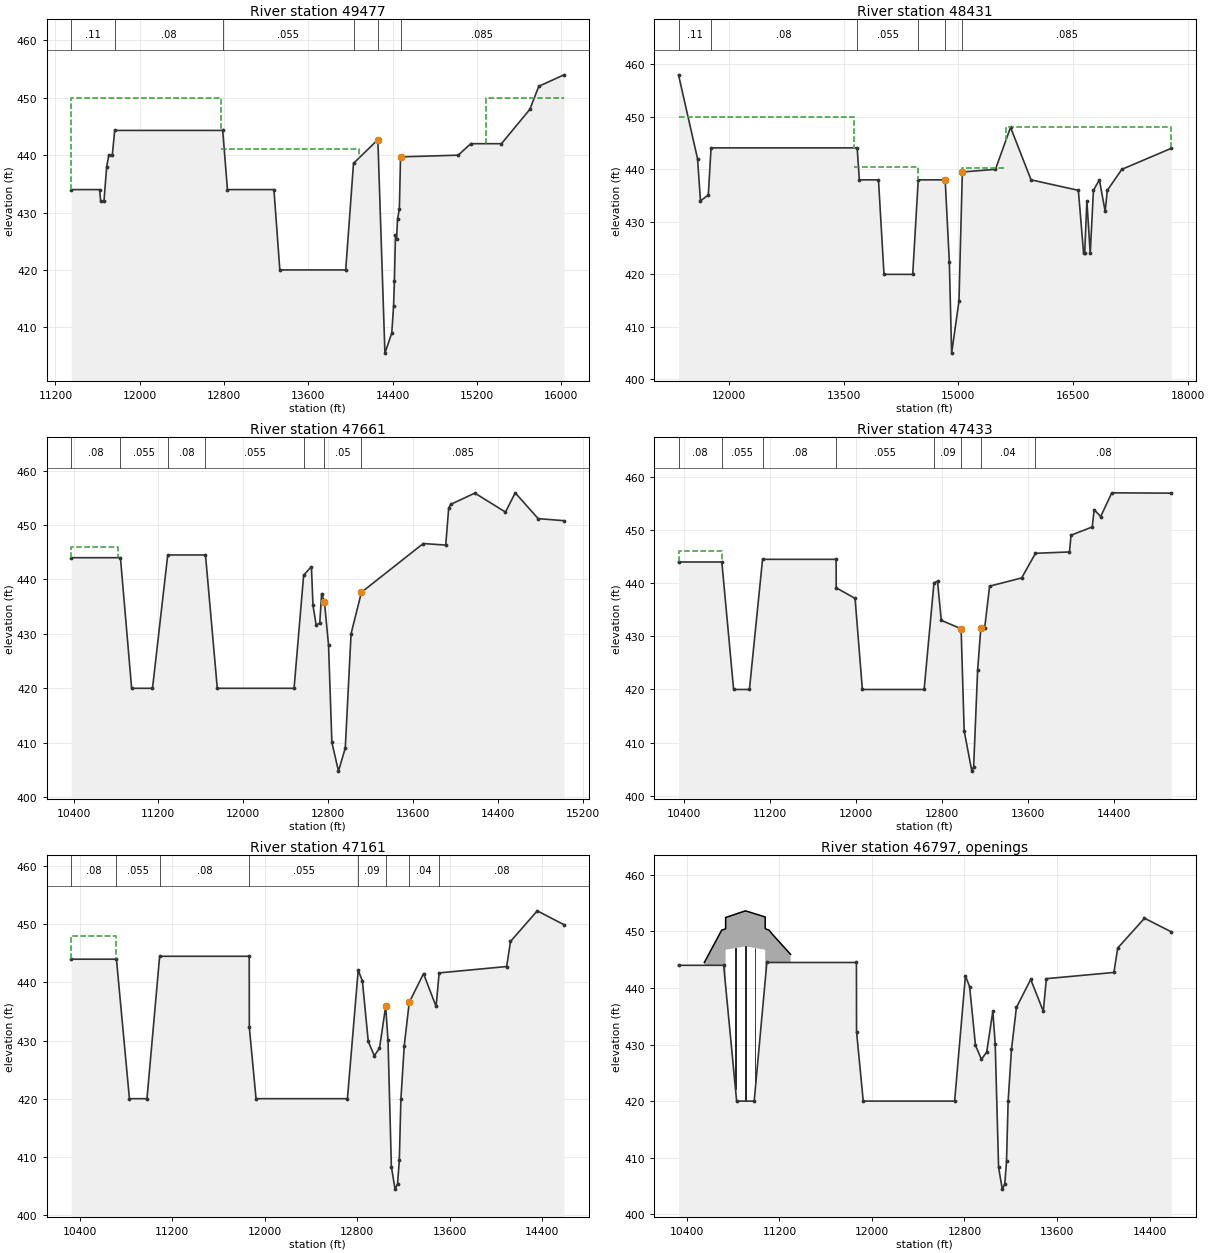
Type RM Length L Ch R = 1 ,49477   ,1046,1046,1046
BEGIN DESCRIPTION:
This cross section corresponds to cross section 49477 of the non-georeferenced CDC model which was the source of this model.
END DESCRIPTION:
XS GIS Cut Line= 4
  2428711.655741 6967912.2032861 2428675.8270731 6967868.9284383
 2425823.8537744 6964415.8713681 2425734.4172735 6964307.9112821
#Sta/Elev= 30
 11350.7     43411618.69     43411629.47     43211660.62     43211686.39     438
11706.55     44011739.65     440 11762.5  444.31 12787.2  444.31   12832     434
   13273     434   13329     420   13954     420   14028  438.58   14259   442.7
   14326   405.5   14391     409   14408   413.7   14416   418.1   14426     426
   14436   425.4   14446   428.9   14463   430.6   14474   439.715021.34     440
15140.64     44215431.75     44215701.23     44815785.65     45216024.91     454
#Mann= 6 ,-1,0
 11350.7     .11       0 11762.5     .08       0 12787.2    .055       0
   14028     .09       0   14259     .05       0   14474    .085       0
#XS Ineff= 3 ,-1
 11350.7   12774     450   12774   14080     441   1528716024.91     450
Permanent Ineff=
       T       F       F
Bank Sta=14259,14474
XS Rating Curve= 0 ,0
Exp/Cntr=0.3,0.1

Type RM Length L Ch R = 1 ,48431   ,817,770,682
BEGIN DESCRIPTION:
48431
END DESCRIPTION:
XS GIS Cut Line= 4
  2429560.894856 6967648.3107693  2429529.360471 6967586.9345797
 2425952.3564701 6962719.8176736 2425896.9766596  6962634.205312
#Sta/Elev= 30
11345.06     45811593.79     44211631.66     43411734.23  435.11   11770  444.09
   13678  444.09   13706     438   13956     438   14028     420   14403     420
   14475     43814826.82     438   14881   422.4   14911     405   15007   414.9
   15051   439.515483.35     44015680.21     44815948.16     43816565.71     436
 16634.2     424 16648.2     42416676.96     43416720.76     42416762.65     436
 16839.9     43816915.85     43216943.54     43617133.41     44017778.15     444
#Mann= 6 ,-1,0
11345.06     .11       0   11770     .08       0   13678    .055       0
   14475      .1       014826.82    .055       0   15051    .085       0
#XS Ineff= 4 ,-1
11345.06   13632     450   13632   14475   440.5   1505115615.97   440.2
15615.9717778.15     448
Permanent Ineff=
       T       F       F       F
Bank Sta=14826.82,15051
XS Rating Curve= 0 ,0
Exp/Cntr=0.3,0.1

Type RM Length L Ch R = 1 ,47661   ,199,228,188
BEGIN DESCRIPTION:
XS added for Wildlife Building 10 with 2016 Grand Prairie topo
END DESCRIPTION:
XS GIS Cut Line= 3
  2429065.657986 6966465.6687776 2428996.8028091 6965451.1396387
 2426611.3492466 6962716.0112507
#Sta/Elev= 30
   10379     44410842.35     44410947.94     42011144.66     42011288.21   444.5
 11644.3   444.511755.69     420 12479.6     42012569.79  440.7812643.14  442.36
12658.14  435.2512687.58  431.6412721.98  431.9712739.32  437.37 12766.3  435.84
 12804.8   427.912836.19  410.0612898.56  404.7812962.56  409.0313017.19  430.02
 13114.8  437.6413697.63   446.613909.91  446.3213937.56  453.08 13954.9  453.78
14184.35  455.8714472.79  452.3914565.44  455.9214781.15  451.18 15025.1   450.8
#Mann= 7 ,-1,0
   10379     .08       010842.35    .055       011288.21     .08       0
 11644.3    .055       012569.79     .09       0 12766.3     .05       0
 13114.8    .085       0
#XS Ineff= 2 , 0
        10822.79     446
Permanent Ineff=
       F       F
Bank Sta=12766.3,13114.8
XS Rating Curve= 0 ,0
Exp/Cntr=0.3,0.1

Type RM Length L Ch R = 1 ,47433   ,183,272,308
BEGIN DESCRIPTION:
XS added for Wildlife Building 10 with 2016 Grand Prairie topo
END DESCRIPTION:
XS GIS Cut Line= 4
  2429162.525246 6966459.3305357 2429169.9028566 6965637.8144622
 2428980.2555981 6965139.1763519  2426850.302837 6962712.3842895
#Sta/Elev= 30
10347.29     444 10750.3     444 10859.9     42011006.96     42011129.19   444.5
11813.61   444.511814.47  439.1411989.93  437.1512057.89     42012632.42     420
12724.07  440.0812757.24  440.37 12791.9  433.0212976.54  431.4313004.95  412.23
13076.21  404.6313093.06  405.44   13130  423.5913160.11   431.613196.12  431.65
13241.59  439.4513539.98     44113668.35  445.6413984.68  445.8913999.36  449.05
14196.36  450.5914214.55  453.8614274.95  452.5414378.25  457.0214931.26  456.96
#Mann= 8 ,-1,0
10347.29     .08       0 10750.3    .055       011129.19     .08       0
11813.61    .055       012724.07     .09       012976.54     .05       0
13160.11     .04       013668.35     .08       0
#XS Ineff= 2 , 0
           10750     446
Permanent Ineff=
       F       F
Bank Sta=12976.54,13160.11
XS Rating Curve= 0 ,0
Exp/Cntr=0.3,0.1

Type RM Length L Ch R = 1 ,47161   ,631,977,1132
BEGIN DESCRIPTION:
XS added for Wildlife Building 10 with 2016 Grand Prairie topo
END DESCRIPTION:
XS GIS Cut Line= 4
  2429204.552393 6966466.6146419 2429216.7052564 6965673.2120292
 2429036.3499741 6965026.4314987  2427444.770152 6962728.6887188
#Sta/Elev= 30
 10327.5     44410717.82     44410830.09     42010981.92     42011091.26   444.5
 11865.9   444.511866.84  432.2711924.77     42012714.87     42012808.21  442.12
12844.44  440.2312895.26  429.8412946.85   427.412992.14  428.6613045.46   435.9
13065.83  430.06   13095  408.2813126.94  404.4413148.31  405.34 13163.6  409.39
13177.42  419.9513206.32  429.1213249.24  436.5613372.89  441.51 13481.6  435.87
13507.94  441.6414092.01  442.7414124.92  447.0514356.57  452.3214587.58  449.93
#Mann= 8 ,-1,0
 10327.5     .08       010717.82    .055       011091.26     .08       0
 11865.9    .055       012808.21     .09       013045.46     .05       0
13249.24     .04       013507.94     .08       0
#XS Ineff= 2 , 0
        10717.82     448
Permanent Ineff=
       F       F
Bank Sta=13045.46,13249.24
XS Rating Curve= 0 ,0
Exp/Cntr=0.3,0.1

Type RM Length L Ch R = 4 ,46797   ,,,
BEGIN DESCRIPTION:
BLR Reclamation Bridge
END DESCRIPTION:
Node Name=BLR bridge
Bridge Culvert--1,0,-1,-1, 0
Deck Dist Width WeirC Skew NumUp NumDn MinLoCord MaxHiCord MaxSubmerge Is_Ogee
120,46,2.6,0, 14, 16, , , 0.95, 0, 0,0,,
10550.6910656.4510674.6310700.62 10726.610734.9510734.95   10906   11077   11077
11085.4411111.42 11137.411296.25
   444.5  448.53  449.22  450.21  450.39  450.45  452.45  453.63  452.55  450.55
  450.39  450.21  449.53  445.94
             435     435     435     435     435  446.75  447.35  446.75     435
     435     435     435
10374.3310389.4810495.2410513.4210539.4110565.3910573.7410573.7410744.7910915.79
10915.7910924.2310950.2110976.1911135.0411220.88
     444   444.5  448.53  449.22  450.21  450.39  450.45  452.45  453.63  452.55
  450.55  450.39  450.21  449.53  445.94     444
                     435     435     435     435     435  446.75  447.35  446.75
     435     435     435     435
Pier Skew, UpSta & Num, DnSta & Num=  ,10820.5, 2 ,10659.29, 2 , 0 , 0 , 0 ,,
       3       3
       0    1000
       3       3
       0    1000
Pier Skew, UpSta & Num, DnSta & Num=  ,10906, 2 ,10744.79, 2 , 0 , 0 , 0 ,,
       3       3
       0    1000
       3       3
       0    1000
Pier Skew, UpSta & Num, DnSta & Num=  ,10991.5, 2 ,10830.29, 2 , 0 , 0 , 0 ,,
       3       3
       0    1000
       3       3
       0    1000
BR Coef=-1 , 1 , 0 ,, 0 ,,,0.8,0,1.2,0,
WSPro=,,,, 1 ,,,, 0 ,,,, 0 ,,,,-1 ,-1 ,-1 , 0 , 0 , 0 , 0 , 0
BC Mult= 1 ,10293.5,10734.95,9992,10573.74
BC Mult= 3 ,10734.95,11077,10573.74,10915.79
BC Mult= 1 ,11077,14808.76,10915.79,14426.07
BC Design=,, 0 ,, 0 ,,,,,,
BC Use User HTab Curves=0
BC User HTab FreeFlow(D)= 0