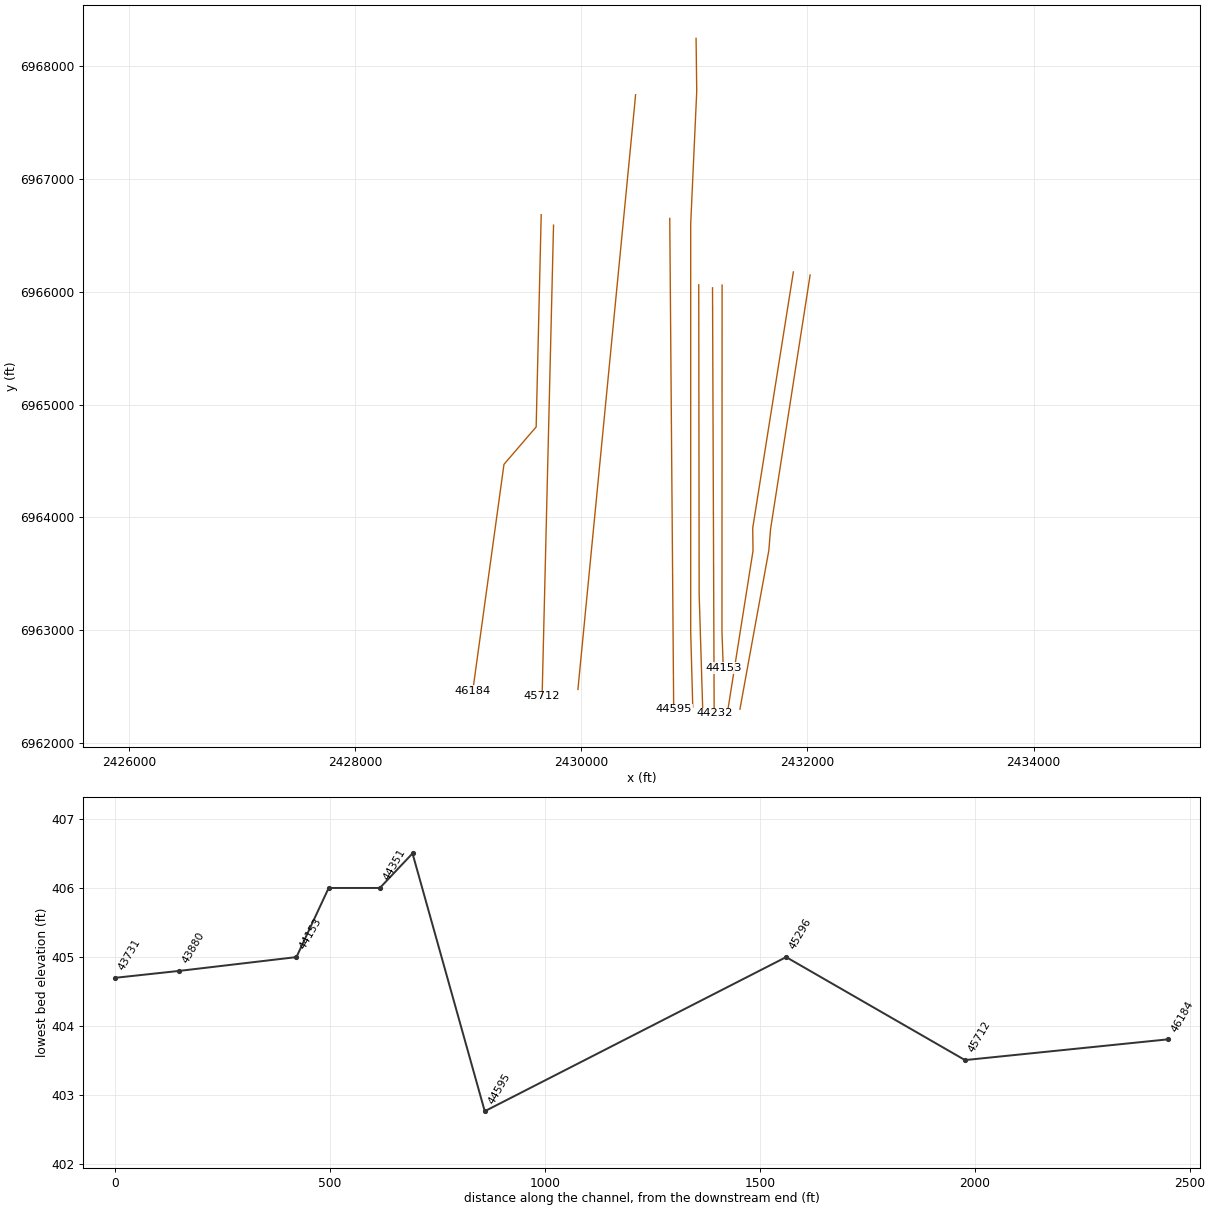
HEC-RAS study CDC_Consolidated_Model.prj: Upper Trinity CDC Consolidated Model

--- CDC_Consolidated_Model.g12 (geometry) --- (continued)

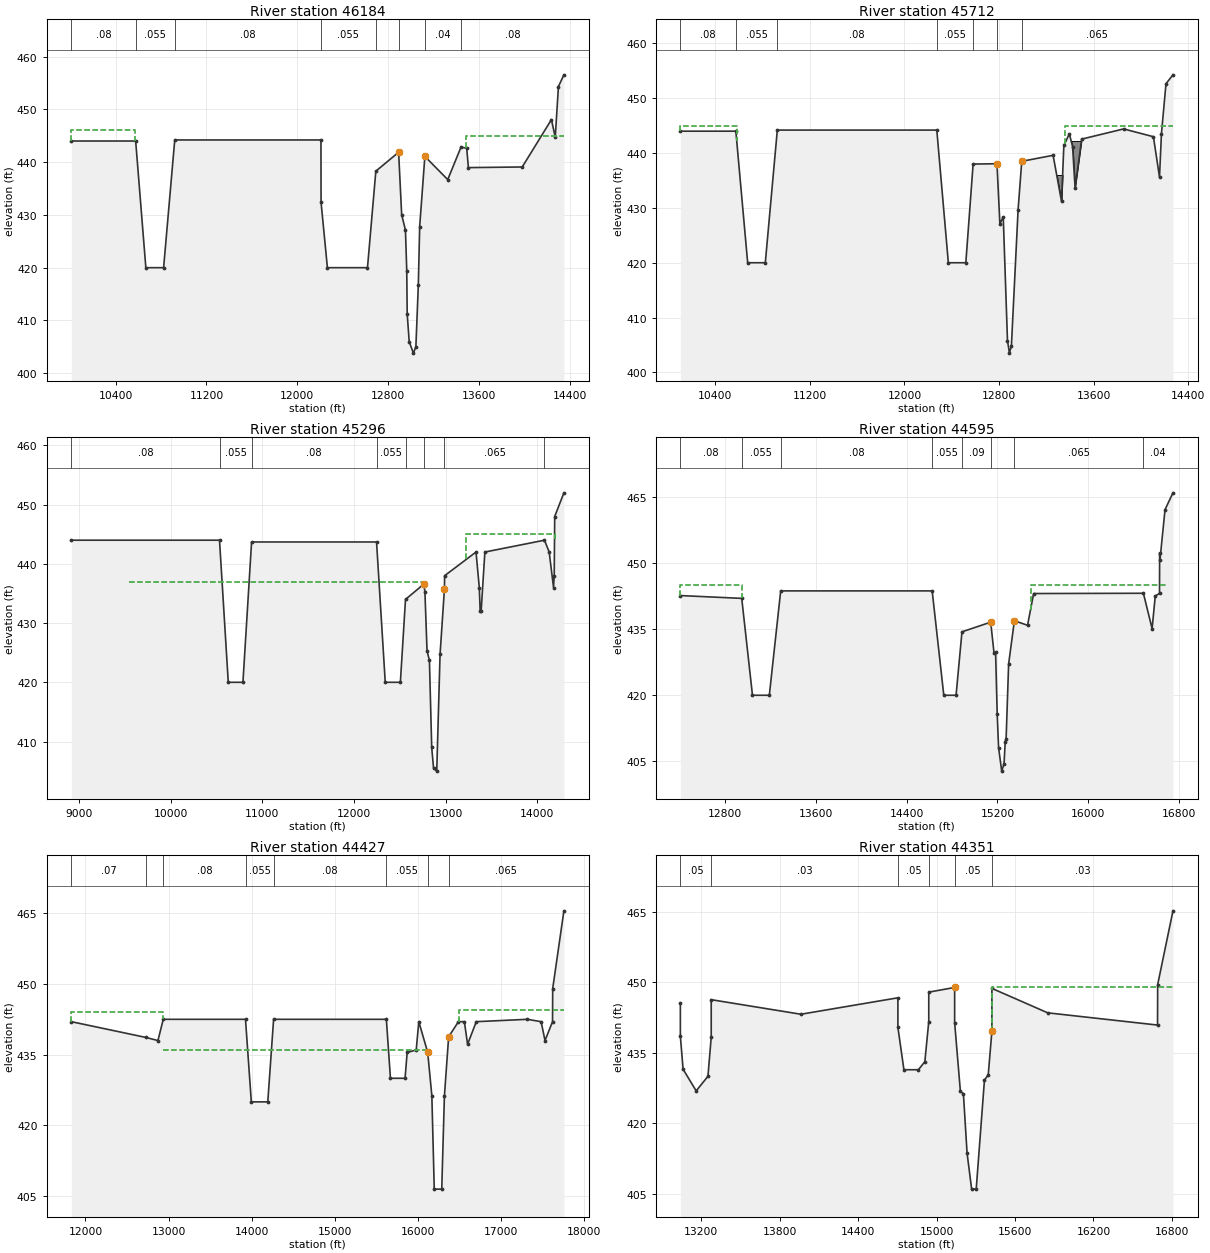
Type RM Length L Ch R = 1 ,46184   ,407,472,518
BEGIN DESCRIPTION:
XS added for Wildlife Building 10 with 2016 Grand Prairie topo
END DESCRIPTION:
XS GIS Cut Line= 4
  2429646.130578 6966680.3248444 2429601.4633451 6964801.7373942
 2429316.9468538 6964470.3955372 2429041.2292294 6962466.8939668
#Sta/Elev= 30
   10010     44410576.85     44410666.52     42010823.05     42010921.04   444.2
12208.73   444.212209.65  432.39 12265.5     42012618.49     42012692.09  438.29
 12892.7  441.8712919.52  430.02 12952.9  427.1112964.33  419.3812968.26  411.23
12985.99  405.9613022.84  403.8113044.66  405.0113066.18  416.6813078.15   427.8
13123.81  441.0813325.21  436.6913442.08  442.8413492.12  442.6513507.22  438.96
13981.37  439.0814238.46  448.0614272.08  444.6914300.09  454.3214348.24  456.54
#Mann= 8 ,-1,0
   10010     .08       010576.85    .055       010921.04     .08       0
12208.73    .055       012692.09     .09       0 12892.7     .05       0
13123.81     .04       013442.08     .08       0
#XS Ineff= 2 , 0
           10569     446   13488             445
Permanent Ineff=
       F       F
Bank Sta=12892.7,13123.81
XS Rating Curve= 0 ,0
Exp/Cntr=0.3,0.1

Type RM Length L Ch R = 1 ,45712   ,447,416,373
BEGIN DESCRIPTION:
XS added for Wildlife Building 10 with 2016 Grand Prairie topo
END DESCRIPTION:
XS GIS Cut Line= 2
  2429755.110019 6966588.2098711 2429654.0872556 6962416.1125723
#Sta/Elev= 30
   10105     44410574.23     44410674.25     42010823.33     42010924.95   444.2
 12273.8   444.2 12371.4     42012519.28     42012580.94     43812782.67  438.06
12807.31  427.1112835.69  428.3812871.62   405.812888.09  403.5112904.76  404.84
12961.34  429.6612992.24   438.513257.37   439.613328.53  431.2113348.35  441.39
13394.83   443.513422.13   441.213443.21  433.6813498.86  442.5513853.98  444.41
14105.87  442.9914157.24  435.6114173.66  443.5414212.21  452.6614271.12  454.28
#Mann= 7 ,-1,0
   10105     .08       010574.23    .055       010924.95     .08       0
 12273.8    .055       012580.94      .1       012782.67     .05       0
12992.24    .065       0
#XS Ineff= 2 , 0
        10581.75     445   13355             445
Permanent Ineff=
       F       F
#Block Obstruct= 2 ,-1
   13275   13385     436   13405   13505   442.2
Bank Sta=12782.67,12992.24
XS Rating Curve= 0 ,0
Exp/Cntr=0.3,0.1

Type RM Length L Ch R = 1 ,45296   ,659,701,761
BEGIN DESCRIPTION:
45296
Cross Section Truncated due to Ineffective Flow Areas, PROPOSED EXCAVATION SWALE MODIFIED FROM CLOMR SUBMITTED TO CITY OF GRAND PRAIRIE ON JUNE 27, 2008, "SOUTHERN EXCAVATION SWALE WIDENED BY 20' TO MITIGATE A MINISCULE RISE CREATED IN THE CDC 100 YEAR WATER SURFACE ELEVATION
END DESCRIPTION:
XS GIS Cut Line= 3
  2430480.573135 6967742.5340061 2430473.1348301 6967662.0807549
 2429970.7290108 6962477.3115969
#Sta/Elev= 30
    8915     444 10532.4     444   10628     420   10788     420 10882.4   443.7
   12246   443.7   12341     420   12506     420   12562     434   12763   436.6
   12774   435.2   12797   425.3   12823   423.7   12848     409   12868   405.5
   12903     405   12939   424.7   12987   435.812988.63     43813331.47     442
13367.28     436 13376.8     43213387.32     43213428.19     44214078.53     444
14129.81     442 14177.4     43614184.87     43814190.12     44814290.43     452
#Mann= 8 ,-1,0
    8915     .08       0 10532.4    .055       0 10882.4     .08       0
   12246    .055       0   12562     .09       0   12763     .05       0
   12987    .065       014078.53     .04       0
#XS Ineff= 4 ,-1
 8994.18    9543  443.13    9543   12763     437   12987   13000   435.8
   13226   14188     445
Permanent Ineff=
       T       F       F       F
#Block Obstruct= 2 , 0
                        13331.47           442.2
Bank Sta=12763,12987
XS Rating Curve= 0 ,0
Exp/Cntr=0.3,0.1

Type RM Length L Ch R = 1 ,44595   ,166,168,159
BEGIN DESCRIPTION:
XS added for Wildlife Building 10 with 2016 Grand Prairie topo
END DESCRIPTION:
XS GIS Cut Line= 2
  2430782.792347 6966648.0850795 2430817.5147188 6962302.9248066
#Sta/Elev= 30
   12403  442.64 12944.3     44213039.08     42013187.76     42013288.05   443.7
14624.24   443.714726.68     42014835.04     42014887.11   434.415140.43   436.6
15169.51  429.6715183.65  429.7615197.96  415.6915210.07  408.11 15237.6  402.77
15258.28  404.4515268.62  409.4815276.35  409.9815298.68  427.0915349.41  436.92
15465.54  435.8915519.27   443.116487.54  443.1616564.22  435.1316592.21  442.54
16629.68  443.1416630.69  452.3216633.82  450.7616678.25  462.15 16748.3  465.97
#Mann= 8 ,-1,0
   12403     .08       0 12944.3    .055       013288.05     .08       0
14624.24    .055       014887.11     .09       015140.43     .05       0
15349.41    .065       016487.54     .04       0
#XS Ineff= 2 ,-1
   12403   12944     445   15492   16700     445
Permanent Ineff=
       F       F
Bank Sta=15140.43,15349.41
XS Rating Curve= 0 ,0
Exp/Cntr=0.3,0.1

Type RM Length L Ch R = 1 ,44427   ,76,76,76
BEGIN DESCRIPTION:
44427
Cross Section Truncated due to Ineffective Flow Areas
---------------------------------------------------------------------
CDC GP011017-1 I-30 Proposed Westbound Frontage Road
Cross-sections 44427 - 47265
--------------------------------------------------------------------
END DESCRIPTION:
XS GIS Cut Line= 6
  2431015.338798 6968242.3233608   2431015.80238 6968214.9284025
 2431021.3200855 6967773.5149152  2430968.011137 6966600.7118146
 2430967.9619245 6962988.1799977 2430986.1498802 6962321.3174863
#Sta/Elev= 30
   11830     442   12724  438.67   12872     438   12936   442.5   13925   442.5
   13995     425   14193     425   14263   442.5   15619   442.5   15668     430
   15844     430   15869  435.47   15978     436   16009     442   16116   435.5
   16166   426.3   16195   406.5   16285   406.5   16317   426.2   16368   438.8
   16486     442   16557     442   16596   437.2   16700     442   17315   442.5
   17480     442   17527     43817617.36     44217619.34     449   17754   465.5
#Mann= 8 ,-1,0
   11830     .07       0   12724     .09       0   12936     .08       0
   13925    .055       0   14263     .08       0   15619    .055       0
   16116     .05       0   16368    .065       0
#XS Ineff= 4 ,-1
   11830   12938     444   12938   16116     436   16368   16491   438.8
   16491   17754   444.5
Permanent Ineff=
       T       F       F       T
Bank Sta=16116,16368
XS Rating Curve= 0 ,0
Exp/Cntr=0.5,0.3

Type RM Length L Ch R = 1 ,44351   ,119,119,119
BEGIN DESCRIPTION:
Wildlife North 3 downstream bounding cross-section.
CDC GP 032919-01 Wildlife North 3
Cross-section 44351 - 58868
Located in LOB
END DESCRIPTION:
XS GIS Cut Line= 3
  2431039.082189  6966059.580351 2431042.6540323 6963323.0989473
 2431074.5719475 6962287.2240506
#Sta/Elev= 30
   13040   445.5   13040   438.5   13061   431.5   13161   426.9   13251     430
   13276   438.3   13276   446.3   13962   443.2   14704   446.7   14704   440.4
   14750   431.4   14861   431.4   14910   433.1   14940   441.6   14940   447.9
   15138   448.9   15138   441.4   15182   426.8   15205   426.3   15233   413.7
   15268     406   15303     406   15366   429.2   15395   430.3   15423   439.6
   15423   448.7   15850   443.5   16690   440.9   16691   449.5   16808   465.2
#Mann= 6 ,-1,0
   13040     .05       0   13276     .03       0   14704     .05       0
   14940     .03       0   15138     .05       0   15423     .03       0
#XS Ineff= 2 , 0
           15138     436   15423             449
Permanent Ineff=
       F       T
Bank Sta=15138,15423
XS Rating Curve= 0 ,0
Exp/Cntr=0.5,0.3

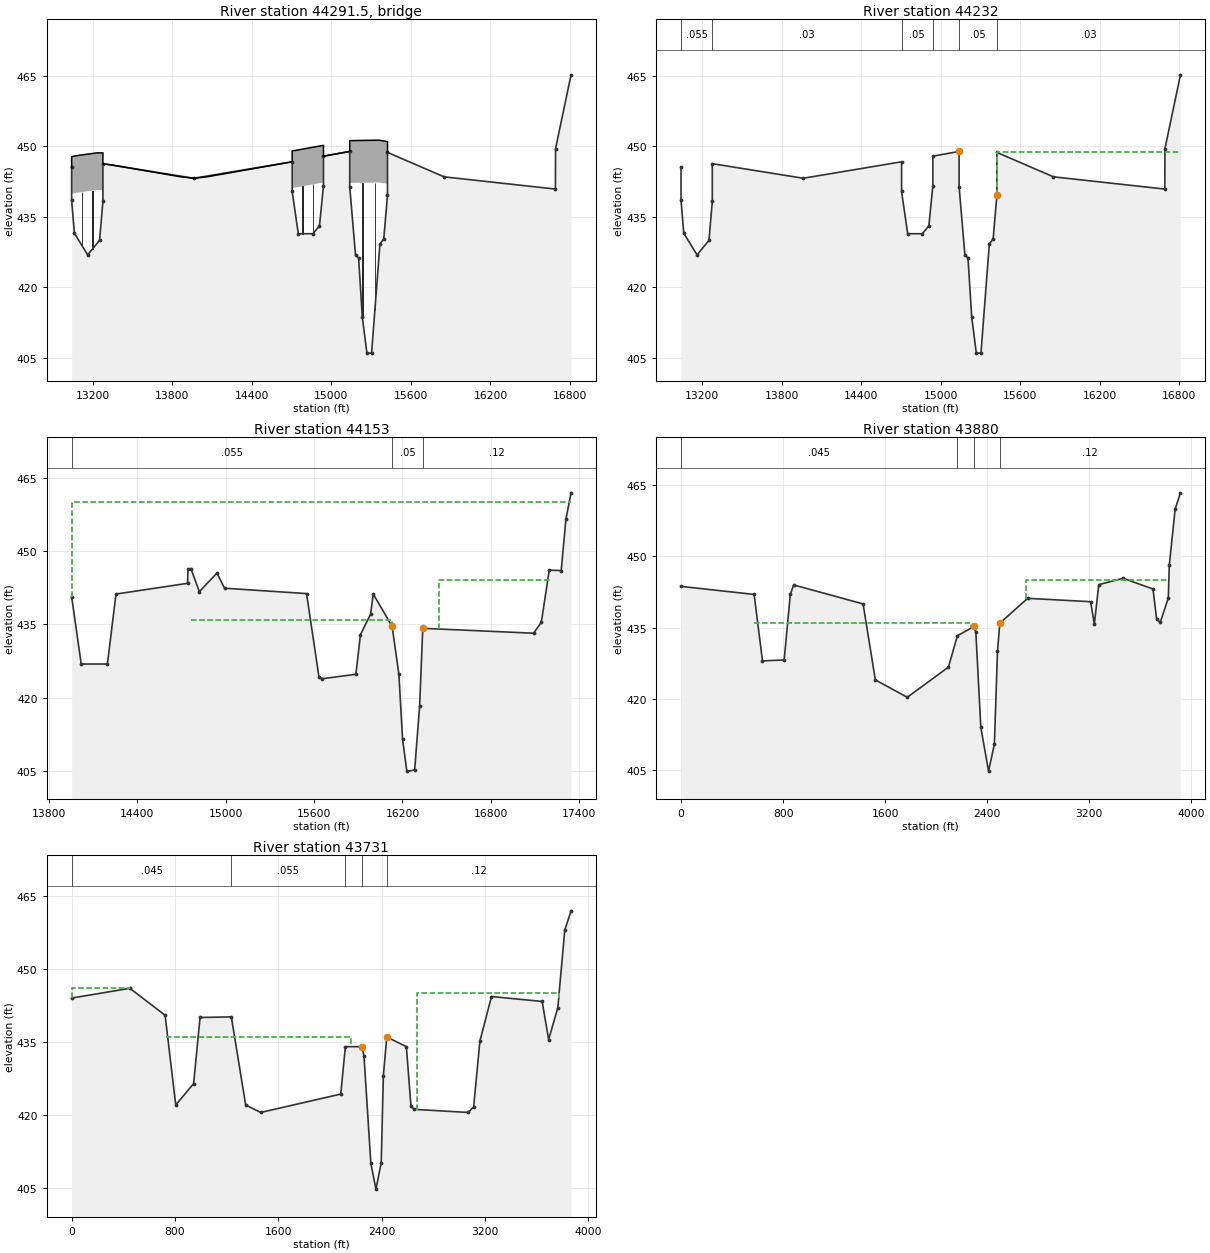
Type RM Length L Ch R = 3 ,44291.5 ,,,
BEGIN DESCRIPTION:
Belt Line Road
END DESCRIPTION:
Node Name=Belt Line Road
Bridge Culvert--1,0,-1,-1, 0
Deck Dist Width WeirC Skew NumUp NumDn MinLoCord MaxHiCord MaxSubmerge Is_Ogee
0.5,117,2.6,0, 19, 19, , , 0.95, 0, ,,,
   13040   13040   13100   13231   13276   13276   13350   13864   13962   14060
   14704   14704   14940   14940   15138   15138   15357   15423   15423
   445.5   447.8   448.1   448.6   448.6   446.3     446   443.5   443.2   443.5
   446.7     449   450.2   447.9   448.9   451.2   451.3     451   448.7
   445.5   439.9   440.2   440.7   440.7   446.3     446   443.5   443.2   443.5
   446.7   441.1   442.3   447.9   448.9   442.2   442.3     442   448.7
   13040   13040   13100   13231   13276   13276   13350   13864   13962   14060
   14704   14704   14940   14940   15138   15138   15357   15423   15423
   445.5   447.8   448.1   448.6   448.6   446.3     446   443.5   443.2   443.5
   446.7     449   450.2   447.9   448.9   451.2   451.3     451   448.7
   445.5   439.9   440.2   440.7   440.7   446.3     446   443.5   443.2   443.5
   446.7   441.1   442.3   447.9   448.9   442.2   442.3     442   448.7
Pier Skew, UpSta & Num, DnSta & Num=  ,13119, 2 ,13119, 2 , 0 , 0 , 0 ,,
     2.5     2.5
     400     444
     2.5     2.5
     400     444
Pier Skew, UpSta & Num, DnSta & Num=  ,13198, 2 ,13198, 2 , 0 , 0 , 0 ,,
     2.5     2.5
     400     444
     2.5     2.5
     400     444
Pier Skew, UpSta & Num, DnSta & Num=  ,14783, 2 ,14783, 2 , 0 , 0 , 0 ,,
     2.5     2.5
     400     444
     2.5     2.5
     400     444
Pier Skew, UpSta & Num, DnSta & Num=  ,14862, 2 ,14862, 2 , 0 , 0 , 0 ,,
     2.5     2.5
     400     444
     2.5     2.5
     400     444
Pier Skew, UpSta & Num, DnSta & Num=  ,15233, 2 ,15233, 2 , 0 , 0 , 0 ,,
       3       3
     400     444
       3       3
     400     444
Pier Skew, UpSta & Num, DnSta & Num=  ,15328, 2 ,15328, 2 , 0 , 0 , 0 ,,
       3       3
     400     444
       3       3
     400     444
BR Coef= 1 , 0 , 0 ,1.05, 0 ,,,0.8,-1,0.5,1,
WSPro=,,,, 1 ,,,, 0 ,,,, 0 ,,,,-1 ,-1 ,-1 , 0 , 0 , 0 , 0 , 0
BC Design=,, 0 ,, 0 ,,,,,,
BC HTab HWMax=449
BC Use User HTab Curves=0
BC User HTab FreeFlow(D)= 0

Type RM Length L Ch R = 1 ,44232   ,75,75,75
BEGIN DESCRIPTION:
This cross section corresponds to cross section 44253 of the non-georeferenced CDC model which was the source of this model.
Belt Line Road downstream bounding cross-section.
--------------------------------------------------------------------
CDC GP080808-1 Belt Line West Reclamation
Cross-section 44232 - 55761
Located in LOB.
New modeling by Halff adopted for this reach of river.  Includes revised cross-sections from 34268 - 53730, new split flow reach, revised split analysis over Hardrock Road.
END DESCRIPTION:
XS GIS Cut Line= 6
  2431160.980098 6966033.3046537 2431166.5697886 6964580.4396907
 2431169.5858587 6963796.2785293 2431169.9631545 6963698.2580561
 2431172.9638047 6962917.9804172 2431175.4516606 6962265.3324442
#Sta/Elev= 30
   13040   445.5   13040   438.5   13061   431.5   13161   426.9   13251     430
   13276   438.3   13276   446.3   13962   443.2   14704   446.7   14704   440.4
   14750   431.4   14861   431.4   14910   433.1   14940   441.6   14940   447.9
   15138   448.9   15138   441.4   15182   426.8   15205   426.3   15233   413.7
   15268     406   15303     406   15366   429.2   15395   430.3   15423   439.6
   15423   448.7   15850   443.5   16690   440.9   16691   449.5   16808   465.2
#Mann= 6 ,-1,0
   13040    .055       0   13276     .03       0   14704     .05       0
   14940     .03       0   15138     .05       0   15423     .03       0
#XS Ineff= 2 , 0
           15138     436   15423           448.7
Permanent Ineff=
       F       T
Bank Sta=15138,15423
XS Rating Curve= 0 ,0
Exp/Cntr=0.5,0.3

Type RM Length L Ch R = 1 ,44153   ,359,273,278
BEGIN DESCRIPTION:
This cross section corresponds to cross section 44153 of the non-georeferenced CDC model which was the source of this model.
Cross-section Truncated due to Ineffective Flow Areas
END DESCRIPTION:
XS GIS Cut Line= 6
  2431245.496262 6966057.5841621 2431245.2589357 6965391.9751411
 2431244.8645795 6964288.7201297 2431244.5771785 6963486.3532962
 2431244.3970608 6962984.8739841 2431255.9629825 6962666.7945678
#Sta/Elev= 30
   13954   440.7   14019   426.9   14197   426.9   14255   441.2   14741   443.4
   14744   446.3   14764   446.4   14821   441.7   14941   445.5   14992   442.4
   15549   441.3   15633   424.3   15657   423.9   15884   424.8   15915   432.9
   15984   437.1   16002   441.2   16130   434.6   16176   424.8   16201   411.5
   16230     405   16283   405.2   16317   418.4   16338   434.2   17090   433.2
   17143   435.4   17197   446.1   17278     446   17310   456.5   17345   461.9
#Mann= 3 ,0,0
   13954    .055       0   16130     .05       0   16338     .12       0
#XS Ineff= 3 ,-1
 13953.5   13954     460   14764   16130     436   16450   17209     444
Permanent Ineff=
       F       F       T
Bank Sta=16130,16338
XS Rating Curve= 0 ,0
Exp/Cntr=0.3,0.1

Type RM Length L Ch R = 1 ,43880   ,136,149,154
BEGIN DESCRIPTION:
This cross section corresponds to cross section 43880 of the non-georeferenced CDC model which was the source of this model.
OVERFLOW SWALE MODELED FROM STATIONS 580-856, FLOWLINE INTERPOLATED FROM THE EFFECTIVE PROFILE,  LEFT OVERBANK TAKEN FROM 1999 CGP TOPOGRAPHY, RIGHT OVERBANK TAKEN FROM COMBINATION OF 12/08 FIELD SURVEYS AND 1999 CGP TOPO
END DESCRIPTION:
XS GIS Cut Line= 6
  2431875.838436  6966174.324034 2431516.2954073 6963906.4269135
 2431517.6167176  6963805.331426 2431518.9380279 6963704.2359385
 2431311.8610553  6962392.4206782431298.20829234 6962305.9315693
#Sta/Elev= 30
       0  443.69  573.08     442  638.52     428  808.43  428.21  856.54     442
  883.18     444 1427.04     440 1522.94     424 1773.46  420.35 2095.65  426.69
 2165.99  433.29 2296.24  435.26 2310.67     434 2349.68     414    2410   404.8
 2455.82  410.48 2480.25     430 2498.45  435.96 2716.91  441.18  3210.4  440.47
 3239.14  435.75  3274.2  444.06 3463.87  445.39 3698.94  443.15 3727.83  436.73
 3756.48  436.18 3819.09  441.26 3826.52  448.11 3872.76  459.99 3914.08  463.39
#Mann= 4 ,-1,0
       0    .045       0 2165.99    .085       0 2296.24     .05       0
 2498.45     .12       0
#XS Ineff= 2 ,-1
     570    2273     436    2707    3824     445
Permanent Ineff=
       F       F
Bank Sta=2296.24,2498.45
XS Rating Curve= 0 ,0
Exp/Cntr=0.3,0.1

Type RM Length L Ch R = 1 ,43731   ,295,301,297
BEGIN DESCRIPTION:
This cross section corresponds to cross section 43731 of the non-georeferenced CDC model which was the source of this model.
OVERFLOW SWALE MODELED FROM STATIONS 740-994, FLOWLINE INTERPOLATED FROM THE EFFECTIVE PROFILE,  LEFT OVERBANK TAKEN FROM 1999 CGP TOPOGRAPHY, RIGHT OVERBANK TAKEN FROM COMBINATION OF 12/08 FIELD SURVEYS AND 1999 CGP TOPO
END DESCRIPTION:
XS GIS Cut Line= 5
      2432023.89      6966146.71 2431674.2286031 6963898.1235317
  2431666.452464 6963802.6154327  2431658.676325 6963707.1073337
  2431403.301283 6962302.6788034
#Sta/Elev= 30
       0     444  451.28     446  724.09  440.46  806.36     422  945.04  426.41
  994.42     440 1236.98  440.13 1347.98     422 1464.66  420.47 2084.31  424.25
 2120.18     434 2249.03     434 2264.52     432 2317.49     410    2357   404.7
 2397.76  410.13 2414.33     428 2440.68     436 2592.53     434 2628.08  421.79
 2652.29  421.11 3071.39  420.47 3113.68  421.61 3161.92  435.12 3251.93  444.31
 3644.28   443.3 3694.45  435.47 3765.38  441.97 3819.38  457.96 3868.15  461.94
#Mann= 5 ,-1,0
       0    .045       0 1236.98    .055       0 2120.18    .085       0
 2249.03     .05       0 2440.68     .12       0
#XS Ineff= 3 ,-1
       0  451.28     446     732    2167     436    2675    3771     445
Permanent Ineff=
       F       F       F
Bank Sta=2249.03,2440.68
XS Rating Curve= 0 ,0
Exp/Cntr=0.3,0.1