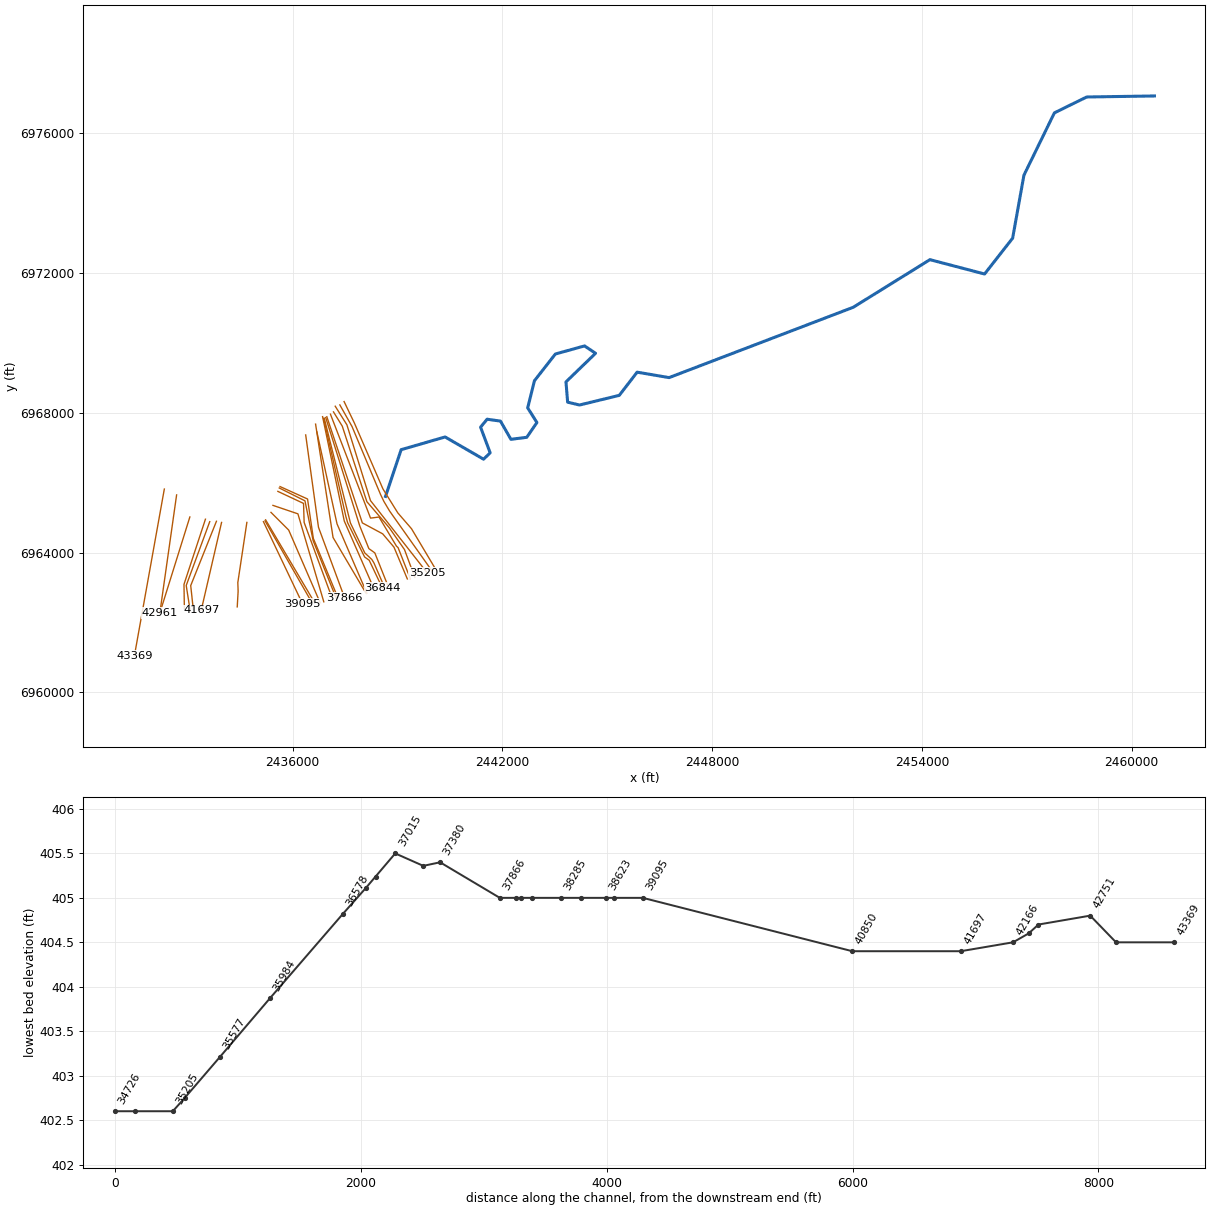
HEC-RAS study CDC_Consolidated_Model.prj: Upper Trinity CDC Consolidated Model

--- CDC_Consolidated_Model.g12 (geometry) --- (continued)

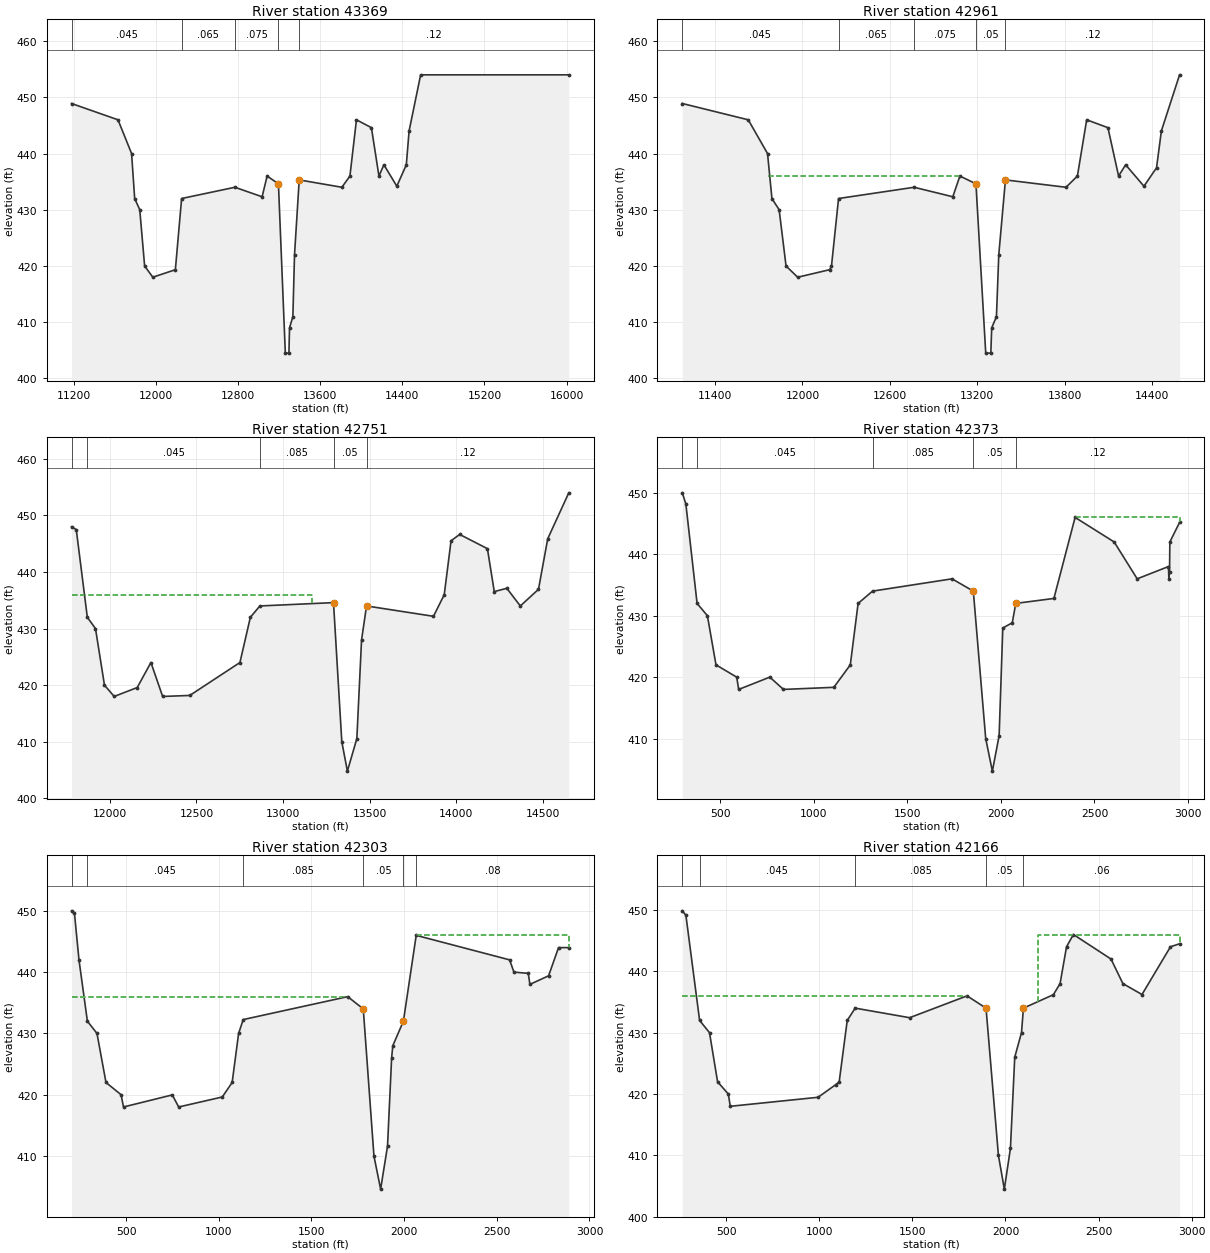
Type RM Length L Ch R = 1 ,43369   ,598,469,449
BEGIN DESCRIPTION:
This cross section corresponds to cross section 43369 of the non-georeferenced CDC model which was the source of this model.
FLOWLINE INTERPOLATED FROM THE EFFECTIVE PROFILE,  LEFT OVERBANK TAKEN FROM 1999 CGP TOPOGRAPHY, RIGHT OVERBANK TAKEN FROM COMBINATION OF 12/08 FIELD SURVEYS AND 1999 CGP TOPO
END DESCRIPTION:
XS GIS Cut Line= 4
      2432333.23      6965821.07      2431701.33      6962297.49
 2431521.0486329 6961291.85804072431477.723772866961050.18656578
#Sta/Elev= 30
   11175   448.911627.93     44611760.38     44011790.52     43211840.11     430
11887.49     42011967.34     41812187.15  419.3412248.12     43212767.37     434
13032.86  432.3113081.51     43613191.79  434.61   13259   404.5   13294   404.5
   13300     40913332.56  410.9813348.64     42213394.37  435.3113810.42     434
13888.69     43613952.35     44614098.21   444.6 14171.5     43614219.98     438
14345.71  434.1914438.47     43814465.51  444.0314578.05     45416021.98     454
#Mann= 5 ,-1,0
   11175    .045       012248.12    .065       012767.37    .075       0
13191.79     .05       013394.37     .12       0
#XS Ineff= 1 ,-1
13952.35   15757     446
Permanent Ineff=
       F
Bank Sta=13191.79,13394.37
XS Rating Curve= 0 ,0
Exp/Cntr=0.3,0.1

Type RM Length L Ch R = 1 ,42961   ,361,210,80
BEGIN DESCRIPTION:
This cross section corresponds to cross section 42961 of the non-georeferenced CDC model which was the source of this model.
FLOWLINE INTERPOLATED FROM THE EFFECTIVE PROFILE,  LEFT OVERBANK TAKEN FROM 1999 CGP TOPOGRAPHY, RIGHT OVERBANK TAKEN FROM COMBINATION OF 12/08 FIELD SURVEYS AND 1999 CGP TOPO
END DESCRIPTION:
XS GIS Cut Line= 6
  2432684.537395 6965652.8939046  2432579.281202 6964911.6617972
  2432509.852207 6964422.7520139 2432440.4209154 6963933.8425587
 2432329.3259932 6963151.5878896   2432204.33707   6962271.55192
#Sta/Elev= 30
   11175   448.911627.93     44611760.38     44011790.52     43211840.11     430
11887.49     42011967.34     41812187.15  419.3412199.64     42012248.12     432
12767.37     43413032.86  432.3113081.51     43613191.79  434.61   13259   404.5
   13294   404.5   13300     40913332.56  410.9813348.64     42213394.37  435.31
13810.42     43413888.69     43613952.35     44614098.21   444.6 14171.5     436
14219.98     43814345.71  434.1914432.07  437.4614465.51  444.0314590.27     454
#Mann= 5 ,-1,0
   11175    .045       012248.12    .065       012767.37    .075       0
13191.79     .05       013394.37     .12       0
#XS Ineff= 2 ,-1
   11763   13081     43613952.35   14502     442
Permanent Ineff=
       F       F
Bank Sta=13191.79,13394.37
XS Rating Curve= 0 ,0
Exp/Cntr=0.3,0.1

Type RM Length L Ch R = 1 ,42751   ,453,421,449
BEGIN DESCRIPTION:
This cross section corresponds to cross section 42751 of the non-georeferenced CDC model which was the source of this model.
FLOWLINE INTERPOLATED FROM THE EFFECTIVE CROSS SECTION AT STATIONS 13352-13417,  LEFT OVERBANK TAKEN FROM 1999 CGP TOPOGRAPHY, RIGHT OVERBANK TAKEN FROM COMBINATION OF 12/08 FIELD SURVEYS AND 1999 CGP TOPO
END DESCRIPTION:
XS GIS Cut Line= 6
  2433063.327041 6965021.7892554 2432846.3843423 6964327.1531237
 2432642.9375708 6963675.7607257 2432439.4825971 6963024.3699682
  2432323.218722 6962652.1469593 2432206.9518942 6962279.9246067
#Sta/Elev= 30
11778.45     44811805.86   447.511869.66     43211916.92     43011968.75     420
12024.87     41812157.98  419.5812237.08     42412304.79     41812461.61  418.18
12751.25     42412811.56     43212866.53     43413291.82  434.5913339.73     410
   13372   404.813426.67  410.5513453.89     42813482.62     43413869.39  432.17
13931.62     43613970.89  445.5314020.84  446.6414180.93  444.1314220.47  436.54
14293.02  437.1214371.02     43414475.93  436.9414529.31  445.8814650.94     454
#Mann= 5 ,-1,0
11778.45    .035       011869.66    .045       012866.53    .085       0
13291.82     .05       013482.62     .12       0
#XS Ineff= 2 ,-1
11778.45   13167     436 14020.8   14567     442
Permanent Ineff=
       F       F
Bank Sta=13291.82,13482.62
XS Rating Curve= 0 ,0
Exp/Cntr=0.3,0.1

Type RM Length L Ch R = 1 ,42373   ,120,80,115
BEGIN DESCRIPTION:
This cross section corresponds to cross section 42373 of the non-georeferenced CDC model which was the source of this model.
FLOWLINE INTERPOLATED FROM EFFECTIVE PROFILE, LEFT OVERBANK TAKEN FROM 1999 CGP TOPOGRAPHY, RIGHT OVERBANK TAKEN FROM COMBINATION OF 12/08 FIELD SURVEYS AND 1999 CGP TOPO
---------------------------------------------------------------------
CDC GP091010-1 Palace Parkway
Cross-section 42373 - 44153
Project located in ROB.
--------------------------------------------------------
END DESCRIPTION:
XS GIS Cut Line= 3
2433508.944494936964957.25519405     2432895.277     6963093.157
2432906.886390686962396.61470836
#Sta/Elev= 30
  295.93     450  314.92  448.19  374.96     432  430.07     430  476.03     422
  586.76     420  597.41     418   763.9     420  836.69     418  1106.2  418.34
 1194.35     422 1236.06     432  1313.4     434 1738.34     436 1852.17     434
 1918.41     410    1954   404.7 1990.21  410.47  2009.8     428  2060.5  428.85
 2079.19     432 2283.13  432.81 2396.44     446 2605.46     442 2728.51     436
 2895.74     438 2897.89     436 2901.53  437.14 2903.18     442 2955.08  445.18
#Mann= 5 ,-1,0
  295.93    .035       0  374.96    .045       0  1313.4    .085       0
 1852.17     .05       0 2079.19     .12       0
#XS Ineff= 2 ,-1
     296 1738.34     436  2396.4    2955     446
Permanent Ineff=
       F       F
Bank Sta=1852.17,2079.19
XS Rating Curve= 0 ,0
Exp/Cntr=0.3,0.1

Type RM Length L Ch R = 1 ,42303   ,156,127,134
BEGIN DESCRIPTION:
This cross section corresponds to cross section 42303 of the non-georeferenced CDC model which was the source of this model.
FLOWLINE INTERPOLATED FROM EFFECTIVE PROFILE, LEFT OVERBANK TAKEN FROM 1999 CGP TOPOGRAPHY, RIGHT OVERBANK TAKEN FROM COMBINATION OF 12/08 FIELD SURVEYS AND 1999 CGP TOPO
END DESCRIPTION:
XS GIS Cut Line= 3
2433632.049699456964887.02022063     2432959.499     6963061.046
2433073.200408496962332.74270938
#Sta/Elev= 30
   205.2     450  220.94  449.61   245.4     442  290.69     432  342.53     430
  391.09     422  472.58     420  485.64     418  748.94  419.97  783.24     418
 1018.61  419.63 1071.88     422 1106.71     430 1131.67  432.26 1695.34     436
 1779.36     434 1836.94     410    1873   404.6 1910.19  411.61 1932.32     426
 1938.81     428 1995.93     432    2065     446    2569     442 2592.29     440
 2669.56   439.8 2678.46     438 2779.26   439.4 2832.96     444 2888.22     444
#Mann= 6 ,-1,0
   205.2    .035       0  290.69    .045       0 1131.67    .085       0
 1779.36     .05       0 1995.93     .06       0    2065     .08       0
#XS Ineff= 2 , 0
            1695     436    2065             446
Permanent Ineff=
       F       F
Bank Sta=1779.36,1995.93
XS Rating Curve= 0 ,0
Exp/Cntr=0.3,0.1

Type RM Length L Ch R = 1 ,42166   ,242,425,444
BEGIN DESCRIPTION:
This cross section corresponds to cross section 42166 of the non-georeferenced CDC model which was the source of this model.
FLOWLINE INTERPOLATED FROM CURRENT EFFECTIVE GEOMETRY, LEFT OVERBANK TAKEN FROM 1999 CGP TOPOGRAPHY, RIGHT OVERBANK TAKEN FROM COMBINATION OF 12/08 FIELD SURVEYS AND 1999 CGP TOPO
END DESCRIPTION:
XS GIS Cut Line= 3
2433823.960378896964899.18512677     2433087.944     6963057.478
2433161.922816556962373.91147914
#Sta/Elev= 30
  264.32  449.86  283.58  449.15  357.19     432   410.4     430  453.72     422
  511.46     420  521.98     418   993.7  419.47 1087.57  421.51 1107.02     422
 1150.21     432 1192.85     434 1485.37  432.44 1793.75     436 1895.77     434
 1962.23     410    1994   404.5 2026.81  411.15 2049.93     426 2086.32  430.02
 2096.57     434 2257.51  436.19 2293.47     438 2328.05     444  2365.1     446
 2567.17     442 2630.76     438  2733.4  436.22 2886.42     444 2935.21  444.49
#Mann= 5 ,-1,0
  264.32    .035       0  357.19    .045       0 1192.85    .085       0
 1895.77     .05       0 2096.57     .06       0
#XS Ineff= 2 , 0
            1793     436    2176             446
Permanent Ineff=
       F       F
Bank Sta=1895.77,2096.57
XS Rating Curve= 0 ,0
Exp/Cntr=0.3,0.1

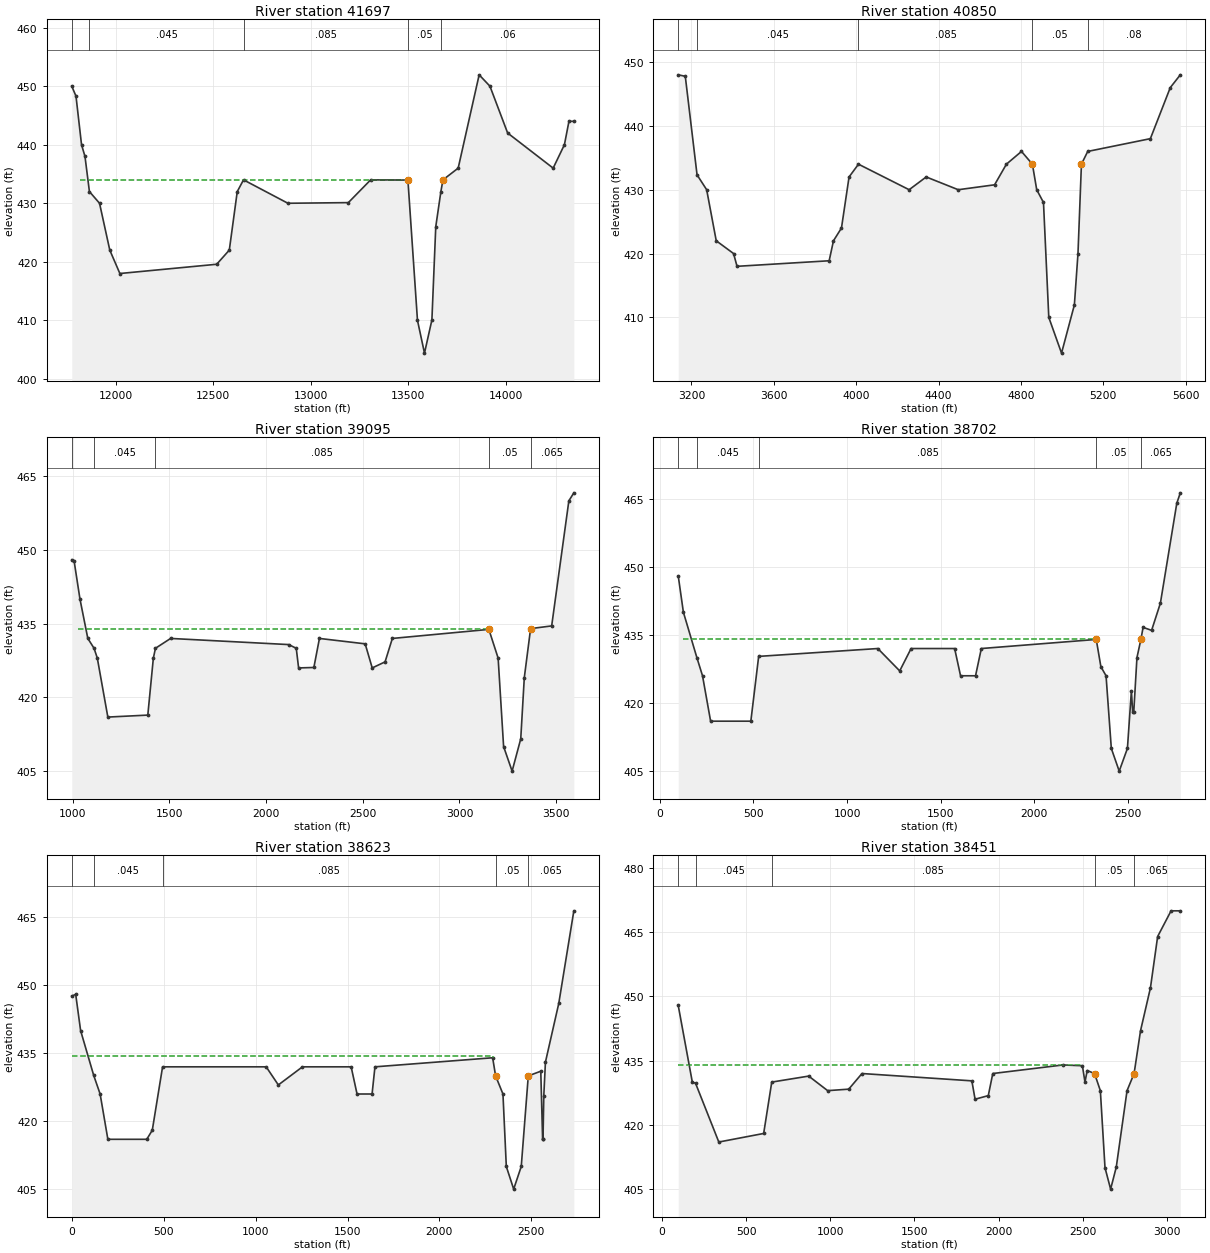
Type RM Length L Ch R = 1 ,41697   ,605,883,938
BEGIN DESCRIPTION:
This cross section corresponds to cross section 41697 of the non-georeferenced CDC model which was the source of this model.
FLOWLINE AND BOTTOM OF CHANNEL TAKEN FROM EFFECTIVE SECTION AT STATIONS 13563 AND 13583, TRANSITION TO 1999 CITY OF GRAND PRAIRIE TOPOGRAPHY AT STATION 13621,
LEFT OVERBANK STARTING AT STATION 13498 TO BEGIN OF XS TAKEN FROM 1999 CGP TOPOGRAPHY
-WAW
END DESCRIPTION:
XS GIS Cut Line= 6
  2433970.322007 6964865.2338734 2433862.5338848 6964399.7766662
 2433794.9539675 6964107.9563837 2433659.7901958 6963524.3161467
 2433524.6211748 6962940.6768941 2433389.4469045 6962357.0379695
#Sta/Elev= 30
11774.32     45011795.95   448.311824.39     44011842.06     438 11864.8     432
11916.68     43011969.25     422   12021     41812517.44  419.5812582.17     422
12622.92     43212655.07     43412882.71     43013192.61  430.1113307.01     434
   13498  433.9613547.05     410   13583   404.413621.02  410.0713640.86     426
13667.13     43213677.74     43413755.77     43613863.33  451.9413918.61     450
14009.42     44214242.81     43614300.56     44014323.81     444 14348.9     444
#Mann= 5 ,-1,0
11774.32    .035       0 11864.8    .045       012655.07    .085       0
   13498     .05       013667.13     .06       0
#XS Ineff= 1 ,-1
   11819   13498     434
Permanent Ineff=
       F
#Block Obstruct= 2 , 0
                           13860           451.7
Bank Sta=13498,13677.74
XS Rating Curve= 0 ,0
Exp/Cntr=0.3,0.1

Type RM Length L Ch R = 1 ,40850   ,1075,1704,1780
BEGIN DESCRIPTION:
This cross section corresponds to cross section 40850 of the non-georeferenced CDC model which was the source of this model.
END DESCRIPTION:
XS GIS Cut Line= 5
  2434693.981471 6964866.1636147 2434435.3497302 6963144.3570026
 2434439.7042704 6963020.3125196  2434444.058797 6962896.2685454
  2434418.596501 6962448.1952808
#Sta/Elev= 30
 3135.65     448 3169.88  447.77 3227.02  432.33 3273.69     430 3320.22     422
 3404.35     420 3421.19     418 3868.56  418.87 3889.49     422 3928.36     424
  3965.2     432 4010.95     434 4256.98     430 4339.81     432 4495.38     430
 4671.88  430.77 4729.27     434 4802.56     436 4855.51     434 4876.52     430
 4909.36     428 4935.12     410    4997   404.4 5059.37  411.95 5076.88     420
 5093.64     434 5124.21     436 5428.42     438 5525.08     446 5573.81     448
#Mann= 5 ,-1,0
 3135.65    .035       0 3227.02    .045       0 4010.95    .085       0
 4855.51     .05       0 5124.21     .08       0
#XS Ineff= 1 ,-1
    3191    4802     434
Permanent Ineff=
       F
Bank Sta=4855.51,5093.64
XS Rating Curve= 0 ,0
Exp/Cntr=0.3,0.1

Type RM Length L Ch R = 1 ,39095   ,107,236,236
BEGIN DESCRIPTION:
This cross section corresponds to cross section 39095 of the non-georeferenced CDC model which was the source of this model.
END DESCRIPTION:
XS GIS Cut Line= 2
     2435167.682     6964887.9172436283.00972025 6962543.4541269
#Sta/Elev= 30
   995.3     448 1007.42  447.75 1037.73     440 1078.28     432  1110.5     430
 1127.34     428 1181.83     416 1388.48   416.4 1417.18     428 1428.11     430
 1506.43     432 2117.14  430.75  2156.1     430 2168.26     426  2247.2  426.09
    2276     432  2512.5   430.9 2548.89     426 2615.35  427.23 2653.06     432
 3152.04  433.84    3200     428 3228.31     410  3272.3     405 3316.97  411.57
 3335.29     424 3367.94     434 3476.86  434.55 3565.73     460 3591.54  461.63
#Mann= 5 ,-1,0
   995.3    .035       0  1110.5    .045       0 1428.11    .085       0
 3152.04     .05       0 3367.94    .065       0
#XS Ineff= 1 ,-1
  1028.3  3151.3     434
Permanent Ineff=
       F
Bank Sta=3152.04,3367.94
XS Rating Curve= 0 ,0
Exp/Cntr=0.3,0.1

Type RM Length L Ch R = 1 ,38702   ,37,64,64
BEGIN DESCRIPTION:
This cross section corresponds to cross section 38702 of the non-georeferenced CDC model which was the source of this model.
END DESCRIPTION:
XS GIS Cut Line= 2
     2435213.571     6964910.862     2436538.604     6962599.224
#Sta/Elev= 30
    98.1     448  125.62     440  197.66     430  227.81     426  271.09     416
  485.96     416   527.8  430.27 1164.34     432 1281.31  427.07 1342.08     432
 1574.72     432 1606.31     426 1686.45     426 1717.36     432 2331.25     434
 2356.02     428 2383.63     426  2411.8     410    2454     405  2497.8     410
  2519.1  422.71 2525.82     418 2531.64     418 2548.75     430 2569.82     434
 2581.58  436.66 2627.01     436 2674.03     442 2761.63     464 2780.38  466.29
#Mann= 5 ,-1,0
    98.1    .035       0  197.66    .045       0   527.8    .085       0
 2331.25     .05       0 2569.82    .065       0
#XS Ineff= 1 ,-1
     121    2331     434
Permanent Ineff=
       F
Bank Sta=2331.25,2569.82
XS Rating Curve= 0 ,0
Exp/Cntr=0.3,0.1

Type RM Length L Ch R = 1 ,38623   ,431,200,184
BEGIN DESCRIPTION:
This cross section corresponds to cross section 38623 of the non-georeferenced CDC model which was the source of this model.
END DESCRIPTION:
XS GIS Cut Line= 2
     2435230.779     6964939.542     2436624.645     6962582.016
#Sta/Elev= 30
       0   447.6   21.37     448   48.11     440  119.39   430.1  154.28     426
  196.39     416  407.97     416     438     418     494     432 1057.62     432
 1123.73     428 1255.01     432 1519.88     432 1551.92     426  1633.7     426
 1649.36     432 2289.63     434 2305.72     430 2345.68     426 2363.96     410
    2404     405 2445.26     410 2483.51     430 2551.45  431.03 2561.43     416
 2563.57     416 2567.94  425.66 2576.75  433.03 2649.33     446 2731.35  466.44
#Mann= 5 ,-1,0
       0    .035       0  119.39    .045       0     494    .085       0
 2305.72     .05       0 2483.51    .065       0
#XS Ineff= 2 , 0
         2289.79  434.47 2483.51             430
Permanent Ineff=
       F       F
Bank Sta=2305.72,2483.51
XS Rating Curve= 0 ,0
Exp/Cntr=0.3,0.1

Type RM Length L Ch R = 1 ,38451   ,427,165,146
BEGIN DESCRIPTION:
This cross section corresponds to cross section 38451 of the non-georeferenced CDC model which was the source of this model.
END DESCRIPTION:
XS GIS Cut Line= 3
2435384.05502298 6965153.3748598     2435890.427     6964647.002
     2436790.991     6962564.807
#Sta/Elev= 30
   96.08  447.89   179.8     430  198.94  429.73  337.27     416     604     418
     652     430  871.64   431.4  984.38     428  1109.6  428.35 1188.43     432
 1841.51  430.29 1860.71     426 1939.25  426.84    1966     432 2382.95     434
 2498.81  433.82 2513.95     430 2527.35   432.7 2570.82     432 2605.44     428
 2633.11     410  2666.5     405 2700.13  410.15 2764.15     428  2806.1     432
 2844.31     442 2903.18     452 2946.04     464 3025.88     470  3080.8     470
#Mann= 5 ,-1,0
   96.08    .035       0  198.94    .045       0     652    .085       0
 2570.82     .05       0  2806.1    .065       0
#XS Ineff= 2 , 0
            2498     434
Permanent Ineff=
       F       F
#Block Obstruct= 2 , 0
              71     448
Bank Sta=2570.82,2806.1
XS Rating Curve= 0 ,0
Exp/Cntr=0.3,0.1

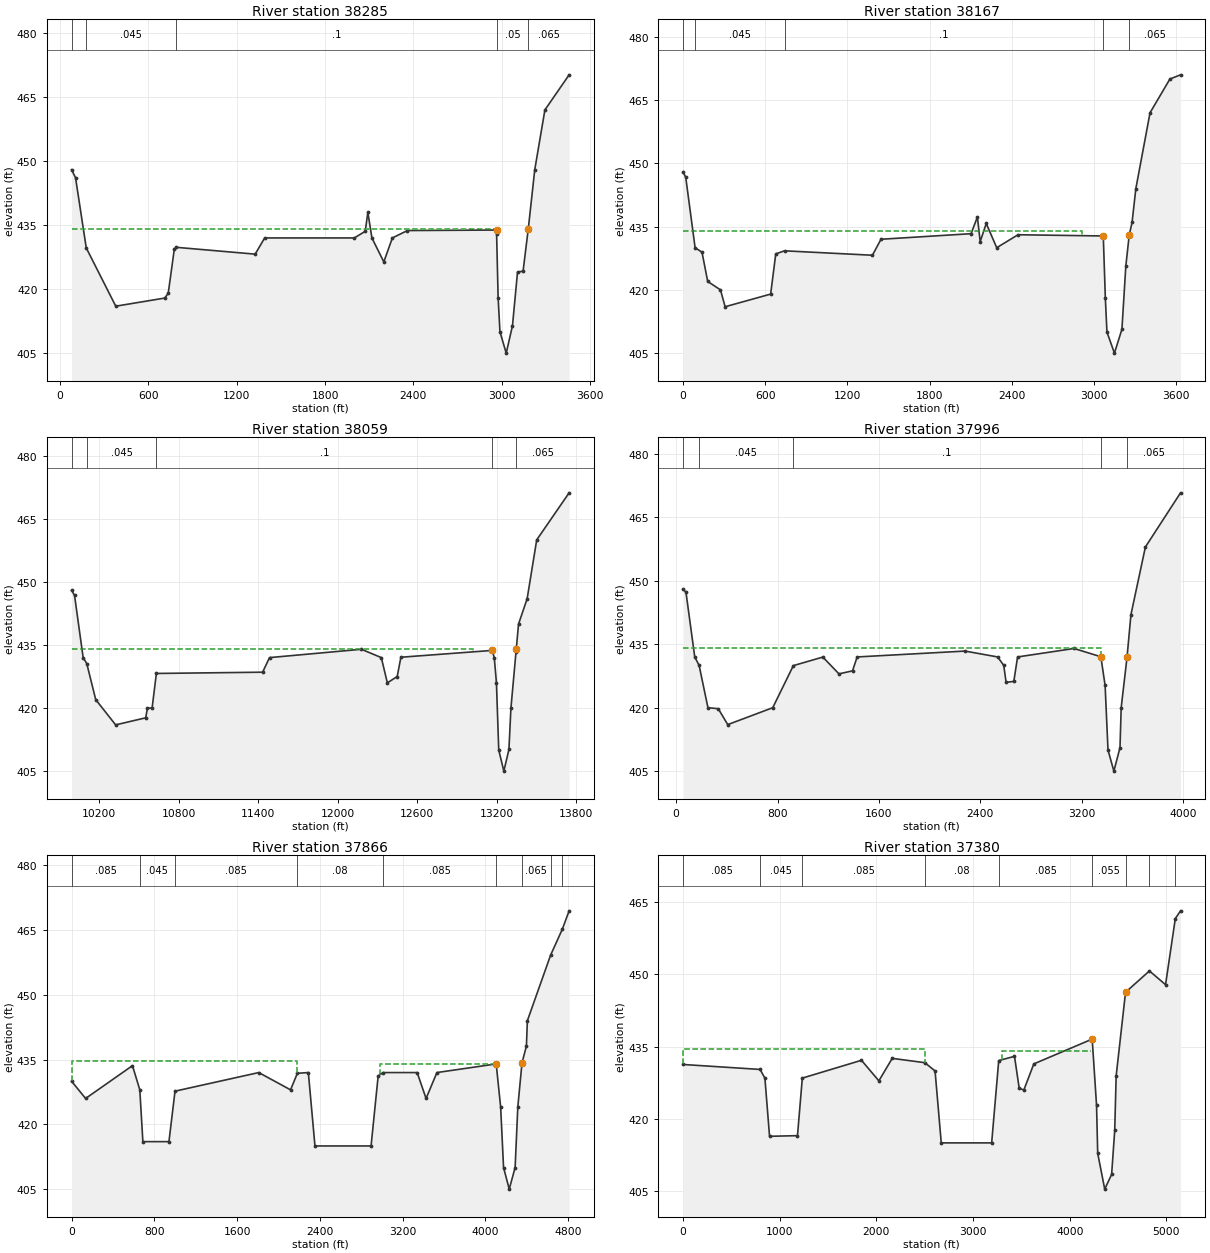
Type RM Length L Ch R = 1 ,38285   ,154,235,249
BEGIN DESCRIPTION:
This cross section corresponds to cross section 38285 of the non-georeferenced CDC model which was the source of this model.
END DESCRIPTION:
XS GIS Cut Line= 4
2435439.981997236965353.66118131     2435460.222     6965346.803
     2436154.287     6965111.624      2436894.24     6962593.488
#Sta/Elev= 30
   78.43     448  105.53  446.12  178.32  429.66  378.68     416  710.39   417.9
  734.86     419     776   429.3     790   429.8 1325.29   428.2 1389.87     432
 1999.11     432 2072.84  433.56 2090.53     438 2118.11     432 2198.94  426.38
 2257.01     432 2359.37  433.73 2964.18  433.85 2964.87  432.88 2975.08     418
 2987.54     410 3030.07     405 3072.64  411.43 3106.83     424 3144.61  424.22
 3179.42     434 3180.69  434.36 3223.93     448 3292.74     462 3457.23  470.23
#Mann= 5 ,-1,0
   78.43    .035       0  178.32    .045       0     790      .1       0
 2964.87     .05       0 3180.69    .065       0
#XS Ineff= 2 , 0
            2964     434
Permanent Ineff=
       F       F
Bank Sta=2964.18,3179.42
XS Rating Curve= 0 ,0
Exp/Cntr=0.3,0.1

Type RM Length L Ch R = 1 ,38167   ,60,95,99
BEGIN DESCRIPTION:
This cross section corresponds to cross section 38167 of the non-georeferenced CDC model which was the source of this model.
END DESCRIPTION:
XS GIS Cut Line= 4
     2435580.679     6965754.064     2436314.897       6965409.9
     2436332.105     6964864.9732437121.446464076962731.02988022
#Sta/Elev= 30
       0     448   20.18  446.71   88.63     430  139.05  428.92  180.51     422
  273.71     420  307.74     416     640     419  677.25  428.53  741.14  429.26
 1382.68  428.21 1445.33     432 2102.68  433.32 2148.79  437.28 2169.22  431.44
 2213.48  435.74 2289.76     430 2445.27  433.07 3067.52  432.78 3082.63     418
 3094.34     410 3148.92     405 3203.51  410.64  3232.1  425.66 3256.81  432.98
 3277.63     436 3305.12     444 3408.82     462 3553.89     470 3631.33  470.99
#Mann= 5 ,-1,0
       0    .035       0   88.63    .045       0  741.14      .1       0
 3067.52    .055       0 3256.81    .065       0
#XS Ineff= 2 , 0
            2912     434
Permanent Ineff=
       F       F
Bank Sta=3067.52,3256.81
XS Rating Curve= 0 ,0
Exp/Cntr=0.3,0.1

Type RM Length L Ch R = 1 ,38059   ,156,39,86
BEGIN DESCRIPTION:
This cross section corresponds to cross section 38059 of the non-georeferenced CDC model which was the source of this model.
END DESCRIPTION:
XS GIS Cut Line= 4
     2435620.832     6965851.578     2436355.049     6965484.469
     2436590.228      6964342.99 2437247.03113126962700.98265719
#Sta/Elev= 30
    9992     44810014.48  446.8310079.56     43210106.85  430.5810174.57     422
10324.69     41610551.45  417.68   10565     420   10600     42010632.12  428.23
11433.79  428.5311486.02     43212179.22  433.9812329.66     432 12375.1     426
12449.31  427.49 12477.5  432.0913166.35  433.7113182.04     432 13198.3     426
13215.78     41013254.19     405 13292.6  410.1513307.71     42013346.14  433.39
13347.89     43413365.25     44013430.14     44613502.31     46013746.83  471.19
#Mann= 5 ,-1,0
    9992    .035       010106.85    .045       010632.12      .1       0
13166.35    .055       013346.14    .065       0
#XS Ineff= 2 , 0
           13021     434
Permanent Ineff=
       F       F
Bank Sta=13166.35,13347.89
XS Rating Curve= 0 ,0
Exp/Cntr=0.3,0.1

Type RM Length L Ch R = 1 ,37996   ,417,130,203
BEGIN DESCRIPTION:
This cross section corresponds to cross section 37966 of the non-georeferenced CDC model which was the source of this model.
END DESCRIPTION:
XS GIS Cut Line= 4
     2435643.776      6965891.73     2436429.618     6965536.094
     2436595.964     6964406.087      2437296.58      6962712.77
#Sta/Elev= 30
   53.59     448   77.12  447.35  146.57     432  181.04     430  250.69     420
  331.92  419.76  407.02     416  761.92     420  924.49  429.95  1157.1  431.97
 1284.18     428 1391.17  428.71 1427.85     432  2278.7  433.39 2536.14     432
 2584.21     430  2602.9     426 2663.64  426.22 2693.47     432 3138.84     434
 3350.35  432.05 3383.89  425.28 3406.65     410 3453.05     405 3501.35  410.56
 3510.72     420 3557.09  431.99 3587.68     442 3701.65     458 3978.93  470.81
#Mann= 5 ,-1,0
   53.59    .035       0  181.04    .045       0  924.49      .1       0
 3350.35    .055       0 3557.09    .065       0
#XS Ineff= 2 , 0
            3350     434
Permanent Ineff=
       F       F
#Block Obstruct= 2 , 0
              54     448
Bank Sta=3350.35,3557.09
XS Rating Curve= 0 ,0
Exp/Cntr=0.3,0.1

Type RM Length L Ch R = 1 ,37866   ,536,486,502
BEGIN DESCRIPTION:
37866-The reach length has been updated and it is the same with the 2018 georeferenced model.
Cross-section Truncated due to Ineffective Flow Areas
END DESCRIPTION:
XS GIS Cut Line= 3
  2436376.5209896967369.186983732436742.338827136964727.09154615
2437487.363911886962714.05685832
#Sta/Elev= 30
       0     430     136     426  588.87   433.6  660.02     428  689.55     416
  941.73     416 1000.39  427.69 1809.96     432 2117.25     428 2183.24  431.83
 2289.33     432 2353.33     415  2895.8     415 2964.34   431.2 3010.54     432
 3341.52     432 3427.48     426  3532.4     432 4105.49     434 4148.57     424
 4176.68     410  4231.5     405 4288.45     410  4314.4     424 4354.87  434.22
 4397.81  438.17 4406.81     444 4631.91  459.22 4744.45  465.18 4810.52  469.46
#Mann= 9 ,-1,0
       0    .085       0  660.02    .045       0 1000.39    .085       0
 2183.24     .08       0 3010.54    .085       0 4105.49    .055       0
 4354.87    .065       0 4631.91     .05       0 4744.45    .065       0
#XS Ineff= 3 ,-1
       0 2181.28 434.691 2181.28 2978.03 426.755 2978.03  4104.5     434
Permanent Ineff=
       F       T       F
Bank Sta=4105.49,4354.87
XS Rating Curve= 0 ,0
Exp/Cntr=0.3,0.1

Type RM Length L Ch R = 1 ,37380   ,137,137,137
BEGIN DESCRIPTION:
XS added for HF project
END DESCRIPTION:
XS GIS Cut Line= 4
     2436659.552     6967678.975     2437158.994     6964434.755
     2438097.159     6962846.703     2438097.159     6962846.703
#Sta/Elev= 30
       0  431.28  797.57  430.25  847.56  428.44  895.55  416.37 1184.48   416.5
 1234.47  428.45 1846.34  432.15  2026.3  427.88 2164.27  432.55  2502.2  431.65
 2607.49  429.93 2671.49     415 3192.82     415 3266.03  432.09 3428.97  432.97
 3477.95  426.31 3525.93  425.99 3628.89   431.4 4232.65  436.55 4277.64  422.82
 4289.63  412.83 4362.13   405.4 4433.58  408.45 4465.57  417.58 4480.56  428.91
 4577.53  446.27 4824.44   450.7 4991.38  447.85 5092.34  461.57 5146.32  463.18
#Mann= 9 ,-1,0
       0    .085       0  797.57    .045       0 1234.47    .085       0
  2502.2     .08       0 3266.03    .085       0 4232.65    .055       0
 4577.53    .065       0 4824.44     .05       0 5092.34    .065       0
#XS Ineff= 3 ,-1
       0 2500.42 434.444 2500.42    3300 426.773    3300    4220     434
Permanent Ineff=
       F       T       F
Bank Sta=4232.65,4577.53
XS Rating Curve= 0 ,0
Exp/Cntr=0.3,0.1

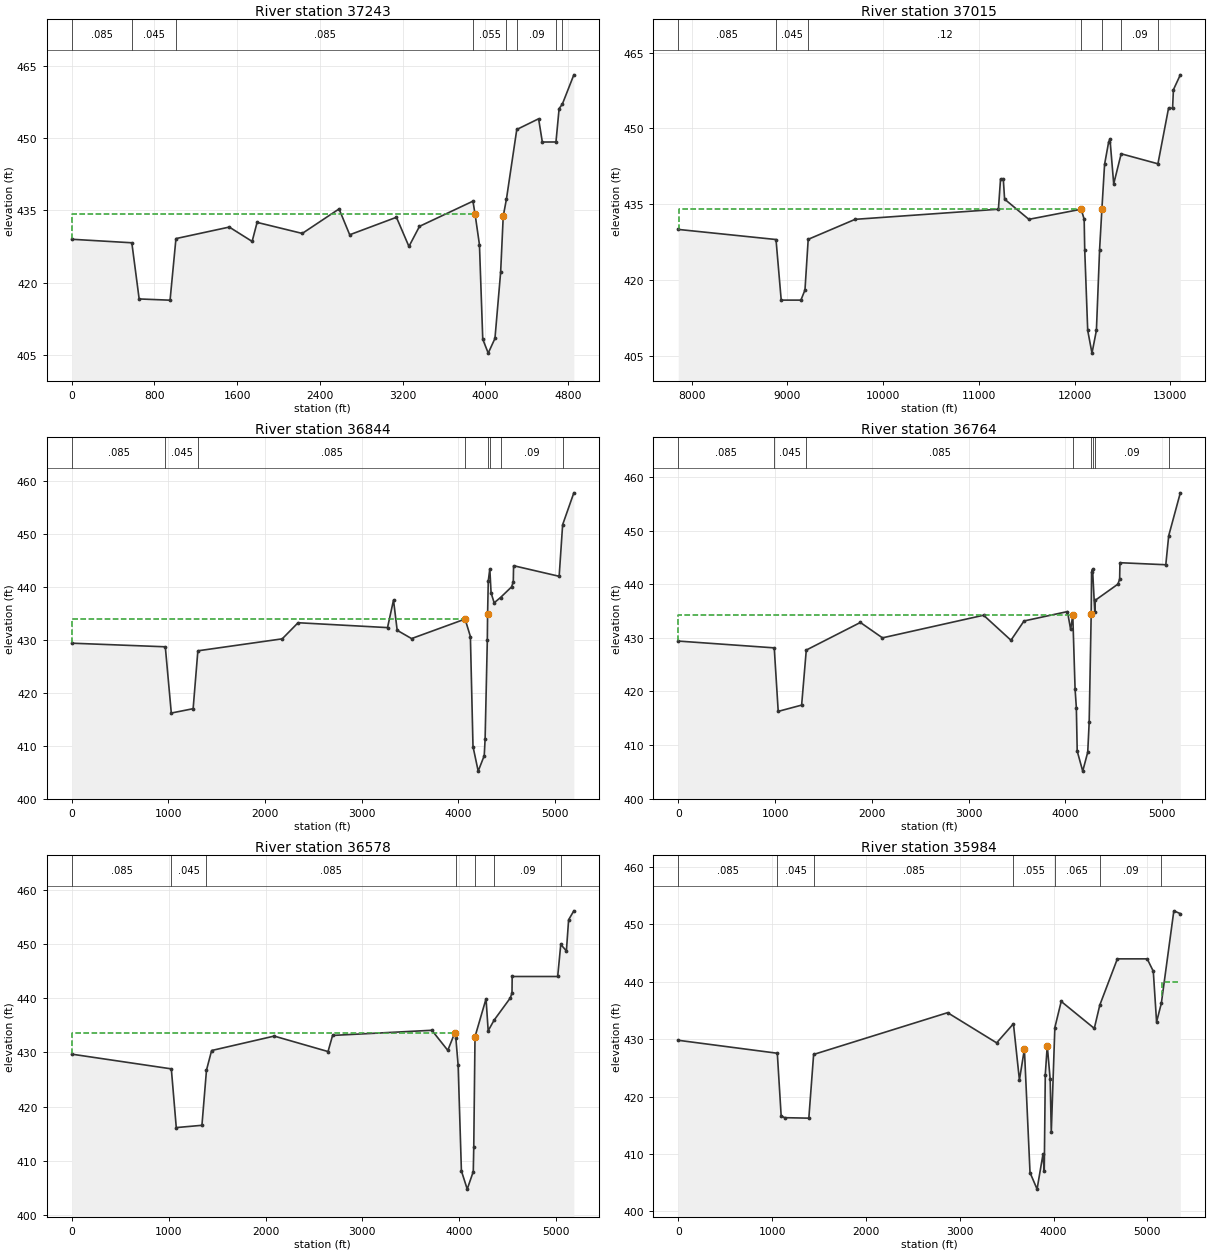
Type RM Length L Ch R = 1 ,37243   ,300,228,241
BEGIN DESCRIPTION:
With fill grading for CDC GP 070319-1.
New cross section.
CDC GP083121-1 Hunter-Ferrell Industrial
Valley storage area in LOB.
Cross-section 37243 - 37866
END DESCRIPTION:
XS GIS Cut Line= 3
  2436696.2470556967456.589696062437272.635994886964824.64548489
2438126.802593636962838.53429964
#Sta/Elev= 30
       0  428.98  580.85  428.25  651.83   416.6  950.76  416.34 1007.75  429.12
 1523.62  431.51 1744.57  428.53 1792.56  432.48 2229.43  430.19 2585.32  435.27
 2688.29  429.91 3140.29  433.54 3261.29  427.49 3363.29  431.66  3880.3  436.88
 3901.41  434.12  3943.3  427.84  3975.3  408.25 4028.13  405.36  4093.3  408.41
  4148.3  422.17  4173.3  433.77  4204.3   437.3  4304.3  451.75 4515.46  453.97
 4551.44  449.15 4683.37  449.16 4713.85  456.09 4744.83     457 4856.31  463.09
#Mann= 8 ,-1,0
       0    .085       0  580.85    .045       0 1007.75    .085       0
  3880.3    .055       0  4204.3    .065       0  4304.3     .09       0
 4683.37    .055       0 4744.83    .065       0
#XS Ineff= 2 , 0
         3901.41  434.12
Permanent Ineff=
       F       F
Bank Sta=3901.41,4173.3
XS Rating Curve= 0 ,0
Exp/Cntr=0.3,0.1

Type RM Length L Ch R = 1 ,37015   ,60,160,241
BEGIN DESCRIPTION:
With fill grading for CDC GP 070319-1.
37015-The reach length has been updated and it is the same with the 2018 georeferenced model.
Cross-section Truncated due to Ineffective Flow Areas
END DESCRIPTION:
XS GIS Cut Line= 3
  2436859.9183166967892.82274748 2437479.88722086964906.89400806
2438356.561976646962905.79007064
#Sta/Elev= 30
    7861     430 8881.83     428  8936.2     416  9141.7     416 9184.24     418
 9217.97  428.04 9708.41     43211204.02     43411226.23     44011254.94     440
11268.47     43611522.11     43212068.39     434 12099.4     432 12105.1     426
12136.32     410   12181   405.512227.13     41012260.45     42612284.33     434
12312.39  442.8812354.38  447.2612368.77  447.9112407.75  439.0212485.71  444.98
12869.52     44312980.47  454.0313022.45     45413031.21  457.6713103.19  460.62
#Mann= 7 ,-1,0
    7861    .085       0 8881.83    .045       0 9217.97     .12       0
12068.39    .055       012284.33    .065       012485.71     .09       0
12869.52     .05       0
#XS Ineff= 1 ,-1
    7870   12068     434
Permanent Ineff=
       F
Bank Sta=12068.39,12284.33
XS Rating Curve= 0 ,0
Exp/Cntr=0.3,0.1

Type RM Length L Ch R = 1 ,36844   ,60,80,94
BEGIN DESCRIPTION:
With fill grading for CDC GP 070319-1.
New cross section
END DESCRIPTION:
XS GIS Cut Line= 6
  2436890.8651046967839.923246982437526.28181306 6965035.2356149
 2437575.76104486964858.15230764 2438060.13606036963878.98563081
2438192.948458726963782.631492812438570.552690396962988.36077164
#Sta/Elev= 30
       0  429.38  967.96   428.7 1029.96   416.2 1255.95  417.02 1304.94  427.94
 2177.85   430.2 2341.84  433.24 3267.57  432.32 3329.54  437.51 3367.53  431.81
 3516.45  430.25 4070.18  433.93 4125.15  430.64 4152.14  409.88 4205.91  405.24
 4268.48  408.16 4277.42   411.3 4300.29  429.91 4303.28  434.98 4310.24  441.13
  4326.2  443.41 4339.19  438.88 4371.14     437 4437.11     438 4551.04     440
 4569.04  440.93 4572.03     444 5043.78     442 5079.76  451.74 5195.73  457.75
#Mann= 8 ,-1,0
       0    .085       0  967.96    .045       0 1304.94    .085       0
 4070.18    .055       0 4303.28    .065       0  4326.2    .055       0
 4437.11     .09       0 5079.76    .065       0
#XS Ineff= 2 , 0
         4070.18  433.93
Permanent Ineff=
       F       F
Bank Sta=4070.18,4303.28
XS Rating Curve= 0 ,0
Exp/Cntr=0.3,0.1

Type RM Length L Ch R = 1 ,36764   ,165,186,136
BEGIN DESCRIPTION:
With fill grading for CDC GP 070319-1.
New cross section
END DESCRIPTION:
XS GIS Cut Line= 6
  2436907.0976836967847.041014892437657.09782438 6964847.0411094
2438066.820102056963992.874510652438268.208806896963805.37455755
2438329.059735066963705.721869722438628.538794896963013.01328139
#Sta/Elev= 30
       0  429.38  991.78  428.11 1032.77  416.26 1274.72  417.43  1322.7   427.7
 1881.58  432.85 2109.53  429.98 3154.34   434.2 3437.15  429.53 3572.06  433.13
 4020.77  434.88 4053.71  431.54 4075.65  434.25 4099.57  420.39 4112.54  416.96
 4121.51  408.84 4178.36  405.11 4230.17  408.64 4245.12  414.26 4265.92  434.48
 4270.05  442.23 4280.01  442.77 4302.94  434.81 4307.93  436.99 4541.83     440
 4559.83  440.93 4562.82     444 5036.59  443.62 5066.58  449.03 5186.52  457.04
#Mann= 8 ,-1,0
       0    .085       0  991.78    .045       0  1322.7    .085       0
 4075.65    .055       0 4265.92    .065       0 4280.01    .055       0
 4307.93     .09       0 5066.58    .065       0
#XS Ineff= 2 , 0
         4075.65  434.25
Permanent Ineff=
       F       F
Bank Sta=4075.65,4265.92
XS Rating Curve= 0 ,0
Exp/Cntr=0.3,0.1

Type RM Length L Ch R = 1 ,36578   ,75,594,598
BEGIN DESCRIPTION:
With fill grading for CDC GP 070319-1.
New cross section
END DESCRIPTION:
XS GIS Cut Line= 5
  2436948.7645956967867.87463464 2437920.98673236964770.65215456
 2438183.22636536964115.964815652438353.365132636963994.43717156
 2438731.83747286963044.78421523
#Sta/Elev= 30
       0  429.69 1027.76  426.98 1078.75  416.16 1343.68  416.58 1390.67  426.75
 1443.65  430.36 2089.49  433.02 2645.38  430.17 2692.37  433.14 3716.76  434.09
 3881.58  430.39 3951.51  433.52 3964.45  432.73 3988.35  427.66  4022.2  408.18
 4082.16  404.82 4144.67  408.05 4149.64   412.5 4162.59  432.91 4276.51  439.89
 4298.49     434 4359.45  435.95 4526.32  440.03 4544.31  440.96 4546.31     444
 5015.95     444 5047.93  449.91 5105.89  448.71 5128.87  454.45 5182.83   456.1
#Mann= 7 ,-1,0
       0    .085       0 1027.76    .045       0 1390.67    .085       0
 3964.45    .055       0 4162.59    .065       0 4359.45     .09       0
 5047.93    .065       0
#XS Ineff= 2 , 0
         3951.51  433.52
Permanent Ineff=
       F       F
Bank Sta=3951.51,4162.59
XS Rating Curve= 0 ,0
Exp/Cntr=0.3,0.1

Type RM Length L Ch R = 1 ,35984   ,212,407,104
BEGIN DESCRIPTION:
With fill grading for CDC GP 070319-1.
New cross section - The ineffective at the ROB is updated to match the ineffectives from CADD_August2019 for elevation 440
END DESCRIPTION:
XS GIS Cut Line= 5
  2436981.3166956967890.009760982437996.941632886964851.81537805
2438578.53889489 6964539.31534692438901.889626136964157.80495507
2439283.834072226963248.08269314
#Sta/Elev= 30
       0  429.81 1055.83  427.55 1096.82  416.63 1134.82  416.32 1391.78  416.24
 1442.77  427.34 2870.54  434.62 3393.25  429.36 3572.02  432.69 3635.94  422.88
 3688.88  428.28  3748.8  406.75 3824.01  403.87 3886.61  409.92 3900.59  407.03
 3911.56  423.84 3932.53  428.87 3963.47  423.03 3975.44  413.75 4013.37  432.02
 4081.24  436.58  4433.7  431.88 4492.69  435.96 4679.63     444 4997.53     444
 5062.51  441.84  5097.5     433 5148.48  436.28 5281.44  452.37 5350.42  451.88
#Mann= 7 ,-1,0
       0    .085       0 1055.83    .045       0 1442.77    .085       0
 3572.02    .055       0 4013.37    .065       0 4492.69     .09       0
 5148.48    .065       0
#XS Ineff= 3 ,-1
       0 3688.88  428.28 3932.53  5158.2  428.87  5158.2 5350.42     440
Permanent Ineff=
       F       F       F
Bank Sta=3688.88,3932.53
XS Rating Curve= 0 ,0
Exp/Cntr=0.3,0.1

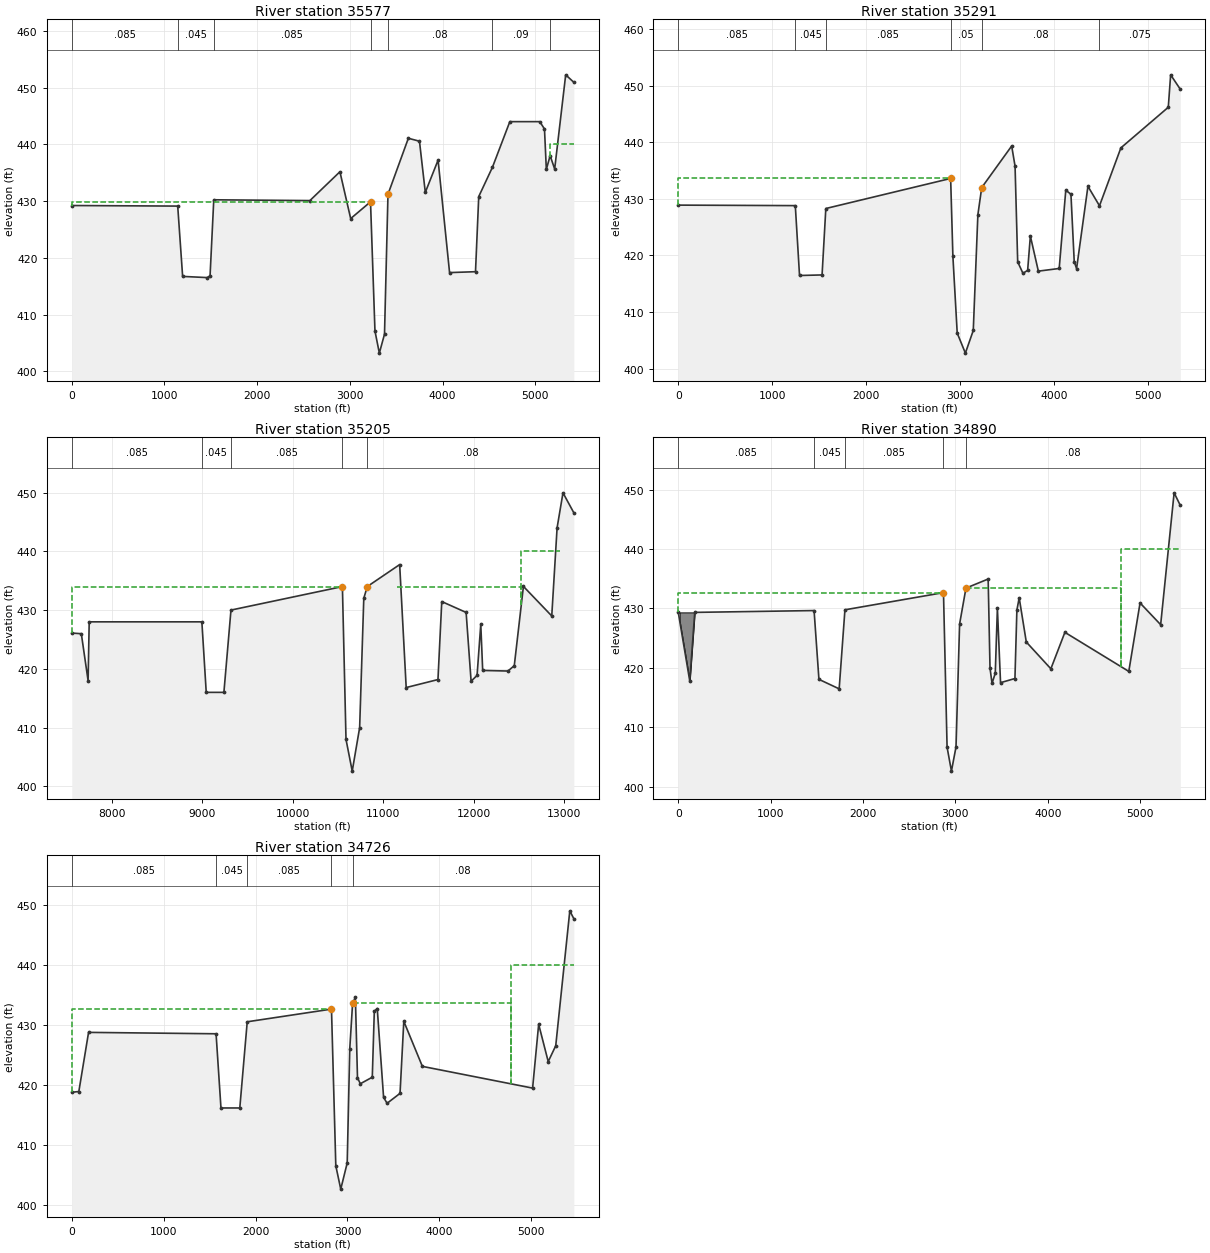
Type RM Length L Ch R = 1 ,35577   ,111,286,145
BEGIN DESCRIPTION:
With fill grading for CDC GP 070319-1.
New cross section -  The ineffective at the ROB is updated to match the ineffectives from CADD_August2019 for elevation 440
END DESCRIPTION:
XS GIS Cut Line= 6
  2437084.3256756967964.084087892438231.316492216964988.96831898
2438473.674275226965020.128689722438972.346506226964188.04242739
2439019.511110056964143.482149062439366.733184646963261.53771873
#Sta/Elev= 30
       0  429.22 1142.84  429.12 1195.83  416.73  1460.8  416.52 1491.79  416.83
 1531.79  430.23 2568.67  430.09 2892.64  435.17 3008.63  426.92 3222.59  429.87
 3270.57  407.11 3317.84  403.21 3373.52  406.55 3411.02   431.2 3630.78  441.07
 3750.67  440.55 3813.61  431.54 3951.49  437.22 4075.38   417.4  4355.1  417.56
 4390.06   430.8 4537.77  435.96 4725.51     444 5048.24     444  5099.2  442.71
 5119.18  435.58 5160.15     438 5209.11  435.66 5328.01  452.25 5415.94  450.93
#Mann= 7 ,-1,0
       0    .085       0 1142.84    .045       0 1531.79    .085       0
 3222.59    .055       0 3411.02     .08       0 4537.77     .09       0
 5160.15     .08       0
#XS Ineff= 3 ,-1
       0 3222.59  429.87 3411.02  5156.9   431.2  5156.9 5415.94     440
Permanent Ineff=
       F       F       F
Bank Sta=3222.59,3411.02
XS Rating Curve= 0 ,0
Exp/Cntr=0.3,0.1

Type RM Length L Ch R = 1 ,35291   ,119,97,213
BEGIN DESCRIPTION:
With fill grading for CDC GP 070319-1.
New cross section -  The ineffective at the ROB is updated to match the ineffectives from CADD_August2019 for elevation 440
END DESCRIPTION:
XS GIS Cut Line= 6
  2437171.1312766968029.188288392437422.867649816967621.20189965
2438125.992555896965459.743624152438764.013261476964717.55613214
2439202.381479226964088.215855392439497.520324636963293.94513422
#Sta/Elev= 30
       0  428.89 1246.39   428.8 1291.39  416.46 1531.38  416.56 1571.38  428.29
  2900.3   433.6  2924.3  419.83 2970.29  406.29 3057.21  402.75 3141.25  406.75
 3190.24  427.19 3231.23  431.99 3550.17  439.33 3586.16  435.77 3614.15  418.87
 3670.14  416.85 3720.13  417.37 3749.13  423.43 3834.13  417.23 4056.13   417.7
 4126.13  431.52 4181.12  430.81 4216.12  418.93 4241.12  417.67 4362.12  432.21
 4485.06  428.77  4712.9     439 5217.59  446.17 5242.66   451.9 5345.59  449.35
#Mann= 6 ,-1,0
       0    .085       0 1246.39    .045       0 1571.38    .085       0
  2900.3     .05       0 3231.23     .08       0 4485.06    .075       0
#XS Ineff= 3 ,-1
       0  2900.3   433.6 3231.23  4973.2  431.99  4973.2 5345.59     440
Permanent Ineff=
       F       F       F
Bank Sta=2900.3,3231.23
XS Rating Curve= 0 ,0
Exp/Cntr=0.3,0.1

Type RM Length L Ch R = 1 ,35205   ,267,305,178
BEGIN DESCRIPTION:
35205 The reach length has been updated and it is the same with the 2018 georeferenced model.Also the geometry has been revised at the ROB per the 2009 LiDAR.The ineffective at the ROB is updated to match the ineffectives from CADD_August2019 for elevation 440
FLOWLINE INTERPOLATED AT STATION 10661 FROM EFFECTIVE PROFILE
The geometry has been revised at the ROB per the 2009 LiDAR.
END DESCRIPTION:
XS GIS Cut Line= 4
  2437221.5101126968191.109880572437555.631163816967658.49939723
2438229.261050136965491.521775812439856.696115466963416.27198932
#Sta/Elev= 30
    7560  426.09 7665.51  425.98 7740.26     418 7752.48     428  8996.6     428
 9044.83     416 9239.96     416 9318.02     43010548.51     43410588.34     408
   10657   402.610738.95     41010784.78     43210823.02     43411180.88  437.74
11252.87  416.82 11603.8  418.1811645.79  431.45 11914.7   429.611969.68   417.9
12035.66  418.8812076.64  427.5812097.64  419.7312376.54  419.6312446.52  420.54
12547.49  434.0312860.37     42912919.35     44412984.33  449.9513104.29  446.55
#Mann= 5 ,-1,0
    7560    .085       0  8996.6    .045       0 9318.02    .085       0
10548.51    .055       010823.02     .08       0
#XS Ineff= 3 ,-1
    7560   10548     434   1115512524.39     43412524.39   12953     440
Permanent Ineff=
       F       F       T
#Block Obstruct= 2 , 0
            7753     428
Bank Sta=10548.51,10823.02
XS Rating Curve= 0 ,0
Exp/Cntr=0.3,0.1

Type RM Length L Ch R = 1 ,34890   ,120,164,157
BEGIN DESCRIPTION:
New cross section -  The ineffective at the ROB is updated to match the ineffectives from CADD_August2019 for elevation 440
END DESCRIPTION:
XS GIS Cut Line= 6
  2437353.4229066968228.841104312437700.645309466967612.52147081
2438516.617430816965668.07719697 2438612.10346036965468.42438106
2438777.034232816965190.646393312439974.950800236963497.93816456
#Sta/Elev= 30
       0  429.38  124.89  417.78  178.85  429.34 1470.29429.6479 1522.85  418.06
 1741.85  416.46 1804.24429.7729 2870.93  432.67 2909.81  406.64    2957   402.6
  3006.5  406.68 3045.38  427.39 3114.18  433.43 3354.46  434.96 3374.44  419.96
 3396.42  417.38 3431.41   419.1 3454.39  430.05 3488.37   417.5 3644.29   418.2
 3665.28  429.71 3690.26   431.8 3767.22  424.35 4033.07  419.84 4184.99  425.98
 4876.58   419.4 4998.49  430.93 5221.37  427.27 5367.22  449.48 5434.17  447.36
#Mann= 5 ,-1,0
       0    .085       0 1470.29    .045       0 1804.24    .085       0
 2870.93    .055       0 3114.18     .08       0
#XS Ineff= 3 ,-1
       0 2870.93  432.67 3114.18  4796.7  433.43  4796.7 5434.17     440
Permanent Ineff=
       F       F       F
#Block Obstruct= 1 ,-1
   14.99  178.85  429.34
Bank Sta=2870.93,3114.18
XS Rating Curve= 0 ,0
Exp/Cntr=0.3,0.1

Type RM Length L Ch R = 1 ,34726   ,0,0,0
BEGIN DESCRIPTION:
New cross section -  The ineffective at the ROB is updated to match the ineffectives from CADD_August2019 for elevation 440
END DESCRIPTION:
XS GIS Cut Line= 6
  2437474.950878 6968324.32713382437770.089724396967708.00750031
2438586.061845726965824.327212562439011.409092146965138.56316414
2439402.034295146964687.174303142440079.117586646963550.02139373
#Sta/Elev= 30
       0  418.78   76.93  418.91  182.82  428.79 1570.27428.5569 1623.47  416.16
 1828.42  416.16 1909.24430.5603 2826.16  432.68 2873.15   406.5    2927   402.6
 2997.14  406.97 3025.14  426.08 3056.14  433.73 3086.14  434.65 3109.13   421.2
 3140.13  420.21 3270.12   421.3 3292.12  432.31 3324.11  432.78 3393.11  417.94
  3431.1  416.94 3572.09   418.6 3613.09  430.64 3815.09  423.11 5014.63  419.48
  5080.6  430.14 5184.55  423.91 5266.43  426.56 5419.43   449.1 5463.41  447.78
#Mann= 5 ,-1,0
       0    .085       0 1570.27    .045       0 1909.24    .085       0
 2826.16    .055       0 3056.14     .08       0
#XS Ineff= 3 ,-1
       0 2826.16  432.68 3056.14  4775.9  433.73  4775.9 5463.41     440
Permanent Ineff=
       F       F       F
#Block Obstruct= 2 , 0
          144.86  428.26
Bank Sta=2826.16,3056.14
XS Rating Curve= 0 ,0
Exp/Cntr=0.3,0.1

River Reach=West Fork       ,wf1
Reach XY= 30
        2438660.      6965610.97      2439107.13       6966947.7
      2440364.74      6967311.11      2441463.54      6966675.05
       2441652.7      6966856.62      2441378.77      6967591.89
      2441565.52      6967819.41      2441947.52      6967765.42
      2442246.67      6967244.02      2442699.76      6967301.91
       2442990.1      6967724.76      2442726.08      6968143.18
      2442919.19      6968919.88       2443518.4      6969685.89
      2444352.98      6969917.06      2444667.07      6969705.87
      2443821.45      6968887.79      2443868.87      6968306.35
      2444209.34      6968225.94      2445345.53      6968501.95
      2445856.58      6969165.84      2446770.54      6969010.06
      2452038.46      6971023.33      2454231.09      6972385.64
      2455794.74      6971975.24      2456596.76      6973000.46
      2456919.85       6974803.1       2457790.9      6976586.85
      2458714.96      6977041.16       2460651.9      6977070.51