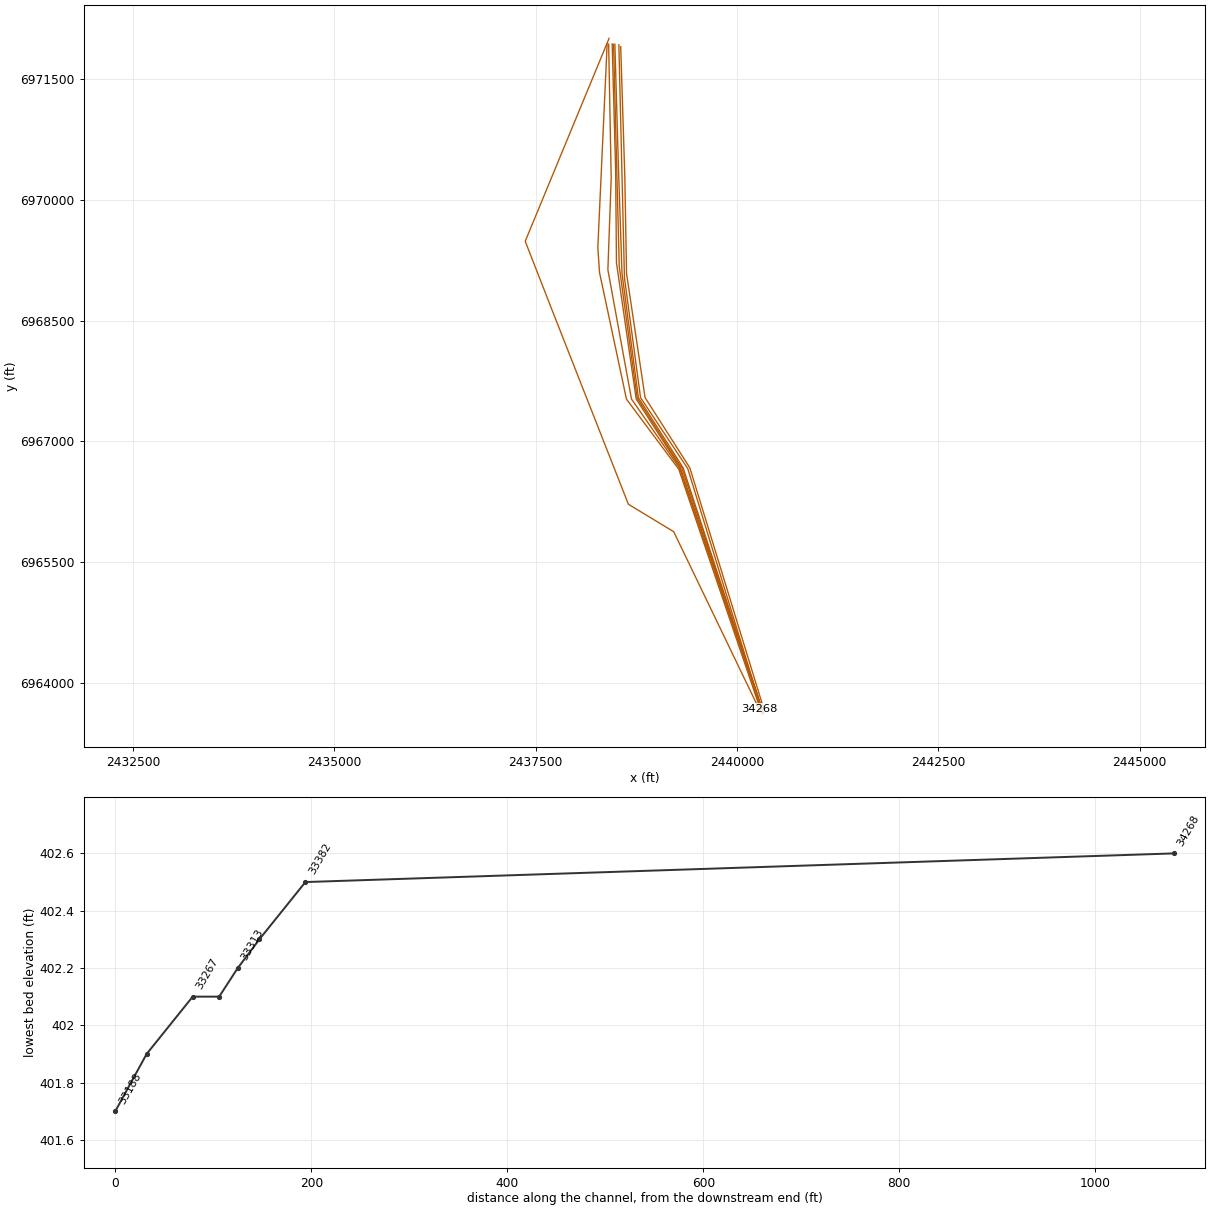
HEC-RAS study CDC_Consolidated_Model.prj: Upper Trinity CDC Consolidated Model

--- CDC_Consolidated_Model.g12 (geometry) --- (continued)

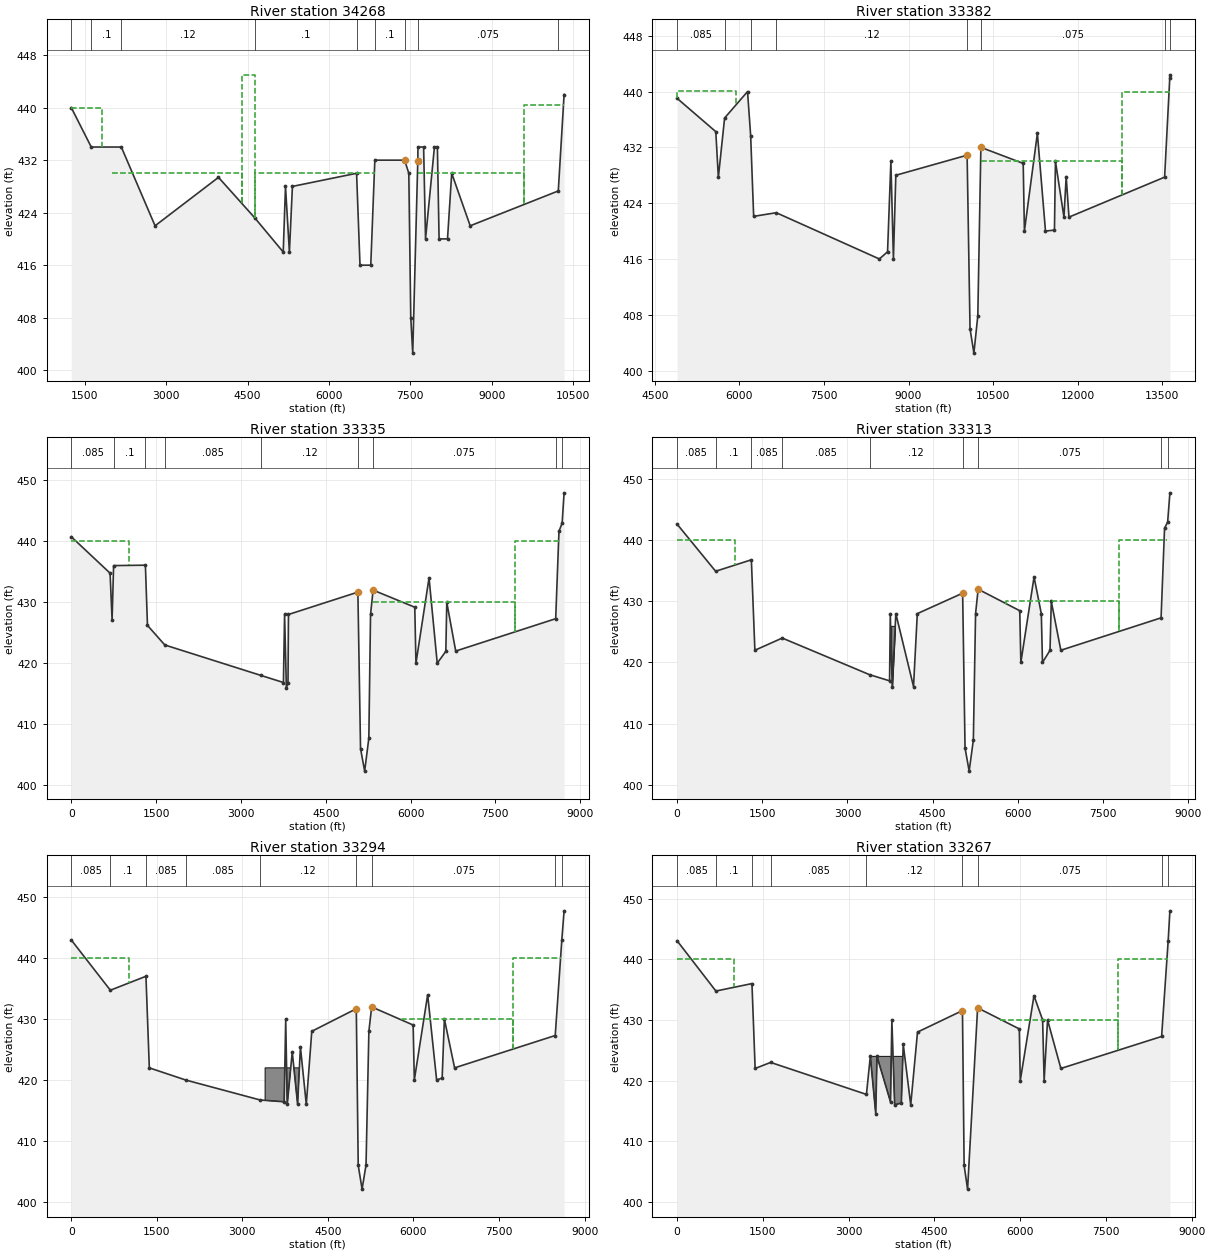
Type RM Length L Ch R = 1 ,34268   ,660,886,300
BEGIN DESCRIPTION:
34268-The reach length has been updated and it is the same with the 2018 georeferenced model.The ineffective at the ROB is updated to match the ineffectives from CADD_August2019 for elevation 440
STATIONS 7543-7573 ADDED FROM EFFECTIVE SECTION
FOR FLOWLINE
END DESCRIPTION:
XS GIS Cut Line= 6
   2438410.820076972007.010057152437369.399908976969485.31989056
 2437700.49504736968636.177888072438650.537110466966217.65286948
2439213.273845886965876.417987642440272.360966556963674.98177373
#Sta/Elev= 30
    1249     440  1616.8     434 2170.75     434 2793.01     422 3962.13  429.38
 4627.69  423.24 5155.75     418 5197.43     428 5269.62     418 5325.11     428
 6507.97     430    6571     416 6769.38     416 6844.63     432 7393.73     432
 7470.61     430 7506.88     408    7543   402.6 7636.07  431.81 7639.87     434
 7743.76     434 7778.93     420 7943.02     434 7997.58     434 8028.91     420
 8184.18     420 8261.76     430 8602.46     42210226.37  427.3110333.35     442
#Mann= 9 ,-1,0
    1249     .12       0  1616.8      .1       0 2170.75     .12       0
 4627.69      .1       0 6507.97    .045       0 6844.63      .1       0
 7393.73    .055       0 7639.87    .075       010226.37     .05       0
#XS Ineff= 6 ,-1
    1251 1822.01  440.01 2003.31    4389     430 4389.04 4626.26     445
 4626.26    6844     430    7639    9600     430    960010326.63 440.463
Permanent Ineff=
       F       F       T       F       F       F
Bank Sta=7393.73,7636.07
XS Rating Curve= 0 ,0
Exp/Cntr=0.3,0.1

Type RM Length L Ch R = 1 ,33382   ,56,47,10
BEGIN DESCRIPTION:
33382-The reach length has been updated and it is the same with the 2018 georeferenced model. The ineffective at the ROB is updated to match the ineffectives from CADD_August2019 for elevation 440
END DESCRIPTION:
XS GIS Cut Line= 6
  2438386.7098826971935.910133732438270.867922316969406.60055982
2438292.569322476969094.10052864 2438626.77075386967522.91994397
2439276.50993988 6966651.8800194 2440305.73983686963621.36016181
#Sta/Elev= 30
    4895  439.03 5581.54  434.25 5626.66  427.69 5737.79  436.21 6144.54     440
 6199.87  433.68 6253.14  422.11 6654.71  422.63 8482.86     416 8628.25  417.03
  8687.4  429.99 8732.44     416 8775.09     42810039.77  430.8810091.57     406
   10160   402.510229.52  407.8710283.96     432 11034.7   429.711056.13     420
11286.22     43411430.16     42011589.17  420.1411606.73     43011757.83     422
11797.07  427.8111846.53     42213543.34  427.7313635.08     44213636.92   442.4
#Mann= 8 ,-1,0
    4895    .085       0 5737.79      .1       0 6199.87    .085       0
 6654.71     .12       010039.77    .055       010283.96    .075       0
13543.34     .05       013635.08    .075       0
#XS Ineff= 4 ,-1
    4895 5935.21 440.011    6137    9895     430   10283   12790     430
   12790   13636     440
Permanent Ineff=
       T       F       F       F
Bank Sta=10039.77,10283.96
XS Rating Curve= 0 ,0
Exp/Cntr=0.3,0.1

Type RM Length L Ch R = 1 ,33335   ,55,22,13
BEGIN DESCRIPTION:
33335-The reach length has been updated and it is the same with the 2018 georeferenced model.The ineffective at the ROB is updated to match the ineffectives from CADD_August2019 for elevation 440
END DESCRIPTION:
XS GIS Cut Line= 6
  2438405.4798576971935.231329312438437.076579396970272.24712248
 2438395.84405036969130.753998642438688.812624476967524.85104248
2439284.515829386966668.731363642440320.431736566963618.92676772
#Sta/Elev= 30
       0  440.75  685.59  434.78  721.21  427.12  748.19  436.02 1310.33  436.09
 1346.95  426.21    1653     423 3354.07     418 3751.43  416.84 3771.72     428
 3803.44     416  3832.1   416.7 3840.67     428 5068.05  431.67 5115.05     406
    5188   402.3 5261.81   407.7 5291.99     428 5337.17     432 6074.34  429.19
 6095.09     420 6326.51     434 6471.56     420 6623.51  421.96 6640.13     430
 6798.23     422 8566.45  427.318624.399  441.65 8680.42     443 8714.93  447.96
#Mann= 9 ,-1,0
       0    .085       0  748.19      .1       0 1310.33    .085       0
    1653    .085       0 3354.07     .12       0 5068.05    .055       0
 5337.17    .075       0 8566.45     .05       0 8680.42    .075       0
#XS Ineff= 4 ,-1
       0 1028.53 440.013    1288    4867     430    5337    7840     430
    7840    8667     440
Permanent Ineff=
       T       F       F       F
Bank Sta=5068.05,5337.17
XS Rating Curve= 0 ,0
Exp/Cntr=0.3,0.1

Type RM Length L Ch R = 1 ,33313   ,50,19,13
BEGIN DESCRIPTION:
33313-The reach length has been updated and it is the same with the 2018 georeferenced model. The ineffective at the ROB is updated to match the ineffectives from CADD_August2019 for elevation 440
STATIONS 1060-1532 2009 CGP TOPOGRAPHY
END DESCRIPTION:
XS GIS Cut Line= 6
  2438449.0834456971937.828765062438492.486245476970352.54223748
2438502.251973976969218.644570892438747.477533396967524.85104248
2439295.437723556966671.986606482440324.843145066963618.92676772
#Sta/Elev= 30
       0  442.66  678.57  434.94 1307.99  436.82    1370     422 1852.02     424
 3390.11     418 3742.22  416.99  3754.7     428 3788.34     416 3852.63     428
 4163.98  416.06 4230.62     428 5029.25  431.35 5071.39     406    5144   402.2
  5217.9   407.3 5256.99     428 5302.07     432 6034.87  428.48 6054.32     420
 6286.96     434 6414.76     428 6435.46     420 6568.16  421.99  6590.6     430
 6758.66     422 8524.09  427.31 8585.43     442 8639.92     443 8679.42  447.79
#Mann= 9 ,-1,0
       0    .085       0  678.57      .1       0 1307.99    .085       0
 1852.02    .085       0 3390.11     .12       0 5029.25    .055       0
 5302.07    .075       0 8524.09     .05       0 8639.92    .075       0
#XS Ineff= 4 ,-1
     .47 1026.52  439.99    1325    4795     430    5795    7789     430
    7789    8627     440
Permanent Ineff=
       T       F       F       F
#Block Obstruct= 1 ,-1
    3770    3839     426
Bank Sta=5029.25,5302.07
XS Rating Curve= 0 ,0
Exp/Cntr=0.3,0.1

Type RM Length L Ch R = 1 ,33294   ,42,27,25
BEGIN DESCRIPTION:
33294-The reach length has been updated and it is the same with the 2018 georeferenced model. The ineffective at the ROB is updated to match the ineffectives from CADD_August2019 for elevation 440
STATIONS 1041-1614 2009 CGP TOPOGRAPHY
END DESCRIPTION:
XS GIS Cut Line= 6
  2438466.3977146971932.283172472438536.901182896969172.12694739
2438759.470619636967536.536714642439148.939656976966922.79351956
2439316.339584636966666.023363812440325.204364816963620.20858932
#Sta/Elev= 30
       0  442.98   684.7  434.74 1308.83  437.03    1368     422    2008     420
  3310.3  416.73 3732.68  416.43 3759.42     430 3786.24     416 3874.24   424.6
  3967.7  416.06 4017.49  425.41  4120.3     416 4216.51     428 4996.94   431.7
 5030.93     406  5098.5   402.1 5167.67  406.06 5217.83     428  5266.5     432
 5993.88  429.03 6014.47     420 6248.52     434 6405.88     420 6502.63  420.34
 6541.85     430 6720.75     422 8485.23  427.31 8600.85     443 8640.66  447.77
#Mann= 9 ,-1,0
       0    .085       0   684.7      .1       0 1308.83    .085       0
    2008    .085       0  3310.3     .12       0 4996.94    .055       0
  5266.5    .075       0 8485.23     .05       0 8600.85    .075       0
#XS Ineff= 4 ,-1
       0 1005.51     440    1322    4814     430    5795    7745     430
    7745    8582     440
Permanent Ineff=
       T       F       F       F
#Block Obstruct= 1 ,-1
    3398    4017     422
Bank Sta=4996.94,5266.5
XS Rating Curve= 0 ,0
Exp/Cntr=0.3,0.1

Type RM Length L Ch R = 1 ,33267   ,42,47,25
BEGIN DESCRIPTION:
33267-The reach length has been updated and it is the same with the 2018 georeferenced model. The ineffective at the ROB is updated to match the ineffectives from CADD_August2019 for elevation 440
STATIONS 1027-1778 2009 CGP TOPOGRAPHY
END DESCRIPTION:
XS GIS Cut Line= 6
  2438482.6266856971933.408498322438526.897593986970412.57525389
2438571.168174716969087.054282892438774.293424646967542.78342131
2439328.980635466966672.991853822440325.725689226963620.69152798
#Sta/Elev= 30
       0  443.06  678.41  434.77    1309     436 1364.94     422    1636     423
 3311.17  417.72 3379.19     424  3473.6  414.57 3495.88     424 3732.06  416.49
    3756     430 3804.84     416  3921.5   416.3 3954.56     426 4085.74     416
  4204.4     428 4990.42  431.55 5019.67     406    5080   402.1 5255.59     432
 5984.58  428.52  6001.4     420 6241.36     434 6392.41     430 6418.87     420
  6478.8     430 6711.57     422 8473.53  427.28 8587.49  442.97 8618.13     448
#Mann= 9 ,-1,0
       0    .085       0  678.41      .1       0    1309    .085       0
    1636    .085       0 3311.17     .12       0 4990.42    .055       0
 5255.59    .075       0 8473.53     .05       0 8587.49    .075       0
#XS Ineff= 4 ,-1
       0  994.94     440    1301    4782     430    5645    7714     430
    7714    8580     440
Permanent Ineff=
       T       F       F       F
#Block Obstruct= 1 ,-1
    3378    3953     424
Bank Sta=4990.42,5255.59
XS Rating Curve= 0 ,0
Exp/Cntr=0.3,0.1

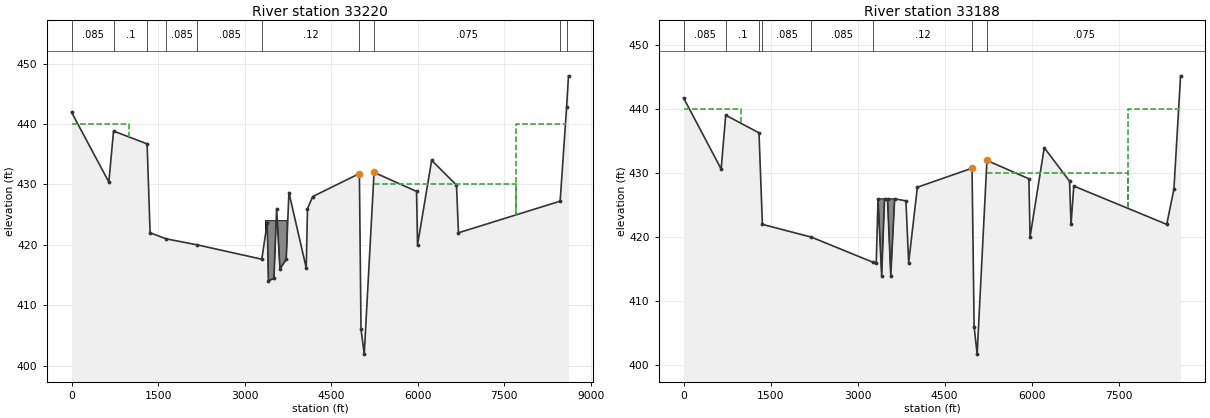
Type RM Length L Ch R = 1 ,33220   ,63,32,20
BEGIN DESCRIPTION:
33220-The reach length has been updated and it is the same with the 2018 georeferenced model. The ineffective at the ROB is updated to match the ineffectives from CADD_August2019 for elevation 440
STATIONS 1018-1847 2009 CGP TOPOGRAPHY
END DESCRIPTION:
XS GIS Cut Line= 6
   2438532.237156971926.218223972438601.681565146969031.25321339
2438801.33438106 6967542.53768692439387.271857476966661.46136506
2440174.614442886964094.320830062440326.789663466963622.57078931
#Sta/Elev= 30
       0  441.98  647.03   430.4   728.1  438.85  1309.7  436.73    1362     422
    1639     421    2180     420 3297.73  417.62 3390.82  423.64 3412.93     414
 3508.32  414.49 3554.53     426 3611.89     416 3720.65  417.58 3767.38  428.66
 4067.54  416.19 4089.48     426 4179.87     428 4988.64  431.81 5016.95     406
    5073   401.9 5242.89     432 5979.18  428.86 5996.39     420 6241.17     434
 6671.55   429.9 6705.82     422 8467.75  427.24 8580.33  442.89 8612.74     448
#Mann= 10 ,-1,0
       0    .085       0   728.1      .1       0  1309.7    .085       0
    1639    .085       0    2180    .085       0 3297.73     .12       0
 4988.64    .055       0 5242.89    .075       0 8467.75     .05       0
 8580.33    .075       0
#XS Ineff= 4 ,-1
       0  990.06 440.007    1320    4853     430    5243    7705     430
    7705    8573     440
Permanent Ineff=
       T       F       F       F
#Block Obstruct= 1 ,-1
    3362    3737     424
Bank Sta=4988.64,5242.89
XS Rating Curve= 0 ,0
Exp/Cntr=0.3,0.1

Type RM Length L Ch R = 1 ,33188   ,118,52,25
BEGIN DESCRIPTION:
33188-The reach length has been updated and it is the same with the 2018 georeferenced model. The ineffective at the ROB is updated to match the ineffectives from CADD_August2019 for elevation 440
STATIONS 1015-1794, 2009 CGP TOPOGRAPHY
END DESCRIPTION:
XS GIS Cut Line= 6
  2438555.1209626971901.796684892438606.02177955 6970289.9337669
2438627.723179716969083.336442562438857.75815272 6967542.5376869
2439413.313472056966670.142121972440331.151531386963676.44371305
#Sta/Elev= 30
       0  441.78  647.84  430.66  726.52  439.08 1300.35  436.32    1359     422
    2205     420  3271.2  416.05 3321.97  416.01 3352.08     426 3414.85     414
 3465.11     426 3516.09  425.95    3572     414 3639.22     426 3833.73  425.68
 3880.52     416 4030.41  427.81 4973.02  430.79 5009.14     406    5061   401.7
 5230.03     432 5953.65  429.13 5973.27     420 6217.76     434 6654.42  428.75
 6679.69     422 6727.25     428 8329.99     422 8453.57  427.52  8568.2  445.24
#Mann= 8 ,-1,0
       0    .085       0  726.52      .1       0 1300.35    .085       0
    1359    .085       0    2205    .085       0  3271.2     .12       0
 4973.02    .055       0 5230.03    .075       0
#XS Ineff= 4 ,-1
       0  994.02     440    1320    4973     430    5230    7662     430
    7662    8542     440
Permanent Ineff=
       T       F       F       F
#Block Obstruct= 1 ,-1
    3352    3639     426
Bank Sta=4973.02,5230.03
XS Rating Curve= 0 ,0
Exp/Cntr=0.3,0.1