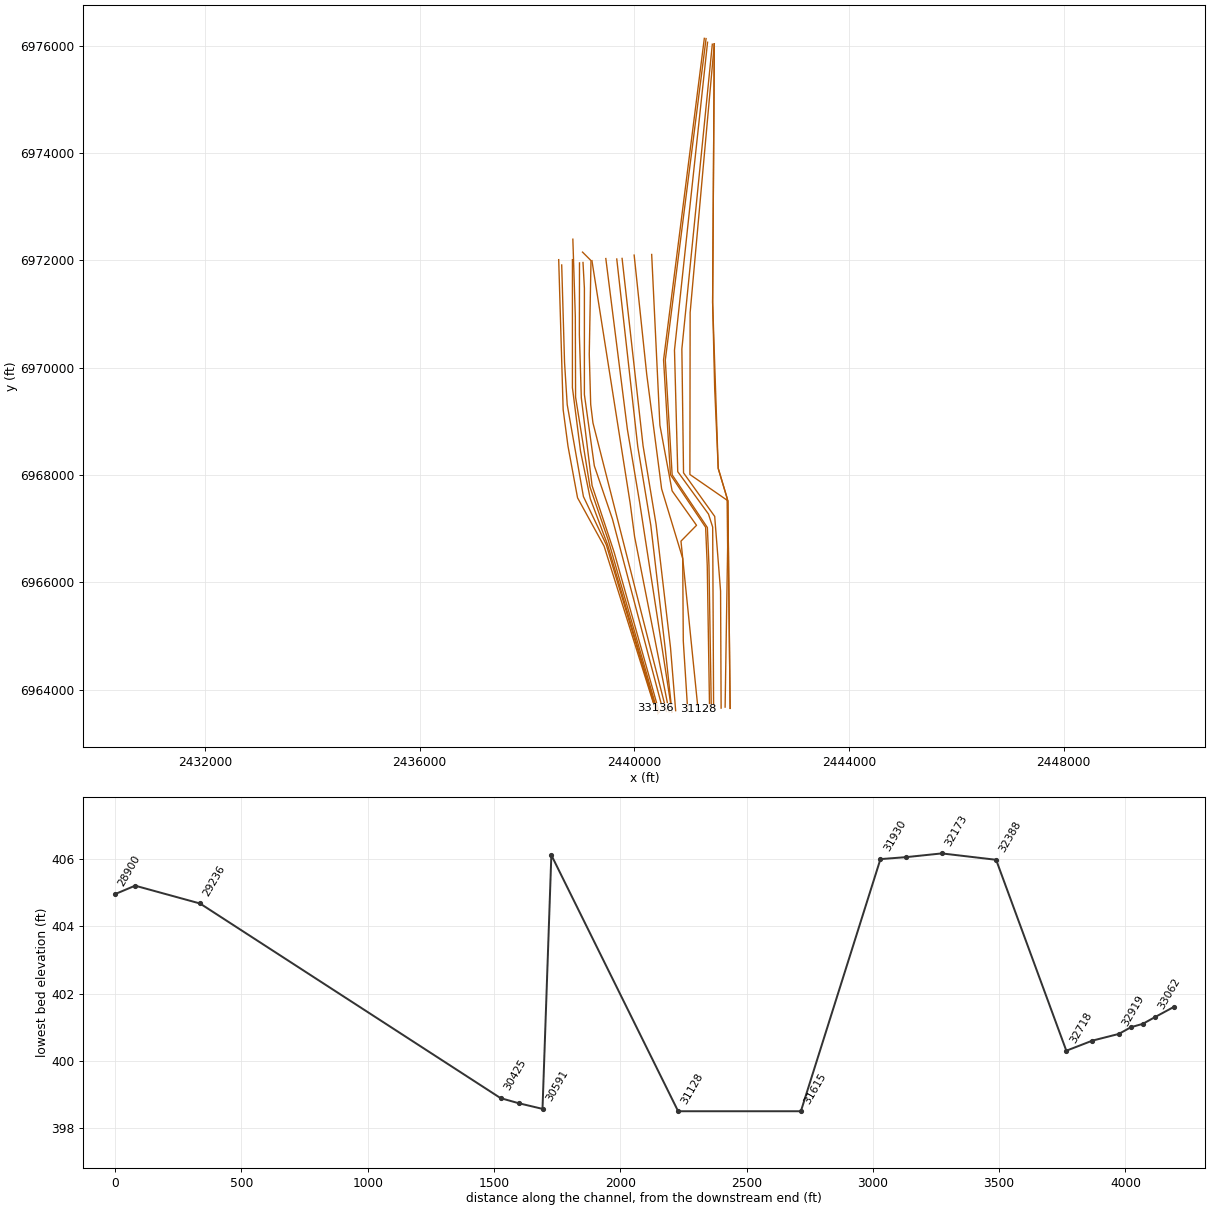
HEC-RAS study CDC_Consolidated_Model.prj: Upper Trinity CDC Consolidated Model

--- CDC_Consolidated_Model.g12 (geometry) --- (continued)

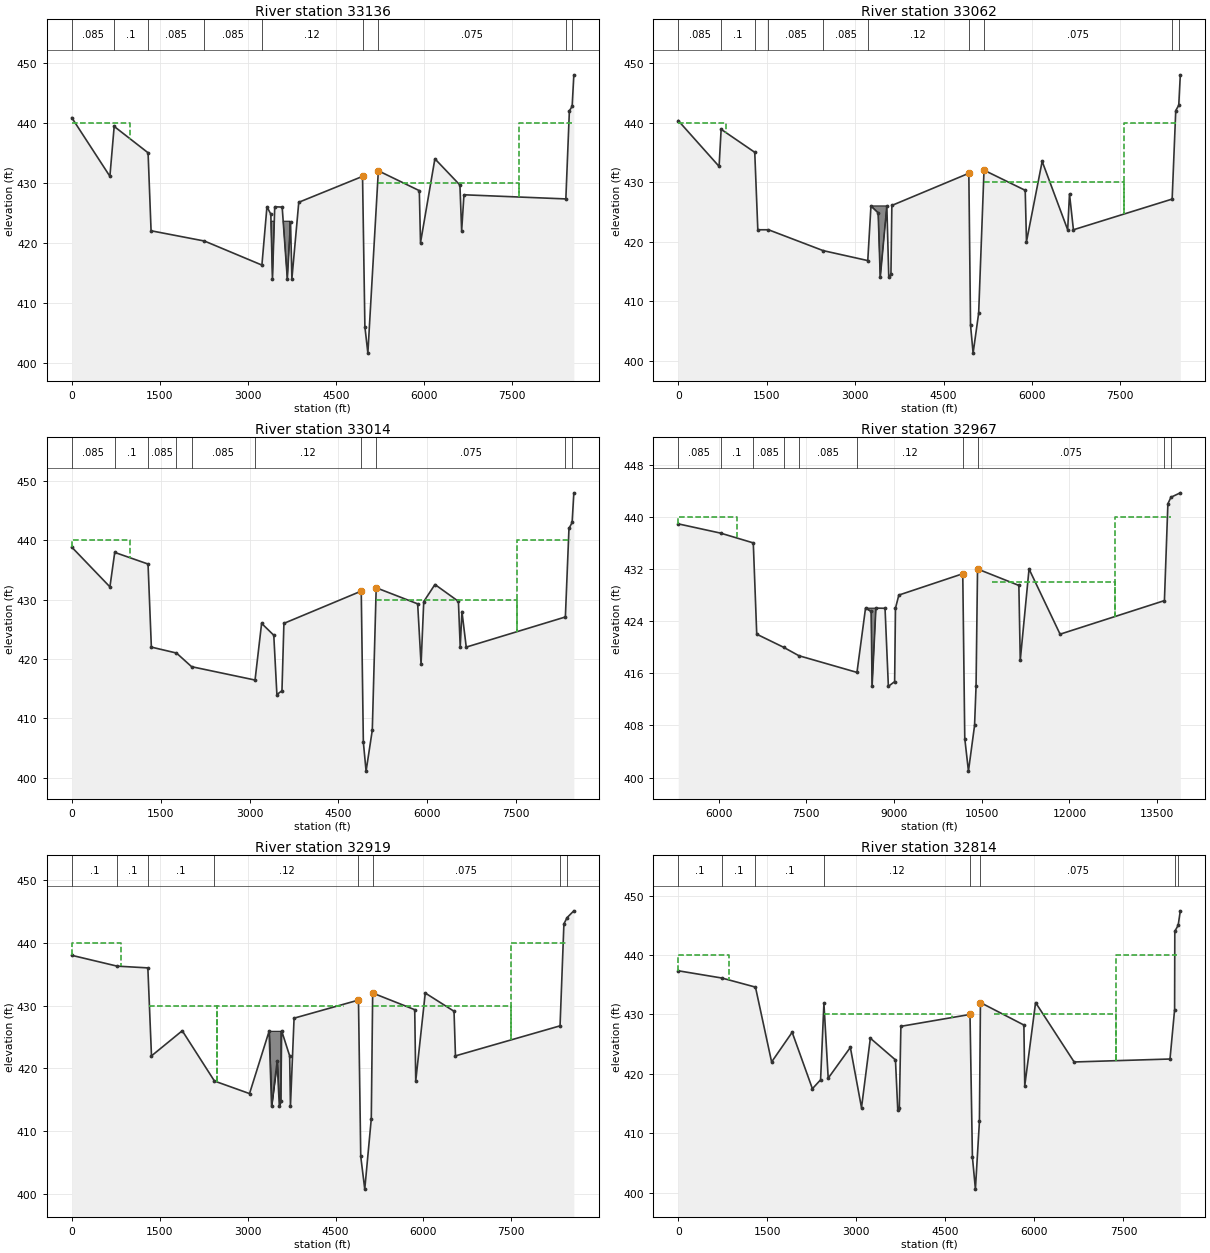
Type RM Length L Ch R = 1 ,33136   ,184,74,25
BEGIN DESCRIPTION:
33136-The reach length has been updated and it is the same with the 2018 georeferenced model.
STATIONS 1024-1873 2009 CGP TOPOGRAPHY
END DESCRIPTION:
XS GIS Cut Line= 6
2438590.401075886972015.513649062438673.477025236969220.41687706
2438763.768183226968538.219094492438941.706147556967577.18755198
2439436.497808896966676.146046982440386.298074636963652.28693722
#Sta/Elev= 30
       0  440.86  649.96  431.08  722.97   439.4    1301     435    1352     422
 2261.87  420.29 3241.53  416.28 3327.43     426 3393.52  424.76 3421.65     414
 3460.22     426 3586.96  425.95 3674.75     414  3729.4  423.52 3752.83     414
  3869.9  426.75 4957.16  431.07 4997.22     406    5048   401.6 5226.59     432
 5924.98  428.69  5945.4     420 6190.62     434  6617.3  429.62 6646.77     422
 6686.18     428  8423.1  427.31  8483.3     442  8530.5  442.74 8559.47     448
#Mann= 9 ,-1,0
       0    .085       0  722.97      .1       0    1301    .085       0
 2261.87    .085       0 3241.53     .12       0 4957.16    .055       0
 5226.59    .075       0  8423.1     .05       0  8530.5    .075       0
#XS Ineff= 4 ,-1
       0  996.68  439.99    1300    4815     430    5227    7618     430
    7618    8520     440
Permanent Ineff=
       T       F       F       F
#Block Obstruct= 1 ,-1
    3327    3717   423.6
Bank Sta=4957.16,5226.59
XS Rating Curve= 0 ,0
Exp/Cntr=0.3,0.1

Type RM Length L Ch R = 1 ,33062   ,190,48,20
BEGIN DESCRIPTION:
33062-The reach length has been updated and it is the same with the 2018 georeferenced model.
STATIONS 1073-1948 2009 CGP TOPOGRAPHY
END DESCRIPTION:
XS GIS Cut Line= 6
2438646.363562396971916.28386064 2438699.51863986970095.41676748
2438748.997871556969314.167017642439051.081256886967600.62516914
2439478.164392226966699.583664152440390.031334896963658.91520481
#Sta/Elev= 30
       0  440.32  693.06  432.63  727.78  438.86    1298     435    1350     422
    1531     422 2458.68   418.5 3215.26  416.83 3269.16     426 3391.74  424.83
 3426.82     414 3538.61  425.96 3571.63     414  3608.2  414.51 3623.64  426.08
 4929.56  431.48 4958.48     406    5002   401.3 5096.21     408 5187.05     432
 5885.88  428.62 5907.44     420 6173.44  433.48 6606.15     422 6637.21     428
 6703.77     422 8378.48  427.15 8439.67     442 8490.72   442.9 8516.96     448
#Mann= 10 ,-1,0
       0    .085       0  727.78      .1       0    1298    .085       0
    1531    .085       0 2458.68    .085       0 3215.26     .12       0
 4929.56    .055       0 5187.05    .075       0 8378.48     .05       0
 8490.72    .075       0
#XS Ineff= 4 ,-1
       0  816.26 439.984    1300    4929     430    5187    7559     430
    7559    8450     440
Permanent Ineff=
       T       F       F       F
#Block Obstruct= 1 ,-1
    3269 3533.41     426
Bank Sta=4929.56,5187.05
XS Rating Curve= 0 ,0
Exp/Cntr=0.3,0.1

Type RM Length L Ch R = 1 ,33014   ,60,47,24
BEGIN DESCRIPTION:
33014-The reach length has been updated and it is the same with the 2018 georeferenced model.
STATIONS 1059-1985 2009 CGP TOPOGRAPHY
END DESCRIPTION:
XS GIS Cut Line= 6
2438846.289343646972015.82434398 2438845.87267786969631.35437539
2438997.695536886968443.333457482439178.685332396967561.56258322
2439501.602009396966702.187661562440395.831192056963661.45358557
#Sta/Elev= 30
       0  438.85  643.82  432.15  724.93  437.96    1287     436    1343     422
    1767     421    2022   418.7 3092.42  416.45 3203.19     426 3408.66     424
 3461.08     414 3546.68  414.65 3579.51     426 4884.41  431.44 4919.89     406
    4966   401.1 5070.81     408 5136.79     432 5836.33  429.29 5893.81  419.08
 5939.06  429.67 6127.95  432.55 6523.96  429.71  6554.5     422 6583.38     428
 6656.08     422 8328.81  427.08  8389.5     4428442.689     443 8471.68     448
#Mann= 10 ,-1,0
       0    .085       0  724.93      .1       0    1287    .085       0
    1767    .065       0    2022    .085       0 3092.42     .12       0
 4884.41    .055       0 5136.79    .075       0 8328.81     .05       0
8442.689    .075       0
#XS Ineff= 4 ,-1
       0  986.23     440    1300    4884     430    5137    7516     430
    7516    8432     440
Permanent Ineff=
       T       F       F       F
Bank Sta=4884.41,5136.79
XS Rating Curve= 0 ,0
Exp/Cntr=0.3,0.1

Type RM Length L Ch R = 1 ,32967   ,54,48,60
BEGIN DESCRIPTION:
32967-The reach length has been updated and it is the same with the 2018 georeferenced model.
STATIONS 6649-7540 2009 CGP TOPOGRAPHY
END DESCRIPTION:
XS GIS Cut Line= 6
2438854.218789736972396.935130312438900.039564226970957.39601465
2438905.247887136969452.187738982439173.477009486967777.70847639
2439514.622980716966785.521156312440441.649341886963559.06993206
#Sta/Elev= 30
    5308  438.92 6032.72   437.5    6592     436    6651     422    7109     420
    7372   418.7 8365.91  416.14 8512.22     426 8609.06  425.49 8624.53     414
 8689.68     426    8846  425.97 8903.09     414  9010.2  414.73 9024.68     426
 9082.24     42810175.69  431.2710210.15     406   10273     40110377.47     408
10403.06     41410428.55     43211135.59  429.48 11159.4     41811309.65     432
11840.67     42213625.75  427.1513684.97     44213737.19     44313897.58  443.68
#Mann= 10 ,-1,0
    5308    .085       0 6032.72      .1       0    6592    .085       0
    7109    .065       0    7372    .085       0 8365.91     .12       0
10175.69    .055       010428.55    .075       013625.75     .05       0
13737.19    .075       0
#XS Ineff= 4 ,-1
    5308 6311.36     440    6610    9837     430   10683   12779     430
   12779   13731     440
Permanent Ineff=
       T       F       F       F
#Block Obstruct= 1 ,-1
    8512    8689     426
Bank Sta=10175.69,10428.55
XS Rating Curve= 0 ,0
Exp/Cntr=0.3,0.1

Type RM Length L Ch R = 1 ,32919   ,96,105,140
BEGIN DESCRIPTION:
32919-The reach length has been updated and it is the same with the 2018 georeferenced model.
STATIONS 1121-2008 2009 CGP TOPOGRAPHY
END DESCRIPTION:
XS GIS Cut Line= 6
2438978.164407976971954.791985722438975.56041056 6970621.4583663
2439012.018670986969439.166767642439212.539595386967803.75009097
2439624.596842146966558.257175152440465.143717476963577.18767798
#Sta/Elev= 30
       0     438  773.64  436.28    1298     436    1360     422    1885     426
    2434     418 3032.56     416 3366.44  425.92 3408.73     414 3503.52  421.11
 3541.11     414 3567.44   414.8 3580.24     426 3717.19     422  3730.7     414
 3792.53     428 4891.32  430.88 4930.08     406  4998.5   400.8 5109.91     412
 5133.63     432 5850.98  429.35 5868.12     418 6030.78     432 6521.42   429.1
 6545.95     422 8330.31  426.78 8396.04     443 8450.28     444 8565.57  445.08
#Mann= 8 ,-1,0
       0      .1       0  773.64      .1       0    1298      .1       0
    2434     .12       0 4891.32    .055       0 5133.63    .075       0
 8330.31     .05       0 8450.28    .075       0
#XS Ineff= 5 ,-1
       0  847.92 439.982    1319    2472     430    2472    4652     430
    5133    7501     430    7501    8434     440
Permanent Ineff=
       T       T       F       F       F
#Block Obstruct= 1 ,-1
    3347    3561     426
Bank Sta=4891.32,5133.63
XS Rating Curve= 0 ,0
Exp/Cntr=0.3,0.1

Type RM Length L Ch R = 1 ,32814   ,176,103,118
BEGIN DESCRIPTION:
32814-The reach length has been updated and it is the same with the 2018 georeferenced model.
Valley storage mitigation site for CDC GP091010-1 Palace Parkway.
Cross-sections 32814 - 33335.  Located in LOB.
CDC GP071315-1 IH-30 Westbound Frontage Road
Cross-sections 32718 - 40850.
Location in ROB.  Included mitigation swale.
CDC GP083121-1 Hunter-Ferrell Industrial
Cross-sections 32814 - 34268
END DESCRIPTION:
XS GIS Cut Line= 6
2439043.268608476971962.604306062439069.310223066971483.43794157
2439069.310223066969501.666970732439254.206178726968173.54200231
2439592.747824486967178.750356732440522.435269556963657.91684723
#Sta/Elev= 30
       0  437.35  734.53  436.13 1300.87   434.6    1573     422    1919     427
    2260   417.5    2398     419 2453.98  431.86 2526.28  419.27 2899.42  424.45
 3087.14   414.3 3236.11     426 3659.15  422.35 3697.63     414  3724.3  414.18
 3750.49     428 4914.83     430 4955.55     406 5005.95   400.6 5073.61     412
 5090.65     432 5822.57  428.22 5837.23     418 6019.54     432 6668.99     422
 8283.91   422.5 8361.51  430.82 8364.84     444 8421.34     445 8457.54  447.44
#Mann= 8 ,-1,0
       0      .1       0  734.53      .1       0 1300.87      .1       0
 2453.98     .12       0 4914.83    .055       0 5090.65    .075       0
 8361.51     .05       0 8421.34    .075       0
#XS Ineff= 5 ,-1
       0  854.34     440    1300 2453.98  431.86 2453.98    4614     430
    5322    7377     430    7377    8408     440
Permanent Ineff=
       T       T       F       F       F
Bank Sta=4914.83,5090.65
XS Rating Curve= 0 ,0
Exp/Cntr=0.3,0.1

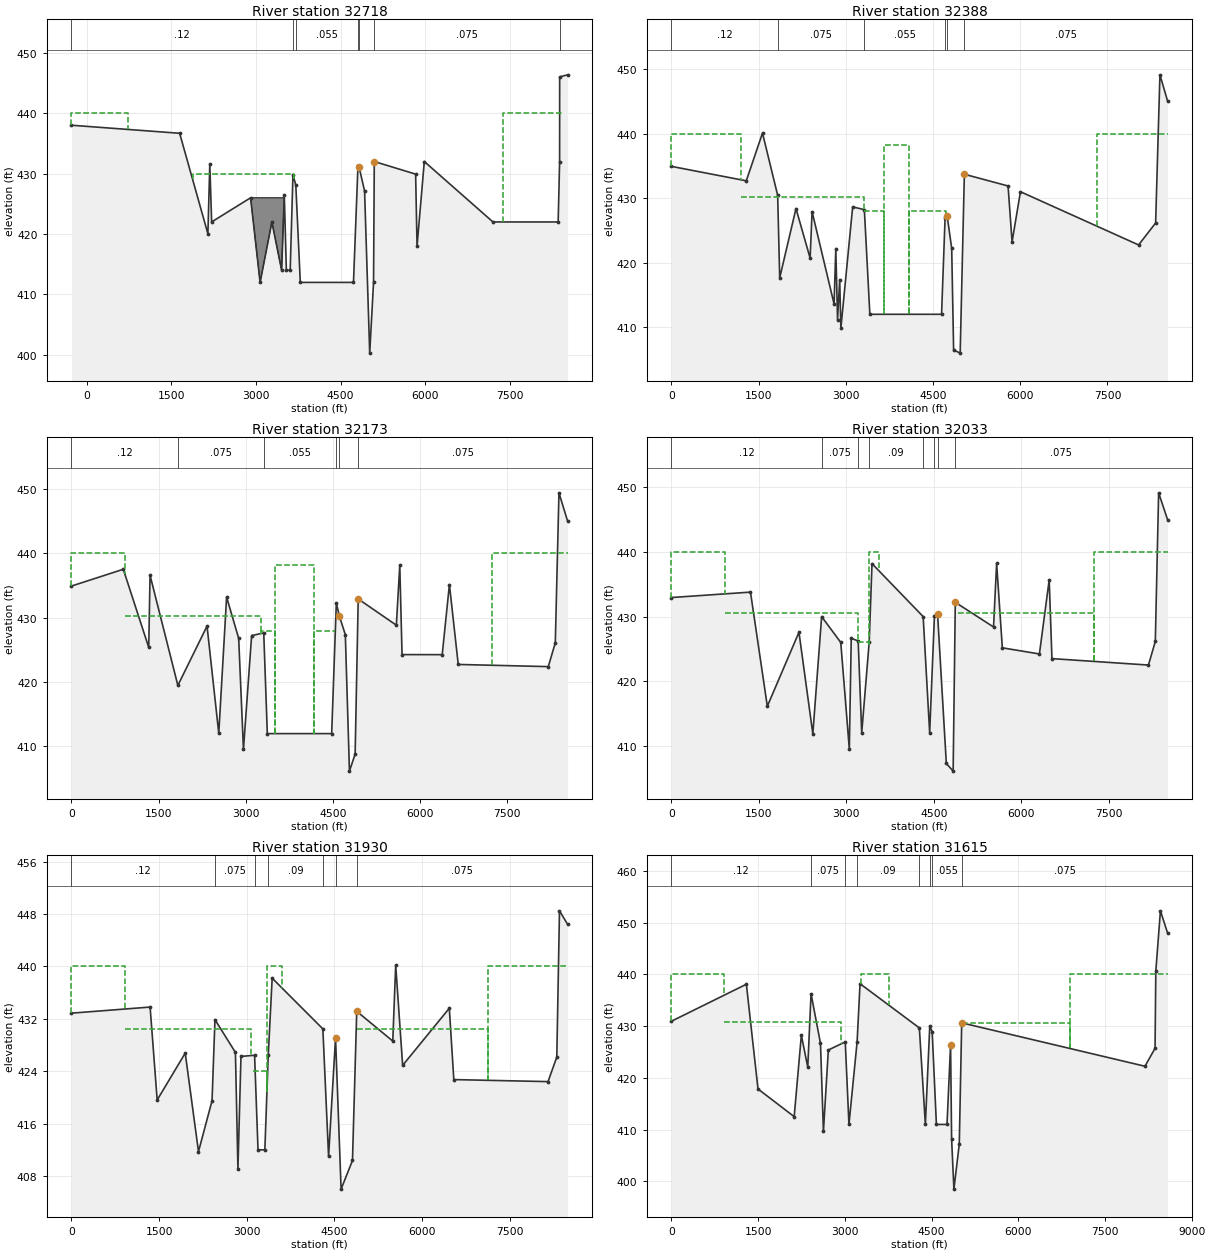
Type RM Length L Ch R = 1 ,32718   ,395,278,194
BEGIN DESCRIPTION:
32718-The reach length has been updated and it is the same with the 2018 georeferenced model.
END DESCRIPTION:
XS GIS Cut Line= 6
2439034.396907056972156.098669722439192.316210646971998.17936614
2439160.125658216970253.869862652439186.673833476969318.20244265
2439228.774471066968973.584365472440599.966282476963593.97012472
#Sta/Elev= 30
    -274     438 1645.33  436.67  2146.9  420.04 2180.41  431.63 2213.04     422
  2904.5     426 3073.18     412 3282.16     422  3454.8  414.03 3502.41  426.43
 3539.08     414 3607.21  414.05 3656.02  429.85 3706.95  428.07 3786.36     412
 4730.02     412 4809.42  431.25 4829.96  431.06    4927  427.12    5018   400.3
  5086.1     412 5099.32     432 5832.82  429.91  5857.9     418 5986.64     432
 7204.81     422 8361.98     422 8387.96     432 8388.63     446 8529.56  446.34
#Mann= 7 ,-1,0
    -274     .12       0 3656.02     .07       0 3706.95    .055       0
 4809.42     .07       0 4829.96    .055       0 5099.32    .075       0
 8387.96     .05       0
#XS Ineff= 4 ,-1
    -274     725     440    1874    3675     430    3675    4857   425.5
    7383    8423     440
Permanent Ineff=
       F       F       T       F
#Block Obstruct= 1 ,-1
    2904    3503     426
Bank Sta=4829.96,5099.32
XS Rating Curve= 0 ,0
Exp/Cntr=0.3,0.1

Type RM Length L Ch R = 1 ,32388   ,221,215,150
XS GIS Cut Line= 4
2439209.891306716971996.536980972439922.854447726967472.91479464
2440005.028495976966852.165379972440649.094465056963587.44225064
#Sta/Elev= 30
       0  434.93 1287.85  432.69 1566.82  440.09  1827.8  430.44 1862.79  417.65
 2142.76  428.39 2385.73  420.71 2419.73   427.9 2797.68  413.61 2827.68  422.19
 2857.67  411.12 2894.67  417.39 2914.67  409.84 3117.64  428.65 3318.82  428.22
 3413.29     412 4646.79     412 4706.97  426.86 4742.18  427.29 4821.08  422.22
 4854.03  406.47 4966.88  405.98 5038.79  433.71 5790.57  431.89 5859.57  423.23
 6003.57     431 8035.57  422.75 8328.57  426.15 8402.57  449.12 8533.57  445.08
#Mann= 6 ,-1,0
       0     .12       0  1827.8    .075       0 3318.82    .055       0
 4706.97    .075       0 4742.18    .055       0 5038.79    .075       0
#XS Ineff= 6 ,-1
       0    1200     440    1200    3318  430.25    3318    3660     428
    3660    4080   438.2    4080    4727     428 7327.57 8533.57     440
Permanent Ineff=
       F       F       T       T       T       F
Bank Sta=4742.18,5038.79
XS Rating Curve= 0 ,0
Exp/Cntr=0.3,0.1

Type RM Length L Ch R = 1 ,32173   ,207,140,105
XS GIS Cut Line= 4
2439468.571891736972035.816429972439870.97430214 6968849.8401904
2440097.891171146967497.746109812440702.019884146963580.41011247
#Sta/Elev= 30
       0  434.93   892.8  437.54  1330.7   425.4 1353.69   436.6 1832.57  419.49
 2335.47  428.71 2537.43  412.04 2672.41  433.22 2880.38   426.8 2962.36  409.55
 3103.34  427.23 3311.86  427.65 3373.68     412 4482.12     412 4562.37  432.28
 4615.36  430.23 4717.36  427.39 4788.36  406.17 4886.36  408.82 4939.36  432.93
 5596.36  428.85 5655.36  438.18 5694.36  424.28 6386.36  424.27 6510.36  435.17
 6662.36  422.75 8213.36  422.41 8334.36  426.11 8397.36  449.42 8546.36  445.03
#Mann= 6 ,-1,0
       0     .12       0 1832.57    .075       0 3311.86    .055       0
 4562.37    .075       0 4615.36    .055       0 4939.36    .075       0
#XS Ineff= 6 ,-1
       0     920     440     920    3260  430.25    3260    3507     428
    3507    4178   438.2    4178    4548     428 7246.14 8546.14     440
Permanent Ineff=
       F       F       T       T       T       F
Bank Sta=4615.36,4939.36
XS Rating Curve= 0 ,0
Exp/Cntr=0.3,0.1

Type RM Length L Ch R = 1 ,32033   ,140,103,93
XS GIS Cut Line= 5
2439672.446155896972027.612050062440063.364665396968535.40906073
2440306.460963966967068.149528062440575.076568476964771.91954048
2440702.019884146963580.41011247
#Sta/Elev= 30
       0  432.95 1356.61  433.79 1645.53  416.11 2188.39  427.57 2426.35  411.83
 2577.32  429.99 2905.26     426 3052.23   409.5 3085.22  426.64 3204.08  426.23
  3264.9     412 3392.94     426 3441.74   438.2    4319     430  4430.7     412
 4512.37  430.08 4565.63  430.47 4716.56  407.26  4833.5  406.06 4870.48  432.21
 5526.42  428.39 5579.42  438.23 5677.42  425.16 6313.42  424.21 6481.42  435.68
 6528.42  423.49 8183.98  422.49 8301.87  426.15 8358.81  449.17 8511.66  445.03
#Mann= 8 ,-1,0
       0     .12       0 2577.32    .075       0 3204.08    .055       0
 3392.94     .09       0    4319    .055       0 4512.37    .075       0
 4565.63    .055       0 4870.48    .075       0
#XS Ineff= 7 ,-1
       0     920     440     920    3200   430.5    3200    3389     426
    3389    3556     440    4200    4550     427 4916.37 7246.14   430.5
 7246.14 8546.14     440
Permanent Ineff=
       F       F       T       F       T       F       F
Bank Sta=4565.63,4870.48
XS Rating Curve= 0 ,0
Exp/Cntr=0.3,0.1

Type RM Length L Ch R = 1 ,31930   ,747,315,244
XS GIS Cut Line= 5
 2439771.82555036972038.73669973 2440162.45075336968549.15345581
2440405.506369556967082.139657562440674.603600386964781.79255223
2440770.089629896963609.91727132
#Sta/Elev= 30
       0  432.86 1345.76  433.79 1466.73  419.61 1946.66  426.76 2173.63  411.73
  2405.6  419.49 2455.59  431.87 2805.56  426.87 2848.55  409.09 2900.55  426.26
  3133.6  426.43 3192.36     412 3309.28     412 3367.33  426.43 3434.65   438.2
  4301.9  430.46 4399.87     411 4518.85  429.04    4614     406 4808.71  410.37
 4881.67  433.14 5498.39   428.6 5548.37   440.2 5667.32  424.89 6465.97  433.61
 6542.93  422.72 8155.31  422.41  8305.3  426.16  8351.3  448.48  8490.3  446.42
#Mann= 7 ,-1,0
       0     .12       0 2455.59    .075       0  3133.6    .055       0
 3367.33     .09       0  4301.9    .055       0 4518.85    .055       0
 4881.67    .075       0
#XS Ineff= 7 ,-1
       0     920     440     920    3070   430.5    3100    3345     424
    3345    3605     440    4100    4500     426 4881.67  7120.3   430.5
  7120.3  8490.3     440
Permanent Ineff=
       F       F       T       F       T       F       F
Bank Sta=4518.85,4881.67
XS Rating Curve= 0 ,0
Exp/Cntr=0.3,0.1

Type RM Length L Ch R = 1 ,31615   ,493,486,211
XS GIS Cut Line= 6
2439996.652200396972100.368794312440231.027059726969878.14653273
2440508.805047476967742.729871812440901.472241136966446.64978682
2440912.450893726964908.528519232440994.915951896963610.78537981
#Sta/Elev= 30
       0  430.95 1296.75   438.1 1497.71  417.86  2123.6  412.51 2247.57  428.24
 2358.53  422.09 2415.52  436.26 2578.46  426.67 2629.45  409.65 2714.42  425.39
 3007.13  426.96 3070.97     411 3212.13  426.96 3262.87   438.2 4288.53  429.66
 4392.75     411 4468.75     430 4510.45  428.91  4583.6     411    4767     411
 4828.72  426.35 4846.45  408.24 4886.36   398.5  4979.3  407.18 5021.26  430.64
 8190.88  422.25 8365.78  425.72 8378.77  440.62 8458.72  452.29 8581.65  448.03
#Mann= 8 ,-1,0
       0     .12       0 2415.52    .075       0 3007.13    .055       0
 3212.13     .09       0 4288.53    .055       0 4468.75    .075       0
 4510.45    .055       0 5021.26    .075       0
#XS Ineff= 7 ,-1
       0     908     440     908    2940  430.71    3000    3200     420
    3279    3760     440    4150    4510     428 5021.26    6887  430.64
    6887 8581.65     440
Permanent Ineff=
       F       F       T       F       T       F       F
Bank Sta=4828.72,5021.26
XS Rating Curve= 0 ,0
Exp/Cntr=0.3,0.1

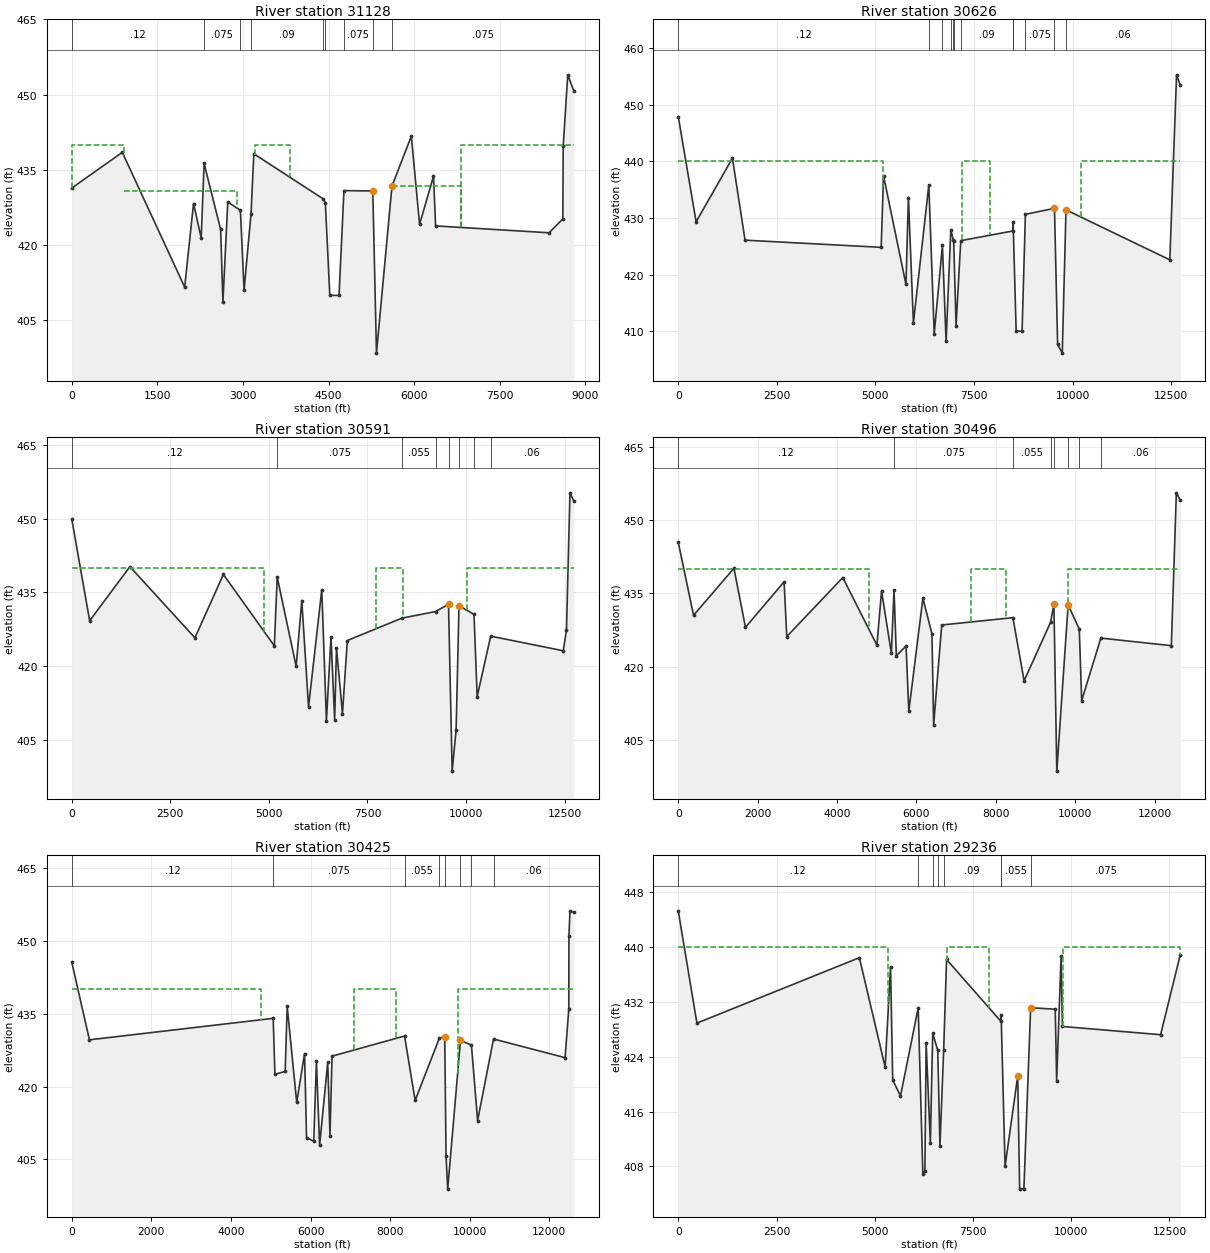
Type RM Length L Ch R = 1 ,31128   ,293,502,246
XS GIS Cut Line= 6
2440323.339539146972112.339242822440476.619744396968929.16811574
2440704.206887636967706.178435732441159.277171726967064.16233131
2440869.346321146966769.023157812441187.054675226963638.81485131
#Sta/Elev= 30
       0  431.38  885.83  438.49  1978.6  411.65 2134.56  428.29 2268.51  421.42
 2319.48  436.28 2609.36  423.14 2649.35  408.65 2734.31   428.6    2956  426.94
 3019.76     411    3142   426.3 3190.88   438.2 4404.06  429.24 4444.27  428.48
 4522.53     410 4684.53     410 4770.61  430.87 5276.29   430.8 5340.74   398.5
 5612.05  431.75 5951.57  441.72 6096.35  424.15 6340.12  433.74 6377.11  423.84
 8365.68  422.47 8606.58  425.23 8613.58  439.74 8693.55  453.93 8799.51  450.73
#Mann= 9 ,-1,0
       0     .12       0 2319.48    .075       0    2956    .055       0
    3142     .09       0 4404.06    .075       0 4444.27    .055       0
 4770.61    .075       0 5276.29    .055       0 5612.05    .075       0
#XS Ineff= 7 ,-1
       0     912     440     912    2890   430.8    2950    3120     419
    3210    3825     440    4150    4450  421.85 5612.05 6813.73  431.75
 6813.73 8799.51     440
Permanent Ineff=
       F       F       T       F       T       F       F
Bank Sta=5276.29,5612.05
XS Rating Curve= 0 ,0
Exp/Cntr=0.3,0.1

Type RM Length L Ch R = 1 ,30626   ,90,35,145
BEGIN DESCRIPTION:
31471 - The reach length has been updated and it is the same with the 2018 georeferenced model.
Than bank station has been revised from the CDC model to match the channel location.
END DESCRIPTION:
XS GIS Cut Line= 6
2441304.614151396976140.389913722440544.760356146970147.18438047
2440672.51764655 6968008.93242342441328.70170164 6967027.2965914
2441358.913255396966315.10608664 2441401.86166036963659.15470564
#Sta/Elev= 30
       0  447.92  452.94  429.32 1373.81  440.57 1693.77  426.08  5146.2  424.81
 5206.19  437.46 5775.08  418.26 5837.07  433.61 5964.04  411.42 6354.91  435.87
 6491.86  409.53 6699.79  425.16 6792.75   408.2 6912.71  427.92 6975.41  426.06
 6985.61  425.99 7045.61     411 7165.61  425.99 8481.16   427.7 8492.63  429.34
    8570     410    8720     410 8804.33  430.64 9542.24  431.71 9621.24  407.69
 9739.24  406.12 9834.24  431.4312467.42   422.612638.42  455.2912733.42  453.45
#Mann= 12 ,-1,0
       0     .12       0 6354.91    .075       0 6699.79    .055       0
 6912.71    .075       0 6975.41     .09       0 6985.61    .055       0
 7165.61     .09       0 8481.16    .075       0 8492.63    .055       0
 8804.33    .075       0 9542.24    .055       0 9834.24     .06       0
#XS Ineff= 5 ,-1
       0    5197     440    6960    7150   417.5    7204    7910     440
    8180    8450     424   1021112733.42     440
Permanent Ineff=
       F       T       F       T       F
Bank Sta=9542.24,9834.24
XS Rating Curve= 0 ,0
Exp/Cntr=0.3,0.1

Type RM Length L Ch R = 1 ,30591   ,283,95,279
BEGIN DESCRIPTION:
With valley storage pond grading for CDC GP 070319-1.
New cross section
END DESCRIPTION:
XS GIS Cut Line= 6
  2441337.1662516976136.049699312440577.312456386970142.84416606
2440705.069746816968004.592208982441361.253801886967022.95637698
2441391.465355636966310.765872232441434.413760566963654.81449123
#Sta/Elev= 30
       0  449.97  453.94  429.23 1474.79  440.26 3123.56  425.75 3845.45  438.67
  5138.2  424.11 5210.19  438.13 5691.09  419.93 5834.07  433.34 6005.03  411.65
 6340.92  435.54 6458.87  408.89 6574.83  425.93  6667.8  408.99 6713.78  423.72
 6865.73  410.31 6988.68   425.2 8373.24  429.76 9226.24   431.1 9555.24   432.6
 9647.87  398.57 9748.24  406.98 9821.24  432.2610202.12  430.5410282.04  413.77
 10624.7  426.0912465.42  423.1112547.42  427.3212635.42  455.3112733.42  453.61
#Mann= 8 ,-1,0
       0     .12       0 5210.19    .075       0 8373.24    .055       0
 9226.24    .075       0 9555.24    .055       0 9821.24     .06       0
10202.12    .045       0 10624.7     .06       0
#XS Ineff= 3 ,-1
       0  4881.7     440  7704.1  8406.3     440 10020.312733.42     440
Permanent Ineff=
       F       F       F
Bank Sta=9555.24,9821.24
XS Rating Curve= 0 ,0
Exp/Cntr=0.3,0.1

Type RM Length L Ch R = 1 ,30496   ,303,71,627
BEGIN DESCRIPTION:
With valley storage pond and outfall grading for CDC GP 070319-1.
New cross section
END DESCRIPTION:
XS GIS Cut Line= 6
  2441364.7075356976067.382513812440748.388229716970329.53539373
2440809.152215816968063.910331822441382.068720896967273.97982506
2441460.19389272 6967030.92420882441477.554750386963654.18818015
#Sta/Elev= 30
       0  445.45  384.92  430.55 1402.71  440.15 1692.65   428.1 2665.47  437.38
 2733.46  426.21 4144.19  438.25 5004.13  424.45 5120.13  435.51 5367.13  422.84
 5435.13  435.75 5493.13  422.28 5738.13  424.29 5807.12  410.97 6161.97  434.03
 6389.88  426.76 6432.86   408.2 6635.78  428.57 8428.58  430.07 8711.31  417.18
 9377.26  429.11 9462.26  432.83 9534.65  398.74 9820.26  432.6810101.26  427.72
10161.26  413.1510644.18   425.912419.92  424.3512545.91  455.5512645.89  454.07
#Mann= 8 ,-1,0
       0     .12       0 5435.13    .075       0 8428.58    .055       0
 9377.26    .075       0 9462.26    .055       0 9820.26     .06       0
10101.26    .045       010644.18     .06       0
#XS Ineff= 3 ,-1
       0  4801.3     440  7381.9 8251.26     440  9810.412645.89     440
Permanent Ineff=
       F       F       F
Bank Sta=9462.26,9820.26
XS Rating Curve= 0 ,0
Exp/Cntr=0.3,0.1

Type RM Length L Ch R = 1 ,30425   ,206,1190,545
BEGIN DESCRIPTION:
With valley storage pond and outfall grading for CDC GP 070319-1.
New cross section
END DESCRIPTION:
XS GIS Cut Line= 6
  2441453.6282896976031.204108482440885.920106896970348.91232347
2440917.170044396968041.620678232441497.899197896967230.16232739
2441607.274307226965839.537483982441617.690953056963657.24558873
#Sta/Elev= 30
       0  445.59   443.8  429.61  5060.6  434.03  5104.6   422.5  5361.6  423.12
  5412.6  436.47 5651.59  416.73 5848.39  426.78 5899.32   409.5 6079.05  408.73
 6146.95  425.21 6226.83  407.89 6430.72  424.97 6487.69   409.9 6538.67  426.25
 8361.24  430.39 8627.24  417.13 9237.82     430 9370.78  430.18 9403.74  405.78
 9444.98  398.89 9766.36   429.510041.09  428.5210196.94     41310596.79  429.78
12393.79  425.9412487.79  435.9412490.79  450.9512516.79  456.1512613.79  455.81
#Mann= 8 ,-1,0
       0     .12       0  5060.6    .075       0 8361.24    .055       0
 9237.82    .075       0 9370.78    .055       0 9766.36     .06       0
10041.09    .045       010596.79     .06       0
#XS Ineff= 3 ,-1
       0  4760.2     440  7083.7    8153     440  9692.912613.79     440
Permanent Ineff=
       F       F       F
Bank Sta=9370.78,9766.36
XS Rating Curve= 0 ,0
Exp/Cntr=0.3,0.1

Type RM Length L Ch R = 1 ,29236   ,332,257,0.01
BEGIN DESCRIPTION:
29040
END DESCRIPTION:
XS GIS Cut Line= 5
2441490.811941716976037.524961982441040.274128886971030.86305931
2441035.617314066968011.366801722441743.576856146967521.87827939
2441785.613189386963652.51725173
#Sta/Elev= 30
       0   445.3  473.99  428.91 4608.75  438.46 5264.63   422.5  5402.6  437.11
 5457.59  420.63 5655.54  418.27 6106.43  431.14  6224.4  406.87 6276.39   407.3
 6308.38  426.06 6415.35  411.45 6475.34  427.44  6603.9  424.93 6659.52     411
  6753.9  424.93  6828.1   438.2 8201.92  429.23 8216.86  430.13    8317     408
 8638.12  421.17 8687.83  404.75 8795.82  404.68  8967.8  431.16  9593.8  430.94
  9629.8  420.52  9742.8  438.69  9776.8  428.42 12274.8  427.22 12776.8  438.92
#Mann= 8 ,-1,0
       0     .12       0 6106.43    .055       0 6475.34     .07       0
  6603.9    .055       0  6753.9     .09       0 8201.92     .07       0
 8216.86    .055       0  8967.8    .075       0
#XS Ineff= 5 ,-1
       0    5349     440    6560    6750  418.86    6827    7915     440
    7920    8120     425  9796.8 12776.8     440
Permanent Ineff=
       F       T       F       T       F
Bank Sta=8638.12,8967.8
XS Rating Curve= 0 ,0
Exp/Cntr=0.3,0.1

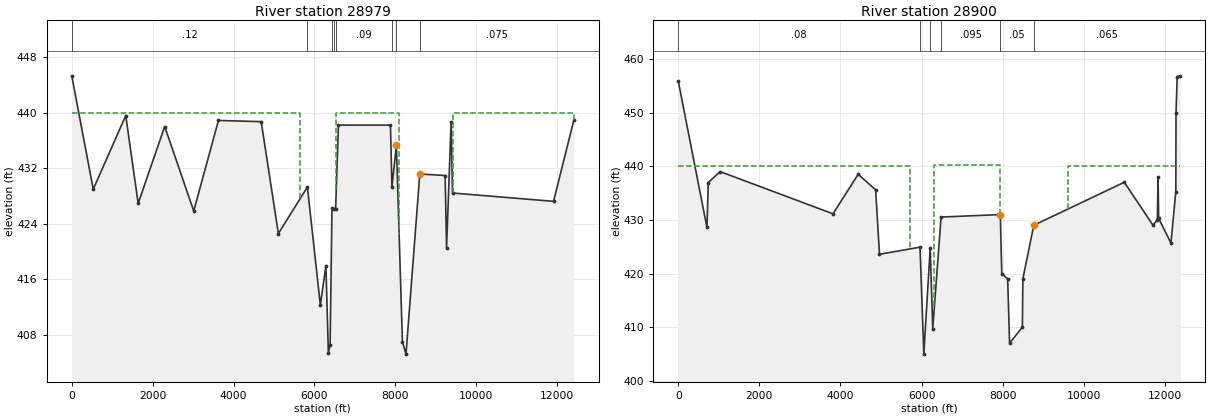
Type RM Length L Ch R = 1 ,28979   ,128,79,0.01
XS GIS Cut Line= 6
2441490.811941716976037.524961982441459.318566386971219.14089797
2441497.513043816969618.446592812441563.48502472 6968125.3908519
2441743.576856146967521.878279392441785.613189386963652.51725173
#Sta/Elev= 30
       0   445.3  530.95  428.96 1334.84  439.58  1641.8  426.92 2297.72     438
 3015.65  425.83  3626.6  438.87 4683.44   438.7 5108.28  422.58 5825.92  429.28
 6145.77  412.28  6283.7  417.93 6344.67  405.36 6387.65  406.58 6433.63  426.26
 6471.32  426.13 6523.56  426.13  6593.1   438.2 7879.82   438.2 7915.72  429.27
 8026.07  435.28  8175.2     407 8263.82  405.21 8604.79  431.16 9230.79  430.94
 9266.79  420.52 9379.79  438.69 9413.79  428.4211911.79  427.2212413.79  438.92
#Mann= 8 ,-1,0
       0     .12       0 5825.92    .055       0 6433.63     .07       0
 6471.32    .055       0 6523.56     .09       0 7915.72     .07       0
 8026.07    .055       0 8604.79    .075       0
#XS Ineff= 4 ,-1
       0    5642     440    6450    6530     426    6539    8094     440
 9434.0912413.79     440
Permanent Ineff=
       F       T       F       F
Bank Sta=8026.07,8604.79
XS Rating Curve= 0 ,0
Exp/Cntr=0.5,0.3

Type RM Length L Ch R = 1 ,28900   ,92,151,92
BEGIN DESCRIPTION:
With valley storage pond grading for CDC GP 070319-1.
Updated for 2019 MacArthur Blvd LOMR with 2016 GP LiDAR Data As-Built Contours in XS station 8015-9135
This cross section corresponds to cross section 28841 of the non-georeferenced CDC model which was the source of this model.
Upstream bounding cross section for Meyers Road/MacArthur Blvd bridge (West Fork Trinity River and Bear Creek bridges modeled).
This cross section is the downstream end of the MacArthur Reclamation Project (GP 072219-01).
END DESCRIPTION:
XS GIS Cut Line= 6
  2441490.811936  6976037.525044   2441459.31856   6971219.14098
  2441563.485019  6968125.390934  2441728.984688  6967570.779182
  2441739.000088  6966655.999844  2441691.999854  6963675.999898
#Sta/Elev= 30
       0  455.94  708.01  428.59  741.01  436.98 1033.11  439.02 3816.74  431.14
  4437.5  438.52 4867.17  435.62 4962.74  423.59 5961.72  424.92 6055.88  404.96
 6212.92  424.71 6276.09  409.71 6481.35  430.54    7942     431    7978     420
    8123     419    8171     407    8486     410    8498     419    8767     429
10998.84  437.0311706.15  429.0211815.04  429.9911831.03  437.9811847.01  430.27
12149.72  425.69 12269.6  435.2912274.59  449.9712303.57  456.7212380.49  456.89
#Mann= 6 ,-1,0
       0     .08       0 5961.72    .055       0 6212.92     .08       0
 6481.35    .095       0    7942     .05       0    8767    .065       0
#XS Ineff= 3 ,-1
       0    5716     440    6317    7943  440.25    9608   12396     440
Permanent Ineff=
       F       F       F
Bank Sta=7942,8767
XS Rating Curve= 0 ,0
Exp/Cntr=0.5,0.3

Type RM Length L Ch R = 3 ,28771   ,,,
BEGIN DESCRIPTION:
MacArthur Boulevard
West Fork Bridge Modeled from As-Built Plans March 20, 2018
-----------------------------
CDC DALCO040803-1 Meyers Road
-----------------------------
END DESCRIPTION:
Node Name=MacArthur Boulev
Bridge Culvert--1,0,-1,-1, 0
Deck Dist Width WeirC Skew NumUp NumDn MinLoCord MaxHiCord MaxSubmerge Is_Ogee
53,86,2.6,0, 251, 252, , , 0.95, 0, 0,0,,
       0   14.19   63.44  115.32  140.69  165.04  173.29  221.91  251.64  279.18
  344.99  393.18  406.18  424.18   476.2   518.2  585.21  604.21  623.21  664.21
  673.21  728.23  752.23  773.23  798.23  829.27  868.27  939.31  965.31  991.31
 1035.31 1052.31 1067.34 1110.34 1166.34 1227.37 1235.37 1256.37 1296.37 1327.41
 1340.41 1391.41 1407.41 1471.42 1507.42 1549.47  1625.5 1637.55 1651.55 1703.65
 1762.68 1791.68 1854.79 1887.79 1940.81 1947.81 1979.83 2037.86 2059.89 2088.89
 2142.91 2148.91 2179.93 2234.95 2259.95    2300    2314 2336.03 2348.03 2363.03
 2402.03 2504.15 2608.18 2643.18 2688.18  2757.2  2775.2  2790.2  2844.2  2854.2
 2892.22 2997.22 3062.23 3130.23 3220.26 3263.26 3287.26 3291.26 3425.29 3457.31
 3497.53 3600.59 3619.59 3627.66 3698.78 3753.88 3762.93 3800.97 3857.09 3942.82
 4064.44 4101.63 4164.91 4256.33 4282.36 4312.38 4325.41 4382.48 4458.58 4463.68
 4500.73  4566.8 4608.86  4639.9  4649.9 4723.05 4730.13 4745.13 4767.15 4821.28
 4843.28 4959.53 4993.64 5115.85 5165.93 5170.93 5202.99 5213.99 5249.09 5448.71
 5463.74 5483.74 5524.96 5543.99 5579.02 5606.09 5629.33 5649.33 5673.42    5696
    5716    5816    5916    6016    6116    6216    6316    6336    6336 6483.13
 6505.16 6523.16 6565.35 6610.38 6625.38 6672.46 6714.57 6794.71  6874.9 6905.01
 6933.03 6992.17 7033.25    7324    7424    7524    7624    7724    7824    7924
  7943.9    7944    8024    8044    8124    8144    8224    8244    8344    8424
    8444    8524    8544    8624    8644  8644.1    8724    8799    8824    8924
    9024    9049    9124    9164    9224    9284    9324    9424  9461.5    9524
  9586.5    9624  9661.5    9724  9786.5    9824    9864    9924    9984   10024
   10064   10124   10184   10224   10264   10324   10384   10424   10464   10524
   10584   10624   10664   10724   10784   10824   10864   10924   10984   11024
   11064   11124   11184   11224   11264   11324   11384   11424   11464   11524
   11524   11584   11624   11644   11724   11824   11924   12024   12105   12185
   12265
  460.41  457.61   454.5  451.44  450.52  448.87  447.86  445.24  443.17  441.69
  438.62  437.05  436.98  436.42  435.69  435.53  435.54  435.11  435.35  434.87
  434.93  434.47   434.5  434.17  434.34   433.9  433.95  434.42  434.74  434.71
  435.11  434.97  435.24  435.26   435.1  434.78  434.52   434.7  434.56  434.74
  434.58  434.92  434.75   435.2  435.02  435.03  434.72  434.91  434.58  434.44
   434.7  435.13  435.38  435.36  435.09  435.29  434.79  434.61  434.79  434.36
  434.47  434.67  434.66  434.92  435.18  435.23   435.1   435.4  435.06  435.15
  434.79  434.33  434.76  435.18  435.18  434.95  435.13   434.8  434.49   434.6
  434.24  434.64  435.04  435.07  434.65  434.35  434.49  434.16  434.78  435.26
  435.16  434.74  434.93  434.57  434.27   434.5  434.76  435.04  435.13  435.08
  434.33  434.23  434.47   435.1  435.14  435.53   435.3  435.17  434.73  434.98
  434.71  434.84  435.33  435.43  435.18   435.5  435.96  436.06  435.77  435.52
  435.15  434.53  434.65  435.93  436.39  436.68   436.8   437.1  437.19  439.22
   439.6  439.55  439.95  440.32   440.4  440.93  440.93  441.59   441.5  446.32
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  437.15  438.26  439.38  439.96   439.4   438.3  437.21
          436.66  438.13  438.34  439.14  439.34  440.14  440.34  441.34  441.52
  441.38  440.03  439.51  437.22  436.45
     121  135.19  184.44  236.32  261.69  286.04  294.29  342.91  372.64  400.18
  465.99  514.18  527.18  545.18   597.2   639.2  706.21  725.21  744.21  785.21
  794.21  849.23  873.23  894.23  919.23  950.27  989.27 1060.31 1086.31 1112.31
 1156.31 1173.31 1188.34 1231.34 1287.34 1348.37 1356.37 1377.37 1417.37 1448.41
 1461.41 1512.41 1528.41 1592.42 1628.42 1670.47  1746.5 1758.55 1772.55 1824.65
 1883.68 1912.68 1975.79 2008.79 2061.81 2068.81 2100.83 2158.86 2180.89 2209.89
 2263.91 2269.91 2300.93 2355.95 2380.95    2421    2435 2457.03 2469.03 2484.03
 2523.03 2625.15 2729.18 2764.18 2809.18  2878.2  2896.2  2911.2  2965.2  2975.2
 3013.22 3118.22 3183.23 3251.23 3341.26 3384.26 3408.26 3412.26 3546.29 3578.31
 3618.53 3721.59 3740.59 3748.66 3819.78 3874.88 3883.93 3921.97 3978.09 4063.82
 4185.44 4222.63 4285.91 4377.33 4403.36 4433.38 4446.41 4503.48 4579.58 4584.68
 4621.73  4687.8 4729.86  4760.9  4770.9 4844.05 4851.13 4866.13 4888.15 4942.28
 4964.28 5080.53 5114.64 5236.85 5286.93 5291.93 5323.99 5334.99 5370.09 5569.71
 5584.74 5604.74 5645.96 5664.99 5700.02 5727.09 5750.33 5770.33 5794.42    5817
    5837    5937    6037    6137    6237    6337    6437    6457    6457 6604.13
 6626.16 6644.16 6686.35 6731.38 6746.38 6793.46 6835.57 6915.71  6995.9 7026.01
 7054.03 7113.17 7154.25    7395    7495    7595    7695    7795    7895    7995
  8014.5    8015    8095    8115    8195    8215    8295    8315    8415    8495
    8515    8595    8615    8695    8715  8715.1    8795    8870    8895    8995
    9095    9120    9195    9235    9295    9355    9395    9495  9532.5    9595
  9657.5    9695  9732.5    9795  9857.5    9895    9935    9995   10055   10095
   10135   10195   10255   10295   10335   10395   10455   10495   10535   10595
   10655   10695   10735   10795   10855   10895   10935   10995   11055   11095
   11135   11195   11255   11295   11335   11395   11455   11495   11535   11595
   11595   11655   11695   11715   11795   11895   11995   12095   12176   12256
   1233612354.89
  460.41  457.61   454.5  451.44  450.52  448.87  447.86  445.24  443.17  441.69
  438.62  437.05  436.98  436.42  435.69  435.53  435.54  435.11  435.35  434.87
  434.93  434.47   434.5  434.17  434.34   433.9  433.95  434.42  434.74  434.71
  435.11  434.97  435.24  435.26   435.1  434.78  434.52   434.7  434.56  434.74
  434.58  434.92  434.75   435.2  435.02  435.03  434.72  434.91  434.58  434.44
   434.7  435.13  435.38  435.36  435.09  435.29  434.79  434.61  434.79  434.36
  434.47  434.67  434.66  434.92  435.18  435.23   435.1   435.4  435.06  435.15
  434.79  434.33  434.76  435.18  435.18  434.95  435.13   434.8  434.49   434.6
  434.24  434.64  435.04  435.07  434.65  434.35  434.49  434.16  434.78  435.26
  435.16  434.74  434.93  434.57  434.27   434.5  434.76  435.04  435.13  435.08
  434.33  434.23  434.47   435.1  435.14  435.53   435.3  435.17  434.73  434.98
  434.71  434.84  435.33  435.43  435.18   435.5  435.96  436.06  435.77  435.52
  435.15  434.53  434.65  435.93  436.39  436.68   436.8   437.1  437.19  439.22
   439.6  439.55  439.95  440.32   440.4  440.93  440.93  441.59   441.5  446.32
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  437.15  438.26  439.38  439.96   439.4   438.3  437.21
          436.66  438.13  438.34  439.14  439.34  440.14  440.34  441.34  441.52
  441.38  440.03  439.51  437.22  436.45
Pier Skew, UpSta & Num, DnSta & Num=  ,5816, 2 ,5916, 2 , 0 , 0 , 0 ,,
       3       3
     400     440
       3       3
     400     440
Pier Skew, UpSta & Num, DnSta & Num=  ,5916, 2 ,6016, 2 , 0 , 0 , 0 ,,
       3       3
     400     440
       3       3
     400     440
Pier Skew, UpSta & Num, DnSta & Num=  ,6016, 2 ,6116, 2 , 0 , 0 , 0 ,,
       4       4
     400     440
       4       4
     400     440
Pier Skew, UpSta & Num, DnSta & Num=  ,6116, 2 ,6216, 2 , 0 , 0 , 0 ,,
       4       4
     400     440
       4       4
     400     440
Pier Skew, UpSta & Num, DnSta & Num=  ,6216, 2 ,6316, 2 , 0 , 0 , 0 ,,
       3       3
     400     440
       3       3
     400     440
Pier Skew, UpSta & Num, DnSta & Num=  ,8044, 2 ,8115, 2 , 0 , 0 , 0 ,,
       3       3
     400     450
       3       3
     400     450
Pier Skew, UpSta & Num, DnSta & Num=  ,8144, 2 ,8215, 2 , 0 , 0 , 0 ,,
       3       3
     400     450
       3       3
     400     450
Pier Skew, UpSta & Num, DnSta & Num=  ,8244, 2 ,8315, 2 , 0 , 0 , 0 ,,
       3       3
     400     450
       3       3
     400     450
Pier Skew, UpSta & Num, DnSta & Num=  ,8344, 2 ,8415, 2 , 0 , 0 , 0 ,,
       3       3
     400     450
       3       3
     400     450
Pier Skew, UpSta & Num, DnSta & Num=  ,8444, 2 ,8515, 2 , 0 , 0 , 0 ,,
       3       3
     400     450
       3       3
     400     450
Pier Skew, UpSta & Num, DnSta & Num=  ,8544, 2 ,8615, 2 , 0 , 0 , 0 ,,
       3       3
     400     450
       3       3
     400     450
BR Coef=-1 , 0 , 0 ,, 0 ,,,0.8,0,,1,
WSPro=,,,, 1 ,,,, 0 ,,,, 0 ,,,,-1 ,-1 ,-1 , 0 , 0 , 0 , 0 , 0
BR Coef=-1 , 0 , 0 ,, 0 ,,,0.8,-1,,1,
WSPro=,,,, 1 ,,,, 0 ,,,, 0 ,,,,-1 ,-1 ,-1 , 0 , 0 , 0 , 0 , 0
BR Coef=-1 , 0 , 0 ,, 0 ,,,0.8,-1,,1,
WSPro=,,,, 1 ,,,, 0 ,,,, 0 ,,,,-1 ,-1 ,-1 , 0 , 0 , 0 , 0 , 0
BR Coef=-1 , 0 , 0 ,, 0 ,,,0.8,-1,,1,
WSPro=,,,, 1 ,,,, 0 ,,,, 0 ,,,,-1 ,-1 ,-1 , 0 , 0 , 0 , 0 , 0
BR U #Sta/Elev= 327
       0  455.94      35  456.15      63  455.66      99  452.43     136  451.21
     176  445.93     204  446.19     231  444.86     244   442.6     268  441.69
  328.01  441.86  365.01  439.27  391.01  438.55  425.01  439.45  501.01  438.38
  529.01  437.13  641.01  436.57  671.01  435.52  689.01  433.45  699.01  429.17
  708.01  428.59  714.01  431.09  724.01  431.84  741.01  436.98  931.11  437.37
  947.11  438.01 1004.11  437.23 1033.11  439.02 1099.11  438.66 1179.11  439.05
 1214.11   439.5 1238.11  437.88 1264.11  438.03 1278.11   439.6 1349.11  438.39
 1426.12  437.68 1469.12  436.73 1512.12  436.63 1572.12  437.15 1585.12  434.94
 1614.12   434.9 1636.12  436.44 1656.12  436.23 1705.12  436.75 1745.12  436.62
 1780.12  434.74 1820.12  435.56 1834.12  434.75 1871.12  435.64 1882.12  436.55
  1956.2  436.79  1967.2  435.82  2000.2  436.58  2024.2  436.03  2053.2  437.07
  2120.2  436.92  2129.2  435.99  2167.2  437.42  2217.2  435.66  2273.2  435.51
  2285.2  435.13  2323.2  436.77  2340.2  436.35  2387.2  436.69  2431.2  434.65
 2459.22  434.55 2465.22  435.25 2542.22   436.8 2556.22  436.67 2585.22  434.04
 2616.22  434.62 2691.22  434.79 2713.22   435.5 2736.22  434.89 2756.22  435.79
 2791.22  435.66 2818.22  436.83 2842.22  436.55 2854.22  437.25 2886.22  436.82
 2936.22  437.45 2975.22  437.45 3013.32   435.6 3040.32  435.46 3061.32   437.5
 3103.32   437.8 3124.32  437.03 3136.32  437.51 3180.32  437.37 3185.32  436.83
 3212.32  438.02 3264.32  437.23 3278.32  438.03 3316.32   437.7 3346.32  436.86
 3371.32  436.88 3404.32  435.34 3431.32  433.46 3440.32  436.01 3482.32  435.48
 3582.74   435.1 3602.74  434.81 3735.74  435.22 3776.74  435.68 3787.74   432.8
 3816.74  431.14 3862.78  436.84 3905.87  437.04 3936.88  437.67 3982.94  436.95
 3994.94  437.57 4044.04  437.15 4056.04  436.44 4136.12  437.46  4201.3  437.41
 4264.34  436.88 4382.46  437.46  4437.5  438.52 4457.53  437.61 4567.68  437.71
 4586.68  437.21 4638.75  438.29 4676.77  437.18 4705.83  435.65 4734.85  434.87
 4759.95  435.04 4793.03   436.2 4844.15  435.23 4867.17  435.62 4876.26  434.41
 4901.49  428.01 4913.56     426 4962.74  423.59 4979.81   425.5 4984.81  424.83
    5012  426.61 5051.22  424.83 5075.25  424.85 5085.49     428 5094.65  428.97
 5110.65  426.86 5129.96     426    5151  422.35 5179.12   423.1 5190.12  422.45
 5247.31  422.37 5272.41  422.98 5290.45  422.33 5304.61  424.14 5343.91  426.66
 5382.24  426.62 5421.35  425.69 5439.45  426.74 5474.58  425.02 5499.61  427.45
 5514.02  425.76 5536.49  425.77 5551.49  424.41 5589.98  425.53  5605.1  423.52
 5624.16  423.23 5645.22  424.62 5664.28   422.6 5682.44  425.75 5691.52   423.3
 5712.62  422.46    5716  437.15    5740     425    5959     424    6016     405
    6116     405    6173     424  6291.6     425    6316  437.21 6481.35  430.54
 6505.58  429.23 6590.58  427.11  6673.9  427.21 6690.14  428.16 6787.57  427.21
 6814.82  427.56 6879.69  427.25 6922.69   427.7  6946.2  426.99 6955.42  427.67
 6979.56  427.27 7018.03  427.95 7057.72  427.77 7078.91  428.35 7139.78  428.18
 7159.94  428.78 7171.36  428.06 7224.08  427.34 7253.68  427.75 7273.99  427.25
 7347.71   427.9 7373.01  428.49 7406.62   428.1 7453.14  428.73 7508.65  427.87
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BR U #Mann= 5
       0     .08    5716    .055    6316    .095    7944     .05    8767    .065
BR U Banks=7944,8644
BR D #Sta/Elev= 340
       0  469.12   28.96  466.62   59.99   464.7  142.06  459.82  164.68   459.2
  226.11  455.55  280.25  453.73  294.61  452.88   358.4  450.22  389.98  446.79
  457.67  442.98  498.55  441.72  537.63  441.78  551.77   440.7  606.16  439.18
  665.98  438.15  701.98  436.03     723     437     754  437.22  813.08  437.18
  864.11  435.11  902.13  435.28  923.13  436.35  956.16  437.08  979.16  435.44
  985.16  429.96  997.32  429.48 1005.32  430.98 1010.32  433.55 1025.32  435.86
 1062.34  435.74 1120.35  435.09 1202.43  435.31 1259.45  435.24 1325.48  435.67
  1381.5  434.77 1446.55  435.56  1462.6  436.62  1476.6  435.75 1510.62  435.87
 1554.65  435.08 1570.65  435.65 1581.65  432.91  1605.7  429.51  1620.7  428.85
  1631.7  430.72 1673.71  427.81 1682.71  427.72 1711.73  428.94 1745.76  426.73
 1771.76  429.83 1806.77  431.43 1824.19  431.55 1830.19   435.3 1857.19  435.72
 1931.27  436.07 1947.27  435.47  1964.3  436.11 2041.32  435.86 2069.37  433.34
 2124.42  433.46 2138.42  430.59 2154.46  428.42 2170.46  423.43 2229.49  423.51
 2254.51  427.02 2264.51  426.62 2273.51  429.22 2299.75  428.36 2312.75  429.56
 2319.75  428.47  2345.8   429.9  2365.8  429.68  2377.8     433 2393.85  433.67
 2399.85  435.49 2411.85   436.4 2421.85  432.96 2442.93  433.32 2448.93  432.39
 2485.96   433.1 2523.99  431.96 2564.99   431.8 2596.11  430.96 2655.14  431.15
 2683.19  430.91 2726.24   431.3 2764.27  431.11 2771.27  432.26 2794.27  432.01
 2824.33  429.18 2832.33  425.47 2840.33  424.32 2847.57  425.12 2864.57  429.04
 2877.57  433.01 2897.63  431.62 2918.63  432.41 2934.63  431.55 2957.73  433.61
 2977.73  431.04 3000.75  430.89 3007.75  428.71 3019.75  428.75  3037.8   425.6
  3050.8  427.34  3065.8  426.18 3082.92  429.19 3096.92  426.74 3119.92  427.93
 3127.09  429.05 3147.09  429.34 3173.13  428.47 3197.13  428.95 3223.19   428.4
 3248.19  428.71 3313.43  430.81 3321.49  430.35 3354.49  430.66 3425.56  430.87
  3460.6  430.43 3493.63  430.43 3513.63  433.64 3560.64  433.46 3588.66  430.71
 3601.66  430.11 3693.72  430.05 3721.73  429.65 3736.73  429.97 3776.77  429.43
 3896.83  429.47 3970.87  430.08 4005.92  430.68 4049.99  430.19 4131.19  430.47
 4200.23  431.04 4297.42   432.1 4366.47   432.3 4462.53  432.01 4528.55  431.49
  4627.6  431.44  4656.6  431.11 4700.63  431.15 4720.65  431.55 4753.68  431.43
 4837.75  430.45 4884.84  430.48 4908.87  430.09 4960.88  430.27 5017.99  429.91
 5105.07  430.11 5120.07  430.92 5130.12  430.27 5148.12  430.98 5163.15  430.02
 5200.17   430.2 5238.23  429.99 5275.32  430.36 5287.32  431.34  5310.4  430.32
  5401.7  431.38  5405.7  431.75  5406.7  426.76  5417.7  426.91  5419.7  431.72
 5460.79  431.37 5479.91  432.14 5504.91   431.8 5558.11  432.63 5619.34  433.24
 5653.37  431.49 5686.39  431.75 5706.44  432.34 5713.44  431.67 5732.46  432.06
 5749.46  433.71 5770.62  431.66 5801.64  433.27  5825.8  432.18  5830.8  432.76
    5837  437.15    5861     425    6080     424    6137     405    6237     405
    6294     424  6412.6     425    6437  437.21 6460.25  427.29 6467.25  428.79
 6480.25  428.54 6509.38  426.68 6513.38  427.54 6533.41  426.96 6558.43  427.02
 6573.43  425.88 6583.48   427.6 6601.54  427.88 6656.77  427.76 6720.98  428.29
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BR D #Mann= 5
       0     .08    5837    .055    6437    .095 7982.03    .055    8715    .065
BR D Banks=8015,8715
BC Design=,, 0 ,, 0 ,,,,,,
BC HTab HWMax=444.13
BC Use User HTab Curves=0
BC User HTab FreeFlow(D)= 0