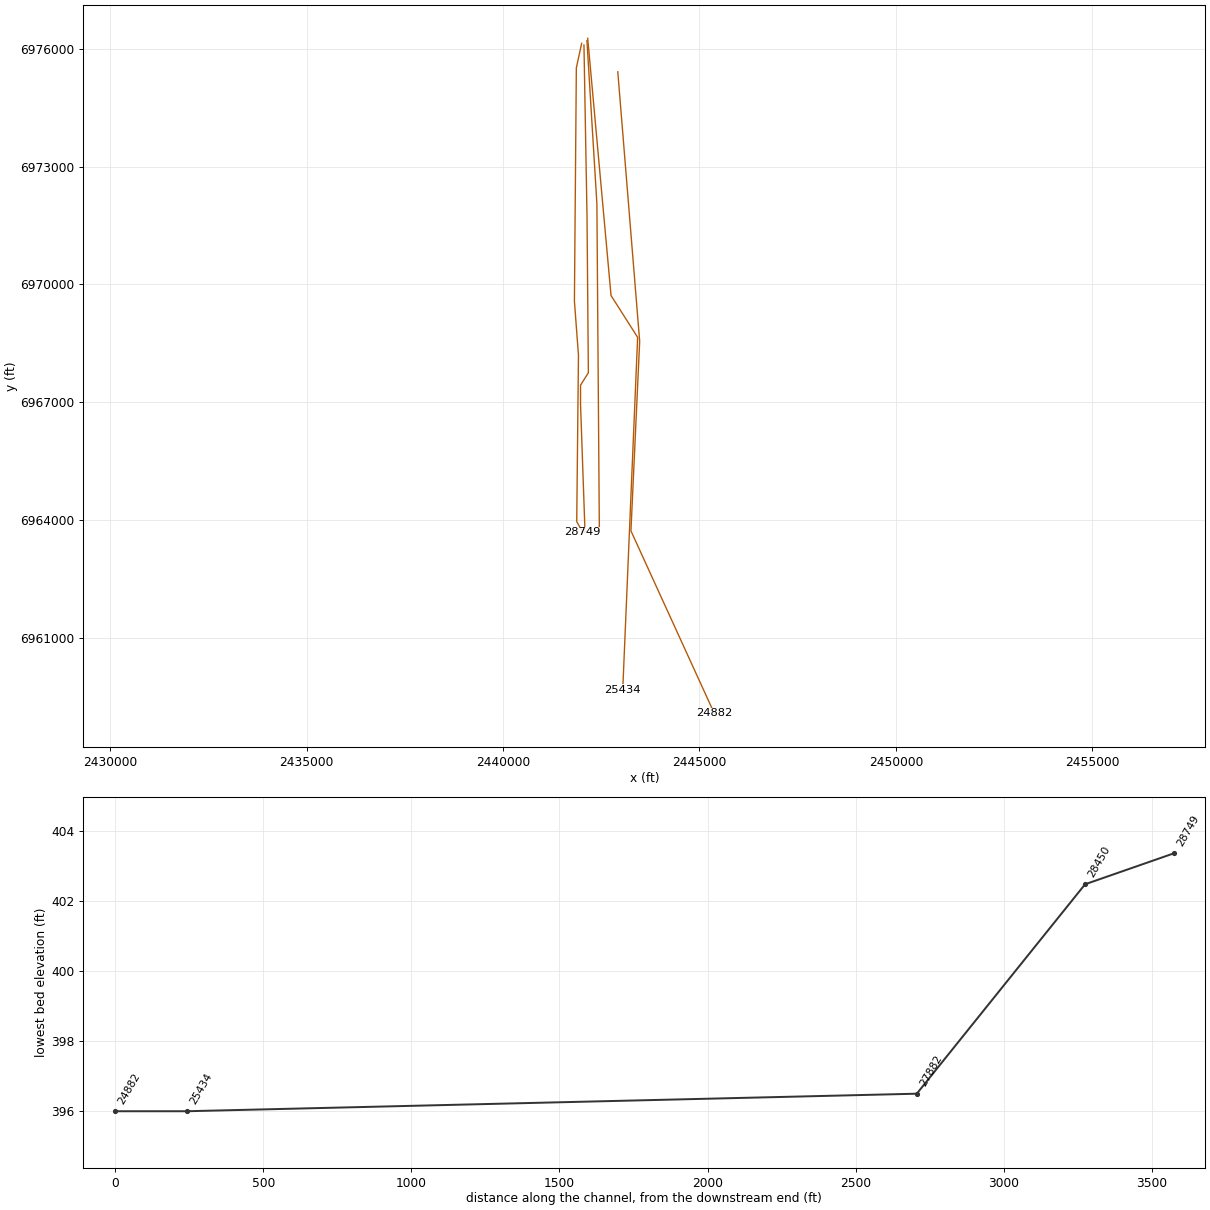
HEC-RAS study CDC_Consolidated_Model.prj: Upper Trinity CDC Consolidated Model

--- CDC_Consolidated_Model.g12 (geometry) --- (continued)

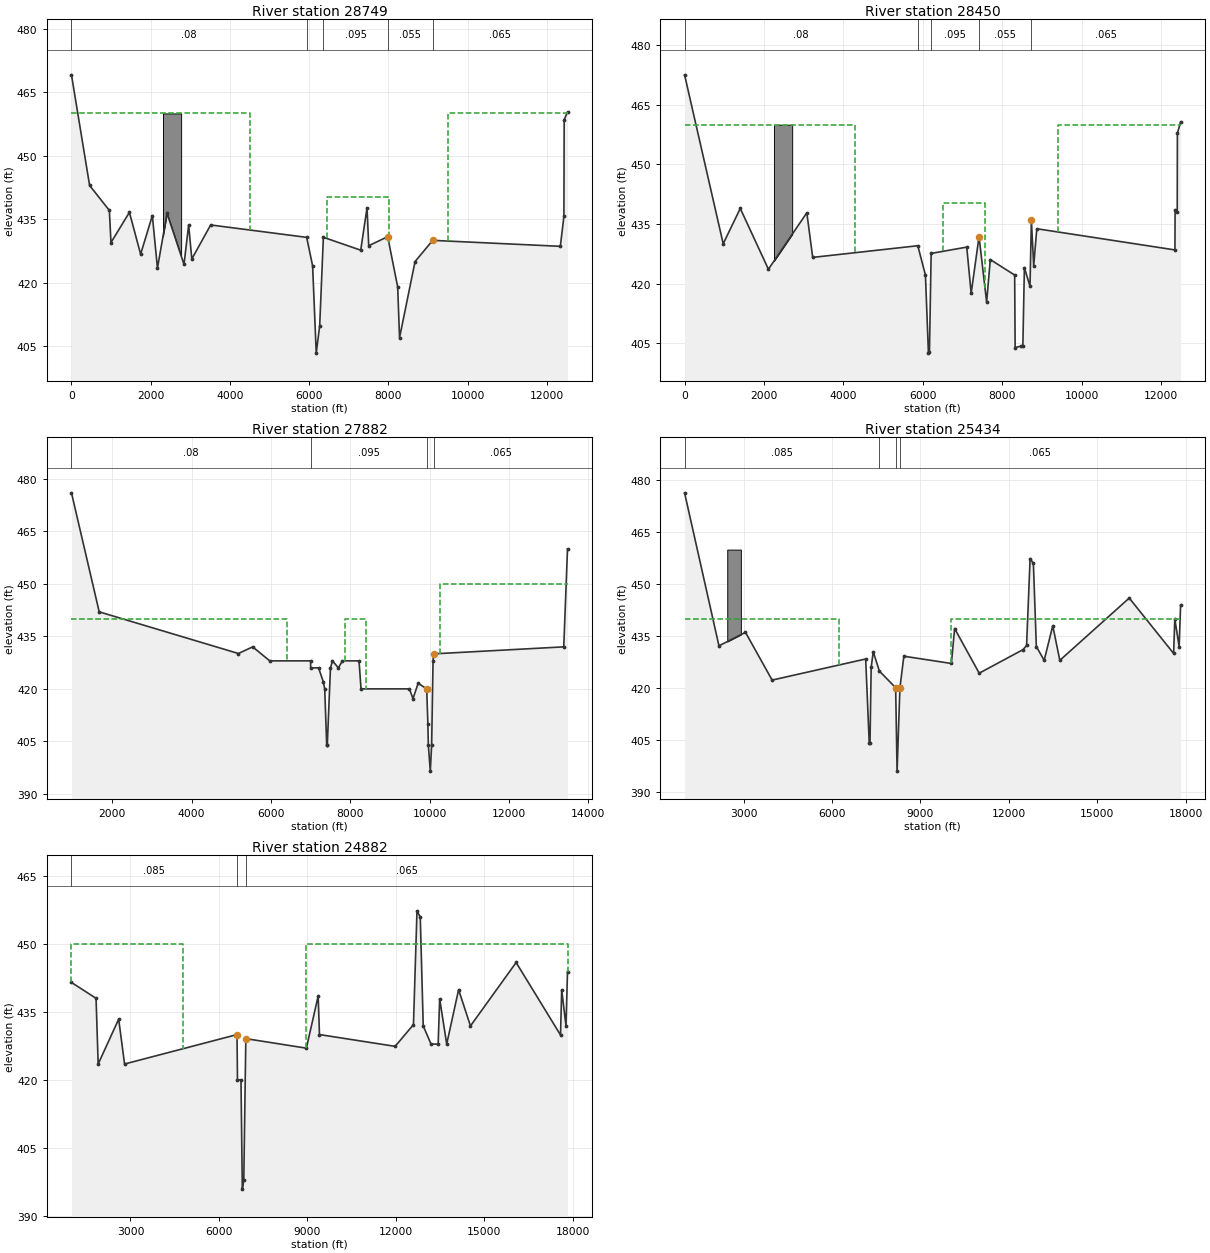
Type RM Length L Ch R = 1 ,28749   ,300,299,90
BEGIN DESCRIPTION:
Updated for 2019 MacArthur Blvd LOMR with 2016 GP LiDAR Data As-Built Contours in XS station 7942-9554
This cross section corresponds to cross section 28749 of the non-georeferenced CDC model which was the source of this model.
Downstream bounding cross section for Meyers Road/MacArthur Blvd bridge (West Fork Trinity River and Bear Creek bridges modeled).
END DESCRIPTION:
XS GIS Cut Line= 6
  2442001.999889 6976138.9999067 2441867.0001597 6975515.9998404
 2441817.9999296 6969575.9999094 2441921.0000517 6968196.0000447
 2441877.0001397 6963958.9999886 2442031.0001598 6963682.9998844
#Sta/Elev= 30
       0  469.12  457.67  442.98  956.16  437.08  997.32  429.48  1462.6  436.62
 1745.76  426.73 2041.32  435.86 2170.46  423.43 2411.85   436.4 2840.33  424.32
 2957.73  433.61  3037.8   425.6 3513.63  433.64 5936.47  430.71 6086.86  423.98
 6178.37  403.35 6265.69  409.86 6358.04  430.73 7300.84  427.68 7460.43   437.7
 7502.99  428.73 7982.03  430.87    8234     419    8281     407    8673     425
    9118     43012339.56  428.5912429.66  435.6512436.33   458.512520.64  460.33
#Mann= 5 ,-1,0
       0     .08       0 5936.47    .055       0 6358.04    .095       0
 7982.03    .055       0    9118    .065       0
#XS Ineff= 3 ,-1
       0    4512     460    6438    8014  440.25    951212520.64     460
Permanent Ineff=
       F       F       F
#Block Obstruct= 1 ,-1
 2309.19 2768.06     460
Bank Sta=7982.03,9118
XS Rating Curve= 0 ,0
Exp/Cntr=0.5,0.3

Type RM Length L Ch R = 1 ,28450   ,440,568,240
BEGIN DESCRIPTION:
This cross section corresponds to cross section 28450 of the non-georeferenced CDC model which was the source of this model.
Updated for 2019 MacArthur Blvd LOMR with 2016 GP LiDAR Data.
END DESCRIPTION:
XS GIS Cut Line= 6
        2442061.        6976097.        2442139.        6971724.
        2442173.        6967750.        2441974.        6967434.
        2441974.        6966940.        2442088.        6963682.
#Sta/Elev= 30
       0  472.56  972.51  430.01    1402  438.91 2110.69   423.6 3077.81  437.81
 3226.05  426.58 5872.21  429.52 6064.31  422.09 6139.37  402.47 6165.37  402.84
 6207.78  427.58  7104.3  429.17 7215.34  417.53 7413.51  431.81 7604.83  415.32
 7696.83  426.04 8310.49  422.13 8322.49  403.87 8480.89  404.27 8517.01  404.39
 8555.38     424 8696.55   419.3 8731.43  435.95 8789.67  424.46 8867.67   433.8
12345.39  428.4612349.39  438.4712403.48     43812407.48  457.8412488.55   460.7
#Mann= 5 ,-1,0
       0     .08       0 5872.21    .055       0 6207.78    .095       0
 7413.51    .055       0 8731.43    .065       0
#XS Ineff= 3 ,-1
       0    4283     460    6518    7565  440.25    9414   12489     460
Permanent Ineff=
       F       F       F
#Block Obstruct= 1 ,-1
 2249.87 2709.22     460
Bank Sta=7413.51,8731.43
XS Rating Curve= 0 ,0
Exp/Cntr=0.3,0.1

Type RM Length L Ch R = 1 ,27882   ,302,2464,1208
BEGIN DESCRIPTION:
This cross section corresponds to cross section 27882 of the non-georeferenced CDC model which was the source of this model.
END DESCRIPTION:
XS GIS Cut Line= 6
     2442136.645     6976211.137  2442390.208591 6972055.5217222
 2442403.7139809 6970257.8112099 2442415.6841013 6968664.2914311
 2442420.1726094  6968066.721432 2442452.6118165 6963747.6683451
#Sta/Elev= 30
     973     476    1672     442    5180   430.1    5540     432    5970     428
    7000     428    7000     426    7200     426    7320     422    7355     420
    7405     404    7420     404    7500     426    7550     428    7700     426
    7800     428    8220     428    8270     420    9490     420    9580   417.2
    9710   421.6    9925     420    9955     410    9966     404   10016   396.5
   10050     404   10085     428   10099     430   13379     432 13473.6     460
#Mann= 4 ,-1,0
     973     .08       0    7000    .095       0    9925    .055       0
   10099    .065       0
#XS Ineff= 3 ,-1
     973    6400     440    7870    8400     440   10250 13473.6     450
Permanent Ineff=
       F       F       F
Bank Sta=9925,10099
XS Rating Curve= 0 ,0
Exp/Cntr=0.3,0.1

Type RM Length L Ch R = 1 ,25434   ,289.34,242,43.84
BEGIN DESCRIPTION:
25434
END DESCRIPTION:
XS GIS Cut Line= 4
  2442156.7090726976268.634753352442750.227591316969717.39054035
2443427.455600566968652.575725532443048.097961666959671.40529726
#Sta/Elev= 30
    1000   476.4    2166   432.2    3066   436.1    3970   422.3    7144   428.4
    7265     404    7290     404    7330     426    7401   430.5    7608   424.9
    8161   420.1    8209     396    8306   420.1    8439   429.2   10052   427.1
   10161   437.2   10995   424.3   12482   431.1   12602   432.3   12722   457.4
   12833     456   12934     432   13199     428   13491     438   13730     428
   16085     446   17591     430   17631     440   17777     432   17828     444
#Mann= 4 ,-1,0
    1000    .085       0    7608    .095       0    8161    .055       0
    8306    .065       0
#XS Ineff= 2 , 0
            6250     440   10040             440
Permanent Ineff=
       F       F
#Block Obstruct= 1 ,-1
 2447.63 2908.96     460
Bank Sta=8161,8306
XS Rating Curve= 0 ,0
Exp/Cntr=0.3,0.1

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
Type RM Length L Ch R = 1 ,24882   ,1720,4958,2260
BEGIN DESCRIPTION:
24882
END DESCRIPTION:
XS GIS Cut Line= 6
  2442922.173902 6975416.6788449 2443204.8055546 6971933.6290525
 2443479.4099923 6968550.1000584  2443256.811028 6963722.4059736
 2444690.0890013 6960582.4752457  2445378.724107 6959073.9651393
#Sta/Elev= 30
    1000   441.6    1834   438.1    1906   423.6    2602   433.5    2801   423.6
    6616   430.1    6632   420.1    6751   420.1    6796     396    6846     398
    6915   429.2    8969   427.1    9369   438.6    9414   430.1   11981   427.5
   12602   432.3   12722   457.4   12833     456   12934     432   13199     428
   13440     428   13491     438   13730     428   14133     440   14536     432
   16085     446   17591     430   17631     440   17777     432   17828     444
#Mann= 3 ,0,0
    1000    .085       0    6616    .055       0    6915    .065       0
#XS Ineff= 2 , 0
            4800     450    8960             450
Permanent Ineff=
       F       F
Bank Sta=6616,6915
XS Rating Curve= 0 ,0
Exp/Cntr=0.3,0.1