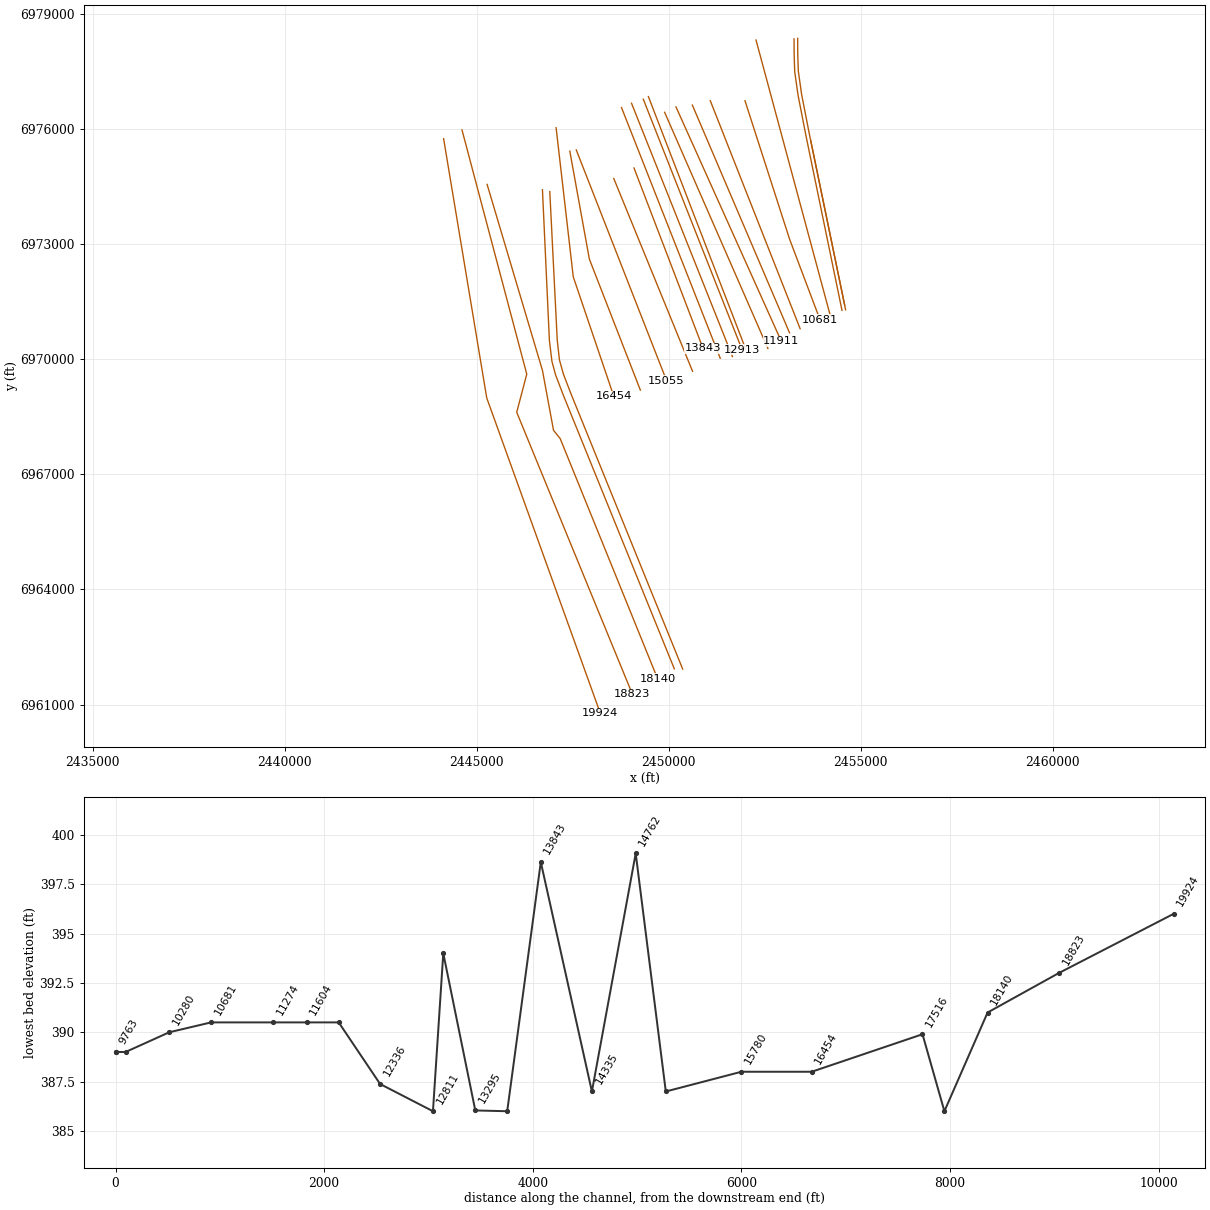
HEC-RAS study CDC_Consolidated_Model.prj: Upper Trinity CDC Consolidated Model

--- CDC_Consolidated_Model.g12 (geometry) --- (continued)

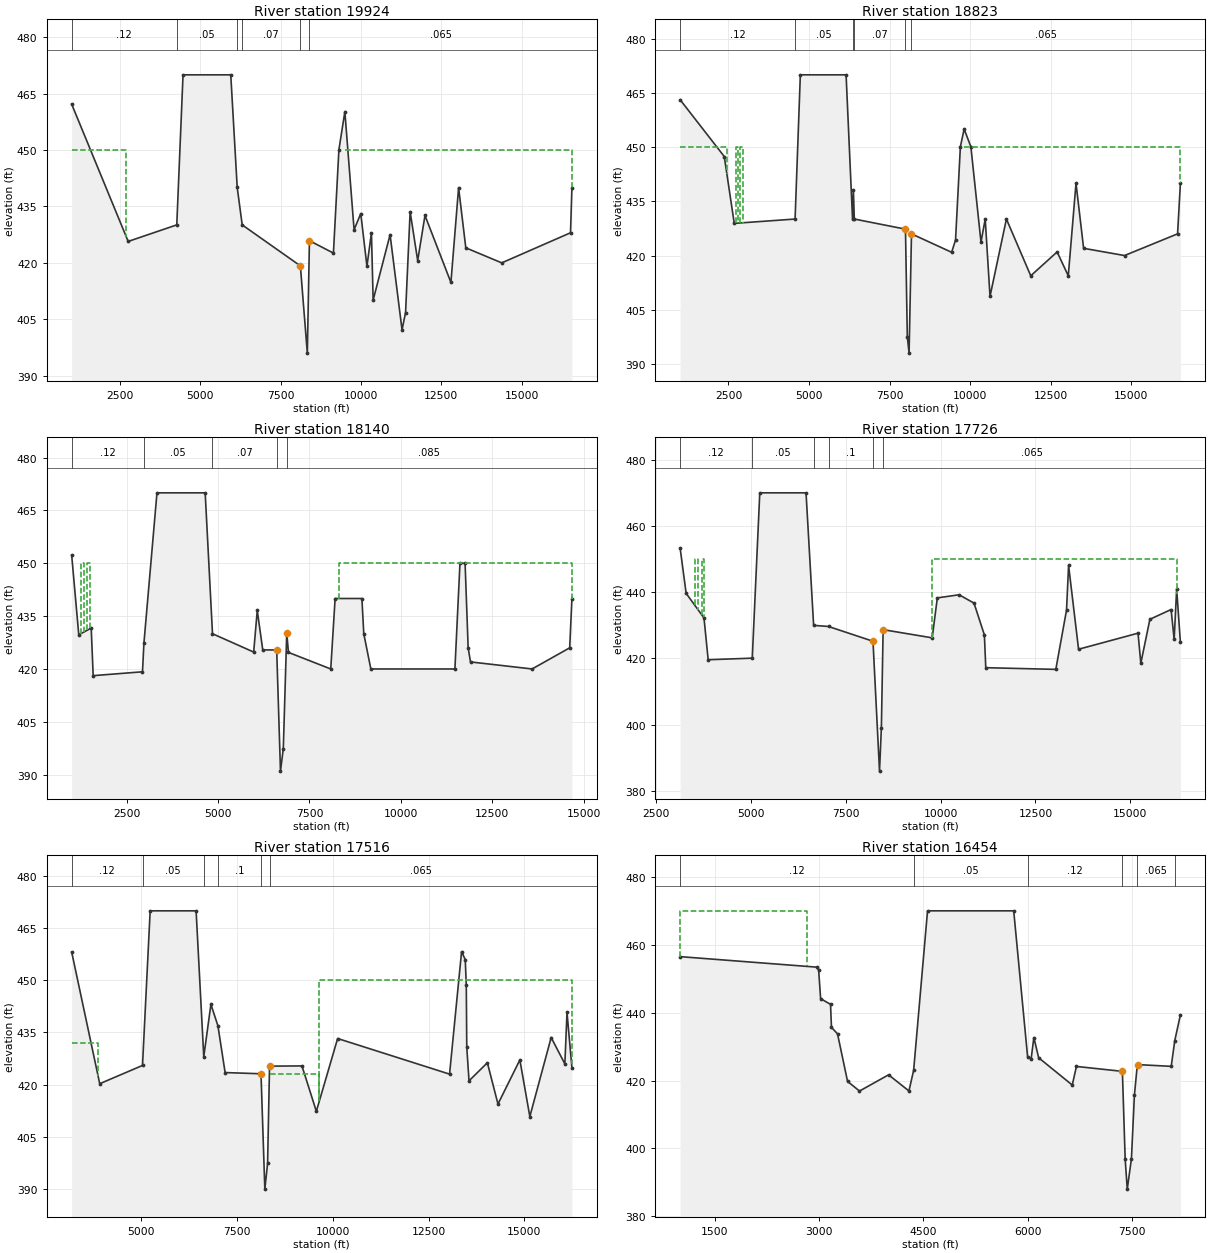
Type RM Length L Ch R = 1 ,19924   ,1050,1101,660
BEGIN DESCRIPTION:
This cross section corresponds to cross section 19924 of the non-georeferenced CDC model which was the source of this model.
Cross-section WF028.  Effective flow limit set at sta 2700 in LOB, 9500 in ROB at Grand Prairie Landfill.  Ineffective flow north of Hunter-Ferrell Road - conveyance removed below elev. 426.2.  Bear Creek channel removed from conveyance in LOB.  Irving Landfill in LOB.
Channel data from 1975 USACOE field survey.
END DESCRIPTION:
XS GIS Cut Line= 6
  2444136.963139 6975743.7369178 2444690.6339477 6972414.3213326
 2445260.6980963 6968986.9938697 2446155.2074622 6966502.6425391
 2447016.7119727 6964110.3290823 2448218.9280722 6960769.0329434
#Sta/Elev= 30
    1000   462.2    2758   425.7    4270   430.1    4465     470    5950     470
    6150   440.1    6306   430.1    8116   419.2    8332     396    8398   425.9
    9144   422.6    9315   450.1    9500   460.2    9787   428.8    9995   433.1
   10187   419.1   10327     428   10380   410.1   10907   427.5   11279   402.2
   11389   406.8   11531   433.6   11766   420.6   11993   432.6   12800   414.8
   13039     440   13263     424   14381     420   16521     428   16565     440
#Mann= 6 ,-1,0
    1000     .12       0    4270     .05       0    6150     .12       0
    6306     .07       0    8116    .055       0    8398    .065       0
#XS Ineff= 4 ,-1
    1000    2700     450    2700    8116   419.2    8398    9500   425.9
    9500   16565     450
Permanent Ineff=
       F       F       F       F
Bank Sta=8116,8398
XS Rating Curve= 0 ,0
Exp/Cntr=0.3,0.1

Type RM Length L Ch R = 1 ,18823   ,400,683,780
BEGIN DESCRIPTION:
This cross section corresponds to cross section 18823 of the non-georeferenced CDC model which was the source of this model.
Cross-section WF027.  Effective flow limit set at sta 2450 in LOB, sta 9814 in ROB at Grand Prairie Landfill.  Houses blocked from sta 2730 - 2800, sta 2870 - 2950 in LOB.  Ineffective flow north of Hunter-Ferrell Road -
conveyance removed below elev. 426.2.  Bear Creek channel removed from conveyance.  Irving Landfill in LOB.
Channel data from 1975 USACOE field survey.
END DESCRIPTION:
XS GIS Cut Line= 6
  2444615.869989 6975971.5100843 2445484.6330159 6972693.2394099
 2446302.4450286 6969607.8318668 2446040.9501447 6968615.0891016
 2447811.1880741 6964296.3890777 2449053.0779787 6961269.5168506
#Sta/Elev= 30
    1000   463.1    2369   447.4    2679   428.9    4567   430.1    4730     470
    6150     470    6350   430.1    6377     438    6405   430.1    7993   427.3
    8050   397.6    8105     393    8180     426    9426   420.9    9547   424.3
    9697   450.1    9814     455   10023   450.1   10337   423.7   10468   430.1
   10617   408.7   11126   430.1   11881   414.4   12700     421   13046   414.4
   13286     440   13522     422   14792     420   16438     426   16526     440
#Mann= 6 ,-1,0
    1000     .12       0    4567     .05       0    6350     .12       0
    6405     .07       0    7993    .045       0    8180    .065       0
#XS Ineff= 8 ,-1
    1000    2450     450    2450    2730     425    2730    2800     450
    2800    2870     425    2870    2950     450    2950    7993     425
    8180    9814   425.7    9814   16526     450
Permanent Ineff=
       F       F       F       F       F       F       F       F
Bank Sta=7993,8180
XS Rating Curve= 0 ,0
Exp/Cntr=0.3,0.1

Type RM Length L Ch R = 1 ,18140   ,430,414,500
BEGIN DESCRIPTION:
This cross section corresponds to cross section 18140 of the non-georeferenced CDC model which was the source of this model WF026 Effective flow limit set at 8300 in ROB at Grand Prairie Landfill. Row of houses blocked from 1250-1350 &1420-1500 in LOB. Old West Fork channel removed from conveyance in ROB. Ineffective flow north of Hunter-Ferrell Road -conveyance removed below 427.3 ft. Bear Creek channel removed from conveyance in LOB. Irving Landfill in LOB. USACE channel realignment data from design plans
END DESCRIPTION:
XS GIS Cut Line= 6
  2445269.988104 6974552.3088545 2446004.8301382 6972080.7127478
 2446711.5101553 6969704.1948631 2446999.3150259 6968145.0050681
 2447173.3789823 6967928.3499896 2449713.4519861 6961663.0478877
#Sta/Elev= 30
    1000   452.3    1194   429.7    1534   431.6    1588   418.1    2936   419.2
    2975   427.3    3332     470    4650     470    4850     430    5976   424.8
    6074   436.6    6224   425.4    6605   425.4    6709     391    6786   397.4
    6880   430.2    6927   424.7  8083.3     420  8202.6     440  8934.6     440
  8986.2     430  9179.3     420   11478     420   11616     450   11756     450
   11840     426   11904     422   13588     420   14616     426   14677     440
#Mann= 5 ,-1,0
    1000     .12       0    2975     .05       0    4850     .07       0
    6605    .039       0    6880    .085       0
#XS Ineff= 7 ,-1
    1000    1250   425.4    1250    1350     450    1350    1420   425.4
    1420    1500     450    1500    6605   425.4    6880    8300   424.7
    8300   14677     450
Permanent Ineff=
       F       F       F       F       F       F       F
Bank Sta=6605,6880
XS Rating Curve= 0 ,0
Exp/Cntr=0.3,0.1

Type RM Length L Ch R = 1 ,17726   ,197,210,197
BEGIN DESCRIPTION:
This cross section corresponds to cross section 17726 of the non-georeferenced CDC model which was the source of this model.
WF025. Effective flow limit set at 3100 in LOB, at 9770 in ROB.  Row of houses blocked from 3520 - 3600, 3700 - 3750 in LOB.  Ineffective flow north of Hunter-Ferrell Road - conveyance removed below elev. 426.1.  At old Gifford-Hill railroad spur line - bridge across West Fork washed out in May 1990 flood.  Irving Landfill in LOB. Channel data from 1975 USACOE field survey.
END DESCRIPTION:
XS GIS Cut Line= 6
  2446711.175182 6974412.5545408 2446891.7358447 6970487.4928372
  2446957.909925 6969941.9440595 2447051.1131507 6969593.9851097
  2447262.373883 6969040.9799822 2450145.1591279 6961928.9981432
#Sta/Elev= 30
    3130  453.25 3288.47  439.65 3758.55  432.24 3868.91  419.62    5032   420.1
    5230     470    6450     470    6650     430 7042.58  429.66    8216   425.2
    8388     386    8437   399.1    8483   428.7 9777.35  426.23  9912.7  438.29
10486.87  439.2310880.22  436.7111153.71  427.1111190.39  417.2213037.68  416.71
 13320.1   434.6 13374.6  448.0813637.49  422.7915206.09  427.6415279.76  418.57
15518.98  431.8316078.21  434.7816158.67  425.75 16224.8  440.97 16323.5  424.84
#Mann= 6 ,-1,0
    3130     .12       0    5032     .05       0    6650     .15       0
 7042.58      .1       0    8216    .039       0    8483    .065       0
#XS Ineff= 7 ,-1
    3130    3520   423.5    3520    3600     450    3600    3700   423.5
    3700    3750     450    3750    8216   423.5    8483    9770   425.5
    977016234.08     450
Permanent Ineff=
       F       F       F       F       F       F       F
Bank Sta=8216,8483
XS Rating Curve= 0 ,0
Exp/Cntr=0.3,0.1

Type RM Length L Ch R = 1 ,17516   ,850,1062,1060
BEGIN DESCRIPTION:
This cross section corresponds to cross section 17516 of the non-georeferenced CDC model which was the source of this model.
WF023.  Effective flow limit set at 3180 in LOB, at 9650 in ROB - old West Fork channel removed from conveyance.  Ineffective flow north of Hunter-Ferrell Road - conveyance removed below elev. 425.9.At old Gifford-Hill railroad spur line - bridge across West Fork washed out in May 1990 flood.  Irving Landfill in LOB.Channel data from 1975 USACOE field survey.
END DESCRIPTION:
XS GIS Cut Line= 6
  2446902.064564 6974364.7472217 2447095.8509221 6970501.4731242
 2447153.6368958 6969979.2251529 2447256.1599847 6969609.5188713
 2447454.9939046 6969093.79483722450362.421485316961924.84744545
#Sta/Elev= 30
    3180  458.14 3912.68  420.24    5030   425.5    5230     470    6430     470
    6630     428 6816.62  443.08 6999.63  436.92  7187.7  423.45    8125   423.1
    8225   389.9    8297   397.3    8348   425.3 9194.63  425.36 9570.45   412.3
10126.64  433.2513049.85     42313363.84  458.2513459.92  455.9613486.69  448.73
13499.45  430.7613558.03  421.0714037.72  426.2714314.54  414.3914886.27  427.09
15146.66  410.7915703.75  433.5416061.62  425.9416117.69  440.7416246.04  424.84
#Mann= 6 ,-1,0
    3180     .12       0    5030     .05       0    6630     .15       0
 6999.63      .1       0    8125    .039       0    8348    .065       0
#XS Ineff= 3 ,-1
       0    3870     432    8348    9650   423.1    965016236.69     450
Permanent Ineff=
       T       F       F
Bank Sta=8125,8348
XS Rating Curve= 0 ,0
Exp/Cntr=0.3,0.1

Type RM Length L Ch R = 1 ,16454   ,630,674,680
BEGIN DESCRIPTION:
This cross section corresponds to cross section 16454 of the non-georeferenced CDC model which was the source of this model.
WF022.  Effective flow limit set at 2800 in LOB. at TRA Wastewater Treatment Plant Levee in ROB.  Ineffective flow north of Hunter-Ferrell Road - conveyance removed below elev. 423.0 from 2830 - 4327.  Irving Landfill in LOB. Channel data from 1975 USACOE field survey.
END DESCRIPTION:
XS GIS Cut Line= 6
   2447066.84409  6976028.362989 2447295.9240128 6974035.9982073
 2447513.5728557 6972143.2539613 2448040.6879432 6970588.7314798
 2448288.7589693 6969857.1945571 2448567.8519151 6969034.2178566
#Sta/Elev= 30
    1000   456.5 2968.86   453.4    2993  452.52 3021.44  444.11 3163.99  442.45
 3177.38  435.67 3264.65  433.75 3408.94  419.75 3580.79   416.9 3999.25  421.68
 4292.37  416.93    4360     423    4560     470    5800     470    6000     427
 6050.96  426.41 6090.09  432.67  6159.1  426.71  6642.5  418.67 6702.68  424.15
    7364   422.7    7404   396.9    7434     388    7494   396.9    7537   415.7
 7577.82  424.38 7590.14  424.68 8066.68  424.18 8117.87  431.77 8198.89  439.34
#Mann= 6 ,-1,0
    1000     .12       0    4360     .05       0    6000     .12       0
    7364    .039       0 7577.82    .065       0 8117.87     .03       0
#XS Ineff= 3 ,-1
    1000    2830     470    2830    7364   422.7    7598    8174   423.9
Permanent Ineff=
       F       F       F
#Block Obstruct= 2 , 0
       0                 8197.34       0     442
Bank Sta=7364,7590.14
XS Rating Curve= 0 ,0
Exp/Cntr=0.3,0.1

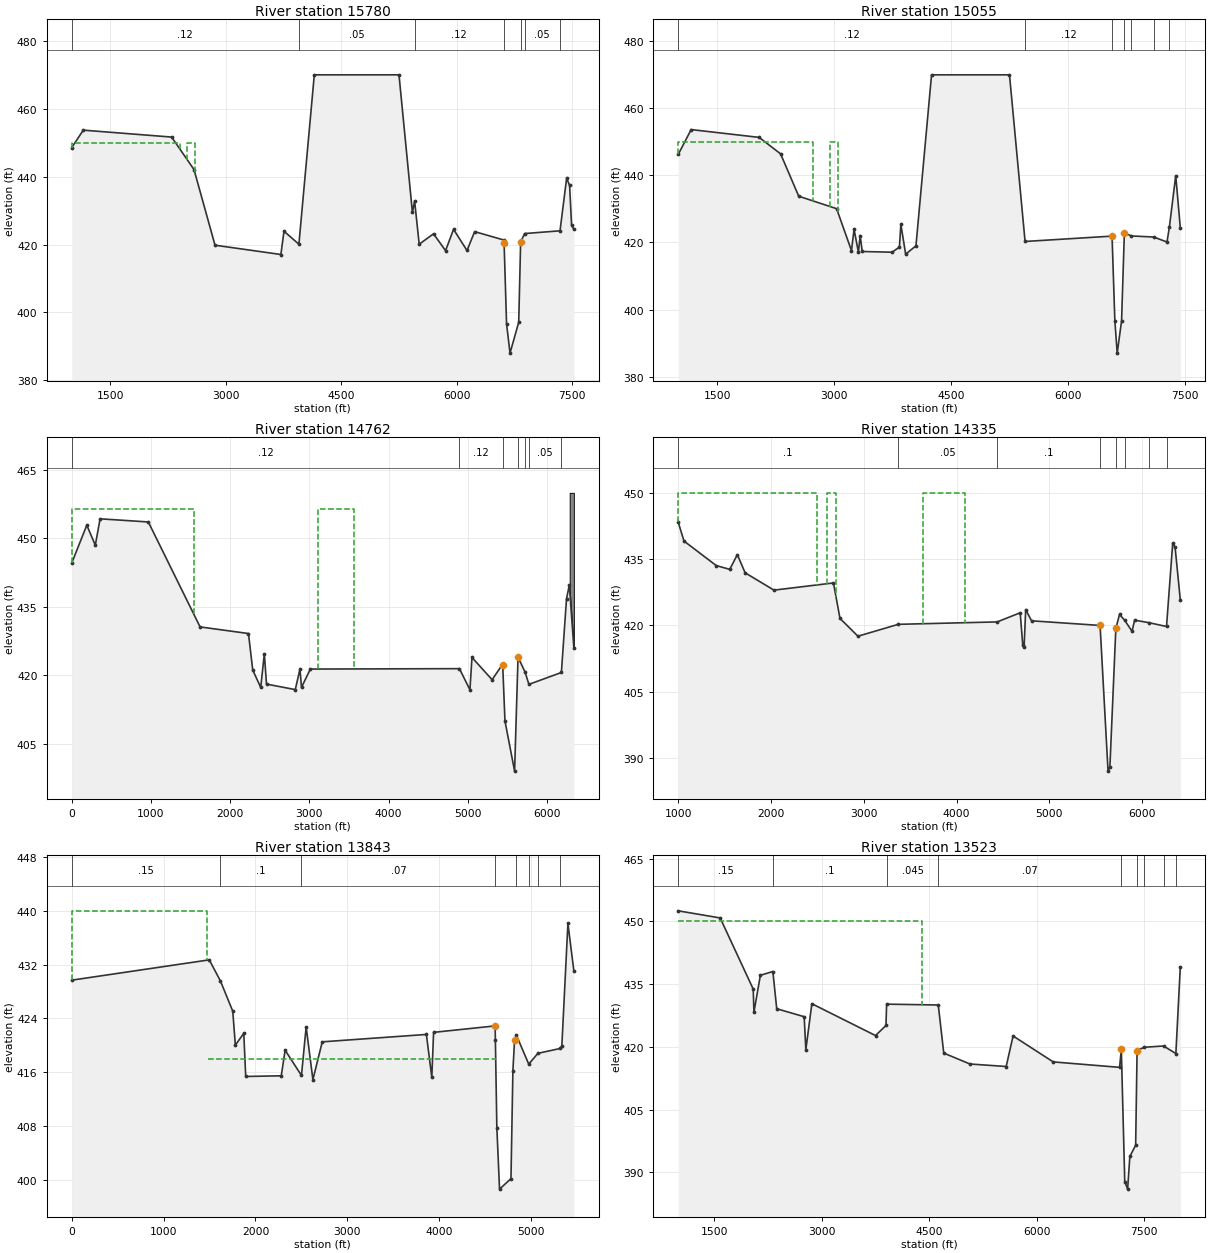
Type RM Length L Ch R = 1 ,15780   ,730,725,730
BEGIN DESCRIPTION:
This cross section corresponds to cross section 15780 of the non-georeferenced CDC model which was the source of this model.
WF021.  Effective flow limit set at 2400 in LOB.  Row of houses blocked out from 2500 - 2600 (elev. set at 455.0).  TRA Wastewater Treatment Plant Levee at ROB.  Ineffective flow north of Hunter-Ferrell Road - conveyance removed below elev. 422.2 (3723). Irving Landfill in LOB.
Channel data from 1975 USACOE field survey.
END DESCRIPTION:
XS GIS Cut Line= 6
  2447423.560896 6975418.2769388  2447686.750987 6973963.8635091
 2447932.4148657   6972606.41314 2448290.0217621 6971687.1830231
 2448611.8849635 6970859.87923152449260.860343646969191.91348706
#Sta/Elev= 30
    1000  448.56 1149.56   453.7 2297.07  451.66 2587.62  442.09 2860.48   419.8
 3715.93  417.06 3756.37  423.91    3950   420.1    4150     470    5250     470
 5424.42  429.45 5452.78  432.84 5512.35  420.09  5698.8  423.16 5854.75  418.19
 5958.57  424.47 6133.35  418.24  6232.6   423.8 6611.78  421.33    6615   420.5
    6647   396.7    6692     388    6805   397.1    6830   420.7 6881.09  423.23
 7341.48  424.04 7427.25  439.54 7465.97  437.41 7491.33   425.7 7520.98  424.44
#Mann= 7 ,-1,0
    1000     .12       0    3950     .05       0 5452.78     .12       0
 6611.78    .039       0    6830     .15       0 6881.09     .05       0
 7341.48     .03       0
#XS Ineff= 5 ,-1
    1000    2400     450    2400    2500   421.2    2500    2600     450
    2600    6611   421.2    6830    7408   420.7
Permanent Ineff=
       F       F       F       F       F
#Block Obstruct= 2 , 0
       0                 7444.04       0     460
Bank Sta=6615,6830
XS Rating Curve= 0 ,0
Exp/Cntr=0.3,0.1

Type RM Length L Ch R = 1 ,15055   ,288.5,288.5,288.5
BEGIN DESCRIPTION:
This cross section corresponds to cross section 15055 of the non-georeferenced CDC model which was the source of this model.
WF020.  Effective flow limit set at 2830 in LOB.  Row of houses blocked out from 2950 - 3050 (elev. set at 455.0).  TRA Wastewater Treatment Plant Levee at ROB.  Ineffective flow north of Hunter-Ferrell Road - conveyance removed below elev. 422.2 (3855). Irving Landfill in LOB.
Channel data from 1975 USACOE field survey.
END DESCRIPTION:
XS GIS Cut Line= 6
  2447591.801045 6975450.3221503 2448126.3550947 6974083.7422063
 2448447.1087183 6973263.7989643 2448767.8777618 6972443.8586751
 2449373.8181509 6970895.09208762449942.661294116969441.28501461
#Sta/Elev= 30
    1000  446.26 1165.71  453.67 2038.21  451.34 2313.21  446.43 2545.85   433.8
 3031.95  430.08 3222.62  417.58 3256.04  423.89 3311.49  417.13 3334.45  422.06
 3360.64  417.31 3744.12   417.1 3838.03  418.62 3856.32  425.37 3917.95  416.52
    4050     419    4250     470    5250     470    5450   420.3    6566   421.9
    6602   396.6    6632     387    6688   396.6    6724   422.9 6812.81  421.95
 7099.85  421.63 7270.82  420.14  7301.1  424.52 7382.96  439.94  7441.7  424.33
#Mann= 7 ,-1,0
    1000     .12       0    5450     .12       0    6566    .039       0
    6724     .15       0 6812.81     .08       0 7099.85     .05       0
  7301.1     .03       0
#XS Ineff= 5 ,-1
    1000    2730     450    2950    3050     450    6724    7348   422.9
    3050    6566   421.9    2730    2950   421.9
Permanent Ineff=
       F       F       F       F       F
#Block Obstruct= 2 , 0
       0                 7387.89       0     460
Bank Sta=6566,6724
XS Rating Curve= 0 ,0
Exp/Cntr=0.3,0.1

Type RM Length L Ch R = 1 ,14762   ,419.9,419.9,419.9
BEGIN DESCRIPTION:
This section has been added as part of the TRA Rail Rehabilitation Project
END DESCRIPTION:
#Sta/Elev= 30
       0  444.64   189.6  452.91   297.2  448.53   357.5  454.31   966.5  453.62
  1619.8  430.64  2230.8  429.19  2284.9  421.18  2385.6  417.39  2431.2  424.76
  2458.5  418.12  2821.9  416.91  2881.1  421.41  2900.4  417.41  3012.3  421.41
  4894.5   421.5  5026.9  416.86  5052.7  423.96  5306.9  419.07  5439.1  422.47
  5440.3   422.4  5469.2  410.05  5590.8  399.06  5634.1  424.01  5722.7  420.76
  5771.6  418.06  6181.6  420.66  6246.2  436.78  6281.7  439.81 6338.81  426.13
#Mann= 7 ,-1,0
       0     .12       0  4894.5     .12       0  5439.1    .039       0
  5634.1     .15       0  5722.7     .08       0  5771.6     .05       0
  6181.6     .03       0
#XS Ineff= 2 ,-1
       0 1538.03  456.39 3107.61 3560.61  456.39
Permanent Ineff=
       F       F
#Block Obstruct= 1 ,-1
  6286.2 6338.81     460
Bank Sta=5440.3,5634.1
XS Rating Curve= 0 ,0
Exp/Cntr=0.3,0.1

Type RM Length L Ch R = 1 ,14335   ,518,490,490
BEGIN DESCRIPTION:
14335
Cross-section WF019.  Effective flow limit set at sta 2500 in LOB.  Row of houses blocked out from sta 2600 - 2700 (elev. set at 455.0).  TRA Wastewater Treatment Plant Levee at ROB.  Ineffective flow north of Hunter-Ferrell Road - conveyance removed below elev. 421.2 from sta 2500 - 3068. Ineffective flow from sta 3635 - 4088 due to Irving Landfill. Channel data from 1975 USACOE field survey. Baseline project - Irving Landfill - in LOB.  Project represented as completed per project plans.
END DESCRIPTION:
XS GIS Cut Line= 3
  2448568.930138 6974705.3243056 2450587.4701389 6969762.0143056
 2450619.52377936969683.51644027
#Sta/Elev= 30
    1000  443.33  1062.2  439.08 1410.01  433.53 1554.96  432.68 1637.21     436
 1720.78   431.9 2031.49  427.97 2672.85   429.6 2743.16  421.57 2936.97  417.54
 3370.96  420.23 4437.47  420.78 4685.24  422.85 4712.44  415.65 4727.28   415.2
 4744.57  423.56 4807.57  421.03 5546.24  419.98    5632     387    5652     388
    5716   419.3 5755.76  422.46 5811.56  421.14 5890.26  418.66 5918.58  421.18
 6074.02   420.6 6262.09  419.74 6328.71  438.54 6354.24  437.74 6410.79  425.75
#Mann= 8 ,-1,0
    1000      .1       0 3370.96     .05       0 4437.47      .1       0
 5546.24    .039       0    5716     .15       0 5811.56     .08       0
 6074.02     .05       0 6262.09     .03       0
#XS Ineff= 7 ,-1
    1000    2500     450    2600    2700     450    3635    4088     450
    5716    6326   419.3    2500    2600   416.8    4088    5536   416.8
    2700    3635   416.8
Permanent Ineff=
       F       F       F       F       F       F       F
#Block Obstruct= 2 , 0
       0                 6350.39       0     450
Bank Sta=5546.24,5716
XS Rating Curve= 0 ,0
Exp/Cntr=0.3,0.1

Type RM Length L Ch R = 1 ,13843   ,322,322,322
BEGIN DESCRIPTION:
13843
CDC GP092823-1 TRA Railway Improvements
END DESCRIPTION:
XS GIS Cut Line= 2
  2449095.740138 6974980.2343056 2450891.27653976970283.45747069
#Sta/Elev= 30
       0  429.69 1496.68  432.71 1618.22  429.58 1752.61  425.08 1780.78  420.04
 1872.49  421.78 1893.76  415.37  2280.6  415.47 2322.76  419.28  2500.5  415.52
  2551.6  422.74 2625.09   414.9 2726.85  420.52 3860.66  421.62 3919.66  415.23
 3938.91  421.93    4609  422.89  4611.8  420.74 4627.61  407.75 4657.03  398.62
 4781.38  400.18 4802.37  416.22 4820.26  420.74 4839.97  421.52 4974.83  417.21
 5074.59  418.81 5319.11  419.54 5335.37  419.94 5401.19  438.14 5465.88  431.08
#Mann= 8 ,-1,0
       0     .15       0 1618.22      .1       0  2500.5     .07       0
  4611.8    .039       0 4839.97     .15       0 4974.83     .08       0
 5074.59     .05       0 5319.11     .03       0
#XS Ineff= 2 ,-1
       0 1476.44     440 1484.29 4615.14     418
Permanent Ineff=
       F       F
#Block Obstruct= 2 , 0
       0                 5423.06       0     441
Bank Sta=4609,4820.26
XS Rating Curve= 0 ,0
Exp/Cntr=0.3,0.1

Type RM Length L Ch R = 1 ,13523   ,306,306,306
BEGIN DESCRIPTION:
13523
Cross-section WF018.  Effective flow limit set at sta 4400 in LOB.  TRA Wastewater Treatment Plant Levee at ROB.  Conveyance removed from channels (not included in ground points) in LOB.
Channel data from 1975 USACOE field survey.
END DESCRIPTION:
XS GIS Cut Line= 2
  2448769.220138 6976555.9743056 2451340.2801389 6970022.9143056
#Sta/Elev= 30
    1000   452.5    1585   450.8    2046   433.8    2056   428.3    2146   437.1
    2320     438    2374   429.1    2757   427.2    2780   419.3    2864   430.3
    3752   422.7    3898   425.1    3907   430.2 4627.57     430    4704   418.5
    5070   415.9    5575   415.3    5671   422.6    6231   416.4    7157   415.1
    7181   419.4    7229   387.8    7269     386    7300   393.8    7381   396.5
    7401   419.1    7500   419.9    7770   420.2    7942   418.4    8004   439.1
#Mann= 9 ,-1,0
    1000     .15       0    2320      .1       0    3907    .045       0
 4627.57     .07       0    7181    .039       0    7401     .15       0
    7500     .08       0    7770     .05       0    7942     .03       0
#XS Ineff= 3 ,-1
    1000    4400     450    4400    7181   419.4    7401    8004   419.1
Permanent Ineff=
       F       T       F
Bank Sta=7181,7401
XS Rating Curve= 0 ,0
Exp/Cntr=0.3,0.1

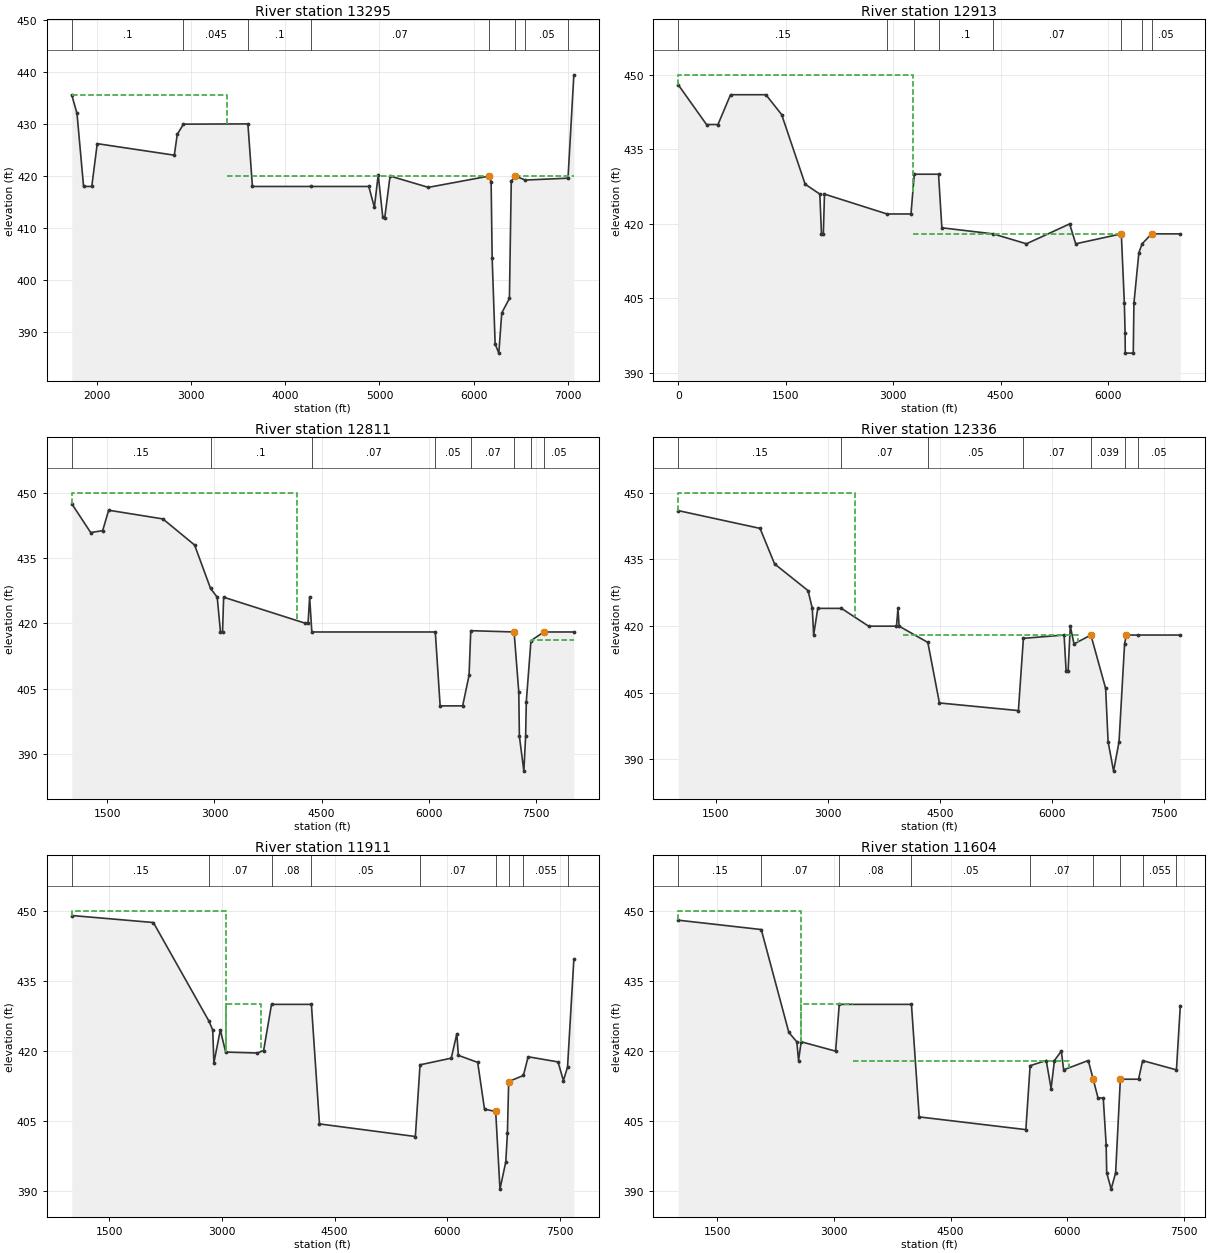
Type RM Length L Ch R = 1 ,13295   ,333.9,306.9,306.03
BEGIN DESCRIPTION:
Added cross-section for Lindamood CDC permit - repeated channel geometry from aapproximatley station 6000 to 6500.
END DESCRIPTION:
XS GIS Cut Line= 2
  2449030.910138 6976666.3343056 2451658.2501389 6970066.5943056
#Sta/Elev= 30
 1730.23  435.54 1785.69  432.01 1855.65     418 1942.84  418.01  2000.9  426.21
 2820.04     424 2851.26     428 2916.91  429.95 3601.94     430 3649.94     418
 4274.54     418 4886.59     418 4945.79     414 4986.69  420.24 5035.13  412.11
 5055.67  411.95 5112.62     420 5519.47  417.83 6166.35     420 6186.46  418.94
 6197.56  404.24 6229.21  387.79 6268.25  386.04 6299.49  393.75 6380.87  396.52
  6400.6  419.04 6442.94     420 6549.52  419.23 7003.54  419.59 7065.54  439.41
#Mann= 8 ,-1,0
 1730.23      .1       0 2916.91    .045       0 3601.94      .1       0
 4274.54     .07       0 6166.35    .039       0 6442.94     .09       0
 6549.52     .05       0 7003.54     .03       0
#XS Ineff= 3 ,-1
 1730.23    3377   435.6    3377    6166     420    6443 7065.54     420
Permanent Ineff=
       F       T       F
Bank Sta=6166.35,6442.94
XS Rating Curve= 0 ,0
Exp/Cntr=0.3,0.1

Type RM Length L Ch R = 1 ,12913   ,99.66,99,97.87
BEGIN DESCRIPTION:
12913
END DESCRIPTION:
XS GIS Cut Line= 6
  2449337.410138 6976771.5943056 2451248.2701389 6971922.6843056
 2451266.3301389 6971876.8443056 2451292.6101389 6971810.1743056
 2451639.0901389 6970930.9743056 2451908.2101389 6970249.6443056
#Sta/Elev= 30
       0     448  395.02     440     555     440     730     446    1224     446
    1444     442    1772     428    1977     426    2000     418    2026     418
    2042     426    2915     422    3250     422 3295.83     430 3634.55     430
 3680.95  419.22    4396     418    4862     416    5465     420 5549.97     416
 6186.82     418 6229.17     404  6239.5     398 6241.86     394 6353.58     394
 6362.51     404 6431.66  414.21 6476.99     416 6609.71     418 7010.34     418
#Mann= 8 ,-1,0
       0     .15       0    2915      .1       0 3295.83    .045       0
 3634.55      .1       0    4396     .07       0 6186.82    .039       0
 6476.99     .09       0 6609.71     .05       0
#XS Ineff= 2 ,-1
       0    3275     450    3275 6134.41     418
Permanent Ineff=
       F       T
Bank Sta=6186.82,6609.71
XS Rating Curve= 0 ,0
Exp/Cntr=0.3,0.1

Type RM Length L Ch R = 1 ,12811   ,501.53,506.71,515.36
BEGIN DESCRIPTION:
12811
Revised XS; Same Ineffectives as Original Model
------------------------------------------------------------------
CDC GP042800-02 West Fork Relief Interceptor WF-1
Cross-section 12811 - 15780
Project located in ROB.
---------------------------------------------------
Cross-section WF017.  Effective flow limit set at sta 4150 in LOB, sta 8040 in ROB.  Approx. 500 feet upstream of left bank of Mountain Creek.
Conveyance removed from channels in LOB.
Channel data from 1975 USACOE field survey.
END DESCRIPTION:
XS GIS Cut Line= 2
  2449470.450138 6976839.6943056 2451999.1501389 6970272.9543056
#Sta/Elev= 30
    1000  447.49 1265.24  440.86 1432.94   441.3    1517     446    2277     444
    2721     438    2945     428    3038     426    3084     418    3113     418
    3128     426    4274     420    4311     420    4333     426    4364     418
    6094     418    6162     401 6477.53  401.01 6566.96     408  6591.1   418.3
 7198.48     418 7263.83  404.21 7272.51     394    7335     386 7359.88     394
 7369.32     402 7434.59     416    7615     418 7615.02     418 8035.52     418
#Mann= 8 ,-1,0
    1000     .15       0    2945      .1       0    4364     .07       0
    6094     .05       0  6591.1     .07       0 7198.48    .039       0
 7434.59     .09       0 7615.02     .05       0
#XS Ineff= 3 ,-1
    1000    4150     450    4150 7198.48     418    7433 8035.52   416.1
Permanent Ineff=
       F       T       F
Bank Sta=7198.48,7615
XS Rating Curve= 0 ,0
Exp/Cntr=0.3,0.1

Type RM Length L Ch R = 1 ,12336   ,395.2,396.85,393.95
BEGIN DESCRIPTION:
Added XS
Left Ineffective Set for Delaware Creek
END DESCRIPTION:
XS GIS Cut Line= 2
  2449893.200138 6976430.6743056 2452581.9501389 6970277.3043056
#Sta/Elev= 30
    1000     446    2094     442    2289     434    2736     428    2793     424
    2811     418    2866     424    3183     424    3546     420    3919     420
    3939     424    3954     420  4338.4  416.34 4493.25  402.72 5549.69     401
 5616.46  417.26 6160.61     418 6187.39     410 6214.69     410 6243.63     420
 6293.35     416 6519.05     418 6716.26     406 6749.39     394 6822.55  387.38
 6895.71     394    6970  416.04 6993.68     418    7150     418 7715.16     418
#Mann= 7 ,-1,0
    1000     .15       0    3183     .07       0  4338.4     .05       0
 5616.46     .07       0 6519.05    .039       0    6970     .09       0
    7150     .05       0
#XS Ineff= 2 ,-1
    1000    3358     450    4000 6345.48     418
Permanent Ineff=
       F       T
Bank Sta=6519.05,6993.68
XS Rating Curve= 0 ,0
Exp/Cntr=0.3,0.1

Type RM Length L Ch R = 1 ,11911   ,306.43,307.09,303.8
BEGIN DESCRIPTION:
11911
Cross-section WF016.  Approx. 400 feet downstream of right bank of Mountain Creek.  Effective flow limit set at sta 3050 in LOB.  Effective flow set at West Levee in ROB.
Channel data from 1975 USACOE field survey.
END DESCRIPTION:
XS GIS Cut Line= 2
  2450188.810138 6976571.0343056 2452932.7601389 6970461.3543056
#Sta/Elev= 30
    1000     449    2087   447.5    2828   426.4    2878   424.5    2893   417.5
    2979   424.5    3050   419.8    3473   419.6 3555.71  420.12 3660.67     430
 4192.17     430  4299.6  404.44 5576.81  401.75 5639.19  417.08    6055   418.5
    6129   423.7    6150   419.1    6407   417.6    6498   407.6    6647   407.1
    6704   390.5    6781   396.3    6803   402.4    6820   413.5    7016   414.8
    7079   418.8    7477   417.7    7549   413.7    7604   416.6    7688   439.6
#Mann= 9 ,-1,0
    1000     .15       0    2828     .07       0 3660.67     .08       0
 4192.17     .05       0 5639.19     .07       0    6647    .039       0
    6820     .09       0    7016    .055       0    7604     .03       0
#XS Ineff= 4 ,-1
       0    3050     450    3050    3525     430    3525    5700   415.5
    6820    7690   413.5
Permanent Ineff=
       F       F       T       F
Bank Sta=6647,6820
XS Rating Curve= 0 ,0
Exp/Cntr=0.3,0.1

Type RM Length L Ch R = 1 ,11604   ,327.37,323.45,323.31
BEGIN DESCRIPTION:
11604
END DESCRIPTION:
XS GIS Cut Line= 2
  2450614.990138 6976618.5843056 2453145.2601389 6970686.2443056
#Sta/Elev= 30
    1000     448 2067.07     446 2421.52     424 2524.02     422 2546.34     418
 2579.93     422  3022.8     420 3069.42     430 3997.27     430 4096.81  405.94
 5467.72  403.22 5522.43  416.89 5729.53     418 5791.97     412 5834.79     418
 5923.68     420 5953.29     416 6269.72     418 6332.96     414 6395.14     410
 6462.43     410 6499.65     400 6506.82     394    6564   390.5 6621.43     394
 6682.11     414 6916.04     414 6968.69  417.98 7402.99     416 7452.74  429.71
#Mann= 9 ,-1,0
    1000     .15       0 2067.07     .07       0 3069.42     .08       0
 3997.27     .05       0 5522.43     .07       0 6332.96    .039       0
 6682.11     .09       0 6968.69    .055       0 7402.99     .03       0
#XS Ineff= 4 ,-1
       0    2580     450    2580    3250     430    3250    6023     418
 6682.11 7452.74     414
Permanent Ineff=
       F       F       T       F
Bank Sta=6332.96,6682.11
XS Rating Curve= 0 ,0
Exp/Cntr=0.3,0.1

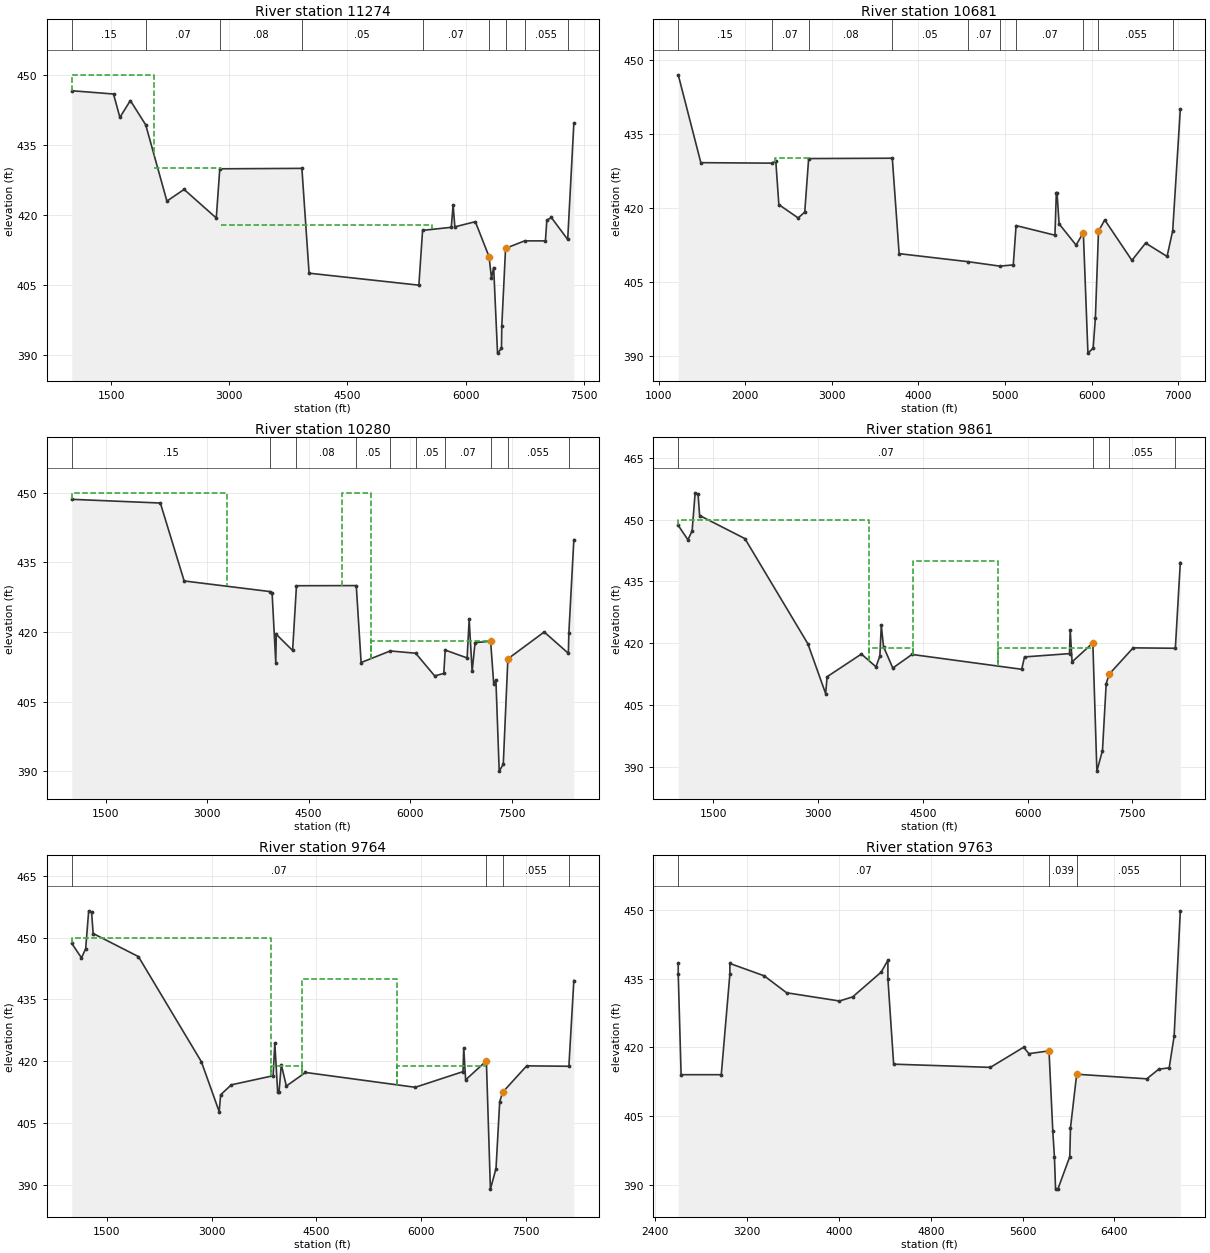
Type RM Length L Ch R = 1 ,11274   ,620,593,600
BEGIN DESCRIPTION:
11274
Cross-section WF015.  Effective flow limit set at sta 2050 in LOB.  Delaware Creek blocked from conveyance in LOB.   Effective flow limit set at West Levee in ROB.
Channel data from 1975 USACOE field survey.
END DESCRIPTION:
XS GIS Cut Line= 2
  2451081.980138 6976732.7643056 2453421.5001389 6970792.3743056
#Sta/Elev= 30
    1000   446.6    1530   445.9    1611   440.9    1744   444.5    1939   439.3
    2208     423    2426   425.5 2834.84  419.39 2879.48  429.91 3921.95     430
  4013.3  407.59 5407.27  405.03 5454.37  416.74    5819   417.4    5842   422.2
    5864   417.5    6124   418.6    6299   411.1    6329   406.5    6357   408.8
    6406   390.5    6456   391.5    6460   396.3    6508   412.9    6750   414.5
    7014   414.5    7032   418.9    7089   419.5    7297   414.8    7375   439.6
#Mann= 9 ,-1,0
    1000     .15       0    1939     .07       0 2879.48     .08       0
 3921.95     .05       0 5454.37     .07       0    6299    .039       0
    6508     .09       0    6750    .055       0    7297     .03       0
#XS Ineff= 3 ,-1
    1000    2050     450    2050    2900     430    2900    5573     418
Permanent Ineff=
       T       F       T
Bank Sta=6299,6508
XS Rating Curve= 0 ,0
Exp/Cntr=0.3,0.1

Type RM Length L Ch R = 1 ,10681   ,530,401,405
BEGIN DESCRIPTION:
10681
Cross-section WF014.  Delaware Creek removed from conveyance in LOB.
Ineffective flow from sta 1226 - 1953 below elev. 429.1 due to high ground.
Effective flow limit set at West Levee in ROB.
Channel data from 1975 USACOE field survey.
END DESCRIPTION:
XS GIS Cut Line= 6
  2451985.490138 6976732.7643056 2452964.9501389 6973690.5543056
 2453067.9301389 6973370.7243056 2453071.6001389 6973359.2943056
 2453146.9401389 6973125.3143056 2453939.6001389 6971025.5843056
#Sta/Elev= 30
    1226   446.9    1487   429.1    2306     429    2353   429.4    2388   420.6
    2611   417.9 2687.16  419.08 2732.25  429.93 3698.56     430 3777.35  410.66
    4574  409.03 4941.75  408.13 5095.78  408.38 5128.11  416.35    5577   414.4
    5593     423    5601     423    5625   416.7    5821   412.4    5905   414.9
    5958   390.5    6018   391.5    6044   397.6    6080   415.2    6152   417.5
    6466   409.3    6624   412.8    6872   410.1    6937   415.3    7025   439.9
#Mann= 10 ,-1,0
    1226     .15       0    2306     .07       0 2732.25     .08       0
 3698.56     .05       0    4574     .07       0 4941.75     .05       0
 5128.11     .07       0    5905    .039       0    6080    .055       0
    6937     .03       0
#XS Ineff= 3 ,-1
    2340    2760     430    2760    5905   414.9    6080    7000   415.2
Permanent Ineff=
       F       T       F
Bank Sta=5905,6080
XS Rating Curve= 0 ,0
Exp/Cntr=0.3,0.1

Type RM Length L Ch R = 1 ,10280   ,350,419,300
BEGIN DESCRIPTION:
10280
Cross-section WF013.  Effective flow limit set at sta 3300 in LOB. Ineffective flow from sta 4990 - 5420 due to Loop 12 embankment - elev. set at 430.0 (minimum low point in roadway).  Delaware Creek blocked from conveyance
in LOB.  Effective flow limit set at West Levee in ROB.  Old West Fork channel (Eagle Ford sluice) removed from conveyance in ROB.
Channel data from 1975 USACOE field survey.
END DESCRIPTION:
XS GIS Cut Line= 2
  2452272.970138 6978313.9043056 2454205.2001389 6971140.1343056
#Sta/Elev= 30
    1000   448.6    2309   447.8    2661     431    3936   428.7    3961   428.3
    4015   413.4    4022   419.5 4263.77  416.01 4320.68  429.97 5204.53     430
 5275.99  413.41 5706.82  415.91 6082.15  415.42 6363.41  410.53 6498.05  411.06
 6518.76   416.1    6843   414.4    6873   422.7    6917   411.5    6960   417.7
    7190     418    7236   408.8    7268   409.7    7317     390    7377   391.5
    7445   414.2    7982     420    8339   415.4    8346   419.7    8420   439.9
#Mann= 10 ,-1,0
    1000     .15       0    3936     .07       0 4320.68     .08       0
 5204.53     .05       0 5706.82     .07       0 6082.15     .05       0
 6518.76     .07       0    7190    .039       0    7445    .055       0
    8346     .03       0
#XS Ineff= 5 ,-1
    1000    3300     450    3300    4990     418    4990    5420     450
    5420    7190     418    7445    8420   414.2
Permanent Ineff=
       F       T       F       F       F
Bank Sta=7190,7445
XS Rating Curve= 0 ,0
Exp/Cntr=0.3,0.1

Type RM Length L Ch R = 1 ,9861    ,95,95,95
BEGIN DESCRIPTION:
This cross section corresponds to cross section 9861 of the non-georeferenced CDC model which was the source of this model. WF012.98 ft upstream of Loop 12.Effective flow limit set at 3730 in LOB. Ineffective flow from 4360-5577 due to Loop 12 embankment. Elev.set at 430.0 (min low point in roadway). Delaware Creek removed from conveyance in LOB.Old West Fork channel (Eagle Ford sluice) removed from conveyance in ROB.  Effective flow limit set at West Levee in ROB. Channel data from 1975 USACE field survey.
END DESCRIPTION:
XS GIS Cut Line= 6
   2453263.27986 6978342.9840159 2453265.7769024 6977926.0721201
 2453280.2880282 6977491.1920843 2453365.6480937 6976885.8921138
 2453572.3409218 6975826.5900986 2454511.7839248 6971270.0529518
#Sta/Elev= 30
    1000   448.6    1139   445.1    1199   447.3    1242   456.5    1284   456.1
    1306     451    1954   445.4    2855   419.9    3110   407.8    3131   411.9
    3622   417.4    3830   414.3    3886   416.9    3906   424.4    3938   419.2
    4071     414    4345   417.3    5916   413.7    5956   416.7    6600   417.5
    6610   423.3    6637   415.5    6934   420.1    6992     389    7072     394
    7125   410.2    7167   412.5    7511   418.9    8115   418.8    8186   439.6
#Mann= 4 ,-1,0
    1000     .07       0    6934    .039       0    7167    .055       0
    8115     .03       0
#XS Ineff= 5 ,-1
    1000    3730     450    3730    4360   418.8    4360    5577     440
    5577    6934   418.8    7167    8186   412.5
Permanent Ineff=
       F       F       F       F       F
Bank Sta=6934,7167
XS Rating Curve= 0 ,0
Exp/Cntr=0.3,0.1

Type RM Length L Ch R = 1 ,9764    ,1,1,1
BEGIN DESCRIPTION:
This cross section corresponds to cross section 9764 of the non-georeferenced CDC model which was the source of this model.
END DESCRIPTION:
XS GIS Cut Line= 6
  2453357.112677 6978358.5043261   2453359.60972 6977941.5924302
 2453374.1208458 6977506.7123945 2453459.4809113  6976901.412424
 2453666.1737394 6975842.1104087 2454605.6167424  6971285.573262
#Sta/Elev= 30
    1000   448.6    1139   445.1    1199   447.3    1242   456.5    1284   456.1
    1306     451    1954   445.4    2855   419.9    3110   407.8    3131   411.9
    3284   414.3    3882   416.5    3906   424.4    3947   412.6    3966   412.5
    3999   419.2    4071     414    4345   417.3    5916   413.7    6600   417.5
    6610   423.3    6637   415.5    6934   420.1    6992     389    7072     394
    7125   410.2    7167   412.5    7511   418.9    8115   418.8    8186   439.6
#Mann= 4 ,-1,0
    1000     .07       0    6934    .039       0    7167    .055       0
    8115     .03       0
#XS Ineff= 5 ,-1
    1000    3850     450    3850    4300   418.8    4300    5650     440
    5650    6934   418.8    7167    8186   412.5
Permanent Ineff=
       F       F       F       F       F
Bank Sta=6934,7167
XS Rating Curve= 0 ,0
Exp/Cntr=0.3,0.1

Type RM Length L Ch R = 1 ,9763    ,145,145,145
BEGIN DESCRIPTION:
This cross section corresponds to cross section 9763 of the non-georeferenced CDC model which was the source of this model.
END DESCRIPTION:
XS GIS Cut Line= 6
  2453697.760618 6975693.1822289 2453751.7316392 6975431.9314391
 2454006.9135435 6974194.1425761  2454186.804916 6973321.6138093
 2454406.6843975 6972255.1917296 2454581.1988123 6971408.8400758
#Sta/Elev= 30
    2600   438.3    2600     436    2625     414    2975     414    3050     436
    3050   438.3    3349   435.6    3544   431.9    4005   430.1    4120     431
    4368   436.4    4427     439    4427     435    4477   416.3    5320   415.6
    5610     420    5655   418.6    5831   419.2    5864   401.6    5878   396.1
    5888     389    5908     389    6012   396.1    6018   402.4    6072   414.1
    6683   413.1    6787   415.2    6878   415.5    6921   422.4    6975   449.8
#Mann= 4 ,-1,0
    2600     .07       0    5831    .039       0    6072    .055       0
    6975     .03       0
#XS Ineff= 2 , 0
                            6072           414.1
Permanent Ineff=
       F       F
Bank Sta=5831,6072
XS Rating Curve= 0 ,0
Exp/Cntr=0.5,0.3