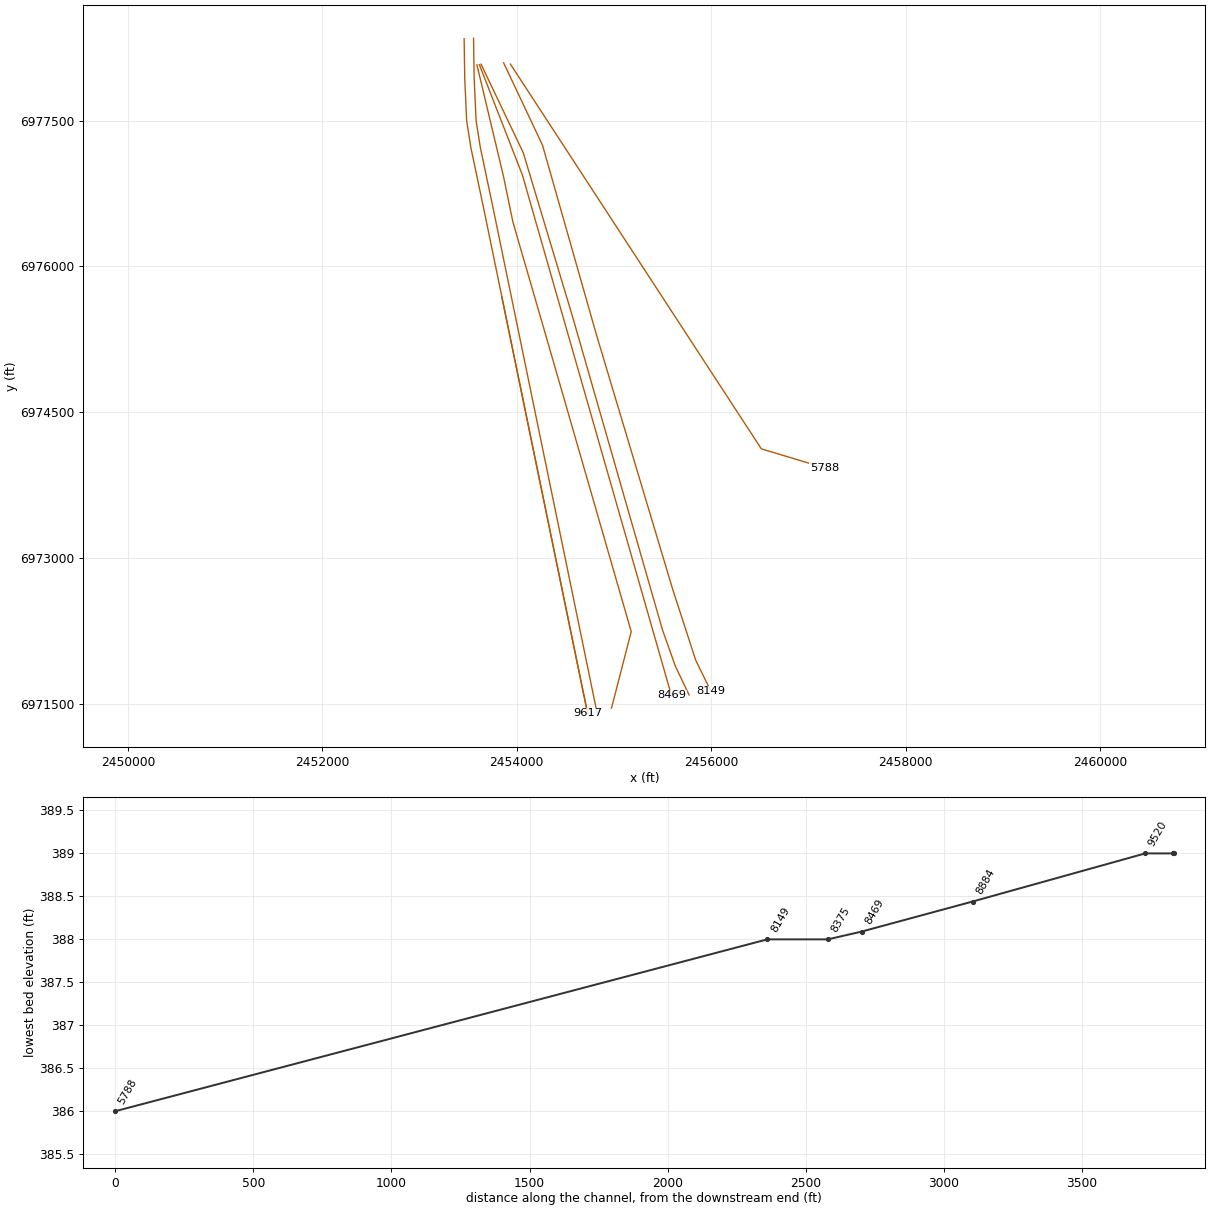
HEC-RAS study CDC_Consolidated_Model.prj: Upper Trinity CDC Consolidated Model

--- CDC_Consolidated_Model.g12 (geometry) --- (continued)

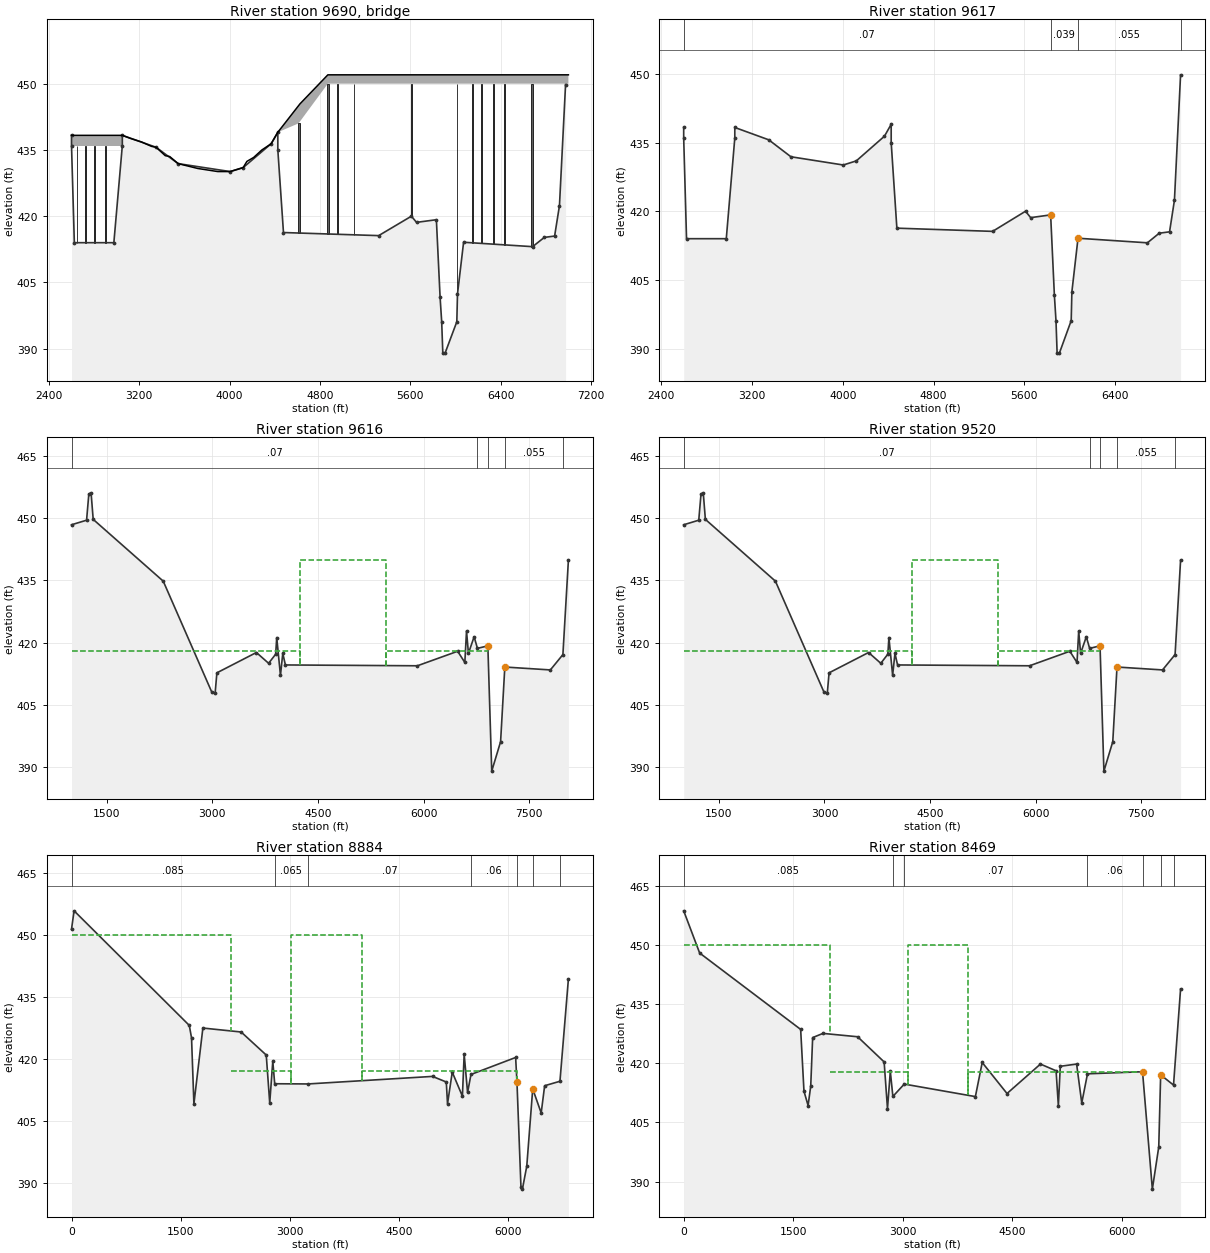
Type RM Length L Ch R = 3 ,9690    ,,,
BEGIN DESCRIPTION:
Loop 12
END DESCRIPTION:
Node Name=Loop 12
Bridge Culvert--1,0,-1,-1, 0
Deck Dist Width WeirC Skew NumUp NumDn MinLoCord MaxHiCord MaxSubmerge Is_Ogee
0.5,144,2.6,0, 23, 23, , , 0.95, 0, ,,,
    2600    3050    3050    3123    3220    3309    3349    3430    3470    3544
    3718    3895    4005    4120    4153    4213    4286    4368    4427    4610
    4622    4870    7000
   438.3   438.3   438.3   437.6   436.8   435.8   435.6   433.7   433.5   431.9
   430.8   430.1   430.1     431   432.4   433.3     435   436.4     439     445
   445.4     452     452
     436     436   438.3   437.6   436.8   435.8   435.6   433.7   433.5   431.9
   430.8   430.1   430.1     431   432.4   433.3     435   436.4     439     441
   441.4     450     450
    2600    3050    3050    3123    3220    3309    3349    3430    3470    3544
    3718    3895    4005    4120    4153    4213    4286    4368    4427    4610
    4622    4870    7000
   438.3   438.3   438.3   437.6   436.8   435.8   435.6   433.7   433.5   431.9
   430.8   430.1   430.1     431   432.4   433.3     435   436.4     439     445
   445.4     452     452
     436     436   438.3   437.6   436.8   435.8   435.6   433.7   433.5   431.9
   430.8   430.1   430.1     431   432.4   433.3     435   436.4     439     441
   441.4     450     450
Pier Skew, UpSta & Num, DnSta & Num=  ,2647, 2 ,2647, 2 , 0 , 0 , 0 ,,
       4       4
     410     437
       4       4
     410     437
Pier Skew, UpSta & Num, DnSta & Num=  ,2722, 2 ,2722, 2 , 0 , 0 , 0 ,,
       4       4
     410     437
       4       4
     410     437
Pier Skew, UpSta & Num, DnSta & Num=  ,2802, 2 ,2802, 2 , 0 , 0 , 0 ,,
       4       4
     410     437
       4       4
     410     437
Pier Skew, UpSta & Num, DnSta & Num=  ,2902, 2 ,2902, 2 , 0 , 0 , 0 ,,
       4       4
     410     437
       4       4
     410     437
Pier Skew, UpSta & Num, DnSta & Num=  ,4616, 2 ,4616, 2 , 0 , 0 , 0 ,,
      12      12
     415   441.4
      12      12
     415   441.4
Pier Skew, UpSta & Num, DnSta & Num=  ,4870.5, 2 ,4870.5, 2 , 0 , 0 , 0 ,,
      15      15
     415   450.5
      15      15
     415   450.5
Pier Skew, UpSta & Num, DnSta & Num=  ,4954.5, 2 ,4954.5, 2 , 0 , 0 , 0 ,,
      15      15
     415   450.5
      15      15
     415   450.5
Pier Skew, UpSta & Num, DnSta & Num=  ,5102.5, 2 ,5102.5, 2 , 0 , 0 , 0 ,,
       5       5
     415   450.5
       5       5
     415   450.5
Pier Skew, UpSta & Num, DnSta & Num=  ,5613, 2 ,5613, 2 , 0 , 0 , 0 ,,
       6       6
     415   450.5
       6       6
     415   450.5
Pier Skew, UpSta & Num, DnSta & Num=  ,6015, 2 ,6015, 2 , 0 , 0 , 0 ,,
       6       6
     400   450.5
       6       6
     400   450.5
Pier Skew, UpSta & Num, DnSta & Num=  ,6152.5, 2 ,6152.5, 2 , 0 , 0 , 0 ,,
       5       5
     400   450.5
       5       5
     400   450.5
Pier Skew, UpSta & Num, DnSta & Num=  ,6231, 2 ,6231, 2 , 0 , 0 , 0 ,,
       6       6
     400   450.5
       6       6
     400   450.5
Pier Skew, UpSta & Num, DnSta & Num=  ,6337, 2 ,6337, 2 , 0 , 0 , 0 ,,
       6       6
     400   450.5
       6       6
     400   450.5
Pier Skew, UpSta & Num, DnSta & Num=  ,6432, 2 ,6432, 2 , 0 , 0 , 0 ,,
       6       6
     400   450.5
       6       6
     400   450.5
Pier Skew, UpSta & Num, DnSta & Num=  ,6675.5, 2 ,6675.5, 2 , 0 , 0 , 0 ,,
      15      15
     400   450.5
      15      15
     400   450.5
BR Coef= 1 , 0 , 0 ,1.05, 0 ,,,0.8,-1,0.5,1,
WSPro=,,,, 1 ,,,, 0 ,,,, 0 ,,,,-1 ,-1 ,-1 , 0 , 0 , 0 , 0 , 0
BC Design=,, 0 ,, 0 ,,,,,,
BC HTab HWMax=449.8
BC Use User HTab Curves=0
BC User HTab FreeFlow(D)= 0

Type RM Length L Ch R = 1 ,9617    ,1,1,1
BEGIN DESCRIPTION:
This cross section corresponds to cross section 9617 of the non-georeferenced CDC model which was the source of this model.
END DESCRIPTION:
XS GIS Cut Line= 6
  2453845.692541 6975687.4062422 2453980.8617583 6975031.0713484
 2454081.8543385 6974540.7029066 2454304.0481198 6973461.8937125
 2454526.2556807 6972383.0864869 2454728.2746336 6971402.3538683
#Sta/Elev= 30
    2600   438.3    2600     436    2625     414    2975     414    3050     436
    3050   438.3    3349   435.6    3544   431.9    4005   430.1    4120     431
    4368   436.4    4427     439    4427     435    4477   416.3    5320   415.6
    5610     420    5655   418.6    5831   419.2    5864   401.6    5878   396.1
    5888     389    5908     389    6012   396.1    6018   402.4    6072   414.1
    6683   413.1    6787   415.2    6878   415.5    6921   422.4    6975   449.8
#Mann= 4 ,-1,0
    2600     .07       0    5831    .039       0    6072    .055       0
    6975     .03       0
#XS Ineff= 2 , 0
                            6072           414.1
Permanent Ineff=
       F       F
Bank Sta=5831,6072
XS Rating Curve= 0 ,0
Exp/Cntr=0.5,0.3

Type RM Length L Ch R = 1 ,9616    ,102,102,102
BEGIN DESCRIPTION:
This cross section corresponds to cross section 9616 of the non-georeferenced CDC model which was the source of this model.
END DESCRIPTION:
XS GIS Cut Line= 6
  2453458.497317 6978343.0883464 2453464.7384467 6977931.1682385
 2453484.7754802 6977494.4017236 2453529.4915981 6977213.4291884
 2453658.6744106  6976600.397278 2454729.2444479 6971402.4985531
#Sta/Elev= 30
    1000   448.4    1214   449.5    1246   455.8    1278   456.1    1308   449.7
    2303   434.8    2994     408    3040   407.8    3065   412.7    3626   417.6
    3800     415    3900   417.2    3915   421.2    3968   412.1    4001   417.4
    4038   414.6    5913   414.4    6485   417.9    6587   415.2    6611   422.8
    6638   417.4    6719   421.4    6766   418.6    6914   419.2    6969     389
    7095   396.1    7155   414.1    7802   413.4    7980   417.1    8058   439.8
#Mann= 5 ,-1,0
    1000     .07       0    6766     .06       0    6914    .039       0
    7155    .055       0    7980     .03       0
#XS Ineff= 4 ,-1
    1000    4240     418    4240    5467     440    5467    6914     418
    7155    8058   414.1
Permanent Ineff=
       F       F       F       F
Bank Sta=6914,7155
XS Rating Curve= 0 ,0
Exp/Cntr=0.3,0.1

Type RM Length L Ch R = 1 ,9520    ,405,625,364
BEGIN DESCRIPTION:
This cross section corresponds to cross section 9520 of the non-georeferenced CDC model which was the source of this model.
END DESCRIPTION:
XS GIS Cut Line= 6
  2453555.368842 6978346.7290871 2453561.6099722 6977934.8089792
 2453581.6470056 6977498.0421362 2453626.3631235 6977217.0699292
  2453755.545936 6976604.0380187 2454826.1159733 6971406.1389657
#Sta/Elev= 30
    1000   448.4    1214   449.5    1246   455.8    1278   456.1    1308   449.7
    2303   434.8    2994     408    3040   407.8    3065   412.7    3626   417.6
    3800     415    3900   417.2    3915   421.2    3968   412.1    4001   417.4
    4038   414.6    5913   414.4    6485   417.9    6587   415.2    6611   422.8
    6638   417.4    6719   421.4    6766   418.6    6914   419.2    6969     389
    7095   396.1    7155   414.1    7802   413.4    7980   417.1    8058   439.8
#Mann= 5 ,-1,0
    1000     .07       0    6766     .06       0    6914    .039       0
    7155    .055       0    7980     .03       0
#XS Ineff= 4 ,-1
    1000    4240     418    4240    5467     440    5467    6914     418
    7155    8058   414.1
Permanent Ineff=
       F       F       F       F
Bank Sta=6914,7155
XS Rating Curve= 0 ,0
Exp/Cntr=0.3,0.1

Type RM Length L Ch R = 1 ,8884    ,224,402,479
BEGIN DESCRIPTION:
This cross section corresponds to cross section 8884 of the non-georeferenced CDC model which was the source of this model.
END DESCRIPTION:
XS GIS Cut Line= 6
  2453590.094167 6978074.2020732 2453862.8373881 6976928.0836305
 2453959.7135067 6976458.6072072 2454301.0153175 6975282.6807533
 2455177.3711763 6972243.7527761 2454974.6766998  6971456.820951
#Sta/Elev= 30
       0  451.47   35.51  455.94 1619.87  428.15 1650.75  425.11 1683.29  409.11
  1806.6  427.51 2332.93  426.55 2678.33  420.96 2726.08  409.33  2768.2  419.45
 2794.51     414 3252.14  413.95 4965.23  415.78 5154.32  414.42 5171.16  409.13
 5236.28  416.82 5375.99  410.98 5400.26  421.14 5447.12  411.88 5493.85  416.25
 6107.99  420.37  6126.2  414.44 6181.13     389 6201.13  388.44 6261.13     394
 6343.02  412.74 6459.48  406.92 6507.06  413.52  6717.6   414.6 6833.56  439.37
#Mann= 7 ,-1,0
       0    .085       0 2794.51    .065       0 3252.14     .07       0
 5493.85     .06       0  6126.2    .039       0 6343.02    .055       0
  6717.6     .03       0
#XS Ineff= 5 ,-1
       0    2200     450    2200    3025     417    3025    3990     450
    3990  6126.2     417 6343.02 6833.56  412.74
Permanent Ineff=
       F       F       F       F       F
Bank Sta=6126.2,6343.02
XS Rating Curve= 0 ,0
Exp/Cntr=0.3,0.1

Type RM Length L Ch R = 1 ,8469    ,108,122,146
BEGIN DESCRIPTION:
This cross section corresponds to cross section 8469 of the non-georeferenced CDC model which was the source of this model.
END DESCRIPTION:
XS GIS Cut Line= 3
   2453615.43073 6978075.6925557 2454058.1490053 6976939.7771767
 2455591.3073563 6971586.4571746
#Sta/Elev= 30
       0  458.59  218.64   447.9 1602.62  428.55    1648   412.9  1704.4  409.27
 1740.56  414.18 1766.97  426.48 1908.12  427.54 2382.99  426.69 2746.47  420.31
 2792.23  408.47 2830.96  417.93 2866.02  411.57 3022.16   414.7 3996.56  411.53
 4090.06  420.17 4429.96  412.31 4887.92  419.77 5102.22  418.07 5133.41  409.21
 5159.88  419.21 5383.61  419.77 5453.88  409.91 5532.59   417.3 6286.71  417.83
 6421.13  388.09 6508.89  398.78 6535.11  417.04 6711.22  414.45 6807.84  438.78
#Mann= 7 ,-1,0
       0    .085       0 2866.02    .065       0 3022.16     .07       0
 5532.59     .06       0 6286.71    .039       0 6535.11    .055       0
 6711.22     .03       0
#XS Ineff= 5 ,-1
       0    2000     450    2000    3080  417.83    3080    3900     450
    3900 6286.71  417.83 6535.11 6807.84  417.04
Permanent Ineff=
       F       F       F       F       F
Bank Sta=6286.71,6535.11
XS Rating Curve= 0 ,0
Exp/Cntr=0.3,0.1

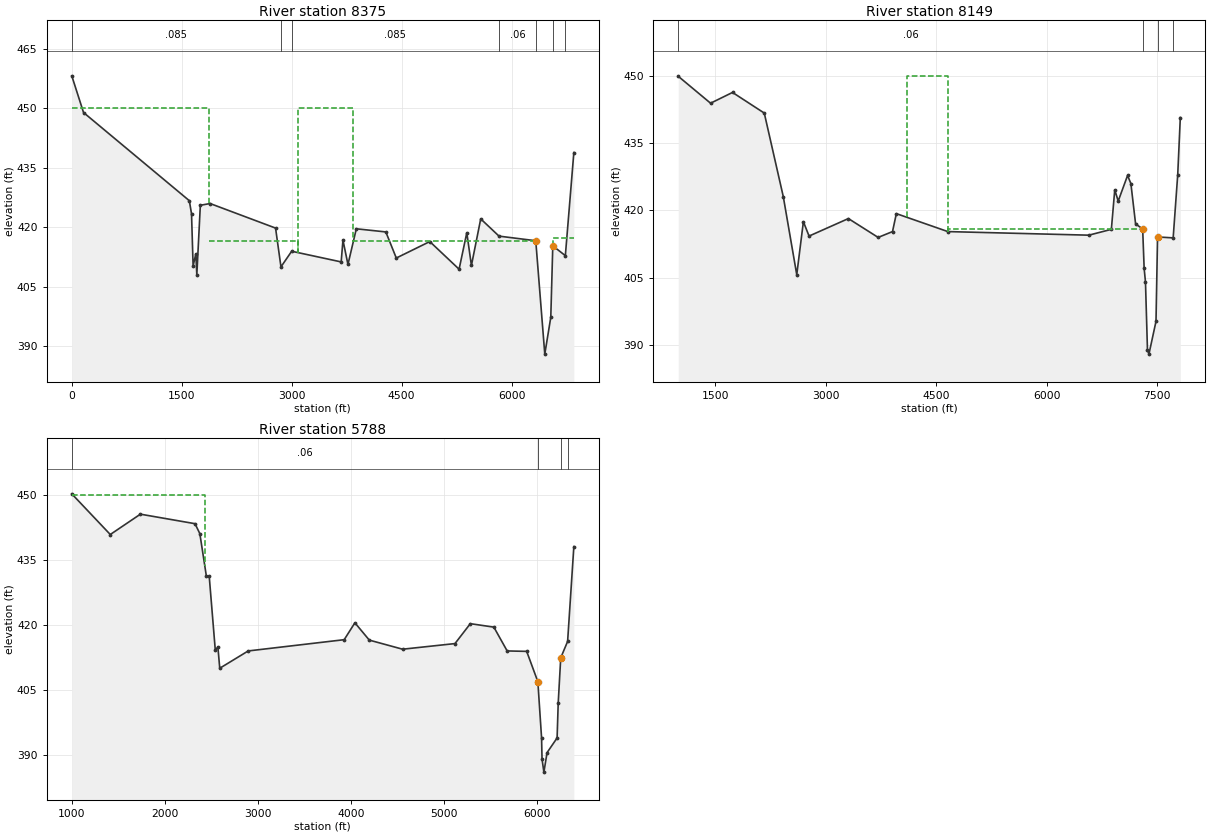
Type RM Length L Ch R = 1 ,8375    ,223,219,233
BEGIN DESCRIPTION:
This cross section corresponds to cross section 8375 of the non-georeferenced CDC model which was the source of this model.
END DESCRIPTION:
XS GIS Cut Line= 6
   2453632.43693  6978080.906128 2454067.2198533 6977168.4679922
 2454570.4179939 6975495.1839372  2455497.999144 6972263.8049013
 2455631.3771581 6971887.9231072 2455772.8240537 6971592.1681212
#Sta/Elev= 30
       0  458.17   160.3  448.92 1603.26  426.69 1633.46  423.39 1655.12  410.24
 1692.37   413.3 1705.81     408  1753.7  425.53 1887.04  425.97 2779.81  419.78
 2853.47     410 2999.54  413.94 3674.74  411.25 3699.04  416.74 3767.15  410.61
 3881.34   419.6 4283.86  418.81 4426.48  412.23 4883.62  416.38 5283.17  409.41
 5388.22  418.61 5451.24  410.35 5578.19   422.1 5827.93  417.75 6328.82  416.59
    6452     388 6533.87  397.29  6561.2   415.3  6732.5  412.83 6848.38  438.82
#Mann= 7 ,-1,0
       0    .085       0 2853.47    .065       0 2999.54    .085       0
 5827.93     .06       0 6328.82    .039       0  6561.2    .055       0
  6732.5     .03       0
#XS Ineff= 5 ,-1
       0    1870     450    1870    3090  416.59    3090    3840     450
    3840 6328.82  416.59  6561.2 6848.38  417.16
Permanent Ineff=
       F       F       F       F       F
Bank Sta=6328.82,6561.2
XS Rating Curve= 0 ,0
Exp/Cntr=0.3,0.1

Type RM Length L Ch R = 1 ,8149    ,1200,2361,2600
BEGIN DESCRIPTION:
This cross section corresponds to cross section 8149 of the non-georeferenced CDC model which was the source of this model.
---------------------------------------------------------------------
CDC IRV030300-1 Farrow Addition
CDC IRV081211-1 Trailer Storage Site
Cross-section 8149 - 9520
Located in LOB.
---------------------------------------------------------------------
END DESCRIPTION:
XS GIS Cut Line= 6
  2453864.572948 6978094.9940263 2454264.8490512 6977247.2201313
 2454816.5480791 6975307.1800482 2455604.6888912 6972676.0009273
 2455841.1310037 6971948.4859782  2455998.194994 6971627.8150316
#Sta/Elev= 30
    1000   449.9    1439   443.9    1737   446.3    2168   441.7    2426   423.1
    2609   405.7    2699   417.5    2776   414.3    3310   418.2    3714     414
    3909   415.3    3961   419.3    4660   415.3    6574   414.5    6880   415.8
    6926   424.6    6973   422.1    7100   427.8    7145     426    7209     417
    7305   415.9    7325   407.1    7343   404.1    7370     389    7390     388
    7486   395.3    7507   414.1    7719   413.9    7781     428    7816   440.7
#Mann= 4 ,-1,0
    1000     .06       0    7305    .039       0    7507    .055       0
    7719     .03       0
#XS Ineff= 4 ,-1
    1000    4100   415.9    4100    4660     450    4660    7305   415.9
    7507    7816   414.1
Permanent Ineff=
       F       F       F       F
Bank Sta=7305,7507
XS Rating Curve= 0 ,0
Exp/Cntr=0.3,0.1

Type RM Length L Ch R = 1 ,5788    ,860,1117,1050
BEGIN DESCRIPTION:
This cross section corresponds to cross section 5788 of the non-georeferenced CDC model which was the source of this model.
Cross-section WF006.  Effective flow limit set at sta 2430 in LOB.  Twin Wells golf course in LOB.  Delaware Creek removed from conveyance in LOB.
Effective flow limit set at West Levee in ROB.
Channel data from 1975 USACOE field survey.
END DESCRIPTION:
XS GIS Cut Line= 6
  2453934.336917 6978081.8500237 2454553.8652055 6977131.8378162
 2455276.6934843 6976023.5050591 2455896.2992004 6975073.5190982
 2456515.9410057 6974123.5449482 2457167.6270383 6973927.6129254
#Sta/Elev= 30
    1000   450.3    1414   440.9    1738   445.6    2325   443.4    2377   441.1
    2447   431.3    2478   431.2    2543   414.2    2571   414.9    2591     410
    2897     414    3929   416.6    4044   420.5    4199   416.5    4557   414.4
    5120   415.7    5285   420.3    5538   419.5    5681     414    5891   413.9
    6011   406.9    6051   393.9    6056     389    6076     386    6110   390.5
    6218   393.9    6230     402    6257   412.4    6331   416.2    6398   438.1
#Mann= 4 ,-1,0
    1000     .06       0    6011    .039       0    6257    .055       0
    6331     .03       0
#XS Ineff= 2 , 0
            2430     450
Permanent Ineff=
       F       F
Bank Sta=6011,6257
XS Rating Curve= 0 ,0
Exp/Cntr=0.3,0.1