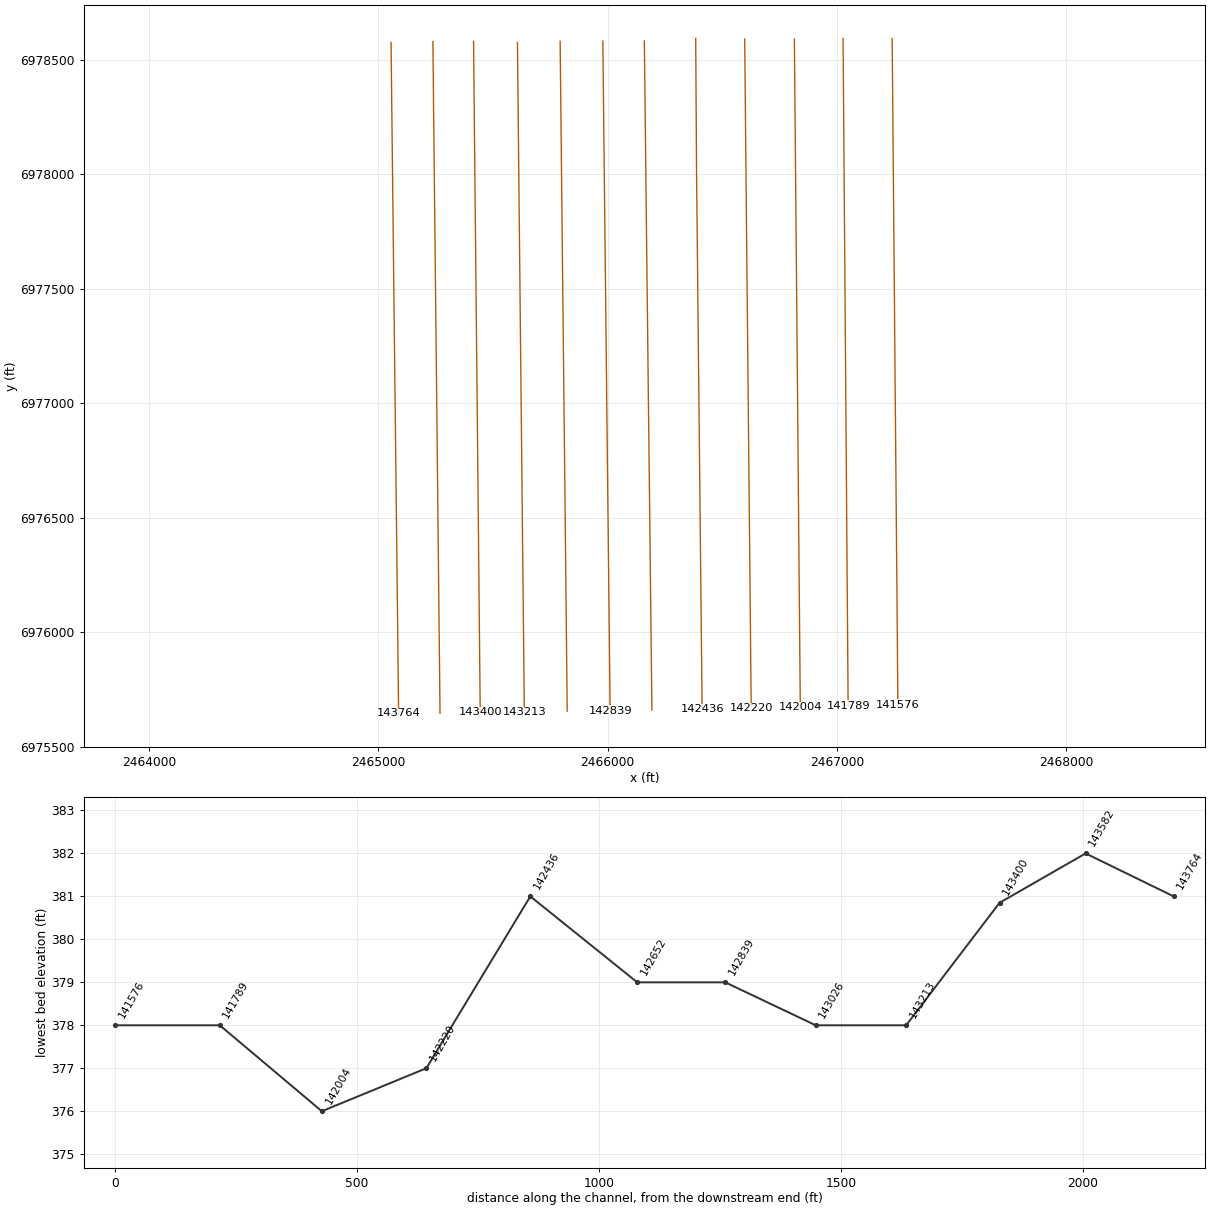
HEC-RAS study CDC_Consolidated_Model.prj: Upper Trinity CDC Consolidated Model

--- CDC_Consolidated_Model.g12 (geometry) --- (continued)

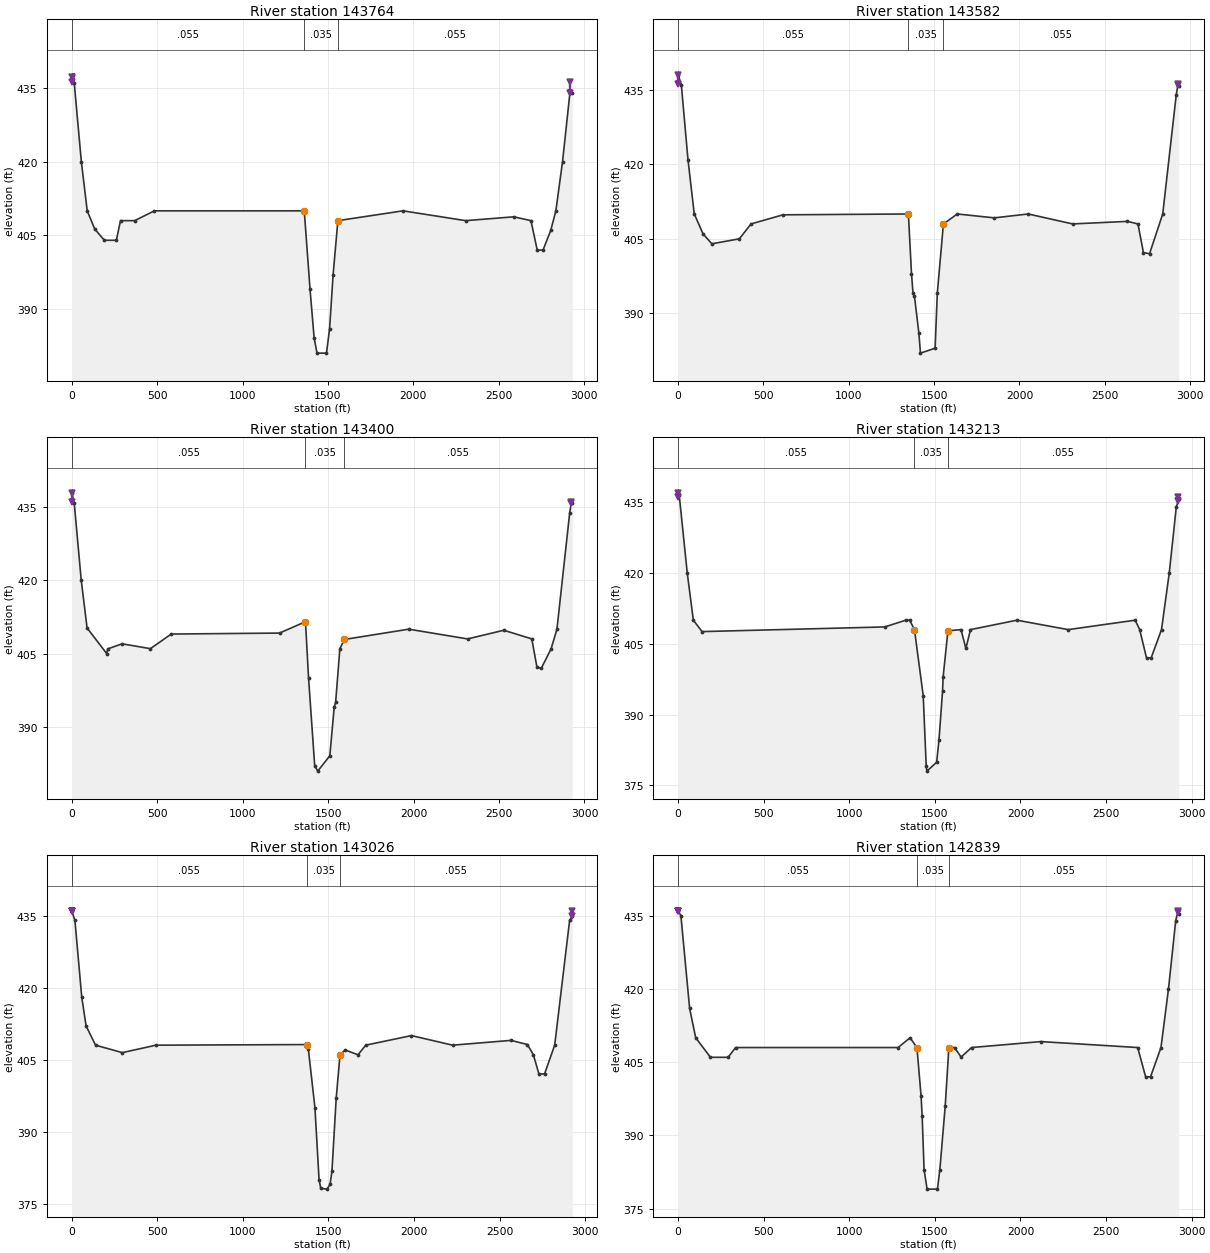
Type RM Length L Ch R = 1 ,143764  ,182,182,182
BEGIN DESCRIPTION:
This cross section corresponds to cross section 143764 of the non-georeferenced CDC model which was the source of this model.
END DESCRIPTION:
XS GIS Cut Line= 2
2465054.850434426978575.97665888  2465087.8644766975646.17280722
#Sta/Elev= 30
       0  437.37    7.15  437.72   15.05     436   56.51     420   90.85     410
  134.88  406.29  191.21     404  261.44     404  285.67     408  368.66     408
  483.95     410 1361.06     410 1394.92     394 1418.93   384.1 1435.69     381
 1491.15     381 1509.39     386 1529.94     397 1557.88     408 1938.89     410
 2305.84     408 2587.43  408.78 2687.91     408  2724.6     402 2758.42     402
 2803.58     406 2833.55     410 2872.68     420 2915.57  433.95 2929.99     434
#Mann= 3 ,0,0
       0    .055       0 1361.06    .035       0 1557.88    .055       0
Levee=-1,0,436.16,-1,2916,436.16,,
#XS Ineff= 2 , 0
         1361.06     410 1557.88             408
Permanent Ineff=
       F       F
Bank Sta=1361.06,1557.88
XS Rating Curve= 0 ,0
Exp/Cntr=0.3,0.1

Type RM Length L Ch R = 1 ,143582  ,178,178,178
BEGIN DESCRIPTION:
This cross section corresponds to cross section 143582 of the non-georeferenced CDC model which was the source of this model.
END DESCRIPTION:
XS GIS Cut Line= 2
2465237.374675666978580.121007552465268.502238096975646.53599547
#Sta/Elev= 30
       0     438   18.56     436   57.52  420.93   94.13  410.04   145.7     406
  197.39     404  358.41     405   427.3     408  614.08  409.83 1349.23     410
 1367.34     398 1376.33     394 1384.81  393.41 1410.61  386.01 1419.84     382
 1505.82  382.99 1518.48     394  1554.3  407.97 1635.29     410 1852.93  409.22
 2051.17     410 2311.47     408 2632.81  408.51 2694.55     408 2726.44  402.24
 2762.36     402 2839.57     410 2918.91     434 2928.71  435.98 2933.75  435.78
#Mann= 3 ,0,0
       0    .055       0 1349.23    .035       0  1554.3    .055       0
Levee=-1,0,436.11,-1,2929,436.11,,
#XS Ineff= 2 , 0
         1349.23     410  1554.3          407.97
Permanent Ineff=
       F       F
Bank Sta=1349.23,1554.3
XS Rating Curve= 0 ,0
Exp/Cntr=0.3,0.1

Type RM Length L Ch R = 1 ,143400  ,193,193,193
BEGIN DESCRIPTION:
This cross section corresponds to cross section 143400 of the non-georeferenced CDC model which was the source of this model.
END DESCRIPTION:
XS GIS Cut Line= 2
2465414.819202666978580.362476892465443.876231166975651.63670705
#Sta/Elev= 30
       0     438    14.5     436   55.58  420.13   89.98  410.24  204.76     405
  211.18  405.95  294.47     407  460.42     406  582.48     409  1216.1   409.2
 1367.81  411.54 1385.64     400  1421.6     382 1439.24  380.85 1510.12     384
 1535.71  393.97 1544.22     395 1568.82     406 1595.62  407.89 1972.11     410
 2316.11     408 2528.08  409.78 2691.85     408 2721.91   402.2  2747.6     402
 2804.55  405.95 2838.91     410 2913.12  433.79 2922.99     436 2928.87     436
#Mann= 3 ,0,0
       0    .055       0 1367.81    .035       0 1595.62    .055       0
Levee=-1,0,436.07,-1,2923,436.07,,
#XS Ineff= 2 , 0
         1367.81  411.54 1595.62          407.89
Permanent Ineff=
       F       F
Bank Sta=1367.81,1595.62
XS Rating Curve= 0 ,0
Exp/Cntr=0.3,0.1

Type RM Length L Ch R = 1 ,143213  ,187,187,187
BEGIN DESCRIPTION:
This cross section corresponds to cross section 143213 of the non-georeferenced CDC model which was the source of this model.
END DESCRIPTION:
XS GIS Cut Line= 2
2465606.275512676978575.489783212465636.285295166975650.50350721
#Sta/Elev= 30
       0     437    6.18  436.52   53.15     420   88.67     410  139.83  407.58
 1207.42  408.57 1329.51     410  1352.6     410 1380.65     408 1431.84     394
 1449.46     379 1453.63     378 1510.42   379.9 1524.11  384.68 1544.85     395
 1548.17  397.96 1576.15  407.75 1652.71     408 1681.12     404 1707.99     408
 1979.21     410 2279.23     408 2670.28     410 2696.71     408 2736.51     402
 2763.55     402 2824.14     408 2869.44     420  2910.5     434 2925.14  435.65
#Mann= 3 ,0,0
       0    .055       0 1380.65    .035       0 1576.15    .055       0
Levee=-1,0,436.02,-1,2922,436.02,,
#XS Ineff= 2 , 0
         1380.65     408 1576.15          407.75
Permanent Ineff=
       F       F
Bank Sta=1380.65,1576.15
XS Rating Curve= 0 ,0
Exp/Cntr=0.3,0.1

Type RM Length L Ch R = 1 ,143026  ,187,187,187
BEGIN DESCRIPTION:
This cross section corresponds to cross section 143026 of the non-georeferenced CDC model which was the source of this model.
END DESCRIPTION:
XS GIS Cut Line= 2
2465792.505455176978580.898893132465823.413529846975655.92213155
#Sta/Elev= 30
       0     436   18.85     434   58.75     418   84.18     412  139.52     408
  295.77  406.45  492.47     408 1374.61  408.13 1382.55  407.22 1421.18     395
 1445.32     380 1455.19  378.17 1491.35     378 1509.51  378.97 1520.56  381.71
 1545.42  396.94 1567.74     406 1598.14     407 1672.91     406 1718.06     408
 1985.33     410 2225.52     408 2567.05     409 2662.38  408.14 2697.67     406
 2729.97     402 2762.75     402  2822.1     408  2909.3     434 2925.14  434.85
#Mann= 3 ,0,0
       0    .055       0 1374.61    .035       0 1567.74    .055       0
Levee=-1,0,435.98,-1,2925,435.98,,
#XS Ineff= 2 , 0
         1374.61  408.13 1567.74             406
Permanent Ineff=
       F       F
Bank Sta=1374.61,1567.74
XS Rating Curve= 0 ,0
Exp/Cntr=0.3,0.1

Type RM Length L Ch R = 1 ,142839  ,182,182,182
BEGIN DESCRIPTION:
This cross section corresponds to cross section 142839 of the non-georeferenced CDC model which was the source of this model.
END DESCRIPTION:
XS GIS Cut Line= 2
2465978.775423826978582.307682962466010.582446846975657.34076388
#Sta/Elev= 30
       0     436   16.06     435   66.98     416   102.5     410  188.74     406
  291.88     406  335.46     408  1285.2     408 1354.88     410 1395.25     408
 1419.44     398  1425.6     394 1436.88     383 1454.51     379 1514.92     379
 1529.05     383 1560.34     396 1581.72     408 1614.88     408 1653.08  406.05
 1714.29     408 2118.87  409.22 2684.87     408 2731.39     402 2759.88     402
 2821.03     408 2864.91     420 2907.18     434 2920.48  435.88 2925.14  435.39
#Mann= 3 ,0,0
       0    .055       0 1395.25    .035       0 1581.72    .055       0
Levee=-1,0,435.94,-1,2921,435.94,,
#XS Ineff= 2 , 0
         1395.25     408 1581.72             408
Permanent Ineff=
       F       F
Bank Sta=1395.25,1581.72
XS Rating Curve= 0 ,0
Exp/Cntr=0.3,0.1

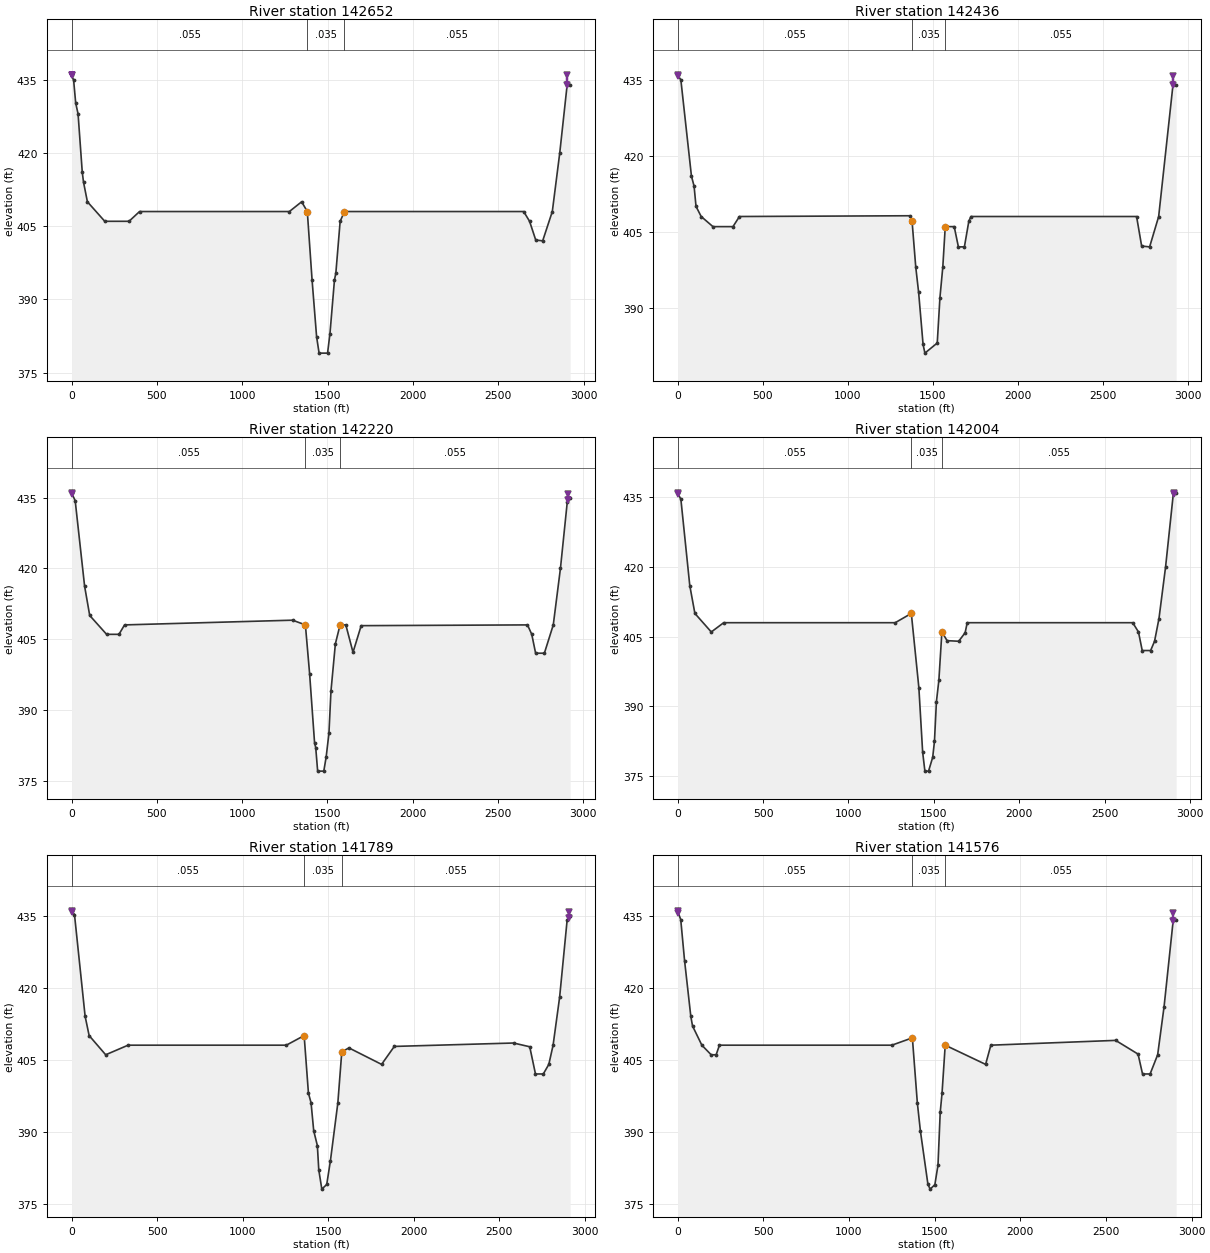
Type RM Length L Ch R = 1 ,142652  ,220,221,220
BEGIN DESCRIPTION:
This cross section corresponds to cross section 142652 of the non-georeferenced CDC model which was the source of this model.
END DESCRIPTION:
XS GIS Cut Line= 2
2466159.834444916978582.615425142466192.884575676975661.38275056
#Sta/Elev= 30
       0     436    12.1  434.84   24.05  430.22   37.92     428   62.46  416.07
   69.95     414   92.59     410   194.4     406  336.44     406   398.2     408
 1276.09     408 1347.95     410 1381.16     408 1409.05     394  1435.6  382.36
 1450.19     379 1499.88     379 1513.93     383 1540.35     394 1548.36  395.37
 1573.61     406 1598.81     408 2649.01     408 2683.55     406 2719.71  402.16
 2760.32     402 2816.78     408 2860.34     420 2903.91     434 2921.42     434
#Mann= 3 ,0,0
       0    .055       0 1381.16    .035       0 1598.81    .055       0
Levee=-1,0,435.89,-1,2904,435.89,,
#XS Ineff= 2 , 0
         1381.16     408 1598.81             408
Permanent Ineff=
       F       F
Bank Sta=1381.16,1598.81
XS Rating Curve= 0 ,0
Exp/Cntr=0.3,0.1

Type RM Length L Ch R = 1 ,142436  ,214,215,214
BEGIN DESCRIPTION:
This cross section corresponds to cross section 142436 of the non-georeferenced CDC model which was the source of this model.
END DESCRIPTION:
XS GIS Cut Line= 3
2466383.967198766978593.199721552466387.703083666978001.33607589
2466411.909728176975663.65702422
#Sta/Elev= 30
       0     436   19.41     435   81.53     416   97.06     414  108.49     410
  138.79     408   207.9     406  325.56     406  363.72     408  1365.3  408.15
 1377.69  407.19 1399.66     398 1416.56     393 1442.62  382.74 1453.37     381
 1525.97     383 1541.72  391.97 1558.57     398 1572.95     406 1625.65     406
  1650.2     402  1685.5     402  1711.6  407.09 1724.25     408 2697.25     408
    2727  402.16 2773.95     402 2827.02     408 2911.13     434 2929.68     434
#Mann= 3 ,0,0
       0    .055       0 1377.69    .035       0 1572.95    .055       0
Levee=-1,0,435.84,-1,2911,435.84,,
#XS Ineff= 2 , 0
         1377.69  407.19 1572.95             406
Permanent Ineff=
       F       F
Bank Sta=1377.69,1572.95
XS Rating Curve= 0 ,0
Exp/Cntr=0.3,0.1

Type RM Length L Ch R = 1 ,142220  ,215,216,215
BEGIN DESCRIPTION:
This cross section corresponds to cross section 142220 of the non-georeferenced CDC model which was the source of this model.
END DESCRIPTION:
XS GIS Cut Line= 2
2466597.649186076978591.059305882466626.075966516975668.03759289
#Sta/Elev= 30
       0     436   21.13  434.32   76.22  416.22   106.2     410  205.19     406
  277.68     406  310.54     408 1295.65     409 1370.78     408 1395.42  397.68
 1424.57     383 1431.28     382 1442.66     377 1478.65     377 1492.53     380
 1508.79     385 1520.76     394  1546.6     404 1574.08     408 1607.82     408
 1649.93  402.19 1697.82  407.84 2672.93     408 2697.93     406 2720.57     402
 2771.95     402  2824.1     408 2866.19     420 2905.82  433.95 2923.16     435
#Mann= 3 ,0,0
       0    .055       0 1370.78    .035       0 1574.08    .055       0
Levee=-1,0,435.78,-1,2913,435.78,,
#XS Ineff= 2 , 0
         1370.78     408 1574.08             408
Permanent Ineff=
       F       F
Bank Sta=1370.78,1574.08
XS Rating Curve= 0 ,0
Exp/Cntr=0.3,0.1

Type RM Length L Ch R = 1 ,142004  ,211,211,211
BEGIN DESCRIPTION:
This cross section corresponds to cross section 142004 of the non-georeferenced CDC model which was the source of this model.
END DESCRIPTION:
XS GIS Cut Line= 2
2466814.435497916978590.682338132466840.237939756975673.41651914
#Sta/Elev= 30
       0     436   19.47   434.6   71.53     416  101.38     410  197.33     406
  269.96     408 1273.56     408 1367.82     410 1411.93     394 1434.12  380.09
 1447.28     376 1468.64     376 1492.96  378.99  1503.2  382.41 1514.74     391
 1529.04  395.58 1546.68     406 1577.15  404.13 1645.03     404 1682.84  405.85
 1694.85     408 2663.41     408 2697.02     406 2718.95     402 2768.07     402
 2791.06     404 2816.92  408.88 2855.53     420  2901.5     436 2917.38     436
#Mann= 3 ,0,0
       0    .055       0 1367.82    .035       0 1546.68    .055       0
Levee=-1,0,435.73,-1,2902,435.73,,
#XS Ineff= 2 , 0
         1367.82     410 1546.68             406
Permanent Ineff=
       F       F
Bank Sta=1367.82,1546.68
XS Rating Curve= 0 ,0
Exp/Cntr=0.3,0.1

Type RM Length L Ch R = 1 ,141789  ,215,216,215
BEGIN DESCRIPTION:
This cross section corresponds to cross section 141789 of the non-georeferenced CDC model which was the source of this model.
END DESCRIPTION:
XS GIS Cut Line= 2
2467026.870112426978594.102934972467048.915343916975678.89649504
#Sta/Elev= 30
       0     436   16.92  435.23   79.07  414.02  102.58     410  199.39     406
   330.3     408 1255.62     408 1359.76     410 1384.89     398 1400.19     396
 1415.71  390.16 1437.04  387.08 1445.35     382 1463.14     378 1491.83  378.97
 1513.44  383.91  1556.9  395.99 1579.87  406.62 1621.79  407.43  1812.6     404
 1887.01  407.74 2584.32  408.45 2678.82  407.67 2712.43     402 2758.17     402
 2790.45     404 2815.45     408 2853.64     418 2897.33     434 2915.29     435
#Mann= 3 ,0,0
       0    .055       0 1359.76    .035       0 1579.87    .055       0
Levee=-1,0,435.68,-1,2907,435.68,,
#XS Ineff= 2 , 0
         1359.76     410 1579.87          406.62
Permanent Ineff=
       F       F
Bank Sta=1359.76,1579.87
XS Rating Curve= 0 ,0
Exp/Cntr=0.3,0.1

Type RM Length L Ch R = 1 ,141576  ,211,211,211
BEGIN DESCRIPTION:
This cross section corresponds to cross section 141576 of the non-georeferenced CDC model which was the source of this model.
END DESCRIPTION:
XS GIS Cut Line= 2
2467241.035038416978592.463174462467266.061891266975682.98080447
#Sta/Elev= 30
       0     436   18.58  434.17   40.95   425.6   77.34     414   87.41     412
  141.75     408  196.12     406  225.18     406  244.46     408 1250.74     408
 1370.36  409.53 1399.26     396 1417.22  390.09 1461.08     379 1474.05     378
 1501.53  378.92  1519.8     383 1532.73  393.97 1543.41  397.97 1561.96     408
 1797.72     404 1828.28     408 2556.51     409 2687.46  406.14  2713.5     402
 2757.65     402 2801.73     406 2839.13     416  2892.4     434 2909.59     434
#Mann= 3 ,0,0
       0    .055       0 1370.36    .035       0 1561.96    .055       0
Levee=-1,0,435.63,-1,2892,435.63,,
#XS Ineff= 2 , 0
         1370.36  409.53 1561.96             408
Permanent Ineff=
       F       F
Bank Sta=1370.36,1561.96
XS Rating Curve= 0 ,0
Exp/Cntr=0.3,0.1