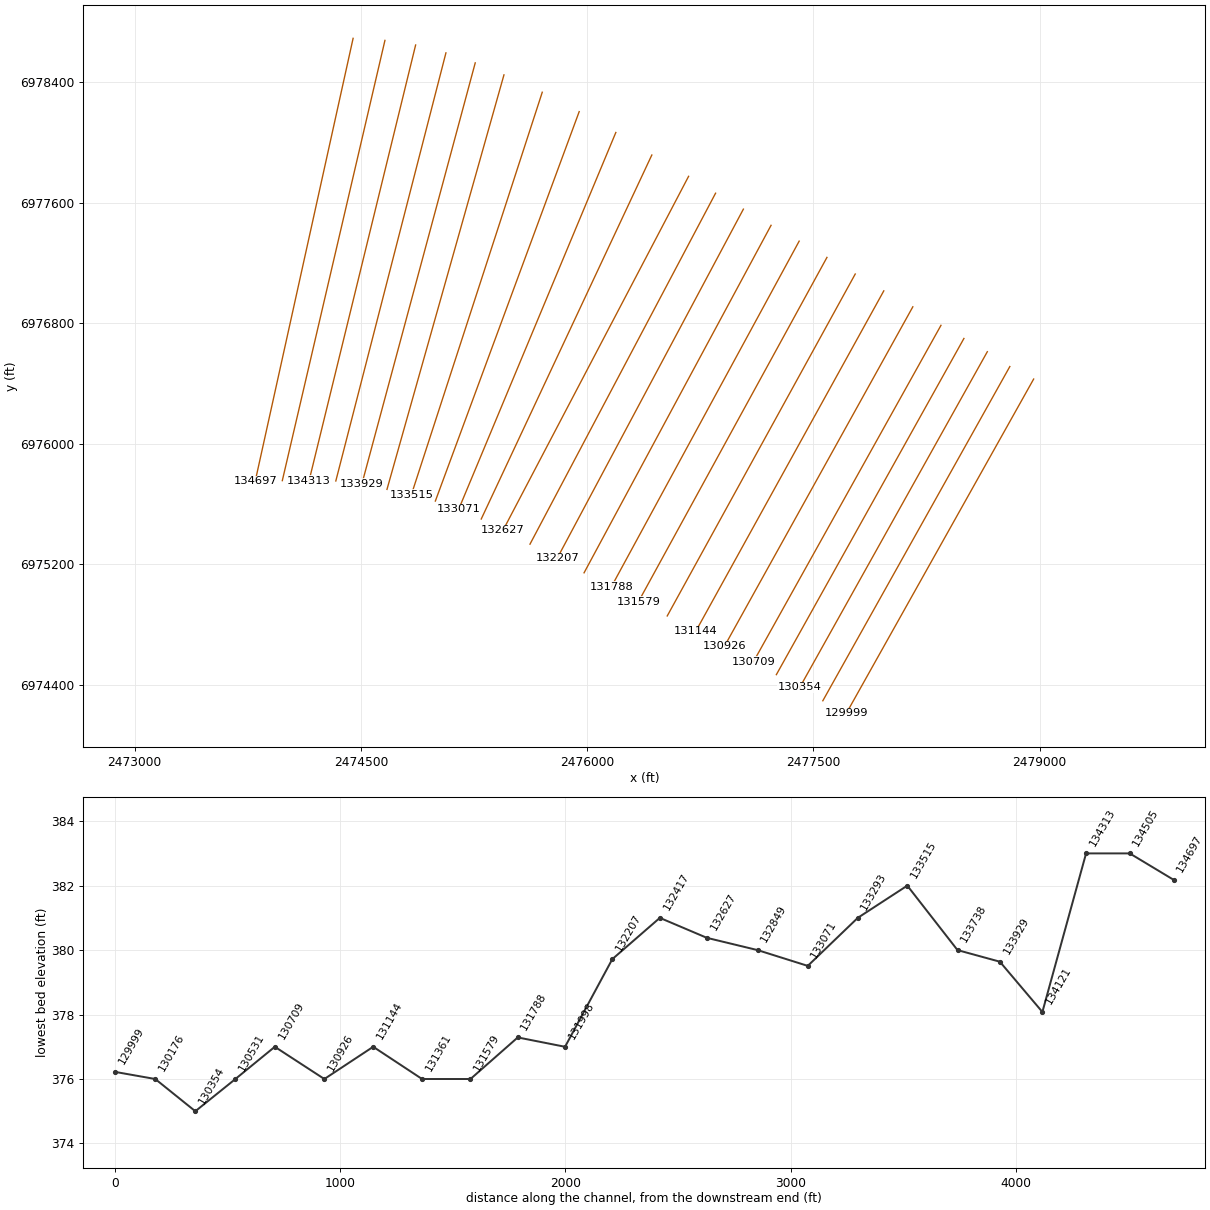
HEC-RAS study CDC_Consolidated_Model.prj: Upper Trinity CDC Consolidated Model

--- CDC_Consolidated_Model.g12 (geometry) --- (continued)

Type RM Length L Ch R = 3 ,134826.5,,,
BEGIN DESCRIPTION:
Hampton/Inwood Road
------------------------------------------------------------------
CDC DAL122205-01 Hampton/Inwood Bridge
-----------------------------------------------------------------
END DESCRIPTION:
Node Name=Hampton Road
Bridge Culvert--1,0,-1,-1, 0
Deck Dist Width WeirC Skew NumUp NumDn MinLoCord MaxHiCord MaxSubmerge Is_Ogee
1,112,2.6,0, 30, 30, , , 0.95, 0, ,,,
       0     100     210     320     430     540     640     740     840     940
    1040    1140    1240    1240    1415    1625    1800    1800    1900    2000
    2100    2200    2300    2400    2510    2620    2740    2840    2950    3060
   448.2   450.8     453   454.6   455.7   456.9     458     459   460.1   461.1
   461.9   462.5     463     463   463.1   463.1     463     463   462.5   461.8
     461     460   458.9   457.9   456.7   455.5   454.2   452.6   450.2   447.1
   439.4     442   444.2   445.8   446.9   448.1   449.2   450.2   451.3   452.3
   453.1   453.7   454.2   452.7   452.8   452.8   452.7   454.2   453.7     453
   452.2   451.2   450.1   449.1   447.9   446.7   445.4   443.8   441.4   438.3
       0     100     210     320     430     540     640     740     840     940
    1040    1140    1240    1240    1415    1625    1800    1800    1900    2000
    2100    2200    2300    2400    2510    2620    2740    2840    2950    3060
   448.2   450.8     453   454.6   455.7   456.9     458     459   460.1   461.1
   461.9   462.5     463     463   463.1   463.1     463     463   462.5   461.8
     461     460   458.9   457.9   456.7   455.5   454.2   452.6   450.2   447.1
   439.4     442   444.2   445.8   446.9   448.1   449.2   450.2   451.3   452.3
   453.1   453.7   454.2   452.7   452.8   452.8   452.7   454.2   453.7     453
   452.2   451.2   450.1   449.1   447.9   446.7   445.4   443.8   441.4   438.3
Pier Skew, UpSta & Num, DnSta & Num=  ,100, 2 ,100, 2 , 0 , 0 , 0 ,,
       3       3
       0     445
       3       3
       0     445
Pier Skew, UpSta & Num, DnSta & Num=  ,210, 4 ,210, 4 , 0 , 0 , 0 ,,
     3.5     3.5       3       3
       0   431.3   431.5     445
     3.5     3.5       3       3
       0   431.3   431.5     445
Pier Skew, UpSta & Num, DnSta & Num=  ,320, 4 ,320, 4 , 0 , 0 , 0 ,,
     3.5     3.5       3       3
       0   432.7   432.7     450
     3.5     3.5       3       3
       0   432.7   432.7     450
Pier Skew, UpSta & Num, DnSta & Num=  ,430, 4 ,430, 4 , 0 , 0 , 0 ,,
     3.5     3.5       3       3
       0   433.9   433.9     450
     3.5     3.5       3       3
       0   433.9   433.9     450
Pier Skew, UpSta & Num, DnSta & Num=  ,540, 4 ,540, 4 , 0 , 0 , 0 ,,
       4       4       3       3
       0   435.1   435.1     450
       4       4       3       3
       0   435.1   435.1     450
Pier Skew, UpSta & Num, DnSta & Num=  ,640, 4 ,640, 4 , 0 , 0 , 0 ,,
       4       4       3       3
       0   436.1   436.1     450
       4       4       3       3
       0   436.1   436.1     450
Pier Skew, UpSta & Num, DnSta & Num=  ,740, 4 ,740, 4 , 0 , 0 , 0 ,,
       4       4       3       3
       0   437.2   437.2     452
       4       4       3       3
       0   437.2   437.2     452
Pier Skew, UpSta & Num, DnSta & Num=  ,840, 4 ,840, 4 , 0 , 0 , 0 ,,
       4       4       3       3
       0   438.3   438.3     452
       4       4       3       3
       0   438.3   438.3     452
Pier Skew, UpSta & Num, DnSta & Num=  ,940, 4 ,940, 4 , 0 , 0 , 0 ,,
       4       4       3       3
       0   439.2   439.2     455
       4       4       3       3
       0   439.2   439.2     455
Pier Skew, UpSta & Num, DnSta & Num=  ,1040, 4 ,1040, 4 , 0 , 0 , 0 ,,
       4       4       3       3
       0     440     440     455
       4       4       3       3
       0     440     440     455
Pier Skew, UpSta & Num, DnSta & Num=  ,1140, 4 ,1140, 4 , 0 , 0 , 0 ,,
       4       4       3       3
       0   440.7   440.7     455
       4       4       3       3
       0   440.7   440.7     455
Pier Skew, UpSta & Num, DnSta & Num=  ,1240, 2 ,1240, 2 , 0 , 0 , 0 ,,
       4       4
       0     455
       4       4
       0     455
Pier Skew, UpSta & Num, DnSta & Num=  ,1415, 2 ,1415, 2 , 0 , 0 , 0 ,,
       4       4
       0     455
       4       4
       0     455
Pier Skew, UpSta & Num, DnSta & Num=  ,1625, 2 ,1625, 2 , 0 , 0 , 0 ,,
       4       4
       0     455
       4       4
       0     455
Pier Skew, UpSta & Num, DnSta & Num=  ,1800, 2 ,1800, 2 , 0 , 0 , 0 ,,
       4       4
       0     455
       4       4
       0     455
Pier Skew, UpSta & Num, DnSta & Num=  ,1900, 4 ,1900, 4 , 0 , 0 , 0 ,,
       4       4       3       3
       0   440.6   440.6     455
       4       4       3       3
       0   440.6   440.6     455
Pier Skew, UpSta & Num, DnSta & Num=  ,2000, 4 ,2000, 4 , 0 , 0 , 0 ,,
       4       4       3       3
       0   439.9   439.9     455
       4       4       3       3
       0   439.9   439.9     455
Pier Skew, UpSta & Num, DnSta & Num=  ,2100, 4 ,2100, 4 , 0 , 0 , 0 ,,
       4       4       3       3
       0   439.1   439.1     455
       4       4       3       3
       0   439.1   439.1     455
Pier Skew, UpSta & Num, DnSta & Num=  ,2200, 4 ,2200, 4 , 0 , 0 , 0 ,,
       4       4       3       3
       0   438.1   438.1     455
       4       4       3       3
       0   438.1   438.1     455
Pier Skew, UpSta & Num, DnSta & Num=  ,2300, 4 ,2300, 4 , 0 , 0 , 0 ,,
     3.5     3.5       3       3
       0   437.1   437.1     455
     3.5     3.5       3       3
       0   437.1   437.1     455
Pier Skew, UpSta & Num, DnSta & Num=  ,2400, 4 ,2400, 4 , 0 , 0 , 0 ,,
     3.5     3.5       3       3
       0     436     436     455
     3.5     3.5       3       3
       0     436     436     455
Pier Skew, UpSta & Num, DnSta & Num=  ,2510, 4 ,2510, 4 , 0 , 0 , 0 ,,
     3.5     3.5       3       3
       0   434.8   434.8     455
     3.5     3.5       3       3
       0   434.8   434.8     455
Pier Skew, UpSta & Num, DnSta & Num=  ,2620, 4 ,2620, 4 , 0 , 0 , 0 ,,
     3.5     3.5       3       3
       0   433.7   433.7     455
     3.5     3.5       3       3
       0   433.7   433.7     455
Pier Skew, UpSta & Num, DnSta & Num=  ,2740, 4 ,2740, 4 , 0 , 0 , 0 ,,
     3.5     3.5       3       3
       0   432.3   432.3     453
     3.5     3.5       3       3
       0   432.3   432.3     453
Pier Skew, UpSta & Num, DnSta & Num=  ,2840, 4 ,2840, 4 , 0 , 0 , 0 ,,
     3.5     3.5       3       3
       0   430.8   430.8     450
     3.5     3.5       3       3
       0   430.8   430.8     450
Pier Skew, UpSta & Num, DnSta & Num=  ,2950, 2 ,2950, 2 , 0 , 0 , 0 ,,
       3       3
       0     445
       3       3
       0     445
BR Coef= 1 , 0 , 0 ,1.05, 0 ,,,0.8,-1,0.5,1,
WSPro=,,,, 1 ,,,, 0 ,,,, 0 ,,,,-1 ,-1 ,-1 , 0 , 0 , 0 , 0 , 0
BC Design=,, 0 ,, 0 ,,,,,,
BC HTab HWMax=435
BC Use User HTab Curves=0
BC User HTab FreeFlow(D)= 0

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
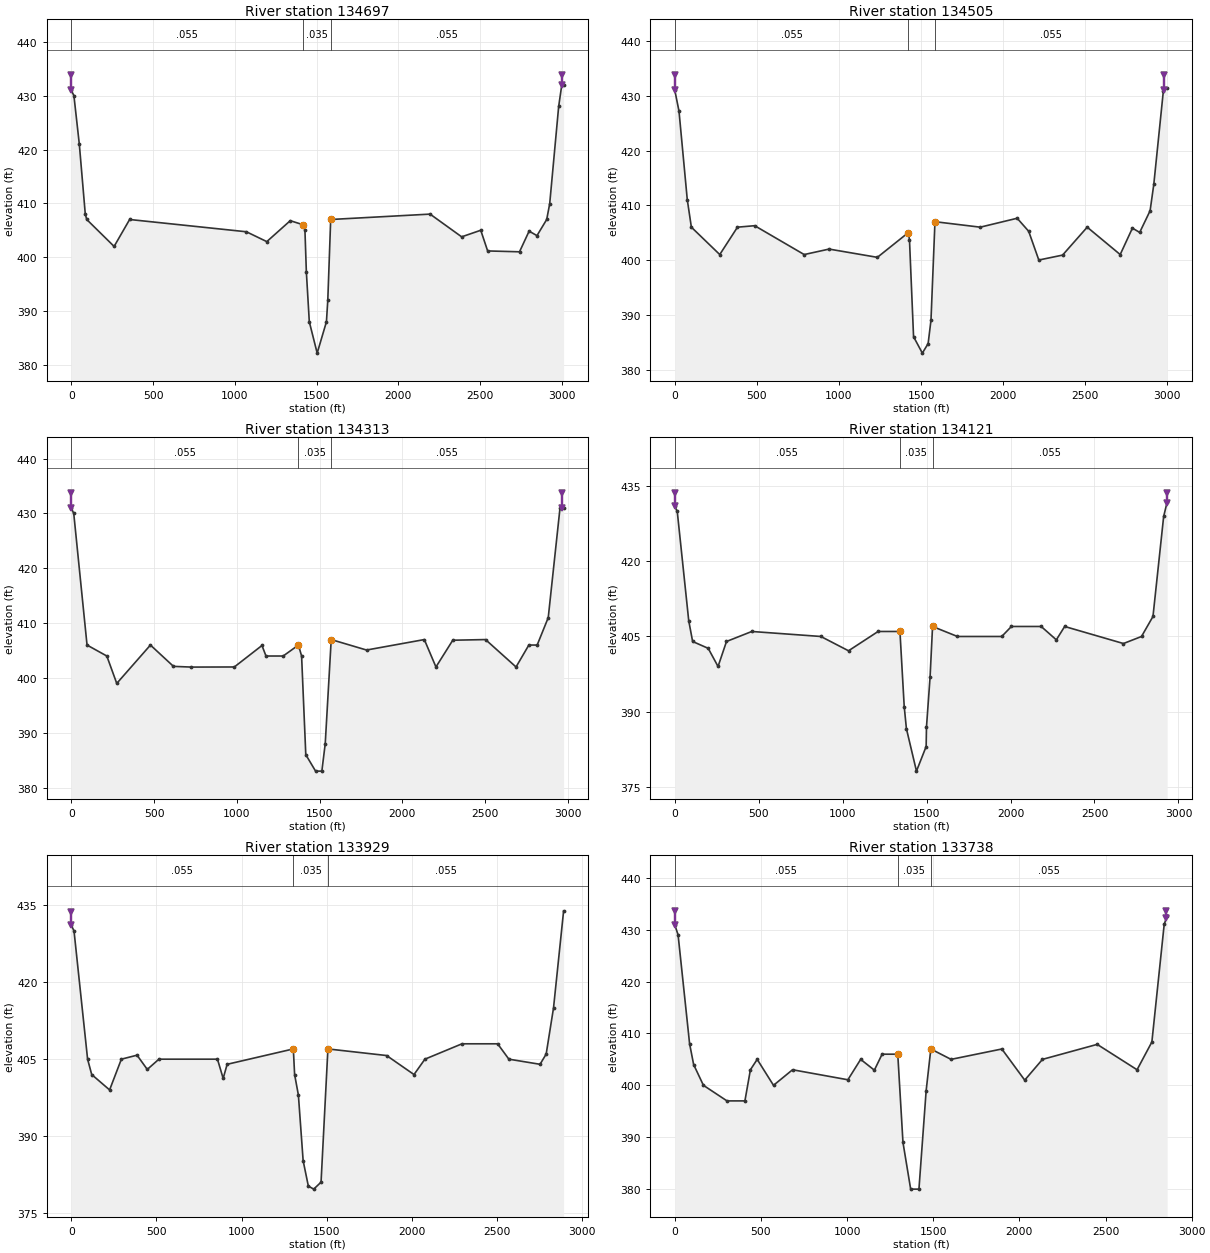
Type RM Length L Ch R = 1 ,134697  ,203,195,191
BEGIN DESCRIPTION:
This cross section corresponds to cross section 134697 of the non-georeferenced CDC model which was the source of this model.
END DESCRIPTION:
XS GIS Cut Line= 2
2474448.759796176978689.546641722473799.544559186975749.98460747
#Sta/Elev= 30
       0     431   16.09     430    49.1     421   85.47  408.04   94.45     407
  261.89     402  356.76     407 1070.82  404.72  1195.5  402.89 1339.01  406.78
 1419.76     406 1428.71     405 1437.33  397.29 1455.41     388 1503.55  382.18
 1560.12     388 1568.43     392 1586.18     407 2193.96     408 2387.01  403.78
 2503.73     405 2545.87  401.16 2740.72     401 2799.47  404.84 2847.49     404
 2906.99     407 2925.34  409.93 2980.18     428 2999.18     432  3010.4     432
#Mann= 3 ,0,0
       0    .055       0 1419.76    .035       0 1586.18    .055       0
Levee=-1,0,433.87,-1,3000,433.87,,
#XS Ineff= 2 , 0
         1419.76     406 1586.18             407
Permanent Ineff=
       F       F
Bank Sta=1419.76,1586.18
XS Rating Curve= 0 ,0
Exp/Cntr=0.3,0.1

Type RM Length L Ch R = 1 ,134505  ,202,194,190
BEGIN DESCRIPTION:
This cross section corresponds to cross section 134505 of the non-georeferenced CDC model which was the source of this model.
END DESCRIPTION:
XS GIS Cut Line= 2
2474659.771185166978675.920684712473979.363753356975754.71458489
#Sta/Elev= 30
       0     431   25.53  427.19   76.05     411  100.91     406  273.83     401
  381.79     406  486.56  406.27  788.21     401  939.95     402 1234.05  400.49
 1422.29     405 1429.64  403.72 1454.54     386 1508.04     383 1543.28  384.74
 1560.68     389 1584.96     407 1860.95     406 2085.77  407.63 2155.89  405.25
 2217.63     400 2362.37   400.9 2512.44     406 2713.43     401 2787.92  405.83
 2832.18  405.04 2895.61     409 2918.08  413.81 2976.61  430.95  2999.4  431.33
#Mann= 3 ,0,0
       0    .055       0 1422.29    .035       0 1584.96    .055       0
Levee=-1,0,433.82,-1,2983,433.82,,
#XS Ineff= 2 , 0
         1422.29     405 1584.96             407
Permanent Ineff=
       F       F
Bank Sta=1422.29,1584.96
XS Rating Curve= 0 ,0
Exp/Cntr=0.3,0.1

Type RM Length L Ch R = 1 ,134313  ,202,194,190
BEGIN DESCRIPTION:
This cross section corresponds to cross section 134313 of the non-georeferenced CDC model which was the source of this model.
END DESCRIPTION:
XS GIS Cut Line= 2
2474863.244531516978645.260312962474156.997256346975755.07908547
#Sta/Elev= 30
       0     431   14.93     430   95.23     406  214.75     404   274.8     399
  478.32     406  617.61  402.11  726.36  401.98  985.31     402 1152.34  405.92
 1176.61     404 1280.45     404 1372.87     406 1391.81     404 1417.15     386
 1476.34     383 1514.17     383 1534.64     388 1570.83     407 1784.32  405.09
 2133.47     407 2203.73     402 2305.35  406.88 2503.24     407 2687.74     402
 2765.07     406 2815.38     406 2882.27     411 2953.27  430.96 2975.22  430.94
#Mann= 3 ,0,0
       0    .055       0 1372.87    .035       0 1570.83    .055       0
Levee=-1,0,433.77,-1,2963,433.77,,
#XS Ineff= 2 , 0
         1372.87     406 1570.83             407
Permanent Ineff=
       F       F
Bank Sta=1372.87,1570.83
XS Rating Curve= 0 ,0
Exp/Cntr=0.3,0.1

Type RM Length L Ch R = 1 ,134121  ,197,189,185
BEGIN DESCRIPTION:
This cross section corresponds to cross section 134121 of the non-georeferenced CDC model which was the source of this model.
END DESCRIPTION:
XS GIS Cut Line= 2
2475064.134549686978593.086860882474334.185222186975752.63027146
#Sta/Elev= 30
       0     431   14.59     430   82.97  408.15  106.14     404  198.96  402.63
  257.57     399  307.91     404  458.65     406  870.16     405 1034.78  402.14
 1210.97     406 1341.12     406 1366.53     391 1379.64  386.57 1439.54  378.08
 1497.21     383 1499.23  386.92 1520.61  396.89 1535.39     407 1683.56     405
 1947.45     405 2005.12     407 2182.51     407 2272.66  404.33 2322.34     407
 2672.44  403.59 2780.12     405 2848.38     409 2912.03  428.99 2932.75  431.88
#Mann= 3 ,0,0
       0    .055       0 1341.12    .035       0 1535.39    .055       0
Levee=-1,0,433.72,-1,2931,433.72,,
#XS Ineff= 2 , 0
         1341.12     406 1535.08           406.7
Permanent Ineff=
       F       F
Bank Sta=1341.12,1535.39
XS Rating Curve= 0 ,0
Exp/Cntr=0.3,0.1

Type RM Length L Ch R = 1 ,133929  ,197,188,185
BEGIN DESCRIPTION:
This cross section corresponds to cross section 133929 of the non-georeferenced CDC model which was the source of this model.
END DESCRIPTION:
XS GIS Cut Line= 2
 2475258.36972556978526.674592142474507.580872746975735.27991247
#Sta/Elev= 30
       0  431.17   16.13     430   95.81     405  119.93     402  224.99     399
   294.1     405  386.05  405.78   446.2     403  514.56     405  858.27     405
  891.77  401.24  915.09     404 1303.69     407 1311.24     402  1333.4     398
 1361.28  385.19 1391.79  380.24 1423.37  379.64 1466.47     381 1506.74     407
 1851.42  405.71 2012.18     402 2076.26     405  2293.9     408 2503.22     408
 2569.28     405  2752.2     404 2788.23     406 2831.32     415  2890.6  433.95
#Mann= 3 ,0,0
       0    .055       0 1303.69    .035       0 1506.74    .055       0
Levee=-1,0,433.67,-1,2891,433.67,,
#XS Ineff= 2 , 0
         1303.69     407 1506.74             407
Permanent Ineff=
       F       F
Bank Sta=1303.69,1506.74
XS Rating Curve= 0 ,0
Exp/Cntr=0.3,0.1

Type RM Length L Ch R = 1 ,133738  ,253,223,210
BEGIN DESCRIPTION:
This cross section corresponds to cross section 133738 of the non-georeferenced CDC model which was the source of this model.
END DESCRIPTION:
XS GIS Cut Line= 2
2475448.824725186978447.136365382474673.314465176975696.73832288
#Sta/Elev= 30
       0   430.9   19.01     429   85.87     408   109.3     404  166.14     400
  302.84     397   406.9     397  438.82     403  478.23     405  572.88     400
  683.41     403  1004.6  401.07 1078.76     405 1158.29  402.92 1203.25     406
 1294.13     406 1324.32     389 1369.03     380 1417.07     380 1458.97     399
 1486.09     407 1603.51     405 1898.25     407 2030.99     401 2134.02     405
 2451.68  407.89 2683.06     403 2769.06  408.35 2840.52     431 2857.64  432.65
#Mann= 3 ,0,0
       0    .055       0 1294.13    .035       0 1486.09    .055       0
Levee=-1,0,433.62,-1,2853,433.62,,
#XS Ineff= 2 , 0
         1294.13     406 1486.09             407
Permanent Ineff=
       F       F
Bank Sta=1294.13,1486.09
XS Rating Curve= 0 ,0
Exp/Cntr=0.3,0.1

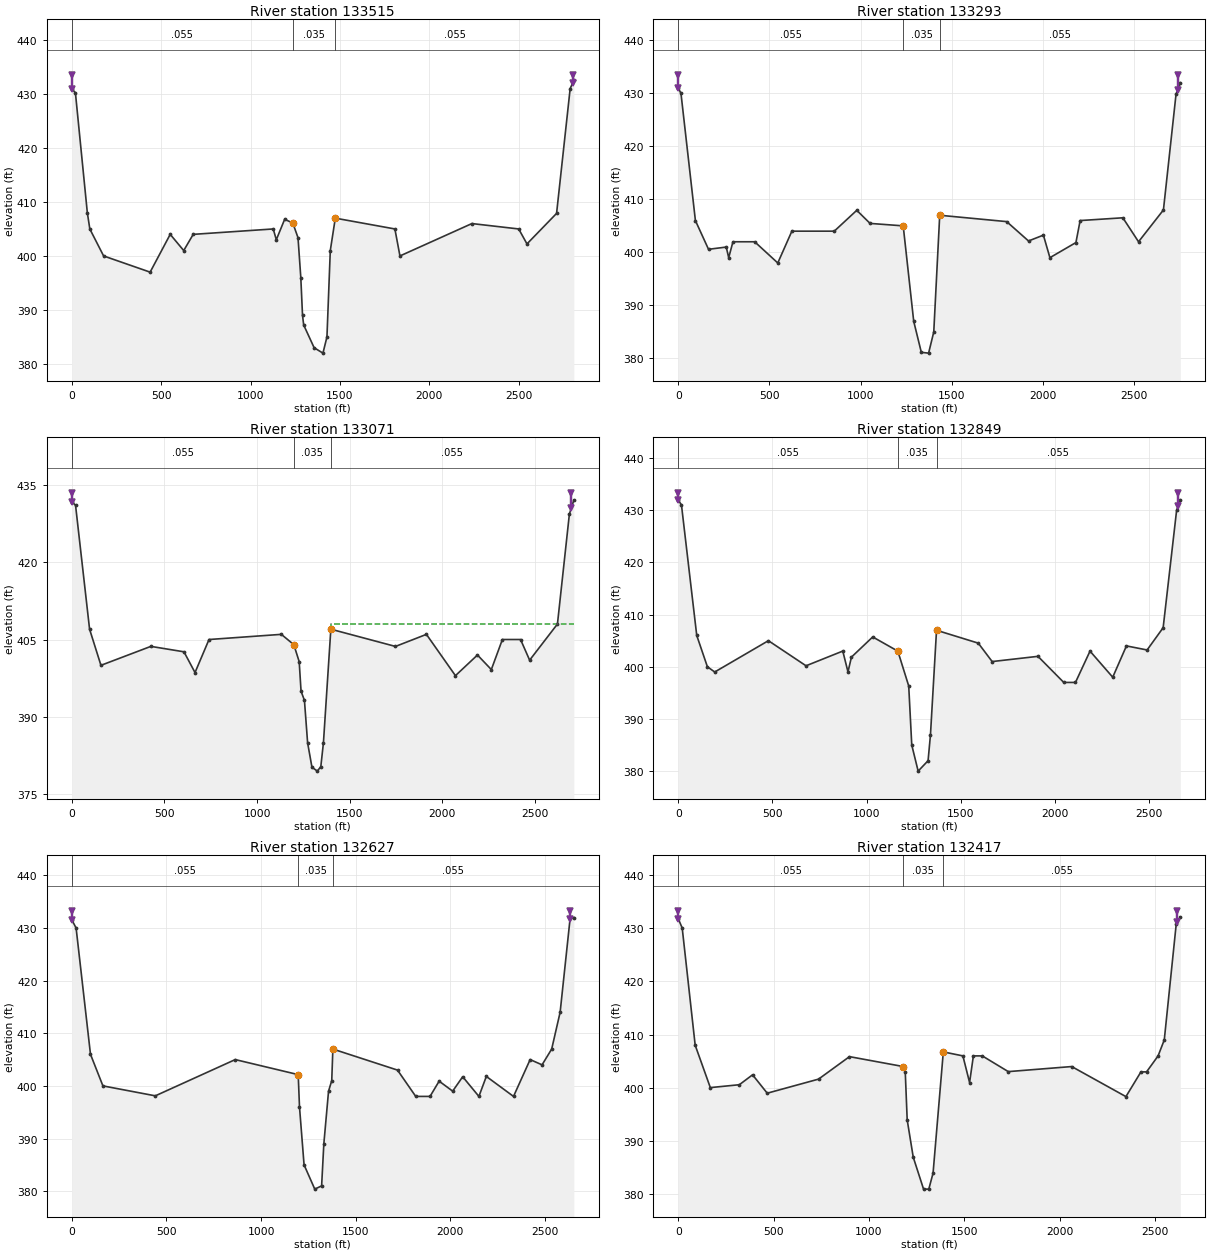
Type RM Length L Ch R = 1 ,133515  ,252,220,208
BEGIN DESCRIPTION:
This cross section corresponds to cross section 133515 of the non-georeferenced CDC model which was the source of this model.
END DESCRIPTION:
XS GIS Cut Line= 2
2475702.735306596978331.928590552474835.012304516975661.44771105
#Sta/Elev= 30
       0     431   20.41  430.21   87.04     408  100.99     405  178.05     400
  438.21     397  550.54     404  626.11     401  679.13     404 1126.72     405
  1143.9     403  1190.6  406.79 1236.21   406.1 1265.28  403.38  1280.9     396
 1290.47     389 1297.03  387.21 1355.41     383 1404.74     382 1427.12     385
 1445.82     401 1473.88     407  1807.1     405 1835.34     400 2237.87     406
 2499.47     405 2545.81  402.23 2711.32  407.88 2787.35     431 2807.92   432.5
#Mann= 3 ,0,0
       0    .055       0 1236.21    .035       0 1473.88    .055       0
Levee=-1,0,433.55,-1,2801,433.55,,
#XS Ineff= 2 , 0
         1236.21   406.1 1473.88             407
Permanent Ineff=
       F       F
Bank Sta=1236.21,1473.88
XS Rating Curve= 0 ,0
Exp/Cntr=0.3,0.1

Type RM Length L Ch R = 1 ,133293  ,254,222,210
BEGIN DESCRIPTION:
This cross section corresponds to cross section 133293 of the non-georeferenced CDC model which was the source of this model.
END DESCRIPTION:
XS GIS Cut Line= 2
2475947.578977026978203.26611821 2474994.0418421 6975619.4172833
#Sta/Elev= 30
       0     431   14.95     430   94.17     406   166.1  400.58  263.35     401
  276.83     399  300.19     402  419.35     402  546.06     398  623.36     404
  855.98     404  979.33  407.93 1052.35  405.46 1234.05     405 1291.76     387
 1333.44  381.15 1373.41     381 1401.77     385 1434.36     407 1801.69   405.8
 1921.47  402.15 2003.12  403.25 2038.85     399 2181.55  401.85 2204.68     406
 2438.97  406.52 2525.01     402 2661.58     408 2730.65   429.8 2754.18     432
#Mann= 3 ,0,0
       0    .055       0 1234.05    .035       0 1434.36    .055       0
Levee=-1,0,433.48,-1,2740,433.48,,
#XS Ineff= 2 , 0
         1234.05     405 1434.36             407
Permanent Ineff=
       F       F
Bank Sta=1234.05,1434.36
XS Rating Curve= 0 ,0
Exp/Cntr=0.3,0.1

Type RM Length L Ch R = 1 ,133071  ,255,223,211
BEGIN DESCRIPTION:
This cross section corresponds to cross section 133071 of the non-georeferenced CDC model which was the source of this model.
END DESCRIPTION:
XS GIS Cut Line= 2
 2476190.44266456978064.769019892475148.14783308 6975563.5610958
#Sta/Elev= 30
       0   431.7   20.41     431   96.12     407  157.44     400  426.82  403.67
  605.48  402.62  665.18   398.6  740.68     405  1131.1     406 1198.46     404
 1227.38  400.71 1237.41     395 1255.78   393.2 1272.81     385  1296.2  380.27
 1325.28  379.51 1344.12  380.39 1358.23     385  1398.2     407 1747.01  403.66
 1914.01     406 2070.65     398 2189.51     402 2264.36  399.18 2324.05     405
 2422.13     405  2471.1     401 2621.18     408 2685.56  429.28 2709.69     432
#Mann= 3 ,0,0
       0    .055       0 1198.46    .035       0  1398.2    .055       0
Levee=-1,0,433.41,-1,2696,433.41,,
#XS Ineff= 2 , 0
         1198.46     404 1400.52             408
Permanent Ineff=
       F       F
Bank Sta=1198.46,1398.2
XS Rating Curve= 0 ,0
Exp/Cntr=0.3,0.1

Type RM Length L Ch R = 1 ,132849  ,258,225,213
BEGIN DESCRIPTION:
This cross section corresponds to cross section 132849 of the non-georeferenced CDC model which was the source of this model.
END DESCRIPTION:
XS GIS Cut Line= 2
2476429.079982526977915.322140312475298.234475176975500.17047454
#Sta/Elev= 30
       0     432    17.2     431   98.32     406  154.89     400  193.87     399
  478.93     405   678.8  400.19     874  403.01  901.59  399.02  919.96  401.85
 1033.06  405.72 1166.42     403 1224.24  396.32 1240.36     385 1274.31     380
 1327.05     382 1339.81     387 1371.94     407 1593.66  404.53 1667.37     401
  1910.7     402 2047.71     397 2109.93     397 2187.16     403 2307.83     398
 2380.64     404 2490.43  403.22 2575.66  407.49 2647.19     430 2666.79     432
#Mann= 3 ,0,0
       0    .055       0 1166.42    .035       0 1371.94    .055       0
Levee=-1,0,433.34,-1,2655,433.34,,
#XS Ineff= 2 , 0
         1166.42     403 1371.94             407
Permanent Ineff=
       F       F
Bank Sta=1166.42,1371.94
XS Rating Curve= 0 ,0
Exp/Cntr=0.3,0.1

Type RM Length L Ch R = 1 ,132627  ,208,209,208
BEGIN DESCRIPTION:
This cross section corresponds to cross section 132627 of the non-georeferenced CDC model which was the source of this model.
END DESCRIPTION:
XS GIS Cut Line= 2
2476672.885269176977773.963171052475442.394948016975424.75363064
#Sta/Elev= 30
       0  431.58   22.92     430   98.86     406  164.57     400  441.36  398.11
  863.49     405 1196.02  402.14 1202.85     396 1226.95     385 1283.54  380.38
 1319.73     381  1331.4  388.98 1356.29     399 1373.19     401  1379.1     407
 1720.56     403 1816.86     398 1892.29     398 1940.45   400.9 2011.91     399
 2064.83  401.74 2150.46     398 2189.73   401.8 2333.28     398 2421.12     405
 2484.07     404 2534.92     407 2579.54     414 2632.37  431.87 2651.96     432
#Mann= 3 ,0,0
       0    .055       0 1196.02    .035       0  1379.1    .055       0
Levee=-1,0,433.27,-1,2632,433.27,,
#XS Ineff= 2 , 0
         1196.02  402.14  1379.1             407
Permanent Ineff=
       F       F
Bank Sta=1196.02,1379.1
XS Rating Curve= 0 ,0
Exp/Cntr=0.3,0.1

Type RM Length L Ch R = 1 ,132417  ,210,211,210
BEGIN DESCRIPTION:
This cross section corresponds to cross section 132417 of the non-georeferenced CDC model which was the source of this model.
END DESCRIPTION:
XS GIS Cut Line= 2
2476851.747116186977661.932883292475621.420508596975333.31483713
#Sta/Elev= 30
       0  431.74    20.8     430   88.91     408  168.32  400.05  320.53  400.59
  389.89  402.45  466.83     399  735.99  401.64  898.22  405.86 1180.56     404
 1190.83     403 1200.99     394 1232.68     387 1286.85     381 1314.34     381
 1336.71     384 1390.49  406.75 1493.16     406 1528.27     401  1548.2     406
 1594.88     406 1731.18  403.05 2064.05     404  2348.4  398.36 2427.12     403
 2456.64     403 2517.12     406 2549.56     409 2612.48  430.82 2633.66  431.99
#Mann= 3 ,0,0
       0    .055       0 1180.56    .035       0 1390.49    .055       0
Levee=-1,0,433.22,-1,2618,433.22,,
#XS Ineff= 2 , 0
         1180.56     404 1390.49          406.75
Permanent Ineff=
       F       F
Bank Sta=1180.56,1390.49
XS Rating Curve= 0 ,0
Exp/Cntr=0.3,0.1

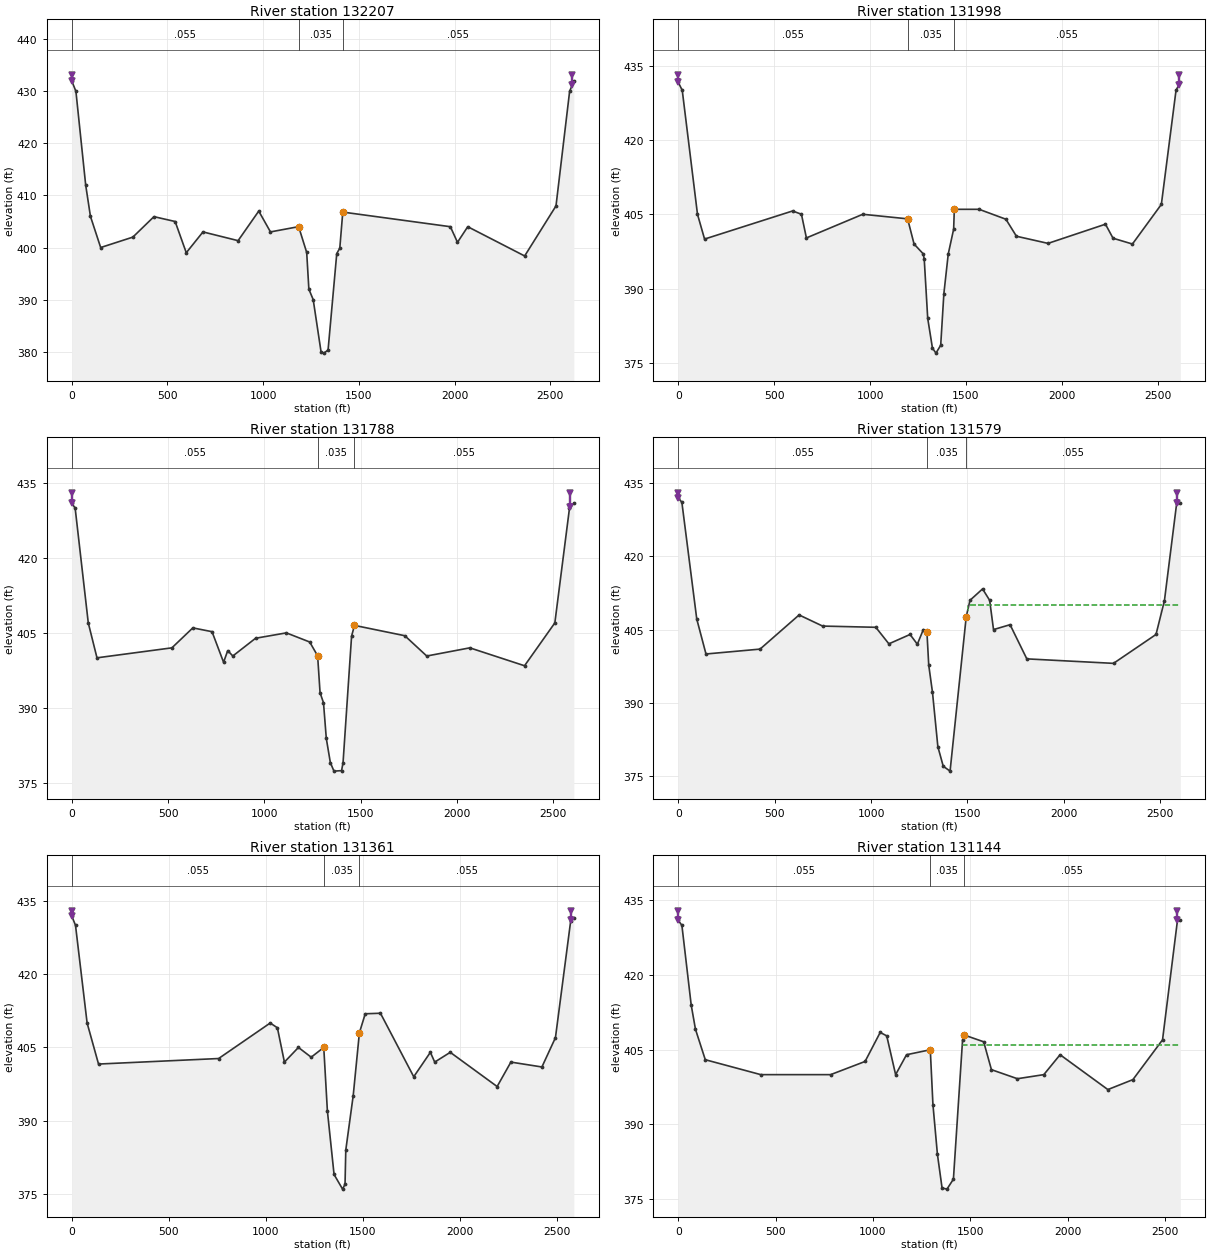
Type RM Length L Ch R = 1 ,132207  ,210,210,210
BEGIN DESCRIPTION:
This cross section corresponds to cross section 132207 of the non-georeferenced CDC model which was the source of this model.
END DESCRIPTION:
XS GIS Cut Line= 2
2477036.049241016977556.132898052475802.39980543 6975240.7113478
#Sta/Elev= 30
       0     432   21.66     430   72.71     412    97.5     406  151.01     400
  319.14     402  429.44  405.93  540.15     405  598.34     399  685.67     403
  869.08  401.32  977.05     407 1038.29     403 1185.46  404.01 1227.61  399.05
 1238.93     392 1261.56     390 1302.46     380 1317.25  379.72 1339.28  380.31
 1384.67  398.84 1400.57  399.88 1416.13  406.81 1978.39     404  2015.5     401
  2069.2     404 2366.57  398.38 2530.35     408  2601.5     430 2623.56  431.97
#Mann= 3 ,0,0
       0    .055       0 1185.46    .035       0 1416.13    .055       0
Levee=-1,0,433.17,-1,2615,433.17,,
#XS Ineff= 2 , 0
         1185.46  404.01 1416.13          406.81
Permanent Ineff=
       F       F
Bank Sta=1185.46,1416.13
XS Rating Curve= 0 ,0
Exp/Cntr=0.3,0.1

Type RM Length L Ch R = 1 ,131998  ,210,210,210
BEGIN DESCRIPTION:
This cross section corresponds to cross section 131998 of the non-georeferenced CDC model which was the source of this model.
END DESCRIPTION:
XS GIS Cut Line= 2
  2477219.5567486977448.828650712475979.97622192 6975143.2509128
#Sta/Elev= 30
       0  431.61   20.91     430  100.35     405   137.3     400  596.45  405.67
  642.35     405  668.23  400.23   962.2     405 1195.88  404.08 1229.56     399
 1276.83  397.04  1282.5     396 1300.71     384 1325.46     378 1343.88     377
 1368.45   378.6 1384.94     389  1407.8     397 1435.92     402 1439.45     406
 1568.91     406 1708.39     404 1763.25  400.57 1928.01  399.13 2227.42     403
 2266.94  400.17 2368.04     399 2518.85  406.99 2595.37     430 2617.68  431.63
#Mann= 3 ,0,0
       0    .055       0 1195.88    .035       0 1439.45    .055       0
Levee=-1,0,433.12,-1,2611,433.12,,
#XS Ineff= 2 , 0
         1195.88  404.08 1439.45             406
Permanent Ineff=
       F       F
Bank Sta=1195.88,1439.45
XS Rating Curve= 0 ,0
Exp/Cntr=0.3,0.1

Type RM Length L Ch R = 1 ,131788  ,211,210,211
BEGIN DESCRIPTION:
This cross section corresponds to cross section 131788 of the non-georeferenced CDC model which was the source of this model.
END DESCRIPTION:
XS GIS Cut Line= 2
2477405.853291426977343.837390882476161.534585836975051.74223755
#Sta/Elev= 30
       0     431    17.6     430   85.74     407  130.98     400  520.14     402
  628.83     406  728.55  405.24  788.56  399.11  810.08  401.44   836.7  400.37
  954.74  403.92 1114.66     405 1235.99  403.17 1277.11   400.4 1289.77     393
 1307.62     391 1322.18  383.84  1343.2     379 1361.95  377.29 1401.54  377.39
 1409.21     379 1453.51  404.35 1468.62   406.5 1729.96  404.43 1843.98  400.36
  2067.7     402 2351.96  398.41 2509.37     407 2585.47     430 2608.07     431
#Mann= 3 ,0,0
       0    .055       0 1277.11    .035       0 1468.62    .055       0
Levee=-1,0,433.07,-1,2589,433.07,,
#XS Ineff= 2 , 0
         1277.11   400.4 1468.62           406.5
Permanent Ineff=
       F       F
Bank Sta=1277.11,1468.62
XS Rating Curve= 0 ,0
Exp/Cntr=0.3,0.1

Type RM Length L Ch R = 1 ,131579  ,215,215,215
BEGIN DESCRIPTION:
This cross section corresponds to cross section 131579 of the non-georeferenced CDC model which was the source of this model.
END DESCRIPTION:
XS GIS Cut Line= 2
2477590.121623676977236.017724632476340.477141356974951.52819914
#Sta/Elev= 30
       0     432   18.85  431.08   96.02  407.17  143.89     400  424.31     401
  626.83     408  748.79  405.72 1024.59  405.47 1092.47  402.08 1202.31     404
  1240.1     402 1271.11     405 1289.75  404.53 1299.24  397.69 1318.66  392.14
 1346.53     381 1374.45     377 1409.86     376  1493.7  407.67 1513.17     411
 1578.33  413.33 1615.11     411 1635.15     405 1720.99     406 1807.91     399
 2257.43  398.08 2477.94     404 2521.63  410.94 2585.48     431 2603.94     431
#Mann= 3 ,0,0
       0    .055       0 1289.75    .035       0  1493.7    .055       0
Levee=-1,0,433.02,-1,2585,433.02,,
#XS Ineff= 2 , 0
         1289.75  404.53 1500.88             410
Permanent Ineff=
       F       F
Bank Sta=1289.75,1493.7
XS Rating Curve= 0 ,0
Exp/Cntr=0.3,0.1

Type RM Length L Ch R = 1 ,131361  ,218,217,218
BEGIN DESCRIPTION:
This cross section corresponds to cross section 131361 of the non-georeferenced CDC model which was the source of this model.
END DESCRIPTION:
XS GIS Cut Line= 2
2477777.637980916977125.75777455 2476531.28286216974857.03855872
#Sta/Elev= 30
       0   431.9   19.23     430   79.11     410  137.96   401.6  757.13  402.73
 1023.12     410 1060.12  409.02 1096.35     402 1168.58     405  1234.4     403
 1299.16     405 1317.85  392.02  1352.3     379 1396.16     376 1408.85     377
 1412.74     384 1451.07  395.16  1482.9     408  1513.1  411.89 1591.47     412
 1763.07     399 1848.86     404 1871.21     402 1951.34     404 2193.04     397
 2263.93     402 2423.91     401 2493.68     407  2572.2  430.87 2588.53  431.42
#Mann= 3 ,0,0
       0    .055       0 1299.16    .035       0  1482.9    .055       0
Levee=-1,0,432.96,-1,2576,432.96,,
#XS Ineff= 2 , 0
         1299.16     405  1482.9             408
Permanent Ineff=
       F       F
Bank Sta=1299.16,1482.9
XS Rating Curve= 0 ,0
Exp/Cntr=0.3,0.1

Type RM Length L Ch R = 1 ,131144  ,217,217,217
BEGIN DESCRIPTION:
This cross section corresponds to cross section 131144 of the non-georeferenced CDC model which was the source of this model.
END DESCRIPTION:
XS GIS Cut Line= 2
2477966.863324256977013.939100552476721.093834166974756.33600421
#Sta/Elev= 30
       0     431   18.76     430   66.53     414   88.47  409.12  138.89     403
  424.03     400  782.69     400  959.57  402.65 1037.22  408.48 1070.77  407.79
 1116.43     400 1172.44     404 1294.44     405 1308.05     394 1331.07     384
  1354.9  377.24 1380.05     377 1413.23     379 1460.21  406.94 1465.86     408
 1568.68   406.6 1608.44     401 1741.86  399.18 1877.45     400 1961.06     404
 2206.44     397 2335.08     399 2487.24     407  2563.9     431 2578.51     431
#Mann= 3 ,0,0
       0    .055       0 1294.44    .035       0 1465.86    .055       0
Levee=-1,0,432.91,-1,2564,432.91,,
#XS Ineff= 2 , 0
         1294.44     405 1458.44          405.91
Permanent Ineff=
       F       F
Bank Sta=1294.44,1465.86
XS Rating Curve= 0 ,0
Exp/Cntr=0.3,0.1

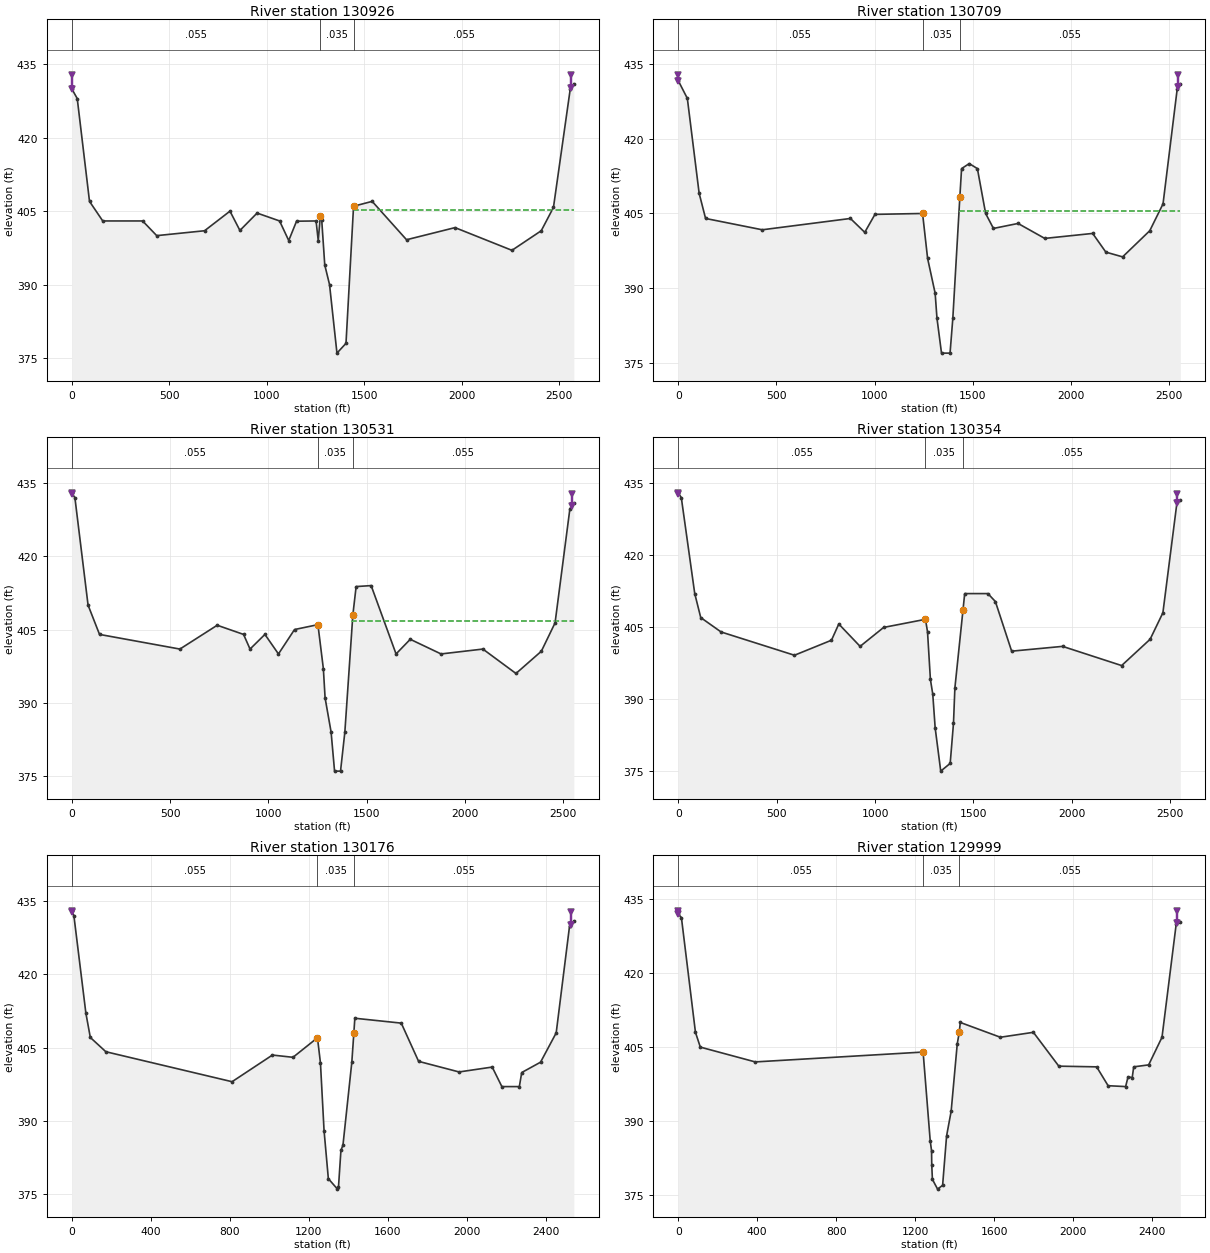
Type RM Length L Ch R = 1 ,130926  ,221,220,221
BEGIN DESCRIPTION:
This cross section corresponds to cross section 130926 of the non-georeferenced CDC model which was the source of this model.
END DESCRIPTION:
XS GIS Cut Line= 2
2478159.452506016976908.186031222476910.719767246974656.00451197
#Sta/Elev= 30
       0     430   28.07     428   90.96     407  158.86     403   363.3     403
  435.68     400  681.14     401  811.41     405  862.42  401.06  950.55  404.61
 1065.92     403 1112.81     399 1152.94  402.95 1253.03     403 1264.14     399
 1274.92     404 1281.88  403.27 1297.64     394  1322.1     390 1360.17     376
 1406.54     378 1445.32     406  1540.8     407  1717.1  399.16  1965.8  401.64
 2257.76     397 2407.97     401 2470.64  405.76 2556.91     430  2575.2     431
#Mann= 3 ,0,0
       0    .055       0 1274.92    .035       0 1445.32    .055       0
Levee=-1,0,432.85,-1,2561,432.85,,
#XS Ineff= 2 , 0
         1274.92     404 1444.21          405.22
Permanent Ineff=
       F       F
Bank Sta=1274.92,1445.32
XS Rating Curve= 0 ,0
Exp/Cntr=0.3,0.1

Type RM Length L Ch R = 1 ,130709  ,175,175,175
BEGIN DESCRIPTION:
This cross section corresponds to cross section 130709 of the non-georeferenced CDC model which was the source of this model.
END DESCRIPTION:
XS GIS Cut Line= 2
 2478345.9934715 6976785.35983332477102.600617086974552.85150304
#Sta/Elev= 30
       0  431.64   46.34  428.07  106.41  409.05  139.12     404  427.72  401.73
  876.29     404  949.34  401.22 1001.23  404.82 1243.58     405 1269.18     396
 1307.63     389 1316.86     384 1339.98     377 1383.45     377 1397.61     384
 1433.28  408.27 1442.12     414 1481.17     415 1522.59     414 1564.56     405
 1604.29     402 1729.53     403 1865.44     400 2109.35     401 2176.42  397.25
 2261.73   396.3 2399.91  401.54 2467.47  406.93 2539.72     430 2555.41     431
#Mann= 3 ,0,0
       0    .055       0 1243.58    .035       0 1433.28    .055       0
Levee=-1,0,432.8,-1,2546,432.8,,
#XS Ineff= 2 , 0
         1243.58     405 1429.18          405.58
Permanent Ineff=
       F       F
Bank Sta=1243.58,1433.28
XS Rating Curve= 0 ,0
Exp/Cntr=0.3,0.1

Type RM Length L Ch R = 1 ,130531  ,179,178,179
BEGIN DESCRIPTION:
This cross section corresponds to cross section 130531 of the non-georeferenced CDC model which was the source of this model.
END DESCRIPTION:
XS GIS Cut Line= 2
2478498.079453416976698.122474972477254.733514936974467.57969196
#Sta/Elev= 30
       0     433   15.96     432   82.88     410  141.17     404  549.98     401
  739.73  405.88   873.8     404  906.73     401  982.35     404 1051.24     400
 1133.02     405 1251.98     406 1279.62     397 1288.45     391 1318.99     384
 1336.64     376 1366.96     376 1388.95     384 1429.65     408 1446.33   413.8
 1522.69     414 1649.37     400 1721.65     403 1878.28     400 2091.04     401
  2259.3     396 2388.31  400.55 2458.12  406.36 2533.55  429.73 2553.67   430.9
#Mann= 3 ,0,0
       0    .055       0 1251.98    .035       0 1429.65    .055       0
Levee=-1,0,432.76,-1,2542,432.76,,
#XS Ineff= 2 , 0
         1251.98     406 1427.13          406.81
Permanent Ineff=
       F       F
Bank Sta=1251.98,1429.65
XS Rating Curve= 0 ,0
Exp/Cntr=0.3,0.1

Type RM Length L Ch R = 1 ,130354  ,178,178,178
BEGIN DESCRIPTION:
This cross section corresponds to cross section 130354 of the non-georeferenced CDC model which was the source of this model.
END DESCRIPTION:
XS GIS Cut Line= 2
2478653.27730575 6976610.30309682477409.834254596974382.89449388
#Sta/Elev= 30
       0     433   15.63     432   83.88     412  114.36     407  217.82     404
  590.48  399.15  778.58  402.28  815.74  405.66  924.01     401 1043.72  404.95
 1256.27  406.64 1266.66     404 1281.23  394.11 1293.22  391.04 1305.44     384
 1333.72     375 1381.75  376.61 1398.53  384.97  1405.6  392.33 1446.68  408.53
 1455.45     412 1573.48     412 1611.41  410.34 1694.07     400 1952.89     401
 2252.81     397 2397.56  402.48  2462.5     408 2534.05     431 2550.98  431.47
#Mann= 3 ,0,0
       0    .055       0 1256.27    .035       0 1446.68    .055       0
Levee=-1,0,432.71,-1,2534,432.71,,
#XS Ineff= 2 , 0
         1256.27  406.64 1439.11          405.54
Permanent Ineff=
       F       F
Bank Sta=1256.27,1446.68
XS Rating Curve= 0 ,0
Exp/Cntr=0.3,0.1

Type RM Length L Ch R = 1 ,130176  ,179,178,179
BEGIN DESCRIPTION:
This cross section corresponds to cross section 130176 of the non-georeferenced CDC model which was the source of this model.
END DESCRIPTION:
XS GIS Cut Line= 2
 2478802.53225666976511.845288472477562.755208586974294.27885747
#Sta/Elev= 30
       0     433   10.78     432   71.38  412.05   93.89  407.06  172.46  404.14
  811.15     398 1015.33  403.46 1119.48     403 1243.25     407 1258.37  401.85
 1276.59     388 1298.34  378.14 1344.61     376  1349.7  376.47    1362  383.94
 1372.28     385 1417.11     402 1427.42     408 1432.35     411 1667.32     410
 1755.04  402.17 1959.77     400 2127.56     401 2176.34     397 2264.82     397
 2276.86  399.88 2372.12     402 2451.28     408 2518.78  429.86  2540.6  430.83
#Mann= 3 ,0,0
       0    .055       0 1243.25    .035       0 1427.42    .055       0
Levee=-1,0,432.66,-1,2525,432.66,,
#XS Ineff= 2 , 0
         1243.25     407 1426.09          407.22
Permanent Ineff=
       F       F
Bank Sta=1243.25,1427.42
XS Rating Curve= 0 ,0
Exp/Cntr=0.3,0.1

Type RM Length L Ch R = 1 ,129999  ,181,180,181
BEGIN DESCRIPTION:
This cross section corresponds to cross section 129999 of the non-georeferenced CDC model which was the source of this model.
END DESCRIPTION:
XS GIS Cut Line= 2
2478960.443358096976428.870716882477718.399910426974210.55559972
#Sta/Elev= 30
       0     432   16.18  431.23   87.16     408  111.79     405     390     402
    1240     404 1275.97     386 1282.74     384 1283.73  381.16 1287.02   378.2
 1313.32  376.22 1338.75     377 1358.85     387 1381.96     392 1412.87  405.67
 1423.08     408  1428.1     410 1631.15     407 1798.34     408 1927.14  401.14
  2118.7     401 2176.74  397.18 2265.38     397 2277.97     399 2298.76  398.81
 2306.45     401 2382.08   401.4 2449.67     407 2521.73     430 2542.36  430.39
#Mann= 3 ,0,0
       0    .055       0    1240    .035       0 1423.08    .055       0
Levee=-1,0,432.62,-1,2527,432.62,,
#XS Ineff= 2 , 0
            1240  393.81  1428.1             410
Permanent Ineff=
       F       F
Bank Sta=1240,1423.08
XS Rating Curve= 0 ,0
Exp/Cntr=0.3,0.1