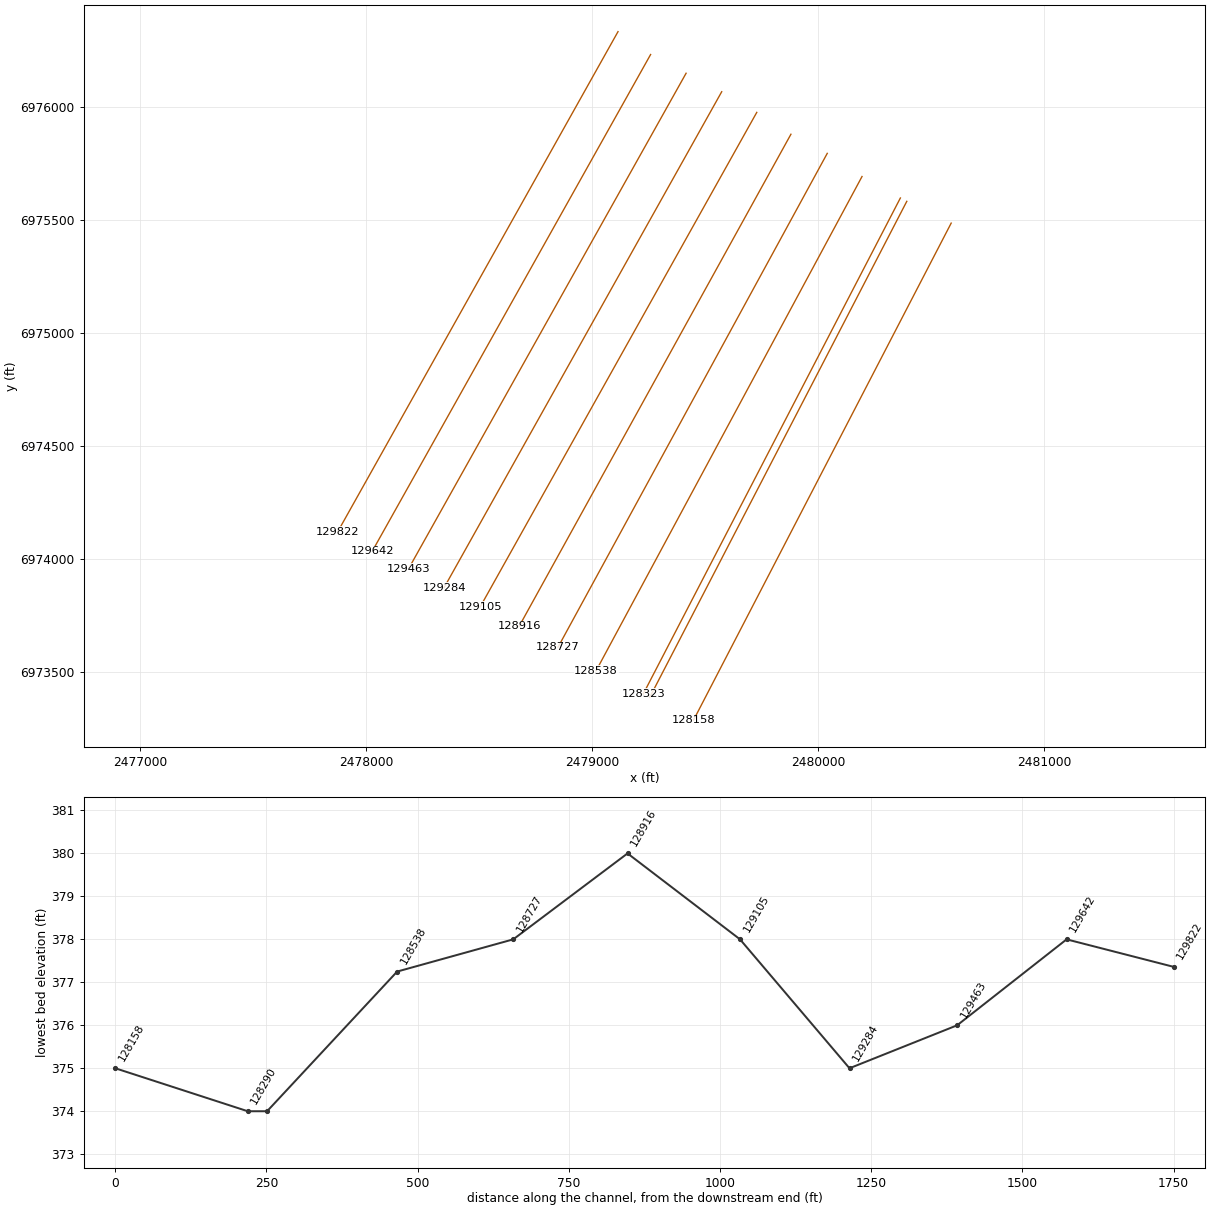
HEC-RAS study CDC_Consolidated_Model.prj: Upper Trinity CDC Consolidated Model

--- CDC_Consolidated_Model.g12 (geometry) --- (continued)

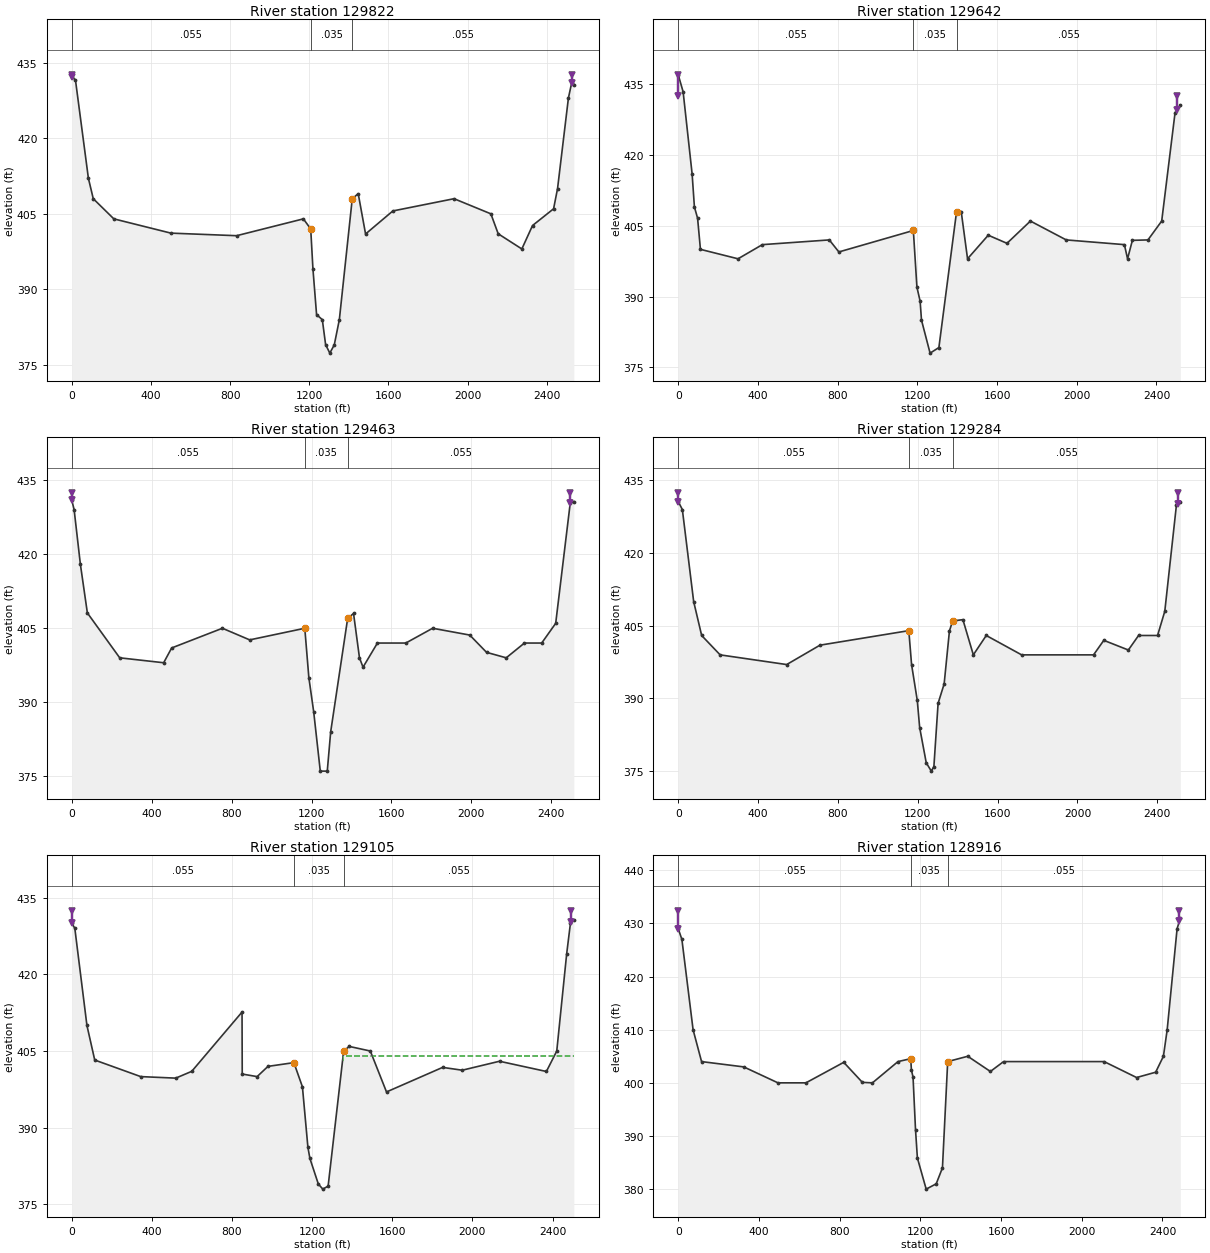
Type RM Length L Ch R = 1 ,129822  ,174,177,174
BEGIN DESCRIPTION:
This cross section corresponds to cross section 129822 of the non-georeferenced CDC model which was the source of this model.
END DESCRIPTION:
XS GIS Cut Line= 2
2479114.10118726 6976333.8863268  2477873.7877236974120.83727522
#Sta/Elev= 30
       0  432.17   18.51  431.59      84  412.05  108.59     408  212.53     404
  500.93  401.17  832.91  400.66 1170.21     404  1207.4     402 1218.53   394.1
 1236.96     385 1266.01     384 1282.61  379.05 1303.88  377.36 1326.42     379
 1352.02     384 1417.26     408 1447.37     409 1484.53     401 1622.39  405.57
 1931.58     408 2117.69     405 2154.64  401.04 2274.14  398.03 2328.24  402.68
 2434.56     406 2454.55     410 2509.56     428 2526.03     431 2536.92  430.62
#Mann= 3 ,0,0
       0    .055       0  1207.4    .035       0 1417.26    .055       0
Levee=-1,0,432.58,-1,2526,432.58,,
#XS Ineff= 2 , 0
          1207.4     402 1417.26             408
Permanent Ineff=
       F       F
Bank Sta=1207.4,1417.26
XS Rating Curve= 0 ,0
Exp/Cntr=0.3,0.1

Type RM Length L Ch R = 1 ,129642  ,179,181,179
BEGIN DESCRIPTION:
This cross section corresponds to cross section 129642 of the non-georeferenced CDC model which was the source of this model.
END DESCRIPTION:
XS GIS Cut Line= 2
2479258.34728983 6976232.60700182478026.54201066 6974034.6212403
#Sta/Elev= 30
       0     437   24.51  433.41   69.65     416   81.13     409   97.11   406.6
  111.39     400     300     398  422.17     401  758.12     402  806.09  399.45
 1179.89     404 1197.75  392.01 1213.91     389 1220.76     385 1263.84     378
 1308.06  379.18 1396.79     408 1420.14     408 1451.87     398 1555.76     403
  1649.8  401.28 1767.32     406 1947.18     402 2239.03     401 2254.89     398
 2279.09  401.91 2357.25     402 2426.24     406 2493.36     429 2519.62  430.57
#Mann= 3 ,0,0
       0    .055       0 1179.89    .035       0 1396.79    .055       0
Levee=-1,0,432.54,-1,2503,432.54,,
#XS Ineff= 2 , 0
         1179.89     404 1391.82             406
Permanent Ineff=
       F       F
Bank Sta=1179.89,1396.79
XS Rating Curve= 0 ,0
Exp/Cntr=0.3,0.1

Type RM Length L Ch R = 1 ,129463  ,177,178,177
BEGIN DESCRIPTION:
This cross section corresponds to cross section 129463 of the non-georeferenced CDC model which was the source of this model.
END DESCRIPTION:
XS GIS Cut Line= 2
2479415.392251346976149.759070382478187.263802086973957.08399379
#Sta/Elev= 30
       0     431   11.74  429.09   43.05     418   78.07  408.11     240     399
     460     398     500     401  753.99     405  890.59  402.64  1166.4     405
 1186.69     395 1211.08     388    1244     376 1278.91     376 1296.08     384
 1381.01     407 1410.45     408 1440.13     399 1457.96   397.1 1529.99     402
 1672.08     402 1806.33     405 1992.09  403.62 2076.27  400.11 2174.69     399
 2265.93     402  2352.3     402 2422.32     406 2495.03  430.38 2513.19  430.72
#Mann= 3 ,0,0
       0    .055       0  1166.4    .035       0 1381.01    .055       0
Levee=-1,0,432.49,-1,2495,432.49,,
#XS Ineff= 2 , 0
          1166.4     405 1381.01             407
Permanent Ineff=
       F       F
Bank Sta=1166.4,1381.01
XS Rating Curve= 0 ,0
Exp/Cntr=0.3,0.1

Type RM Length L Ch R = 1 ,129284  ,179,181,179
BEGIN DESCRIPTION:
This cross section corresponds to cross section 129284 of the non-georeferenced CDC model which was the source of this model.
END DESCRIPTION:
XS GIS Cut Line= 2
2479573.033668346976067.985283812478344.520377346973873.39387247
#Sta/Elev= 30
       0  430.65   20.63     429   77.29     410  117.33     403  209.84     399
  543.27     397     710     401    1155     404 1168.85     397 1197.41  389.59
 1209.39     384 1242.29  376.73  1267.7     375 1280.67  375.95 1301.74     389
 1332.02     393 1358.57  403.95  1374.6     406    1426  406.27  1478.2     399
 1542.96     403 1720.22     399 2080.43     399 2131.85     402 2254.75     400
 2305.96     403 2401.08     403  2437.3     408  2495.8     430 2515.05   430.5
#Mann= 3 ,0,0
       0    .055       0    1155    .035       0  1374.6    .055       0
Levee=-1,0,432.45,-1,2501,432.45,,
#XS Ineff= 2 , 0
            1155  398.83 1358.57          403.95
Permanent Ineff=
       F       F
Bank Sta=1155,1374.6
XS Rating Curve= 0 ,0
Exp/Cntr=0.3,0.1

Type RM Length L Ch R = 1 ,129105  ,184,186,187
BEGIN DESCRIPTION:
This cross section corresponds to cross section 129105 of the non-georeferenced CDC model which was the source of this model.
END DESCRIPTION:
XS GIS Cut Line= 2
 2479728.11669156975976.512697712478504.646041336973788.94292589
#Sta/Elev= 30
       0     430    15.2     429   75.68     410  114.62  403.24  344.07     400
     519   399.7     599  401.03     850  412.62     851   400.5  925.27     400
  979.61     402 1108.86  402.73 1151.48     398 1178.86  386.17 1188.82     384
 1230.87     379 1253.34     378  1279.8  378.59 1357.37     405 1385.09   405.9
  1490.4     405 1571.21     397 1851.33   401.8 1949.39  401.25 2135.34     403
 2369.38     401 2421.17     405 2470.65     424 2489.51     430 2506.46   430.6
#Mann= 3 ,0,0
       0    .055       0 1108.86    .035       0 1357.37    .055       0
Levee=-1,0,432.41,-1,2494,432.41,,
#XS Ineff= 2 , 0
         1108.86  402.73 1351.81             404
Permanent Ineff=
       F       F
Bank Sta=1108.86,1357.37
XS Rating Curve= 0 ,0
Exp/Cntr=0.3,0.1

Type RM Length L Ch R = 1 ,128916  ,187,189,190
BEGIN DESCRIPTION:
This cross section corresponds to cross section 128916 of the non-georeferenced CDC model which was the source of this model.
END DESCRIPTION:
XS GIS Cut Line= 2
2479879.359171186975879.822930472478676.222797936973701.49920313
#Sta/Elev= 30
       0     429   18.06     427   73.58     410  115.59     404  324.71     403
  494.31     400  632.88     400  820.34  403.86  912.68  400.09  962.59     400
 1089.16     404 1152.36  404.55 1155.66  402.45 1163.83  401.06 1176.05  391.18
 1185.35  385.86 1228.92     380 1278.63     381 1309.55     384 1335.56     404
 1434.97     405 1547.17  402.14 1612.59     404 2110.87     404 2271.82     401
 2366.29     402 2404.75     405 2423.32  409.95 2472.55     429  2488.5     431
#Mann= 3 ,0,0
       0    .055       0 1152.36    .035       0 1335.56    .055       0
Levee=-1,0,432.37,-1,2484,432.37,,
#XS Ineff= 2 , 0
         1152.36  404.55 1335.56             404
Permanent Ineff=
       F       F
#XS Lid=6
     920  419.12  413.72   921.7  419.12  413.72  921.71  419.12  418.42
  954.29  419.12  418.42   954.3  419.12  413.72     956  419.12  413.72
Bank Sta=1152.36,1335.56
XS Rating Curve= 0 ,0
Exp/Cntr=0.3,0.1

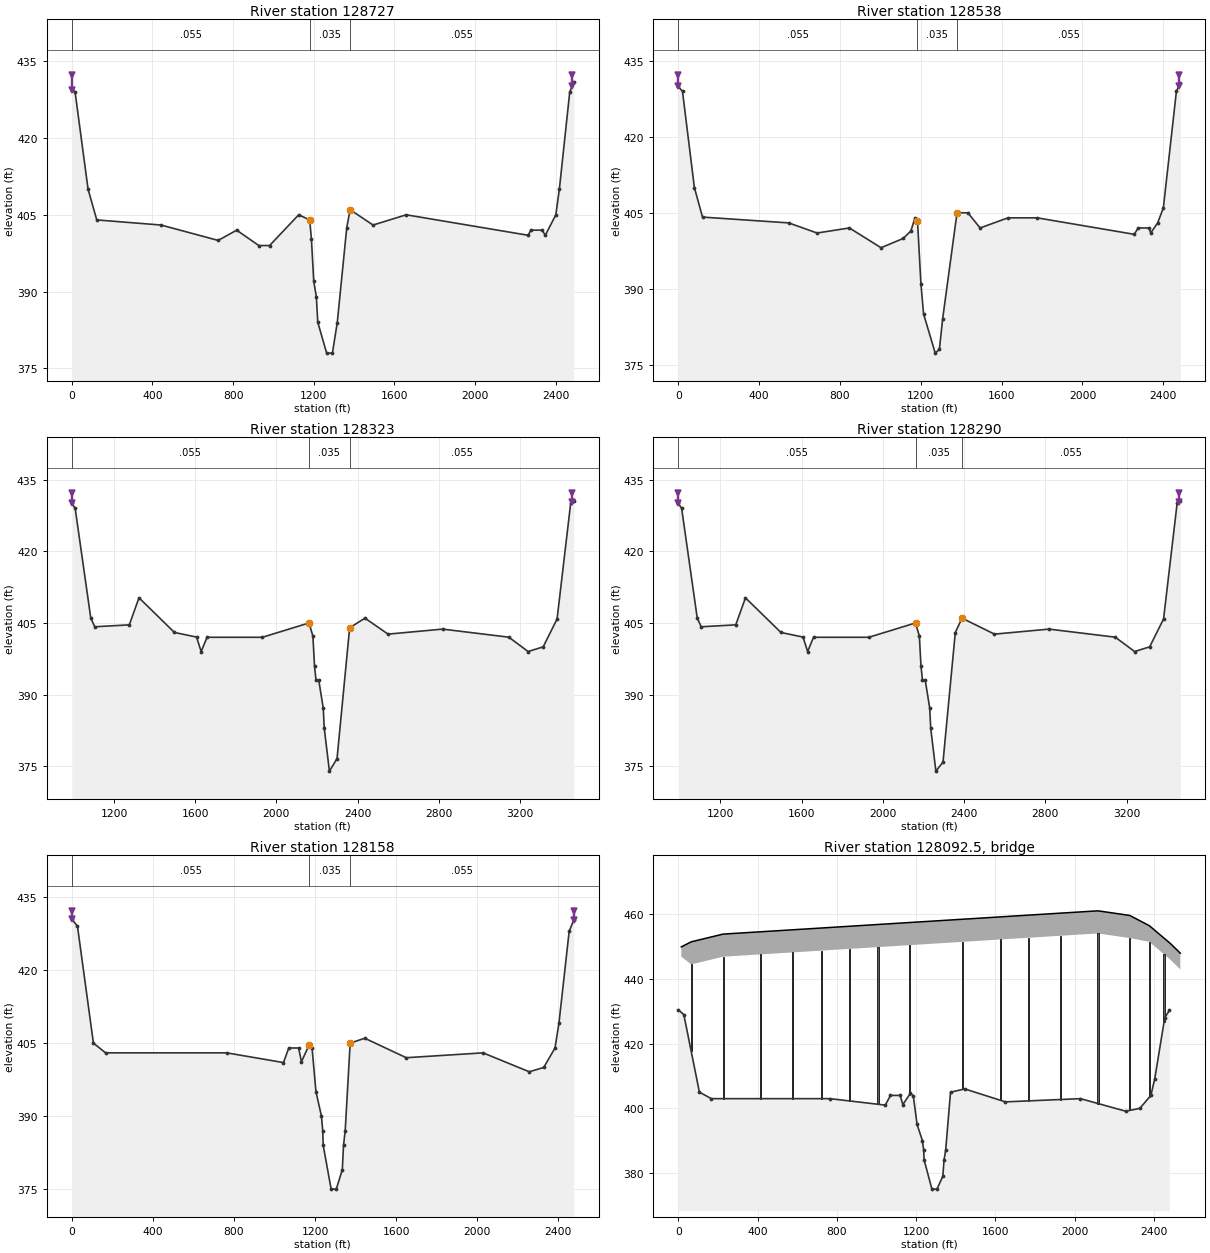
Type RM Length L Ch R = 1 ,128727  ,189,192,193
BEGIN DESCRIPTION:
This cross section corresponds to cross section 128727 of the non-georeferenced CDC model which was the source of this model.
END DESCRIPTION:
XS GIS Cut Line= 2
2480040.092445496975795.140357052478848.293319916973609.11192071
#Sta/Elev= 30
       0  429.42   16.35     429    80.8     410  123.95     404  442.89     403
  725.92     400  817.82     402  927.52     399  980.99     399 1125.34     405
  1179.8     404 1188.28  400.37 1199.99     392 1212.95     389 1219.89  384.04
 1263.99     378 1292.43     378 1316.52  383.94 1363.62  402.48 1380.36     406
 1494.01     403  1658.6     405  2263.7     401 2276.34     402 2332.57     402
  2348.2     401 2400.46     405 2417.96     410 2469.48  428.98  2489.8  430.96
#Mann= 3 ,0,0
       0    .055       0  1179.8    .035       0 1380.36    .055       0
Levee=-1,0,432.32,-1,2482,432.32,,
#XS Ineff= 2 , 0
          1179.8     404 1380.36             406
Permanent Ineff=
       F       F
#XS Lid=6
     920  428.46  423.06   921.7  428.46  423.06  921.71  428.46  427.76
  954.29  428.46  427.76   954.3  428.46  423.06     956  428.46  423.06
Bank Sta=1179.8,1380.36
XS Rating Curve= 0 ,0
Exp/Cntr=0.3,0.1

Type RM Length L Ch R = 1 ,128538  ,215,215,215
BEGIN DESCRIPTION:
This cross section corresponds to cross section 128538 of the non-georeferenced CDC model which was the source of this model.
END DESCRIPTION:
XS GIS Cut Line= 2
2480194.010116676975692.73570621  2479016.9901616973505.26468746
#Sta/Elev= 30
       0     430   21.11     429   79.81     410  120.15  404.15  546.76     403
  686.84     401  846.77     402 1003.47  398.09 1113.14  399.93 1150.96   401.4
 1171.33     404 1183.73  403.41 1200.62     391 1213.77     385 1271.52  377.25
  1292.1     378 1308.07     384 1379.35     405 1433.16     405 1493.37     402
 1631.27     404 1775.99     404 2256.18  400.74 2275.59     402 2329.77     402
 2337.53     401 2371.99     403 2400.24     406 2464.62     429 2484.03  430.67
#Mann= 3 ,0,0
       0    .055       0 1183.73    .035       0 1379.35    .055       0
Levee=-1,0,432.28,-1,2477,432.28,,
#XS Ineff= 2 , 0
         1183.73  403.41 1379.35             405
Permanent Ineff=
       F       F
#XS Lid=6
     920  437.81  432.41   921.7  437.81  432.41  921.71  437.81  437.11
  954.29  437.81  437.11   954.3  437.81  432.41     956  437.81  432.41
Bank Sta=1183.73,1379.35
XS Rating Curve= 0 ,0
Exp/Cntr=0.3,0.1

Type RM Length L Ch R = 1 ,128323  ,32,32,32
BEGIN DESCRIPTION:
This cross section corresponds to cross section 128323 of the non-georeferenced CDC model which was the source of this model.
END DESCRIPTION:
XS GIS Cut Line= 2
2480363.676443996975597.635502712479225.499258436973402.20091721
#Sta/Elev= 30
     992     430 1008.69     429 1085.67     406 1105.34   404.2 1275.33   404.6
 1323.13  410.26 1497.72  403.01 1606.67  402.04 1629.28  399.02  1658.4     402
 1930.85     402 2160.62     405 2179.65  402.24 2187.59     396 2195.06     393
 2208.68     393 2230.73  387.15 2235.47     383    2261     374 2298.57  376.62
 2360.66     404 2436.32     406 2549.65  402.66 2818.43  403.71 3144.73  402.02
 3239.76  399.02  3313.9     400 3382.39  405.83 3449.18     430 3464.93  430.44
#Mann= 3 ,0,0
     992    .055       0 2160.62    .035       0 2360.66    .055       0
Levee=-1,992,432.22,-1,3458,432.22,,
#XS Ineff= 2 , 0
         2160.62     405 2360.66             404
Permanent Ineff=
       F       F
#XS Lid=6
    1886  448.21  442.81  1887.7  448.21  442.81 1887.71  448.21  447.51
 1920.29  448.21  447.51  1920.3  448.21  442.81    1922  448.21  442.81
Bank Sta=2160.62,2360.66
XS Rating Curve= 0 ,0
Exp/Cntr=0.3,0.1

Type RM Length L Ch R = 1 ,128290  ,218,219,218
BEGIN DESCRIPTION:
This cross section corresponds to cross section 128290 of the non-georeferenced CDC model which was the source of this model.
END DESCRIPTION:
XS GIS Cut Line= 2
2480392.127502596975582.894062392479254.234437176973387.31183939
#Sta/Elev= 30
     992     430 1008.69     429 1085.67     406 1105.34   404.2 1275.33   404.6
 1323.13  410.26 1497.72  403.01 1606.67  402.04 1629.28  399.02  1658.4     402
 1930.85     402 2160.62     405 2179.65  402.24 2187.59     396 2195.06     393
 2208.68     393 2230.73  387.15 2235.47     383    2261     374 2296.08  375.89
 2356.63     403 2389.79     406 2549.65  402.66 2818.43  403.71 3144.73  402.02
 3239.76  399.02  3313.9     400 3382.39  405.83 3449.18     430 3464.93  430.44
#Mann= 3 ,0,0
     992    .055       0 2160.62    .035       0 2389.79    .055       0
Levee=-1,992,432.22,-1,3458,432.22,,
#XS Ineff= 2 , 0
         2160.62     405 2389.79             406
Permanent Ineff=
       F       F
#XS Lid=6
    1886  449.91  444.51  1887.7  449.91  444.51 1887.71  449.91  449.21
 1920.29  449.91  449.21  1920.3  449.91  444.51    1922  449.91  444.51
Bank Sta=2160.62,2389.79
XS Rating Curve= 0 ,0
Exp/Cntr=0.3,0.1

Type RM Length L Ch R = 1 ,128158  ,131,131,131
BEGIN DESCRIPTION:
This cross section corresponds to cross section 128158 of the non-georeferenced CDC model which was the source of this model.
END DESCRIPTION:
XS GIS Cut Line= 2
      2480588.63     6975486.541     2479448.447     6973287.122
#Sta/Elev= 30
       0  430.51   28.18     429  106.81     405  166.88     403  764.72     403
 1044.68     401 1070.78     404 1119.52     404 1133.25  401.17 1171.17  404.63
  1185.8  403.91 1204.96     395 1231.97     390 1238.34     387 1240.51  384.04
  1279.8     375 1305.21     375 1334.98     379  1340.9     384 1349.17     387
  1373.7     405 1445.75     406 1650.53     402 2029.21     403  2257.5  399.11
 2328.76     400 2384.51     404 2404.03  409.15 2454.32  427.98 2477.39  430.31
#Mann= 3 ,0,0
       0    .055       0 1171.17    .035       0  1373.7    .055       0
Levee=-1,0,432.18,-1,2477,432.18,,
#XS Ineff= 2 , 0
         1171.17  404.63  1373.7             405
Permanent Ineff=
       F       F
#XS Lid=6
     920  455.47  450.07   921.7  455.47  450.07  921.71  455.47  454.77
  954.29  455.47  454.77   954.3  455.47  450.07     956  455.47  450.07
Bank Sta=1171.17,1373.7
XS Rating Curve= 0 ,0
Exp/Cntr=0.3,0.1

Type RM Length L Ch R = 3 ,128092.5,,,
BEGIN DESCRIPTION:
Sylvan Avenue Bridge
END DESCRIPTION:
Node Name=Sylvan Avenue
Bridge Culvert--1,0,-1,-1, 0
Deck Dist Width WeirC Skew NumUp NumDn MinLoCord MaxHiCord MaxSubmerge Is_Ogee
7,117,2.6,0, 18, 18, , , 0.98, 0, 0,0,,
    15.5    65.5   226.5     416     577     721     865    1009  1198.5  1435.5
    1625    1767    1928  2117.5  2277.5    2377    2483    2533
  449.96  451.53  453.92  454.64  455.25   455.8  456.35   456.9  457.62  458.52
  459.25  459.79   460.4  461.12   459.7  456.51     451  448.01
  446.96  444.53  446.92  447.64  448.25   448.8  449.35   449.9  450.62  451.52
  452.25  452.79   453.4  454.12   452.7  451.51     446  443.01
   970.5  1020.5  1181.5    1371    1532    1676    1820    1964  2153.5  2390.5
    2580    2722    2883  3072.5  3232.5    3332    3438    3490
  449.96  451.53  453.92  454.64  455.25   455.8  456.35   456.9  457.62  458.52
  459.25  459.79   460.4  461.12   459.7  456.51     451  448.01
  446.96  444.53  446.92  447.64  448.25   448.8  449.35   449.9  450.62  451.52
  452.25  452.79   453.4  454.12   452.7  451.51     446  443.01
Pier Skew, UpSta & Num, DnSta & Num=  ,65.5, 2 ,1020.5, 2 , 0 , 0 , 0 ,,
       6       6
       0     446
       6       6
       0     446
Pier Skew, UpSta & Num, DnSta & Num=  ,226.5, 2 ,1181.5, 2 , 0 , 0 , 0 ,,
       6       6
       0     448
       6       6
       0     448
Pier Skew, UpSta & Num, DnSta & Num=  ,416, 2 ,1371, 2 , 0 , 0 , 0 ,,
       6       6
       0     449
       6       6
       0     449
Pier Skew, UpSta & Num, DnSta & Num=  ,577, 2 ,1532, 2 , 0 , 0 , 0 ,,
       6       6
       0     450
       6       6
       0     450
Pier Skew, UpSta & Num, DnSta & Num=  ,721, 2 ,1676, 2 , 0 , 0 , 0 ,,
       6       6
       0     450
       6       6
       0     450
Pier Skew, UpSta & Num, DnSta & Num=  ,865, 2 ,1820, 2 , 0 , 0 , 0 ,,
       6       6
       0     450
       6       6
       0     450
Pier Skew, UpSta & Num, DnSta & Num=  ,1009, 2 ,1964, 2 , 0 , 0 , 0 ,,
       8       8
       0     451
       8       8
       0     451
Pier Skew, UpSta & Num, DnSta & Num=  ,1165, 2 ,2124, 2 , 0 , 0 , 0 ,,
       6       6
       0     451
       6       6
       0     451
Pier Skew, UpSta & Num, DnSta & Num=  ,1435.5, 2 ,2390.5, 2 , 0 , 0 , 0 ,,
       6       6
       0     452
       6       6
       0     452
Pier Skew, UpSta & Num, DnSta & Num=  ,1625, 2 ,2580, 2 , 0 , 0 , 0 ,,
       8       8
       0     453
       8       8
       0     453
Pier Skew, UpSta & Num, DnSta & Num=  ,1767, 2 ,2722, 2 , 0 , 0 , 0 ,,
       6       6
       0     453
       6       6
       0     453
Pier Skew, UpSta & Num, DnSta & Num=  ,1928, 2 ,2883, 2 , 0 , 0 , 0 ,,
       6       6
       0     454
       6       6
       0     454
Pier Skew, UpSta & Num, DnSta & Num=  ,2117.5, 2 ,3072.5, 2 , 0 , 0 , 0 ,,
       6       6
       0     455
       6       6
       0     455
Pier Skew, UpSta & Num, DnSta & Num=  ,2277.5, 2 ,3232.5, 2 , 0 , 0 , 0 ,,
       6       6
       0     455
       6       6
       0     455
Pier Skew, UpSta & Num, DnSta & Num=  ,2377, 2 ,3332, 2 , 0 , 0 , 0 ,,
       6       6
       0     453
       6       6
       0     453
Pier Skew, UpSta & Num, DnSta & Num=  ,2451, 2 ,3410, 2 , 0 , 0 , 0 ,,
       6       6
       0     450
       6       6
       0     450
BR Coef=-1 , 0 , 0 ,, 0 ,,,0.8,-1,,0,
WSPro=,,,, 1 ,,,, 0 ,,,, 0 ,,,,-1 ,-1 ,-1 , 0 , 0 , 0 , 0 , 0
BC Design=,, 0 ,, 0 ,,,,,,
BC Use User HTab Curves=0
BC User HTab FreeFlow(D)= 0