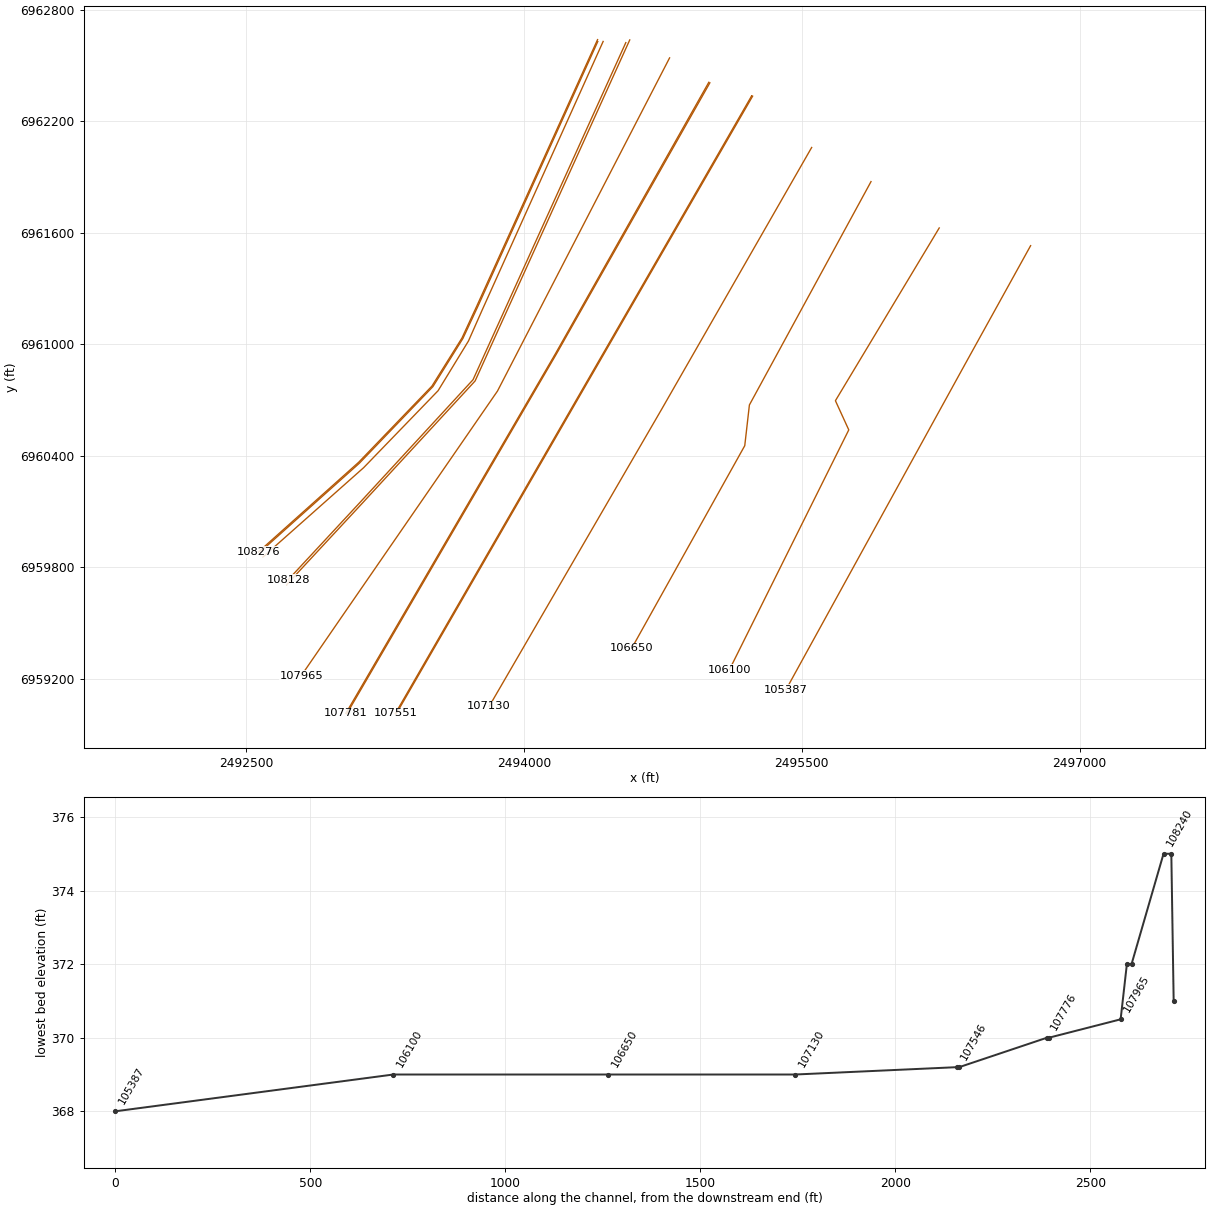
HEC-RAS study CDC_Consolidated_Model.prj: Upper Trinity CDC Consolidated Model

--- CDC_Consolidated_Model.g12 (geometry) --- (continued)

Type RM Length L Ch R = 3 ,108287  ,,,
BEGIN DESCRIPTION:
This cross section corresponds to cross section 108287  Abandoned Atchinson, Topeka, and Santa Fe Railroad bridge and includes modifications for the CDC DAL010909-1 Sante Fe Trestle Trail. of the non-georeferenced CDC model which was the source of this model.
END DESCRIPTION:
Node Name=ATSF Railroad
Bridge Culvert--1,0,-1,-1, 0
Deck Dist Width WeirC Skew NumUp NumDn MinLoCord MaxHiCord MaxSubmerge Is_Ogee
1,20,2.6,0, 77, 77, , , 0.95, 0, ,,,
    1000    1200    2010    2010    2010    2058    2058    2058    2105  2212.5
  2319.5  2319.5    2414    2414    2418    2418    2419    2419    2440    2440
    2441    2441    2462    2462    2463    2463    2484    2484    2485    2485
    2506    2506    2507    2507    2528    2528    2529    2529    2550    2550
    2551    2551    2572    2572    2573    2573    2594    2594    2595    2595
    2616    2616    2617    2617    2622    2622    2715    2715    2725    2725
    2745    2745    2802    2802    2890    2962    3000    3042    3114    3197
    3255    3825    3855    3855    3855    4300    4300
   422.2   422.7   422.7   422.7  427.95  427.95   422.7  421.97  423.71  427.95
  427.95  427.95  427.95  427.95  427.95     435     435  427.95  427.95     435
     435  427.95  427.95     435     435  427.95  427.95     435     435  427.95
  427.95     435     435  427.95  427.95     435     435  427.95  427.95     435
     435  427.95  427.95     435     435  427.95  427.95     435     435  427.95
  427.95     435     435  427.95  427.95  427.95  427.95  427.95  427.95     435
     435   422.6   422.6   422.6   422.9   422.9     423   423.1   423.3   423.2
     423   422.9   422.9   422.9  427.95  427.95   422.9
   419.5     420     420   422.7  427.95  427.95   422.7  416.47  418.21  422.45
  422.45  419.17  419.17     417     417     417     417     417     417     417
     417     417     417     417     417     417     417     417     417     417
     417     417     417     417     417     417     417     417     417     417
     417     417     417     417     417     417     417     417     417     417
     417     417     417     417     417  420.72  420.72  420.72  420.72     435
     435     420     420   422.6   422.9   422.9     423   423.1   423.3   423.2
     420     420     420   422.9  427.95  427.95   422.9
    1000    1200    2010    2010    2010    2058    2058    2058    2105  2212.5
  2319.5  2319.5    2414    2414    2418    2418    2419    2419    2440    2440
    2441    2441    2462    2462    2463    2463    2484    2484    2485    2485
    2506    2506    2507    2507    2528    2528    2529    2529    2550    2550
    2551    2551    2572    2572    2573    2573    2594    2594    2595    2595
    2616    2616    2617    2617    2622    2622    2715    2715    2725    2725
    2745    2745    2802    2802    2890    2962    3000    3042    3114    3197
    3255    3825    3855    3855    3855    4300    4300
   422.2   422.7   422.7   422.7  427.95  427.95   422.7  421.97  423.71  427.95
  427.95  427.95  427.95  427.95  427.95     435     435  427.95  427.95     435
     435  427.95  427.95     435     435  427.95  427.95     435     435  427.95
  427.95     435     435  427.95  427.95     435     435  427.95  427.95     435
     435  427.95  427.95     435     435  427.95  427.95     435     435  427.95
  427.95     435     435  427.95  427.95  427.95  427.95  427.95  427.95     435
     435   422.6   422.6   422.6   422.9   422.9     423   423.1   423.3   423.2
     423   422.9   422.9   422.9  427.95  427.95   422.9
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Pier Skew, UpSta & Num, DnSta & Num=  ,1014, 2 ,1014, 2 , 0 , 0 , 0 ,,
     1.3     1.3
       0     500
     1.3     1.3
       0     500
Pier Skew, UpSta & Num, DnSta & Num=  ,1028, 2 ,1028, 2 , 0 , 0 , 0 ,,
     1.3     1.3
     360     421
     1.3     1.3
     360     421
Pier Skew, UpSta & Num, DnSta & Num=  ,1042, 2 ,1042, 2 , 0 , 0 , 0 ,,
     1.3     1.3
     360     421
     1.3     1.3
     360     421
Pier Skew, UpSta & Num, DnSta & Num=  ,1056, 2 ,1056, 2 , 0 , 0 , 0 ,,
     1.3     1.3
     370     421
     1.3     1.3
     370     421
Pier Skew, UpSta & Num, DnSta & Num=  ,1070, 2 ,1070, 2 , 0 , 0 , 0 ,,
     1.3     1.3
     360     421
     1.3     1.3
     360     421
Pier Skew, UpSta & Num, DnSta & Num=  ,1084, 2 ,1084, 2 , 0 , 0 , 0 ,,
     1.3     1.3
     370     421
     1.3     1.3
     370     421
Pier Skew, UpSta & Num, DnSta & Num=  ,1098, 2 ,1098, 2 , 0 , 0 , 0 ,,
     1.3     1.3
     360     421
     1.3     1.3
     360     421
Pier Skew, UpSta & Num, DnSta & Num=  ,1112, 2 ,1112, 2 , 0 , 0 , 0 ,,
     1.3     1.3
     370     421
     1.3     1.3
     370     421
Pier Skew, UpSta & Num, DnSta & Num=  ,1126, 2 ,1126, 2 , 0 , 0 , 0 ,,
     1.3     1.3
     360     421
     1.3     1.3
     360     421
Pier Skew, UpSta & Num, DnSta & Num=  ,1140, 2 ,1140, 2 , 0 , 0 , 0 ,,
     1.3     1.3
     370     421
     1.3     1.3
     370     421
Pier Skew, UpSta & Num, DnSta & Num=  ,1154, 2 ,1154, 2 , 0 , 0 , 0 ,,
     1.3     1.3
     360     421
     1.3     1.3
     360     421
Pier Skew, UpSta & Num, DnSta & Num=  ,1168, 2 ,1168, 2 , 0 , 0 , 0 ,,
     1.3     1.3
     370     421
     1.3     1.3
     370     421
Pier Skew, UpSta & Num, DnSta & Num=  ,1182, 2 ,1182, 2 , 0 , 0 , 0 ,,
     1.3     1.3
     370     421
     1.3     1.3
     370     421
Pier Skew, UpSta & Num, DnSta & Num=  ,1196, 2 ,1196, 2 , 0 , 0 , 0 ,,
     1.3     1.3
     370     421
     1.3     1.3
     370     421
Pier Skew, UpSta & Num, DnSta & Num=  ,1210, 2 ,1210, 2 , 0 , 0 , 0 ,,
     1.3     1.3
     370     421
     1.3     1.3
     370     421
Pier Skew, UpSta & Num, DnSta & Num=  ,1224, 2 ,1224, 2 , 0 , 0 , 0 ,,
     1.3     1.3
     370     421
     1.3     1.3
     370     421
Pier Skew, UpSta & Num, DnSta & Num=  ,1238, 2 ,1238, 2 , 0 , 0 , 0 ,,
     1.3     1.3
     370     421
     1.3     1.3
     370     421
Pier Skew, UpSta & Num, DnSta & Num=  ,1252, 2 ,1252, 2 , 0 , 0 , 0 ,,
     1.3     1.3
     370     421
     1.3     1.3
     370     421
Pier Skew, UpSta & Num, DnSta & Num=  ,1266, 2 ,1266, 2 , 0 , 0 , 0 ,,
     1.3     1.3
     370     421
     1.3     1.3
     370     421
Pier Skew, UpSta & Num, DnSta & Num=  ,1280, 2 ,1280, 2 , 0 , 0 , 0 ,,
     1.3     1.3
     370     421
     1.3     1.3
     370     421
Pier Skew, UpSta & Num, DnSta & Num=  ,1294, 2 ,1294, 2 , 0 , 0 , 0 ,,
     1.3     1.3
     370     421
     1.3     1.3
     370     421
Pier Skew, UpSta & Num, DnSta & Num=  ,1308, 2 ,1308, 2 , 0 , 0 , 0 ,,
     1.3     1.3
     370     421
     1.3     1.3
     370     421
Pier Skew, UpSta & Num, DnSta & Num=  ,1322, 2 ,1322, 2 , 0 , 0 , 0 ,,
     1.3     1.3
     370     421
     1.3     1.3
     370     421
Pier Skew, UpSta & Num, DnSta & Num=  ,1336, 2 ,1336, 2 , 0 , 0 , 0 ,,
     1.3     1.3
     370     421
     1.3     1.3
     370     421
Pier Skew, UpSta & Num, DnSta & Num=  ,1350, 2 ,1350, 2 , 0 , 0 , 0 ,,
     1.3     1.3
     370     421
     1.3     1.3
     370     421
Pier Skew, UpSta & Num, DnSta & Num=  ,1364, 2 ,1364, 2 , 0 , 0 , 0 ,,
     1.3     1.3
     370     421
     1.3     1.3
     370     421
Pier Skew, UpSta & Num, DnSta & Num=  ,1378, 2 ,1378, 2 , 0 , 0 , 0 ,,
     1.3     1.3
     370     421
     1.3     1.3
     370     421
Pier Skew, UpSta & Num, DnSta & Num=  ,1392, 2 ,1392, 2 , 0 , 0 , 0 ,,
     1.3     1.3
     370     421
     1.3     1.3
     370     421
Pier Skew, UpSta & Num, DnSta & Num=  ,1406, 2 ,1406, 2 , 0 , 0 , 0 ,,
     1.3     1.3
     370     421
     1.3     1.3
     370     421
Pier Skew, UpSta & Num, DnSta & Num=  ,1420, 2 ,1420, 2 , 0 , 0 , 0 ,,
     1.3     1.3
     370     421
     1.3     1.3
     370     421
Pier Skew, UpSta & Num, DnSta & Num=  ,1434, 2 ,1434, 2 , 0 , 0 , 0 ,,
     1.3     1.3
     370     421
     1.3     1.3
     370     421
Pier Skew, UpSta & Num, DnSta & Num=  ,1448, 2 ,1448, 2 , 0 , 0 , 0 ,,
     1.3     1.3
     370     421
     1.3     1.3
     370     421
Pier Skew, UpSta & Num, DnSta & Num=  ,1462, 2 ,1462, 2 , 0 , 0 , 0 ,,
     1.3     1.3
     370     421
     1.3     1.3
     370     421
Pier Skew, UpSta & Num, DnSta & Num=  ,1476, 2 ,1476, 2 , 0 , 0 , 0 ,,
     1.3     1.3
     370     421
     1.3     1.3
     370     421
Pier Skew, UpSta & Num, DnSta & Num=  ,1490, 2 ,1490, 2 , 0 , 0 , 0 ,,
     1.3     1.3
     370     421
     1.3     1.3
     370     421
Pier Skew, UpSta & Num, DnSta & Num=  ,1504, 2 ,1504, 2 , 0 , 0 , 0 ,,
     1.3     1.3
     370     421
     1.3     1.3
     370     421
Pier Skew, UpSta & Num, DnSta & Num=  ,1518, 2 ,1518, 2 , 0 , 0 , 0 ,,
     1.3     1.3
     370     421
     1.3     1.3
     370     421
Pier Skew, UpSta & Num, DnSta & Num=  ,1532, 2 ,1532, 2 , 0 , 0 , 0 ,,
     1.3     1.3
     370     421
     1.3     1.3
     370     421
Pier Skew, UpSta & Num, DnSta & Num=  ,1546, 2 ,1546, 2 , 0 , 0 , 0 ,,
     1.3     1.3
     370     421
     1.3     1.3
     370     421
Pier Skew, UpSta & Num, DnSta & Num=  ,1560, 2 ,1560, 2 , 0 , 0 , 0 ,,
     1.3     1.3
     370     421
     1.3     1.3
     370     421
Pier Skew, UpSta & Num, DnSta & Num=  ,1574, 2 ,1574, 2 , 0 , 0 , 0 ,,
     1.3     1.3
     370     421
     1.3     1.3
     370     421
Pier Skew, UpSta & Num, DnSta & Num=  ,1588, 2 ,1588, 2 , 0 , 0 , 0 ,,
     1.3     1.3
     370     421
     1.3     1.3
     370     421
Pier Skew, UpSta & Num, DnSta & Num=  ,1602, 2 ,1602, 2 , 0 , 0 , 0 ,,
     1.3     1.3
     370     421
     1.3     1.3
     370     421
Pier Skew, UpSta & Num, DnSta & Num=  ,1616, 2 ,1616, 2 , 0 , 0 , 0 ,,
     1.3     1.3
     370     421
     1.3     1.3
     370     421
Pier Skew, UpSta & Num, DnSta & Num=  ,1630, 2 ,1630, 2 , 0 , 0 , 0 ,,
     1.3     1.3
     370     421
     1.3     1.3
     370     421
Pier Skew, UpSta & Num, DnSta & Num=  ,1644, 2 ,1644, 2 , 0 , 0 , 0 ,,
     1.3     1.3
     370     421
     1.3     1.3
     370     421
Pier Skew, UpSta & Num, DnSta & Num=  ,1658, 2 ,1658, 2 , 0 , 0 , 0 ,,
     1.3     1.3
     370     421
     1.3     1.3
     370     421
Pier Skew, UpSta & Num, DnSta & Num=  ,1672, 2 ,1672, 2 , 0 , 0 , 0 ,,
     1.3     1.3
     370     421
     1.3     1.3
     370     421
Pier Skew, UpSta & Num, DnSta & Num=  ,1686, 2 ,1686, 2 , 0 , 0 , 0 ,,
     1.3     1.3
     370     421
     1.3     1.3
     370     421
Pier Skew, UpSta & Num, DnSta & Num=  ,1700, 2 ,1700, 2 , 0 , 0 , 0 ,,
     1.3     1.3
     370     421
     1.3     1.3
     370     421
Pier Skew, UpSta & Num, DnSta & Num=  ,1714, 2 ,1714, 2 , 0 , 0 , 0 ,,
     1.3     1.3
     370     421
     1.3     1.3
     370     421
Pier Skew, UpSta & Num, DnSta & Num=  ,1728, 2 ,1728, 2 , 0 , 0 , 0 ,,
     1.3     1.3
     370     421
     1.3     1.3
     370     421
Pier Skew, UpSta & Num, DnSta & Num=  ,1742, 2 ,1742, 2 , 0 , 0 , 0 ,,
     1.3     1.3
     370     421
     1.3     1.3
     370     421
Pier Skew, UpSta & Num, DnSta & Num=  ,1756, 2 ,1756, 2 , 0 , 0 , 0 ,,
     1.3     1.3
     370     421
     1.3     1.3
     370     421
Pier Skew, UpSta & Num, DnSta & Num=  ,1770, 2 ,1770, 2 , 0 , 0 , 0 ,,
     1.3     1.3
     370     421
     1.3     1.3
     370     421
Pier Skew, UpSta & Num, DnSta & Num=  ,1784, 2 ,1784, 2 , 0 , 0 , 0 ,,
     1.3     1.3
     370     421
     1.3     1.3
     370     421
Pier Skew, UpSta & Num, DnSta & Num=  ,1798, 2 ,1798, 2 , 0 , 0 , 0 ,,
     1.3     1.3
     370     421
     1.3     1.3
     370     421
Pier Skew, UpSta & Num, DnSta & Num=  ,1812, 2 ,1812, 2 , 0 , 0 , 0 ,,
     1.3     1.3
     370     421
     1.3     1.3
     370     421
Pier Skew, UpSta & Num, DnSta & Num=  ,1826, 2 ,1826, 2 , 0 , 0 , 0 ,,
     1.3     1.3
     370     421
     1.3     1.3
     370     421
Pier Skew, UpSta & Num, DnSta & Num=  ,1840, 2 ,1840, 2 , 0 , 0 , 0 ,,
     1.3     1.3
     370     421
     1.3     1.3
     370     421
Pier Skew, UpSta & Num, DnSta & Num=  ,1854, 2 ,1854, 2 , 0 , 0 , 0 ,,
     1.3     1.3
     370     421
     1.3     1.3
     370     421
Pier Skew, UpSta & Num, DnSta & Num=  ,1868, 2 ,1868, 2 , 0 , 0 , 0 ,,
     1.3     1.3
     370     421
     1.3     1.3
     370     421
Pier Skew, UpSta & Num, DnSta & Num=  ,1882, 2 ,1882, 2 , 0 , 0 , 0 ,,
     1.3     1.3
     370     421
     1.3     1.3
     370     421
Pier Skew, UpSta & Num, DnSta & Num=  ,1896, 2 ,1896, 2 , 0 , 0 , 0 ,,
     1.3     1.3
     370     421
     1.3     1.3
     370     421
Pier Skew, UpSta & Num, DnSta & Num=  ,1910, 2 ,1910, 2 , 0 , 0 , 0 ,,
     1.3     1.3
     370     421
     1.3     1.3
     370     421
Pier Skew, UpSta & Num, DnSta & Num=  ,1924, 2 ,1924, 2 , 0 , 0 , 0 ,,
     1.3     1.3
     370     421
     1.3     1.3
     370     421
Pier Skew, UpSta & Num, DnSta & Num=  ,1938, 2 ,1938, 2 , 0 , 0 , 0 ,,
     1.3     1.3
     370     421
     1.3     1.3
     370     421
Pier Skew, UpSta & Num, DnSta & Num=  ,1952, 2 ,1952, 2 , 0 , 0 , 0 ,,
     1.3     1.3
     370     421
     1.3     1.3
     370     421
Pier Skew, UpSta & Num, DnSta & Num=  ,1966, 2 ,1966, 2 , 0 , 0 , 0 ,,
     1.3     1.3
     370     421
     1.3     1.3
     370     421
Pier Skew, UpSta & Num, DnSta & Num=  ,1980, 2 ,1980, 2 , 0 , 0 , 0 ,,
     1.3     1.3
     370     421
     1.3     1.3
     370     421
Pier Skew, UpSta & Num, DnSta & Num=  ,1994, 2 ,1994, 2 , 0 , 0 , 0 ,,
     1.3     1.3
     370     421
     1.3     1.3
     370     421
Pier Skew, UpSta & Num, DnSta & Num=  ,2008, 2 ,2008, 2 , 0 , 0 , 0 ,,
     1.3     1.3
     370     421
     1.3     1.3
     370     421
Pier Skew, UpSta & Num, DnSta & Num=  ,2061.5, 2 ,2061.5, 2 , 0 , 0 , 0 ,,
       4       4
     370     421
       4       4
     370     421
Pier Skew, UpSta & Num, DnSta & Num=  ,2078, 2 ,2078, 2 , 0 , 0 , 0 ,,
     1.3     1.3
     370     421
     1.3     1.3
     370     421
Pier Skew, UpSta & Num, DnSta & Num=  ,2092, 2 ,2092, 2 , 0 , 0 , 0 ,,
     1.3     1.3
     370     421
     1.3     1.3
     370     421
Pier Skew, UpSta & Num, DnSta & Num=  ,2105, 2 ,2105, 2 , 0 , 0 , 0 ,,
       4       4
     370     421
       4       4
     370     421
Pier Skew, UpSta & Num, DnSta & Num=  ,2120, 2 ,2120, 2 , 0 , 0 , 0 ,,
     1.3     1.3
     370     421
     1.3     1.3
     370     421
Pier Skew, UpSta & Num, DnSta & Num=  ,2134, 2 ,2134, 2 , 0 , 0 , 0 ,,
     1.3     1.3
     370     421
     1.3     1.3
     370     421
Pier Skew, UpSta & Num, DnSta & Num=  ,2148, 2 ,2148, 2 , 0 , 0 , 0 ,,
     1.3     1.3
     370     421
     1.3     1.3
     370     421
Pier Skew, UpSta & Num, DnSta & Num=  ,2162, 2 ,2162, 2 , 0 , 0 , 0 ,,
     1.3     1.3
     370     421
     1.3     1.3
     370     421
Pier Skew, UpSta & Num, DnSta & Num=  ,2176, 2 ,2176, 2 , 0 , 0 , 0 ,,
     1.3     1.3
     370     421
     1.3     1.3
     370     421
Pier Skew, UpSta & Num, DnSta & Num=  ,2190, 2 ,2190, 2 , 0 , 0 , 0 ,,
     1.3     1.3
     370     423
     1.3     1.3
     370     423
Pier Skew, UpSta & Num, DnSta & Num=  ,2204, 2 ,2204, 2 , 0 , 0 , 0 ,,
     1.3     1.3
     370     423
     1.3     1.3
     370     423
Pier Skew, UpSta & Num, DnSta & Num=  ,2212.5, 2 ,2212.5, 2 , 0 , 0 , 0 ,,
       4       4
     370     423
       4       4
     370     423
Pier Skew, UpSta & Num, DnSta & Num=  ,2232, 2 ,2232, 2 , 0 , 0 , 0 ,,
     1.3     1.3
     370     423
     1.3     1.3
     370     423
Pier Skew, UpSta & Num, DnSta & Num=  ,2246, 2 ,2246, 2 , 0 , 0 , 0 ,,
     1.3     1.3
     370     423
     1.3     1.3
     370     423
Pier Skew, UpSta & Num, DnSta & Num=  ,2260, 2 ,2260, 2 , 0 , 0 , 0 ,,
     1.3     1.3
     370     423
     1.3     1.3
     370     423
Pier Skew, UpSta & Num, DnSta & Num=  ,2274, 2 ,2274, 2 , 0 , 0 , 0 ,,
     1.3     1.3
     370     423
     1.3     1.3
     370     423
Pier Skew, UpSta & Num, DnSta & Num=  ,2288, 2 ,2288, 2 , 0 , 0 , 0 ,,
     1.3     1.3
     370     423
     1.3     1.3
     370     423
Pier Skew, UpSta & Num, DnSta & Num=  ,2302, 2 ,2302, 2 , 0 , 0 , 0 ,,
     1.3     1.3
     370     423
     1.3     1.3
     370     423
Pier Skew, UpSta & Num, DnSta & Num=  ,2319.5, 2 ,2319.5, 2 , 0 , 0 , 0 ,,
       4       4
     370     423
       4       4
     370     423
Pier Skew, UpSta & Num, DnSta & Num=  ,2330, 2 ,2330, 2 , 0 , 0 , 0 ,,
     1.3     1.3
     370     421
     1.3     1.3
     370     421
Pier Skew, UpSta & Num, DnSta & Num=  ,2344, 2 ,2344, 2 , 0 , 0 , 0 ,,
     1.3     1.3
     370     421
     1.3     1.3
     370     421
Pier Skew, UpSta & Num, DnSta & Num=  ,2358, 2 ,2358, 2 , 0 , 0 , 0 ,,
     1.3     1.3
     370     421
     1.3     1.3
     370     421
Pier Skew, UpSta & Num, DnSta & Num=  ,2372, 2 ,2372, 2 , 0 , 0 , 0 ,,
     1.3     1.3
     370     421
     1.3     1.3
     370     421
Pier Skew, UpSta & Num, DnSta & Num=  ,2386, 2 ,2386, 2 , 0 , 0 , 0 ,,
     1.3     1.3
     370     421
     1.3     1.3
     370     421
Pier Skew, UpSta & Num, DnSta & Num=  ,2400, 2 ,2400, 2 , 0 , 0 , 0 ,,
     1.3     1.3
     370     421
     1.3     1.3
     370     421
Pier Skew, UpSta & Num, DnSta & Num=  ,2418, 2 ,2418, 2 , 0 , 0 , 0 ,,
       8       8
     370     421
       8       8
     370     421
Pier Skew, UpSta & Num, DnSta & Num=  ,2618, 2 ,2618, 2 , 0 , 0 , 0 ,,
       8       8
     370     421
       8       8
     370     421
Pier Skew, UpSta & Num, DnSta & Num=  ,2636, 2 ,2636, 2 , 0 , 0 , 0 ,,
     1.3     1.3
     370     421
     1.3     1.3
     370     421
Pier Skew, UpSta & Num, DnSta & Num=  ,2650, 2 ,2650, 2 , 0 , 0 , 0 ,,
     1.3     1.3
     370     421
     1.3     1.3
     370     421
Pier Skew, UpSta & Num, DnSta & Num=  ,2664, 2 ,2664, 2 , 0 , 0 , 0 ,,
     1.3     1.3
     370     421
     1.3     1.3
     370     421
Pier Skew, UpSta & Num, DnSta & Num=  ,2678, 2 ,2678, 2 , 0 , 0 , 0 ,,
     1.3     1.3
     370     421
     1.3     1.3
     370     421
Pier Skew, UpSta & Num, DnSta & Num=  ,2692, 2 ,2692, 2 , 0 , 0 , 0 ,,
     1.3     1.3
     370     421
     1.3     1.3
     370     421
Pier Skew, UpSta & Num, DnSta & Num=  ,2704, 2 ,2704, 2 , 0 , 0 , 0 ,,
     1.3     1.3
     370     421
     1.3     1.3
     370     421
Pier Skew, UpSta & Num, DnSta & Num=  ,2720, 2 ,2720, 2 , 0 , 0 , 0 ,,
     1.3     1.3
     370     421
     1.3     1.3
     370     421
Pier Skew, UpSta & Num, DnSta & Num=  ,2748, 2 ,2748, 2 , 0 , 0 , 0 ,,
     1.3     1.3
     370     421
     1.3     1.3
     370     421
Pier Skew, UpSta & Num, DnSta & Num=  ,2762, 2 ,2762, 2 , 0 , 0 , 0 ,,
     1.3     1.3
     370     421
     1.3     1.3
     370     421
Pier Skew, UpSta & Num, DnSta & Num=  ,2776, 2 ,2776, 2 , 0 , 0 , 0 ,,
     1.3     1.3
     370     421
     1.3     1.3
     370     421
Pier Skew, UpSta & Num, DnSta & Num=  ,2790, 2 ,2790, 2 , 0 , 0 , 0 ,,
     1.3     1.3
     370     421
     1.3     1.3
     370     421
Pier Skew, UpSta & Num, DnSta & Num=  ,3288, 2 ,3288, 2 , 0 , 0 , 0 ,,
       2       2
     370     421
       2       2
     370     421
Pier Skew, UpSta & Num, DnSta & Num=  ,3321, 2 ,3321, 2 , 0 , 0 , 0 ,,
       2       2
     370     421
       2       2
     370     421
Pier Skew, UpSta & Num, DnSta & Num=  ,3354, 2 ,3354, 2 , 0 , 0 , 0 ,,
       2       2
     370     421
       2       2
     370     421
Pier Skew, UpSta & Num, DnSta & Num=  ,3387, 2 ,3387, 2 , 0 , 0 , 0 ,,
       2       2
     370     421
       2       2
     370     421
Pier Skew, UpSta & Num, DnSta & Num=  ,3420, 2 ,3420, 2 , 0 , 0 , 0 ,,
       2       2
     370     421
       2       2
     370     421
Pier Skew, UpSta & Num, DnSta & Num=  ,3453, 2 ,3453, 2 , 0 , 0 , 0 ,,
       2       2
     370     421
       2       2
     370     421
Pier Skew, UpSta & Num, DnSta & Num=  ,3486, 2 ,3486, 2 , 0 , 0 , 0 ,,
       2       2
     370     421
       2       2
     370     421
Pier Skew, UpSta & Num, DnSta & Num=  ,3519, 2 ,3519, 2 , 0 , 0 , 0 ,,
       2       2
     370     421
       2       2
     370     421
Pier Skew, UpSta & Num, DnSta & Num=  ,3552, 2 ,3552, 2 , 0 , 0 , 0 ,,
       2       2
     370     421
       2       2
     370     421
Pier Skew, UpSta & Num, DnSta & Num=  ,3585, 2 ,3585, 2 , 0 , 0 , 0 ,,
       2       2
     370     421
       2       2
     370     421
Pier Skew, UpSta & Num, DnSta & Num=  ,3618, 2 ,3618, 2 , 0 , 0 , 0 ,,
       2       2
     370     421
       2       2
     370     421
Pier Skew, UpSta & Num, DnSta & Num=  ,3651, 2 ,3651, 2 , 0 , 0 , 0 ,,
       2       2
     370     421
       2       2
     370     421
Pier Skew, UpSta & Num, DnSta & Num=  ,3684, 2 ,3684, 2 , 0 , 0 , 0 ,,
       2       2
     370     421
       2       2
     370     421
Pier Skew, UpSta & Num, DnSta & Num=  ,3717, 2 ,3717, 2 , 0 , 0 , 0 ,,
       2       2
     370     421
       2       2
     370     421
Pier Skew, UpSta & Num, DnSta & Num=  ,3750, 2 ,3750, 2 , 0 , 0 , 0 ,,
       2       2
     370     421
       2       2
     370     421
Pier Skew, UpSta & Num, DnSta & Num=  ,3783, 2 ,3783, 2 , 0 , 0 , 0 ,,
       2       2
     370     421
       2       2
     370     421
Pier Skew, UpSta & Num, DnSta & Num=  ,3816, 2 ,3816, 2 , 0 , 0 , 0 ,,
       2       2
     370     421
       2       2
     370     421
Pier Skew, UpSta & Num, DnSta & Num=  ,3849, 2 ,3849, 2 , 0 , 0 , 0 ,,
       2       2
     370     421
       2       2
     370     421
BR Coef= 1 , 1 , 1 ,2.5, 0 ,,,0.8,0,1.2,0,
WSPro=,,,, 1 ,,,, 0 ,,,, 0 ,,,,-1 ,-1 ,-1 , 0 , 0 , 0 , 0 , 0
BC Design=,, 0 ,, 0 ,,,,,,
BC HTab HWMax=428
BC Use User HTab Curves=0
BC User HTab FreeFlow(D)= 0

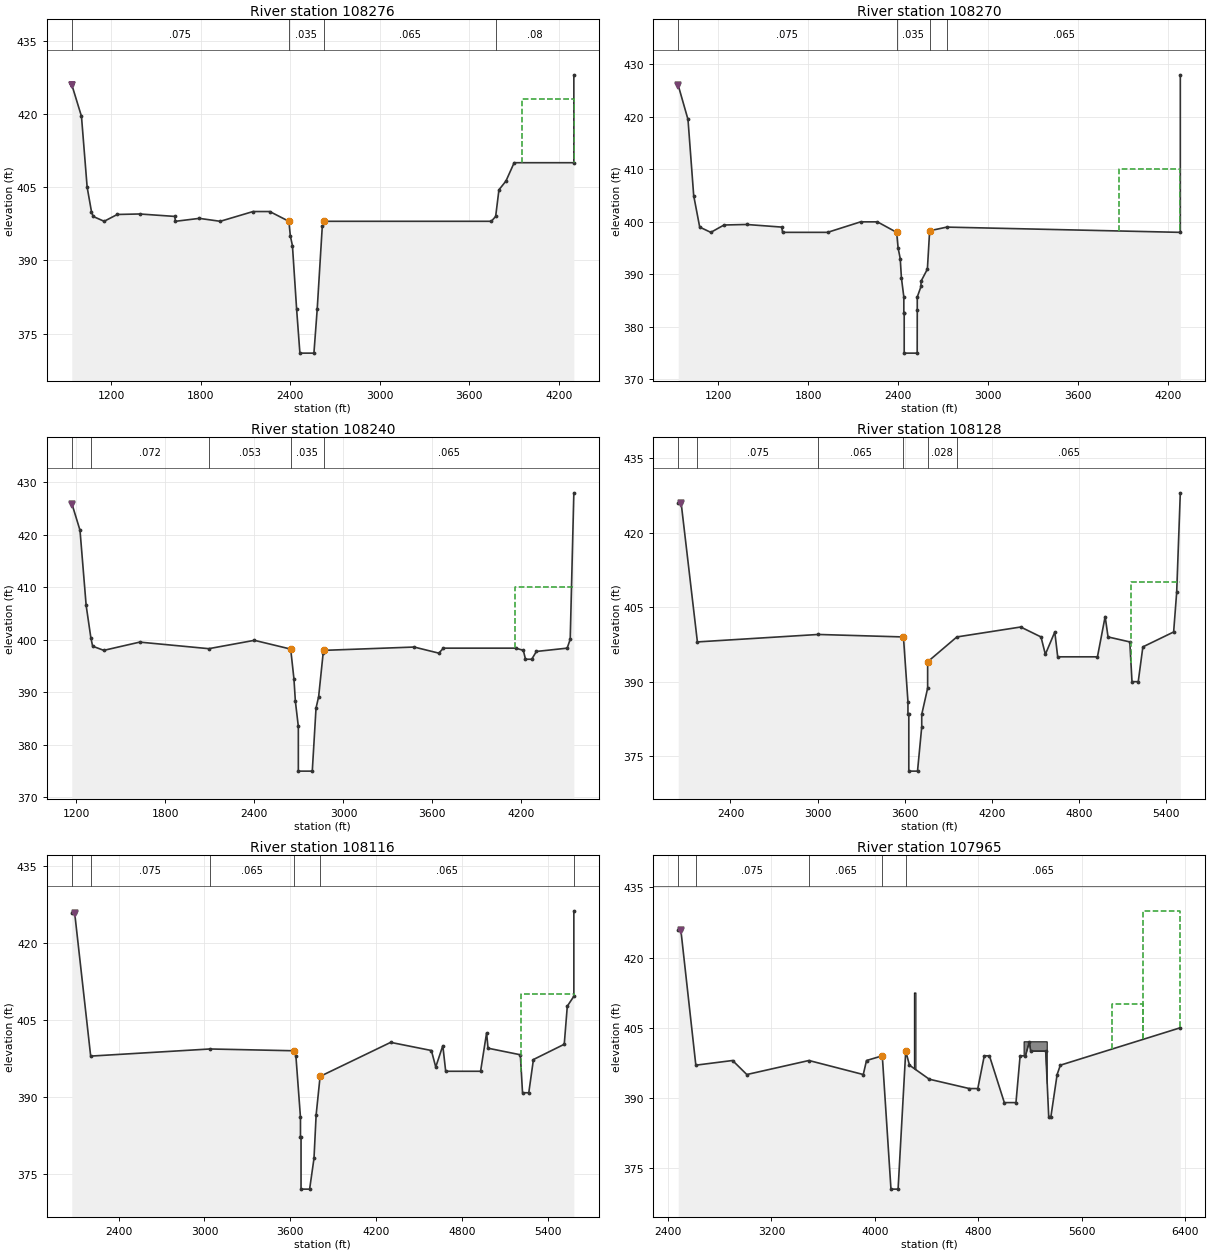
Type RM Length L Ch R = 1 ,108276  ,6,6,6
BEGIN DESCRIPTION:
Downstream bounding cross-section for ATSF Railroad bridge.
Cross-section modified for Sante Fe Trestle Trail.
END DESCRIPTION:
XS GIS Cut Line= 6
  2494397.261328 6962638.4575556 2493744.5243166 6961203.5746456
 2493664.9357675 6961032.6948435 2493502.9707377  6960774.405451
 2493107.6036026 6960364.8684124 2492565.6960248  6959881.727606
#Sta/Elev= 30
     935     426    1000   419.5    1038     405    1067     400    1078     399
    1152     398    1240   399.4    1390   399.5    1625     399    1630     398
    1790   398.6    1930     398    2150     400    2262     400    2390     398
    2400     395    2414     393    2442     380    2464     371    2558     371
    2580     380    2614     397    2625     398    3747     398    3776     399
    3798  404.45    3845  406.25    3900     410    4300     410    4300     428
#Mann= 4 ,-1,0
     935    .075       0    2390    .035       0    2625    .065       0
    3776     .08       0
Levee=-1,935,425.91,0,,,,
#XS Ineff= 2 , 0
                            3950             423
Permanent Ineff=
       F       T
#XS Lid=12
     935     426     426     935     432     432    2742     432     432
    2742     428  422.45    2753     428  422.45    2753     432     432
    2770     432     432    2770     428  422.45    2784     428  422.45
    2784     432     432    4300     432     432    4300     428     428
Bank Sta=2390,2625
XS Rating Curve= 0 ,0
Exp/Cntr=0.6,0.4

Type RM Length L Ch R = 1 ,108270  ,19.58,20,20.98
BEGIN DESCRIPTION:
Proposed Lamar Levee in LOB.
Cross-section modified for Sante Fe Trestle Trail.
Cross-section added for Standing Wave Park  - structure partially demolished.
END DESCRIPTION:
XS GIS Cut Line= 6
  2494398.412953  6962628.239742 2493749.5113724 6961200.3383647
 2493670.0422771 6961030.6304565 2493508.3621807 6960771.8649564
 2493111.4211205 6960359.9078273 2492579.9132928 6959886.1874824
#Sta/Elev= 30
     935     426    1000   419.5    1038     405    1078     399    1152     398
    1240   399.4    1390   399.5    1625     399    1630     398    1930     398
    2150     400    2262     400    2390     398    2400     395    2414     393
    2422   389.3    2438   385.7 2438.01   382.7  2440.5   382.7 2440.51     375
    2527     375  2527.5   383.2 2527.51   385.7  2552.5   387.7 2552.51  388.68
 2594.96     391 2609.96   398.3    2724     399    4280     398    4280     428
#Mann= 4 ,-1,0
     935    .075       0    2390    .035       0 2609.96    .029       0
    2724    .065       0
Levee=-1,935,425.79,0,,,,
#XS Ineff= 2 , 0
                            3870             410
Permanent Ineff=
       F       T
#XS Lid=12
     935     426     426     935     432     432    2712     432     432
    2712     428  422.45    2723     428  422.45    2723     432     432
    2740     432     432    2740     428  422.45    2754     428  422.45
    2754     432     432    4280     432     432    4280     428     428
Bank Sta=2390,2609.96
XS Rating Curve= 0 ,0
Exp/Cntr=0.6,0.4

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
Type RM Length L Ch R = 1 ,108240  ,80.28,82,86.01
BEGIN DESCRIPTION:
Proposed Lamar Levee in LOB.
Cross-section modified for Sante Fe Trestle Trail.
Cedar Creek in ROB.
Cross-section added for Standing Wave Park - structure partially demolished.
END DESCRIPTION:
XS GIS Cut Line= 6
  2494427.347694 6962628.6798152 2493774.4466516 6961184.1569602
 2493700.2866285  6961017.247332 2493536.1786366 6960749.6623654
 2493134.3969845 6960335.7545356 2492590.1104961 6959854.6100068
#Sta/Elev= 30
 1168.45     426 1223.94  420.87 1265.44  406.55 1297.11  400.41 1309.13  398.79
 1384.41     398 1626.55  399.57 2092.16  398.32 2399.77  399.91 2644.38  398.24
 2666.43  392.56    2676   388.3    2696   383.5 2696.01     375    2790     375
  2815.3     387    2833   389.2 2863.68  397.57  2868.8     398 3476.71  398.63
 3643.13  397.47 3674.45  398.42 4161.95  398.42 4212.86     398 4227.54  396.31
 4269.63  396.31 4300.96  397.79 4508.49  398.42 4529.05  400.11 4553.52     428
#Mann= 5 ,-1,0
 1168.45    .067       0 1297.11    .072       0 2092.16    .053       0
 2644.38    .035       0  2868.8    .065       0
Levee=-1,1172.676,425.83,0,,,,
#XS Ineff= 2 , 0
                            4155             410
Permanent Ineff=
       F       T
#XS Lid=12
 1168.45     426     426 1168.45     432     432    2942     432     432
    2942     428  422.45    2953     428  422.45    2953     432     432
    2970     432     432    2970     428  422.45    2984     428  422.45
    2984     432     432 4553.52     432     432 4553.52     428     428
Bank Sta=2644.38,2868.8
XS Rating Curve= 0 ,0
Exp/Cntr=0.6,0.4

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
Type RM Length L Ch R = 1 ,108128  ,15.83,12,19.14
BEGIN DESCRIPTION:
Proposed Lamar Levee in LOB.
Cross-section modified for CDC DAL010909-1 Sante Fe Trestle Trail.
Cedar Creek in ROB.
Cross-section added for Standing Wave Park - structure partially demolished.
END DESCRIPTION:
XS GIS Cut Line= 4
  2494549.735185 6962622.2649611        2493725.        6960809.
        2493113.        6960147. 2492726.7935581 6959732.6358934
#Sta/Elev= 30
    2040  425.98    2060  425.98    2172     398    3005   399.5    3592     399
    3623     386 3623.01   383.4    3629   383.4 3629.01     372    3689     372
    3718   380.9 3718.01   383.4 3758.77   388.7 3758.78     394    3960     399
    4400     401    4540     399    4570   395.5    4635     400    4655     395
    4929     395    4982   403.1    5002     399    5152     398    5167     390
    5210     390    5242     397    5454     400    5475     408    5500     428
#Mann= 6 ,-1,0
    2040    .035       0    2172    .075       0    3005    .065       0
    3592    .035       0 3758.78    .028       0    3960    .065       0
Levee=-1,2060,425.77,0,,,,
#XS Ineff= 2 , 0
                            5160             410
Permanent Ineff=
       F       T
#XS Lid=18
    2025  425.98  425.98    2025     432     432    3846     432     432
    3846  422.15  416.66    3857  422.15  416.66    3857     432     432
    3886     432     432    3886  423.26  417.77    3896  423.26  417.77
    3896     432     432    3904     432     432    3904  424.84  419.34
    3916  424.84  419.34    3916  426.42  420.93    3936  426.42  420.93
    3936     432     432    5500     432     432    5500     428     428
Bank Sta=3592,3758.78
XS Rating Curve= 0 ,0
Exp/Cntr=0.6,0.4

Type RM Length L Ch R = 1 ,108116  ,21.11,16,25.52
BEGIN DESCRIPTION:
Proposed Lamar Levee in LOB.
Cross-section modified for CDC DAL010909-1 Sante Fe Trestle Trail.
Cedar Creek in ROB.
Cross-section added for Standing Wave Park - structure partially demolished.
END DESCRIPTION:
XS GIS Cut Line= 5
  2494570.955038  6962636.743518        2493736.        6960802.
        2493122.        6960139. 2492722.8490759 6959710.7584153
 2492719.7142644 6959707.3951345
#Sta/Elev= 30
 2072.39  425.98 2092.42  425.97 2204.55  397.96 3038.54  399.35 3626.23     399
    3639     398    3671     386 3671.01   382.2    3675   382.2 3675.01     372
    3735     372  3765.5     378 3780.51   386.5 3808.22     394 4301.54  400.64
 4586.05  399.05 4616.53  395.83    4666     400    4686     395    4930     395
    4972   402.5    4982   399.5 5207.91  398.22 5223.15  390.81 5266.85  390.81
 5299.36  397.29 5514.78  400.27 5536.12  407.71 5581.84  409.63 5581.84  426.31
#Mann= 6 ,-1,0
 2072.39    .035       0 2204.55    .075       0 3038.54    .065       0
 3626.23    .035       0 3808.22    .065       0 5581.84    .065       0
Levee=-1,2092.401,425.75,0,,,,
#XS Ineff= 2 , 0
                            5215             410
Permanent Ineff=
       F       T
#XS Lid=9
    2025     432     432    3904     432     432    3904  424.84  419.34
    3916  424.84  419.34    3916  426.42  420.93    3936  426.42  420.93
    3936     432     432 5581.84     432     432 5581.84  426.31  426.31
Bank Sta=3626.23,3808.22
XS Rating Curve= 0 ,0
Exp/Cntr=0.6,0.4

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
Type RM Length L Ch R = 1 ,107965  ,215,184,245
BEGIN DESCRIPTION:
Proposed Lamar Levee in LOB.
Cross-section modified for CDC DAL010909-1 Sante Fe Trestle Trail.
Cedar Creek in ROB.
END DESCRIPTION:
XS GIS Cut Line= 4
  2494786.067038 6962540.1937088        2493857.        6960748.
  2493009.007372 6959523.1994359 2492797.9539408 6959217.3525457
#Sta/Elev= 30
    2480  425.97    2500  425.97    2616     397    2900     398    3010     395
    3490     398    3910     395    3935     398    4057     399    4124   370.5
    4179   370.5    4238     400    4267     397    4420     394    4730     392
    4795     392    4845     399    4885     399    5000     389    5090     389
    5122     399  5163.5     399  5193.5     402  5203.5     400    5320     400
    5343     386    5360     386    5408     395    5433     397    6360     405
#Mann= 5 ,-1,0
    2480    .035       0    2616    .075       0    3490    .065       0
    4057    .035       0    4238    .065       0
Levee=-1,2500,425.77,0,,,,
#XS Ineff= 2 ,-1
    5830    6070     410    6070    6360     430
Permanent Ineff=
       T       T
#Block Obstruct= 2 ,-1
  4300.5  4313.5  412.55  5152.5  5331.5     402
#XS Lid=10
    2480  425.97  425.97    2480     432     432  4273.5     432     432
  4273.5  419.45  413.95  4291.5  419.45  413.95  4291.5  421.07  415.57
  4313.5  421.07  415.57  4313.5     432     432    6360     432     432
    6360     405     405
Bank Sta=4057,4238
XS Rating Curve= 0 ,0
Exp/Cntr=0.5,0.3

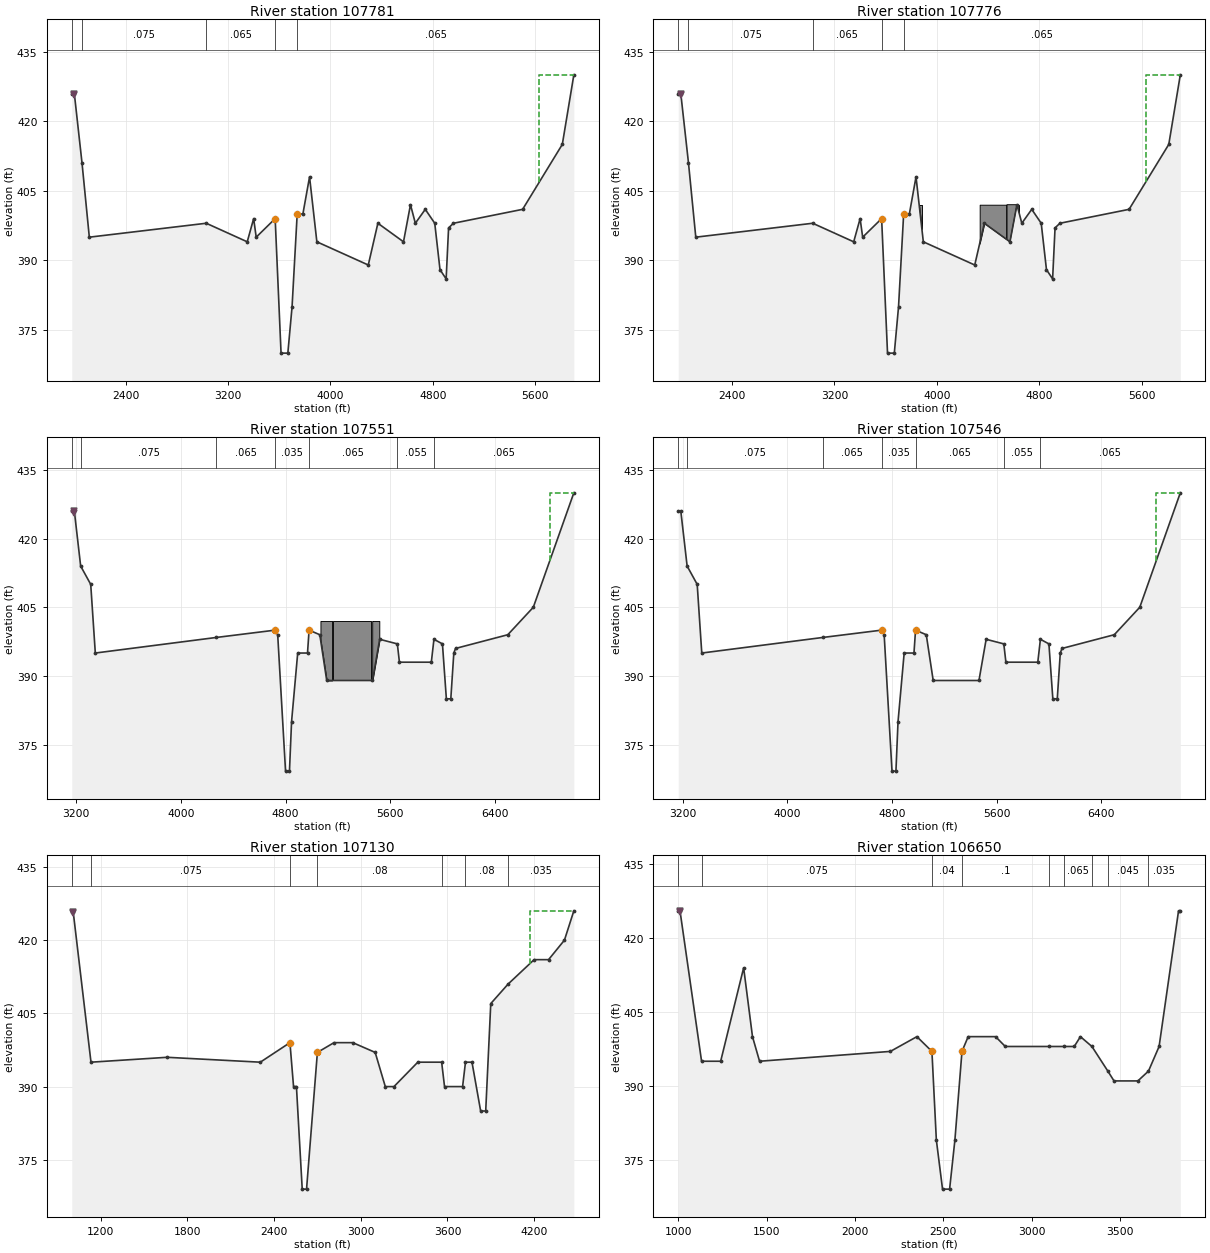
Type RM Length L Ch R = 1 ,107781  ,5,5,5
BEGIN DESCRIPTION:
Proposed Lamar Levee in LOB.
Cross-section added for CDC DAL010909-1 Sante Fe Trestle Trail.
Cedar Creek in ROB.
END DESCRIPTION:
XS GIS Cut Line= 5
  2494997.938727 6962408.9357767 2494168.8828058 6960947.1053928
 2493077.5588648 6959081.3098448 2493043.2265616 6959022.6131956
 2493038.2195137 6959014.0528339
#Sta/Elev= 30
    1980  425.95    2000  425.95    2060     411    2117     395    3030     398
    3350     394    3400     399    3420     395    3568     399    3614     370
    3667     370    3700     380    3740     400  3784.5     400  3836.5     408
 3893.58     394    4295     389    4370     398    4570     394  4624.5     402
  4662.5     398    4740     401    4814     398    4855     388    4903     386
    4922     397    4960     398    5500     401    5810     415    5900     430
#Mann= 5 ,-1,0
    1980    .035       0    2060    .075       0    3030    .065       0
    3568    .035       0    3740    .065       0
Levee=-1,2000,425.75,0,,,,
#XS Ineff= 2 , 0
                            5630             430
Permanent Ineff=
       F       T
Bank Sta=3568,3740
XS Rating Curve= 0 ,0
Exp/Cntr=0.5,0.3

Type RM Length L Ch R = 1 ,107776  ,225,225,225
BEGIN DESCRIPTION:
Proposed Lamar Levee in LOB.
Cross-section modified for Sante Fe Trestle Trail.
Cedar Creek in ROB.
END DESCRIPTION:
XS GIS Cut Line= 5
  2495003.590952 6962406.1953038 2494173.3473178 6960944.6453555
 2493082.6616799  6959079.171165 2493048.2362086 6959020.2909286
 2493043.2045958 6959011.6850174
#Sta/Elev= 30
    1980  425.95    2000  425.95    2060     411    2117     395    3030     398
    3350     394    3400     399    3420     395    3568     399    3614     370
    3667     370    3700     380    3740     400  3784.5     400  3836.5     408
 3893.58     394    4295     389    4370     398    4570     394  4624.5     402
  4662.5     398    4740     401    4814     398    4855     388    4903     386
    4922     397    4960     398    5500     401    5810     415    5900     430
#Mann= 5 ,-1,0
    1980    .035       0    2060    .075       0    3030    .065       0
    3568    .035       0    3740    .065       0
Levee=-1,2000,425.74,0,,,,
#XS Ineff= 2 , 0
                            5630             430
Permanent Ineff=
       F       T
#Block Obstruct= 3 ,-1
    3840  3882.5     402  4333.5    4541     402    4547  4641.5     402
Bank Sta=3568,3740
XS Rating Curve= 0 ,0
Exp/Cntr=0.5,0.3

Type RM Length L Ch R = 1 ,107551  ,5,5,5
BEGIN DESCRIPTION:
Proposed Lamar Levee in LOB.
Cross-section modified for CDC DAL010909-1 Sante Fe Trestle Trail.
Cedar Creek in ROB.
END DESCRIPTION:
XS GIS Cut Line= 6
  2495229.629547 6962336.6197214 2495229.6295474 6962336.6197214
        2494649.        6961333. 2493321.6725627 6959041.1484419
 2493305.6067219  6959013.408096 2493305.6067219  6959013.408096
#Sta/Elev= 30
    3165  425.93    3185  425.93    3233     414    3310     410    3345     395
    4270   398.4    4720     400    4740     399    4800   369.2    4830   369.2
    4846     380    4893     395    4968     395    4980     400    5062     399
    5115     389    5465     389    5520     398    5655     397    5671     393
    5915     393    5935     398    6000     397    6030     385    6064     385
    6087     395    6100     396    6500     399    6695     405    7005     430
#Mann= 7 ,-1,0
    3165    .035       0    3233    .075       0    4270    .065       0
    4720    .035       0    4980    .065       0    5655    .055       0
    5935    .065       0
Levee=-1,3185,425.69,0,,,,
#XS Ineff= 1 ,-1
    6820    6820     430
Permanent Ineff=
       T
#Block Obstruct= 3 ,-1
    5067 5155.85     402 5164.15 5457.23     402 5462.77    5517     402
Bank Sta=4720,4980
XS Rating Curve= 0 ,0
Exp/Cntr=0.5,0.3

Type RM Length L Ch R = 1 ,107546  ,416,416,416
BEGIN DESCRIPTION:
Proposed Lamar Levee in LOB.
Cross-section added for CDC DAL010909-1 Sante Fe Trestle Trail.
This is the approximate location of the borrow area used for CDC DAL061307-1 Moore Park Gateway Phase 1.  The borrow area for this project is in the same area as the borrow area for SFTT.  No additional modifications to the model have been made for the Moore Park project.
Cedar Creek in ROB.
END DESCRIPTION:
XS GIS Cut Line= 5
   2495234.33737  6962334.281581 2495234.2290097 6962334.0944019
  2494371.380222 6960843.6286776 2493310.1793671 6959011.3980701
 2493310.0709685 6959011.2109131
#Sta/Elev= 30
    3165  425.93    3185  425.93    3233     414    3310     410    3345     395
    4270   398.4    4720     400    4740     399    4800   369.2    4830   369.2
    4846     380    4893     395    4968     395    4980     400    5062     399
    5115     389    5465     389    5520     398    5655     397    5671     393
    5915     393    5935     398    6000     397    6030     385    6064     385
    6087     395    6100     396    6500     399    6695     405    7005     430
#Mann= 7 ,-1,0
    3165    .035       0    3233    .075       0    4270    .065       0
    4720    .035       0    4980    .065       0    5655    .055       0
    5935    .065       0
Levee=-1,1000,425.71,0,,,,
#XS Ineff= 1 ,-1
    6820    6820     430
Permanent Ineff=
       T
Bank Sta=4720,4980
XS Rating Curve= 0 ,0
Exp/Cntr=0.5,0.3

Type RM Length L Ch R = 1 ,107130  ,390,480,490
BEGIN DESCRIPTION:
Proposed Lamar Levee in LOB.
Wetland Cell A in ROB.
Downstream limit of CDC DAL010909-1 Sante Fe Trestle Trail.
Cedar Creek in ROB.
END DESCRIPTION:
XS GIS Cut Line= 3
  2495553.154773 6962058.2185528 2494741.6140662 6960647.1556268
 2493811.7903872 6959051.0301465
#Sta/Elev= 30
    1000  425.78    1010  425.78    1133     395    1660     396    2305     395
    2510     399    2535     390    2555     390    2595     369    2625     369
    2700     397    2815     399    2945     399    3100     397    3170     390
    3230     390    3395     395    3560     395    3580     390    3705     390
    3725     395    3770     395    3830     385    3865     385    3900     407
    4020     411    4200     416    4300     416    4410     420    4475     426
#Mann= 7 ,-1,0
    1000    .035       0    1133    .075       0    2510     .04       0
    2700     .08       0    3560    .055       0    3725     .08       0
    4020    .035       0
Levee=-1,1010,425.55,0,,,,
#XS Ineff= 2 , 0
                            4170             426
Permanent Ineff=
       F       F
Bank Sta=2510,2700
XS Rating Curve= 0 ,0
Exp/Cntr=0.3,0.1

Type RM Length L Ch R = 1 ,106650  ,425,550,480
BEGIN DESCRIPTION:
Downstream of Cedar Creek.
Proposed Lamar Levee in LOB.
Proposed Cadillac Heights Levee in ROB.
Wetland Cell A in ROB.
END DESCRIPTION:
Node Name=Cedar Creek
XS GIS Cut Line= 4
  2495873.613679 6961874.5766682        2495217.        6960673.
        2495192.        6960454. 2494581.0324116 6959363.1459218
#Sta/Elev= 30
    1000  425.58    1010  425.58    1132     395    1240     395    1370     414
    1420     400    1460     395    2200     397    2350     400    2435     397
    2460     379    2495     369    2535     369    2565     379    2605     397
    2640     400    2795     400    2850     398    3100     398    3180     398
    3240     398    3275     400    3340     398    3430     393    3465     391
    3600     391    3660     393    3720     398    3830  425.58    3840  425.58
#Mann= 9 ,-1,0
    1000    .035       0    1132    .075       0    2435     .04       0
    2605      .1       0    3100    .045       0    3180    .065       0
    3340    .035       0    3430    .045       0    3660    .035       0
Levee=-1,1010,425.33,0,,,,
Bank Sta=2435,2605
XS Rating Curve= 0 ,0
Exp/Cntr=0.5,0.3

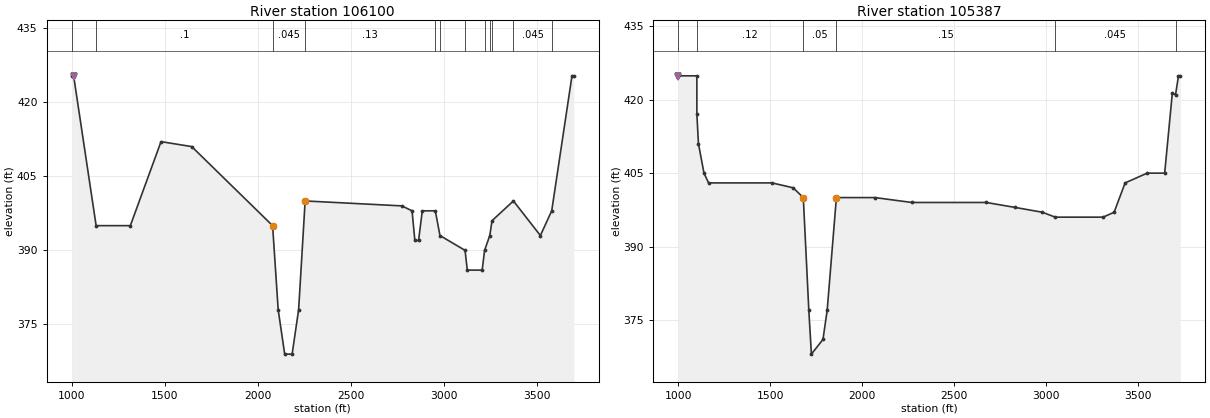
Type RM Length L Ch R = 1 ,106100  ,500,713,360
BEGIN DESCRIPTION:
Proposed Lamar Levee in LOB.
Proposed Cadillac Heights Levee in ROB.
Wetland Cell A in ROB.
END DESCRIPTION:
XS GIS Cut Line= 6
  2496241.955657  6961625.320377 2496228.8865135 6961603.6492107
 2495681.4412137 6960695.8791308 2495717.5147249 6960617.3906735
 2495753.5882362 6960538.9022163 2495109.3735706 6959248.9579186
#Sta/Elev= 30
    1000  425.32    1010  425.32    1131     395    1315     395    1480     412
    1645     411    2080     395    2110     378    2145     369    2185     369
    2220     378    2255     400    2775     399    2830     398    2845     392
    2865     392    2885     398    2955     398    2980     393    3115     390
    3127     386    3207     386    3220     390    3248     393    3260     396
    3375     400    3520     393    3581     398    3690  425.32    3700  425.32
#Mann= 12 ,-1,0
    1000    .035       0    1131      .1       0    2080    .045       0
    2255     .13       0    2955    .035       0    2980    .045       0
    3115    .025       0    3220    .045       0    3248    .035       0
    3260    .065       0    3375    .045       0    3581    .035       0
Levee=-1,1010,425.06,0,,,,
Bank Sta=2080,2255
XS Rating Curve= 0 ,0
Exp/Cntr=0.3,0.1

Type RM Length L Ch R = 1 ,105387  ,58,58,58
BEGIN DESCRIPTION:
Upstream bounding cross-section for Martin Luther King Jr. bridge.
Proposed Lamar Levee in LOB.
Proposed Cadillac Heights Levee in ROB.
Wetland Cell A in ROB.
END DESCRIPTION:
XS GIS Cut Line= 3
  2496735.376627 6961530.0195241 2496367.3822478  6960867.109049
 2495414.3967408 6959140.8975133
#Sta/Elev= 29
    1000  424.89  1101.3  424.89  1101.3     417    1110     411    1140     405
    1165     403    1510     403    1625     402    1680     400    1710     377
    1724     368    1787     371    1810     377    1860     400    2070     400
    2270     399    2675     399    2830     398    2980     397    3050     396
    3310     396    3370     397    3430     403    3550     405    3645     405
  3686.7   421.4    3704     421    3720  424.89    3730  424.89
#Mann= 6 ,-1,0
    1000    .035       0  1101.3     .12       0    1680     .05       0
    1860     .15       0    3050    .045       0    3704    .035       0
Levee=-1,1000,424.61,0,,,,
Bank Sta=1680,1860
XS Rating Curve= 0 ,0
Exp/Cntr=0.5,0.3