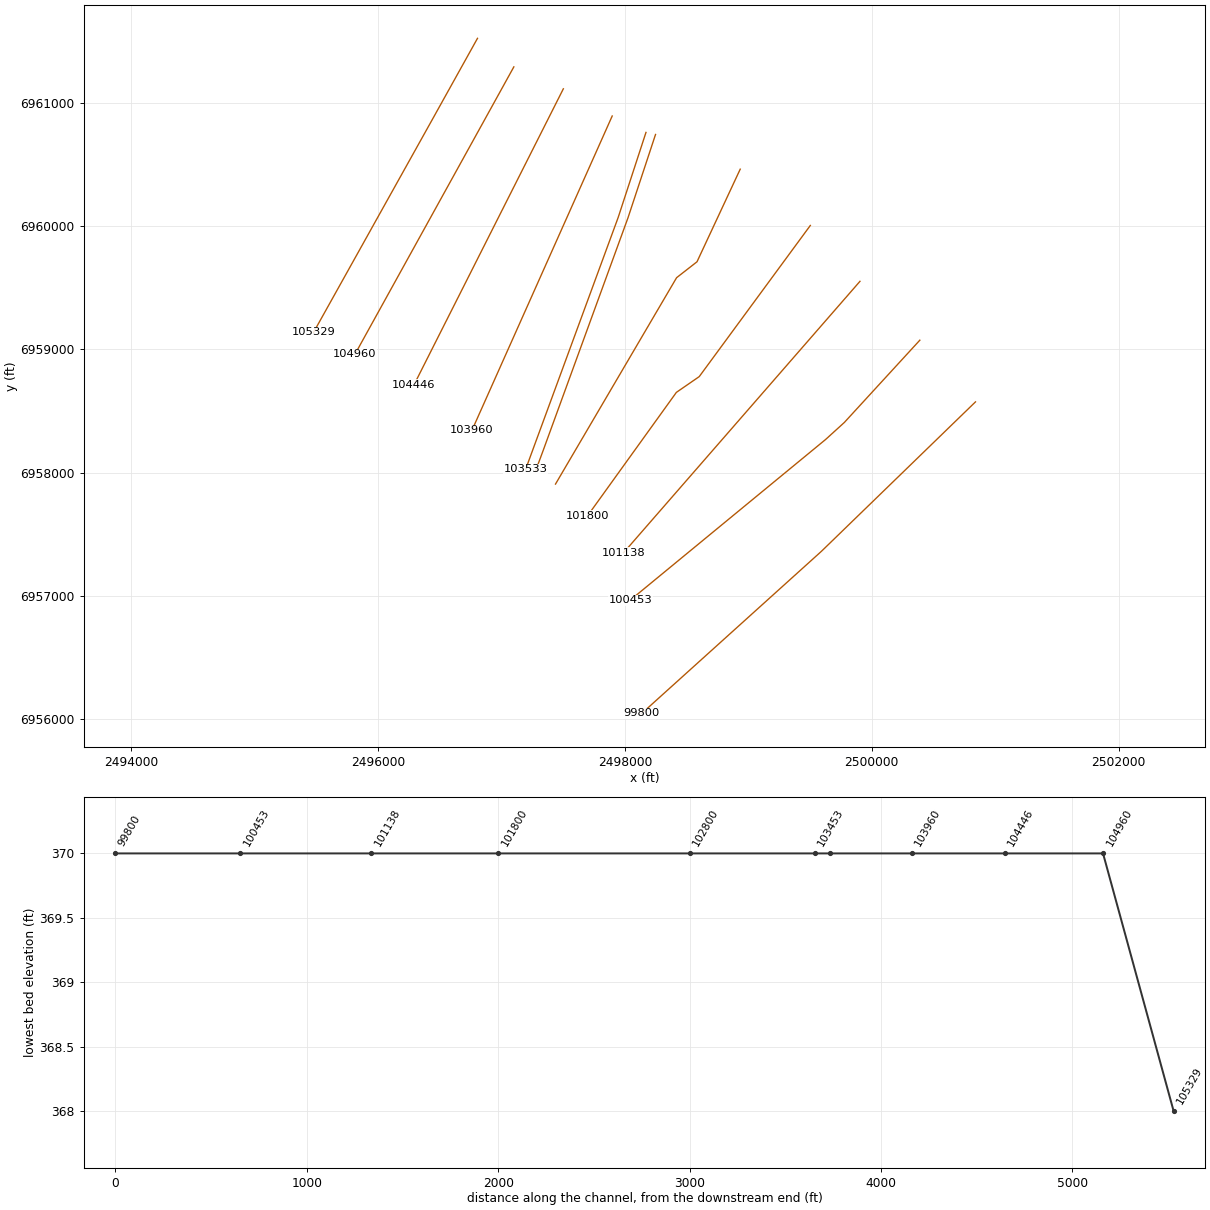
HEC-RAS study CDC_Consolidated_Model.prj: Upper Trinity CDC Consolidated Model

--- CDC_Consolidated_Model.g12 (geometry) --- (continued)

Type RM Length L Ch R = 3 ,105358  ,,,
BEGIN DESCRIPTION:
Martin Luther King Jr. Boulevard
END DESCRIPTION:
Node Name=MLK Jr. Blvd.
Bridge Culvert--1,0,-1,-1, 0
Deck Dist Width WeirC Skew NumUp NumDn MinLoCord MaxHiCord MaxSubmerge Is_Ogee
1,56,2.6,0, 56, 56, , , 0.95, 0, ,,,
    1100    1141    1191    1241    1291    1341    1391    1441    1491    1541
    1598    1598    1641    1691    1741    1791    1841    1891    1941    1964
    1964    1991    2041    2091    2141    2191    2241    2291    2341    2391
    2441    2491    2541    2591    2641    2691    2741    2791    2841    2891
    2941    2991    3041    3091    3141    3191    3241    3291    3341    3391
    3441    3491    3541    3591    3641    3686
   425.1   425.5     426   426.5   426.9   427.3   427.7   428.1   428.4   428.7
     429     429   429.3   429.5   429.7   429.9     430   430.1   430.2   430.2
   430.2   430.3   430.3   430.4   430.3   430.3   430.2   430.1     430   429.9
   429.7   429.5   429.3   429.1   428.9   428.7   428.5   428.3   428.1   427.9
   427.7   427.5   427.3   427.1   426.9   426.7   426.5   426.3   426.1   425.9
   425.7   425.5   425.2   424.9   424.3   423.7
   418.7   419.1   419.6   420.1   420.5   420.9   421.3   421.7     422   422.3
   422.6   420.4   420.7   420.9   421.1   421.3   421.4   421.5   421.6   421.6
   423.8   423.9   423.9     424   423.9   423.9   423.8   423.7   423.6   423.5
   423.3   423.1   422.9   422.7   422.5   422.3   422.1   421.9   421.7   421.5
   421.3   421.1   420.9   420.7   420.5   420.3   420.1   419.9   419.7   419.5
   419.3   419.1   418.8   418.5   418.3   417.3
    1100    1141    1191    1241    1291    1341    1391    1441    1491    1541
    1598    1598    1641    1691    1741    1791    1841    1891    1941    1964
    1964    1991    2041    2091    2141    2191    2241    2291    2341    2391
    2441    2491    2541    2591    2641    2691    2741    2791    2841    2891
    2941    2991    3041    3091    3141    3191    3241    3291    3341    3391
    3441    3491    3541    3591    3641    3686
   425.1   425.5     426   426.5   426.9   427.3   427.7   428.1   428.4   428.7
     429     429   429.3   429.5   429.7   429.9     430   430.1   430.2   430.2
   430.2   430.3   430.3   430.4   430.3   430.3   430.2   430.1     430   429.9
   429.7   429.5   429.3   429.1   428.9   428.7   428.5   428.3   428.1   427.9
   427.7   427.5   427.3   427.1   426.9   426.7   426.5   426.3   426.1   425.9
   425.7   425.5   425.2   424.9   424.3   423.7
   418.7   419.1   419.6   420.1   420.5   420.9   421.3   421.7     422   422.3
   422.6   420.4   420.7   420.9   421.1   421.3   421.4   421.5   421.6   421.6
   423.8   423.9   423.9     424   423.9   423.9   423.8   423.7   423.6   423.5
   423.3   423.1   422.9   422.7   422.5   422.3   422.1   421.9   421.7   421.5
   421.3   421.1   420.9   420.7   420.5   420.3   420.1   419.9   419.7   419.5
   419.3   419.1   418.8   418.5   418.3   417.3
Pier Skew, UpSta & Num, DnSta & Num=  ,1145, 2 ,1145, 2 , 0 , 0 , 0 ,,
     2.5     2.5
       0   420.5
     2.5     2.5
       0   420.5
Pier Skew, UpSta & Num, DnSta & Num=  ,1190, 2 ,1190, 2 , 0 , 0 , 0 ,,
     2.5     2.5
       0   421.5
     2.5     2.5
       0   421.5
Pier Skew, UpSta & Num, DnSta & Num=  ,1241, 2 ,1241, 2 , 0 , 0 , 0 ,,
     2.5     2.5
       0     423
     2.5     2.5
       0     423
Pier Skew, UpSta & Num, DnSta & Num=  ,1292, 2 ,1292, 2 , 0 , 0 , 0 ,,
     2.5     2.5
       0     424
     2.5     2.5
       0     424
Pier Skew, UpSta & Num, DnSta & Num=  ,1343, 2 ,1343, 2 , 0 , 0 , 0 ,,
     2.5     2.5
       0   422.5
     2.5     2.5
       0   422.5
Pier Skew, UpSta & Num, DnSta & Num=  ,1394, 2 ,1394, 2 , 0 , 0 , 0 ,,
     2.5     2.5
       0   422.5
     2.5     2.5
       0   422.5
Pier Skew, UpSta & Num, DnSta & Num=  ,1445, 2 ,1445, 2 , 0 , 0 , 0 ,,
     2.5     2.5
       0   422.5
     2.5     2.5
       0   422.5
Pier Skew, UpSta & Num, DnSta & Num=  ,1496, 2 ,1496, 2 , 0 , 0 , 0 ,,
     2.5     2.5
       0   424.5
     2.5     2.5
       0   424.5
Pier Skew, UpSta & Num, DnSta & Num=  ,1547, 2 ,1547, 2 , 0 , 0 , 0 ,,
     2.5     2.5
       0   424.5
     2.5     2.5
       0   424.5
Pier Skew, UpSta & Num, DnSta & Num=  ,1598, 2 ,1598, 2 , 0 , 0 , 0 ,,
       3       3
       0     424
       3       3
       0     424
Pier Skew, UpSta & Num, DnSta & Num=  ,1711, 2 ,1711, 2 , 0 , 0 , 0 ,,
       4       4
       0     424
       4       4
       0     424
Pier Skew, UpSta & Num, DnSta & Num=  ,1851, 2 ,1851, 2 , 0 , 0 , 0 ,,
       4       4
       0   423.5
       4       4
       0   423.5
Pier Skew, UpSta & Num, DnSta & Num=  ,1964, 2 ,1964, 2 , 0 , 0 , 0 ,,
       3       3
       0   423.5
       3       3
       0   423.5
Pier Skew, UpSta & Num, DnSta & Num=  ,2015, 2 ,2015, 2 , 0 , 0 , 0 ,,
     2.5     2.5
       0     424
     2.5     2.5
       0     424
Pier Skew, UpSta & Num, DnSta & Num=  ,2066, 2 ,2066, 2 , 0 , 0 , 0 ,,
     2.5     2.5
       0     424
     2.5     2.5
       0     424
Pier Skew, UpSta & Num, DnSta & Num=  ,2117, 2 ,2117, 2 , 0 , 0 , 0 ,,
     2.5     2.5
       0     424
     2.5     2.5
       0     424
Pier Skew, UpSta & Num, DnSta & Num=  ,2168, 2 ,2168, 2 , 0 , 0 , 0 ,,
     2.5     2.5
       0     424
     2.5     2.5
       0     424
Pier Skew, UpSta & Num, DnSta & Num=  ,2219, 2 ,2219, 2 , 0 , 0 , 0 ,,
     2.5     2.5
       0     424
     2.5     2.5
       0     424
Pier Skew, UpSta & Num, DnSta & Num=  ,2270, 2 ,2270, 2 , 0 , 0 , 0 ,,
     2.5     2.5
       0     424
     2.5     2.5
       0     424
Pier Skew, UpSta & Num, DnSta & Num=  ,2321, 2 ,2321, 2 , 0 , 0 , 0 ,,
     2.5     2.5
       0     424
     2.5     2.5
       0     424
Pier Skew, UpSta & Num, DnSta & Num=  ,2372, 2 ,2372, 2 , 0 , 0 , 0 ,,
     2.5     2.5
       0     425
     2.5     2.5
       0     425
Pier Skew, UpSta & Num, DnSta & Num=  ,2423, 2 ,2423, 2 , 0 , 0 , 0 ,,
     2.5     2.5
       0     424
     2.5     2.5
       0     424
Pier Skew, UpSta & Num, DnSta & Num=  ,2423, 2 ,2423, 2 , 0 , 0 , 0 ,,
     2.5     2.5
       0     424
     2.5     2.5
       0     424
Pier Skew, UpSta & Num, DnSta & Num=  ,2474, 2 ,2474, 2 , 0 , 0 , 0 ,,
     2.5     2.5
       0     424
     2.5     2.5
       0     424
Pier Skew, UpSta & Num, DnSta & Num=  ,2525, 2 ,2525, 2 , 0 , 0 , 0 ,,
     2.5     2.5
       0     424
     2.5     2.5
       0     424
Pier Skew, UpSta & Num, DnSta & Num=  ,2576, 2 ,2576, 2 , 0 , 0 , 0 ,,
     2.5     2.5
       0     424
     2.5     2.5
       0     424
Pier Skew, UpSta & Num, DnSta & Num=  ,2627, 2 ,2627, 2 , 0 , 0 , 0 ,,
     2.5     2.5
       0     424
     2.5     2.5
       0     424
Pier Skew, UpSta & Num, DnSta & Num=  ,2678, 2 ,2678, 2 , 0 , 0 , 0 ,,
     2.5     2.5
       0     424
     2.5     2.5
       0     424
Pier Skew, UpSta & Num, DnSta & Num=  ,2729, 2 ,2729, 2 , 0 , 0 , 0 ,,
     2.5     2.5
       0     424
     2.5     2.5
       0     424
Pier Skew, UpSta & Num, DnSta & Num=  ,2780, 2 ,2780, 2 , 0 , 0 , 0 ,,
     2.5     2.5
       0     424
     2.5     2.5
       0     424
Pier Skew, UpSta & Num, DnSta & Num=  ,2831, 2 ,2831, 2 , 0 , 0 , 0 ,,
     2.5     2.5
       0     424
     2.5     2.5
       0     424
Pier Skew, UpSta & Num, DnSta & Num=  ,2882, 2 ,2882, 2 , 0 , 0 , 0 ,,
     2.5     2.5
       0     424
     2.5     2.5
       0     424
Pier Skew, UpSta & Num, DnSta & Num=  ,2933, 2 ,2933, 2 , 0 , 0 , 0 ,,
     2.5     2.5
       0     424
     2.5     2.5
       0     424
Pier Skew, UpSta & Num, DnSta & Num=  ,2984, 2 ,2984, 2 , 0 , 0 , 0 ,,
     2.5     2.5
       0     424
     2.5     2.5
       0     424
Pier Skew, UpSta & Num, DnSta & Num=  ,3035, 2 ,3035, 2 , 0 , 0 , 0 ,,
     2.5     2.5
       0     424
     2.5     2.5
       0     424
Pier Skew, UpSta & Num, DnSta & Num=  ,3086, 2 ,3086, 2 , 0 , 0 , 0 ,,
     2.5     2.5
       0     424
     2.5     2.5
       0     424
Pier Skew, UpSta & Num, DnSta & Num=  ,3137, 2 ,3137, 2 , 0 , 0 , 0 ,,
     2.5     2.5
       0     424
     2.5     2.5
       0     424
Pier Skew, UpSta & Num, DnSta & Num=  ,3188, 2 ,3188, 2 , 0 , 0 , 0 ,,
     2.5     2.5
       0     423
     2.5     2.5
       0     423
Pier Skew, UpSta & Num, DnSta & Num=  ,3239, 2 ,3239, 2 , 0 , 0 , 0 ,,
     2.5     2.5
       0     423
     2.5     2.5
       0     423
Pier Skew, UpSta & Num, DnSta & Num=  ,3290, 2 ,3290, 2 , 0 , 0 , 0 ,,
     2.5     2.5
       0     423
     2.5     2.5
       0     423
Pier Skew, UpSta & Num, DnSta & Num=  ,3341, 2 ,3341, 2 , 0 , 0 , 0 ,,
     2.5     2.5
       0     423
     2.5     2.5
       0     423
Pier Skew, UpSta & Num, DnSta & Num=  ,3392, 2 ,3392, 2 , 0 , 0 , 0 ,,
     2.5     2.5
       0     423
     2.5     2.5
       0     423
Pier Skew, UpSta & Num, DnSta & Num=  ,3443, 2 ,3443, 2 , 0 , 0 , 0 ,,
     2.5     2.5
       0     423
     2.5     2.5
       0     423
Pier Skew, UpSta & Num, DnSta & Num=  ,3494, 2 ,3494, 2 , 0 , 0 , 0 ,,
     2.5     2.5
       0     422
     2.5     2.5
       0     422
Pier Skew, UpSta & Num, DnSta & Num=  ,3545, 2 ,3545, 2 , 0 , 0 , 0 ,,
     2.5     2.5
       0     422
     2.5     2.5
       0     422
Pier Skew, UpSta & Num, DnSta & Num=  ,3596, 2 ,3596, 2 , 0 , 0 , 0 ,,
     2.5     2.5
       0     422
     2.5     2.5
       0     422
Pier Skew, UpSta & Num, DnSta & Num=  ,3641, 2 ,3641, 2 , 0 , 0 , 0 ,,
     2.5     2.5
       0     421
     2.5     2.5
       0     421
BR Coef= 1 , 0 , 0 ,1.05, 0 ,,,0.8,-1,0.5,1,
WSPro=,,,, 1 ,,,, 0 ,,,, 0 ,,,,-1 ,-1 ,-1 , 0 , 0 , 0 , 0 , 0
BC Design=,, 0 ,, 0 ,,,,,,
BC HTab HWMax=425.1
BC Use User HTab Curves=0
BC User HTab FreeFlow(D)= 0

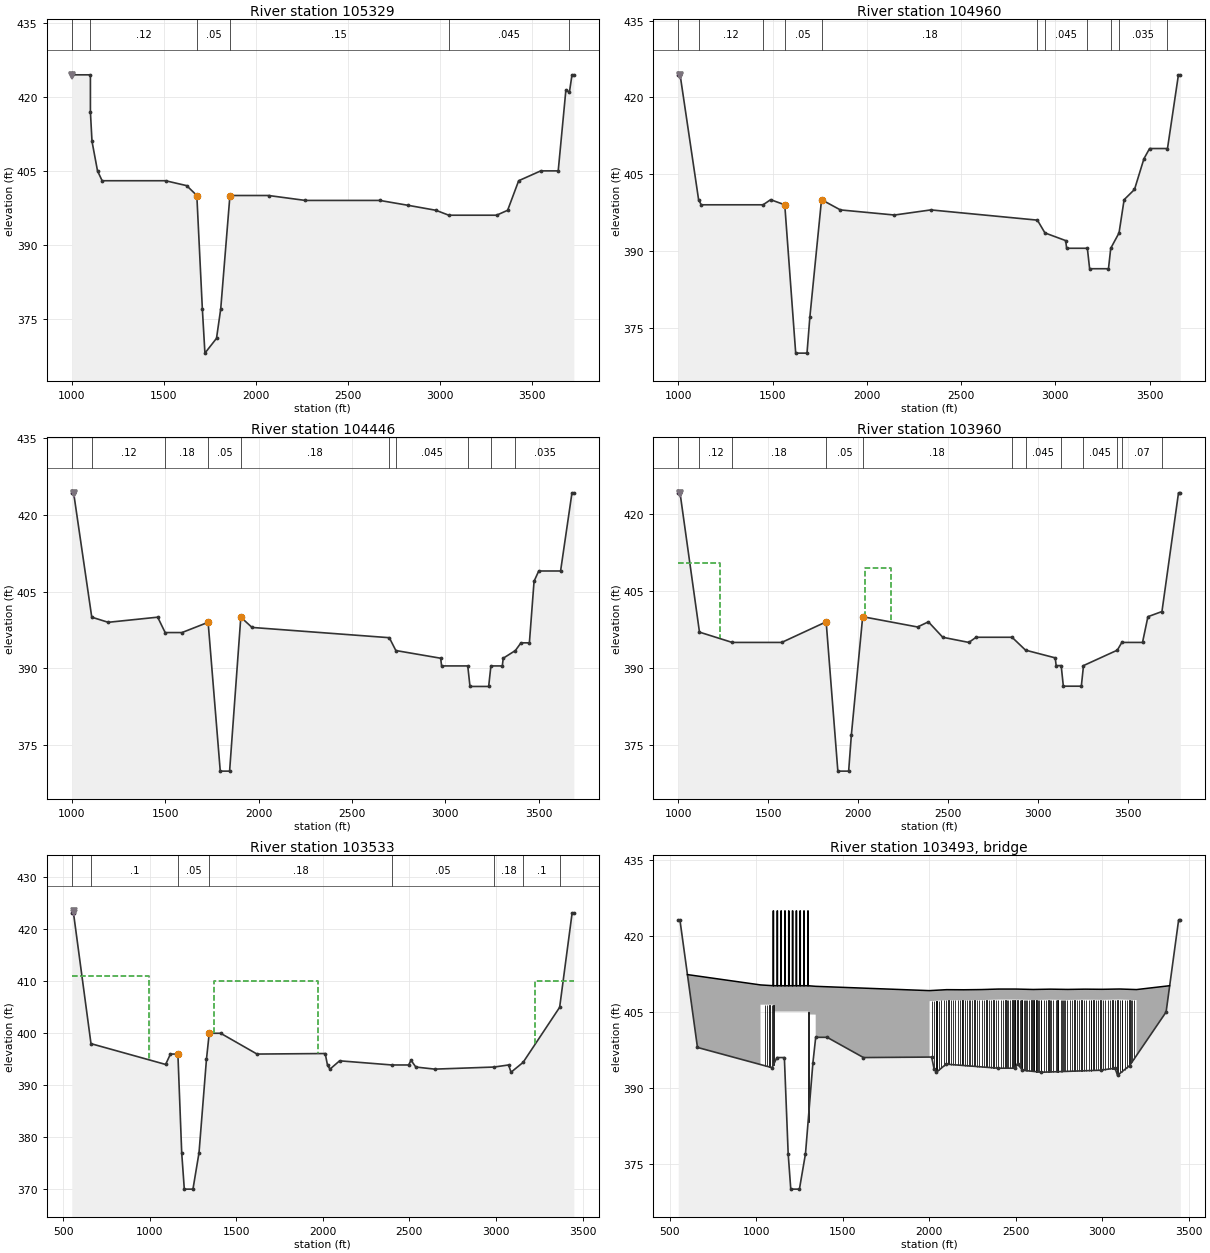
Type RM Length L Ch R = 1 ,105329  ,364,369,364
BEGIN DESCRIPTION:
Downstream bounding cross-section for Martin Luther King Jr. bridge.
Proposed Lamar Levee in LOB.
Proposed Cadillac Heights Levee in ROB.
Wetland Cell B in ROB.
END DESCRIPTION:
XS GIS Cut Line= 3
  2496805.688841 6961521.7474988 2496436.8880104 6960858.4223979
 2495477.0273287 6959136.8876651
#Sta/Elev= 29
    1000   424.5  1101.3   424.5  1101.3     417    1110     411    1140     405
    1165     403    1510     403    1625     402    1680     400    1710     377
    1724     368    1787     371    1810     377    1860     400    2070     400
    2270     399    2675     399    2830     398    2980     397    3050     396
    3310     396    3370     397    3430     403    3550     405    3645     405
  3686.7   421.4    3706     421    3720   424.5    3730   424.5
#Mann= 6 ,-1,0
    1000    .035       0  1101.3     .12       0    1680     .05       0
    1860     .15       0    3050    .045       0    3706    .035       0
Levee=-1,1000,424.24,0,,,,
Bank Sta=1680,1860
XS Rating Curve= 0 ,0
Exp/Cntr=0.5,0.3

Type RM Length L Ch R = 1 ,104960  ,475,514,525
BEGIN DESCRIPTION:
Proposed Lamar Levee in LOB.
Proposed Cadillac Heights Levee in ROB.
Wetland Cell B in ROB.
END DESCRIPTION:
XS GIS Cut Line= 4
  2497100.286026 6961290.5178257        2497100.        6961290.
        2495813.        6958960. 2495812.7139735 6958959.4821743
#Sta/Elev= 30
    1000  424.41    1010  424.41    1108     400    1122     399    1450     399
    1490     400    1565     399    1623     370    1683     370    1698     377
    1760     400    1860     398    2147     397    2340     398    2905     396
    2945   393.5    3055     392    3060   390.5    3170   390.5    3182   386.5
    3282   386.5    3294   390.5    3338   393.5    3365     400    3420     402
    3470     408    3500     410    3595     410    3653  424.41    3663  424.41
#Mann= 11 ,-1,0
    1000    .035       0    1108     .12       0    1450     .15       0
    1565     .05       0    1760     .18       0    2905    .035       0
    2945    .045       0    3170    .025       0    3294    .045       0
    3338    .035       0    3595    .035       0
Levee=-1,1010,424.15,0,,,,
Bank Sta=1565,1760
XS Rating Curve= 0 ,0
Exp/Cntr=0.3,0.1

Type RM Length L Ch R = 1 ,104446  ,470,486,540
BEGIN DESCRIPTION:
Proposed Lamar Levee in LOB.
Proposed Cadillac Heights Levee in ROB.
Wetland Cell B in ROB.
END DESCRIPTION:
XS GIS Cut Line= 4
  2497501.222103 6961112.5586703 2497486.4593714 6961083.2742301
 2496305.9791053 6958741.5868466 2496291.2163731 6958712.3024064
#Sta/Elev= 30
    1000  424.23    1010  424.23    1107     400    1195     399    1460     400
    1500     397    1590     397    1730     399    1795     370    1845     370
    1905     400    1965     398    2700     396    2735   393.5    2975     392
    2980   390.5    3120   390.5    3132   386.5    3232   386.5    3244   390.5
    3305   390.5    3310     392    3375   393.5    3405     395    3450     395
    3475     407    3500     409    3617     409    3678  424.23    3688  424.23
#Mann= 10 ,-1,0
    1000    .035       0    1107     .12       0    1500     .18       0
    1730     .05       0    1905     .18       0    2700    .035       0
    2735    .045       0    3120    .025       0    3244    .045       0
    3375    .035       0
Levee=-1,1010,423.96,0,,,,
Bank Sta=1730,1905
XS Rating Curve= 0 ,0
Exp/Cntr=0.5,0.3

Type RM Length L Ch R = 1 ,103960  ,370,427,470
BEGIN DESCRIPTION:
Proposed Lamar Levee in LOB.
Proposed Cadillac Heights Levee in ROB.
Wetland Cell B in ROB.
END DESCRIPTION:
XS GIS Cut Line= 4
  2497897.047436 6960892.1063969        2497897.        6960892.
        2496761.        6958344.  2496760.952564 6958343.8936032
#Sta/Elev= 30
    1000  424.06    1010  424.06    1118     397    1300     395    1575     395
    1822     399    1887     370    1947     370    1962     377    2025     400
    2330     398    2390     399    2470     396    2615     395    2655     396
    2855     396    2930   393.5    3095     392    3100   390.5    3128   390.5
    3140   386.5    3240   386.5    3252   390.5    3440   393.5    3465     395
    3580     395    3610     400    3688     401    3780  424.06    3790  424.06
#Mann= 12 ,-1,0
    1000    .035       0    1118     .12       0    1300     .18       0
    1822     .05       0    2025     .18       0    2855    .035       0
    2930    .045       0    3128    .025       0    3252    .045       0
    3440    .035       0    3465     .07       0    3688    .035       0
Levee=-1,1010,423.78,0,,,,
#XS Ineff= 2 ,-1
    1000    1230   410.5    2040    2180   409.5
Permanent Ineff=
       F       F
Bank Sta=1822,2025
XS Rating Curve= 0 ,0
Exp/Cntr=0.3,0.1

Type RM Length L Ch R = 1 ,103533  ,80,80,80
BEGIN DESCRIPTION:
Upstream bounding cross-section for Burlington Northern Santa Fe Railroad bridge.
END DESCRIPTION:
XS GIS Cut Line= 5
  2498170.604232 6960759.0442309 2498152.0408107 6960702.2011704
 2497945.7050376 6960070.3803358 2497259.7121223 6958202.2371821
 2497196.0125127 6958028.0902264
#Sta/Elev= 30
     550  423.14     560  423.14     661     398    1092     394    1120     396
    1163     396    1185     377    1200     370    1250     370    1285     377
    1328     395    1344     400    1410     400    1620     396  2013.8   396.1
  2027.5   393.8  2041.5   393.1  2097.1   394.7  2398.2   393.9  2495.8   393.9
  2509.6   394.8  2537.3   393.5  2646.5   393.1  2989.1   393.5  3073.1   393.9
  3087.2   392.5  3156.9   394.4    3368     405    3440  423.14    3450  423.14
#Mann= 8 ,-1,0
     550    .035       0     661      .1       0    1163     .05       0
    1344     .18       0  2398.2     .05       0  2989.1     .18       0
  3156.9      .1       0    3368    .035       0
Levee=-1,560,423.57,0,,,,
#XS Ineff= 3 ,-1
     550     995     411    1374    1971   410.1    3227    3500     410
Permanent Ineff=
       F       F       F
Bank Sta=1163,1344
XS Rating Curve= 0 ,0
Exp/Cntr=0.5,0.3

Type RM Length L Ch R = 3 ,103493  ,,,
BEGIN DESCRIPTION:
Burlington Northern Santa Fe Railroad
END DESCRIPTION:
Node Name=BNSF RR
Bridge Culvert--1,0,-1,-1, 0
Deck Dist Width WeirC Skew NumUp NumDn MinLoCord MaxHiCord MaxSubmerge Is_Ogee
30,20,2.6,0, 61, 61, , , 0.95, 0, 2.5,2.5,,
     603    1025    1025    1099    1099    1100    1100    1122    1122    1123
    1123    1144    1144    1145    1145    1166    1166    1167    1167    1188
    1188    1189    1189    1210    1210    1211    1211    1232    1232    1233
    1233    1254    1254    1255    1255    1276    1276    1277    1277    1299
    1299    1300    1300    1344    1344    2001    2001    2100    2200    2300
    2400    2500    2600    2700    2800    2900    3000    3100    3197    3197
    3388
   412.4  410.36  410.36   410.2     425     425   410.2   410.2     425     425
   410.2   410.2     425     425   410.2   410.2     425     425   410.2   410.2
     425     425   410.2   410.2     425     425   410.2   410.2     425     425
   410.2   410.2     425     425   410.2   410.2     425     425   410.2   410.2
     425     425   410.2  410.08  410.08  409.23  409.23  409.42   409.4  409.44
  409.54  409.54  409.46  409.52  409.47  409.52  409.49  409.55  409.44  409.44
   410.2
     390     390  406.45  406.45   405.1   405.1   405.1   405.1   405.1   405.1
   405.1   405.1   405.1   405.1   405.1   405.1   405.1   405.1   405.1   405.1
   405.1   405.1   405.1   405.1   405.1   405.1   405.1   405.1   405.1   405.1
   405.1   405.1   405.1   405.1   405.1   405.1   405.1   405.1   405.1   405.1
   405.1   405.1  404.52  404.49     394     394  407.15  407.34  407.32  407.36
  407.46  407.46  407.38  407.44  407.39  407.44  407.41  407.47  407.36     390
     390
     603    1025    1025    1099    1099    1100    1100    1122    1122    1123
    1123    1144    1144    1145    1145    1166    1166    1167    1167    1188
    1188    1189    1189    1210    1210    1211    1211    1232    1232    1233
    1233    1254    1254    1255    1255    1276    1276    1277    1277    1299
    1299    1300    1300    1344    1344    2001    2001    2100    2200    2300
    2400    2500    2600    2700    2800    2900    3000    3100    3197    3197
    3388
   412.4  410.36  410.36   410.2     425     425   410.2   410.2     425     425
   410.2   410.2     425     425   410.2   410.2     425     425   410.2   410.2
     425     425   410.2   410.2     425     425   410.2   410.2     425     425
   410.2   410.2     425     425   410.2   410.2     425     425   410.2   410.2
     425     425   410.2  410.08  410.08  409.23  409.23  409.42   409.4  409.44
  409.54  409.54  409.46  409.52  409.47  409.52  409.49  409.55  409.44  409.44
   410.2
     390     390  406.45  406.45   405.1   405.1   405.1   405.1   405.1   405.1
   405.1   405.1   405.1   405.1   405.1   405.1   405.1   405.1   405.1   405.1
   405.1   405.1   405.1   405.1   405.1   405.1   405.1   405.1   405.1   405.1
   405.1   405.1   405.1   405.1   405.1   405.1   405.1   405.1   405.1   405.1
   405.1   405.1  404.52  404.49     394     394  407.15  407.34  407.32  407.36
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Pier Skew, UpSta & Num, DnSta & Num=  ,1038, 2 ,1038, 2 , 0 , 0 , 0 ,,
       1       1
       0     407
       1       1
       0     407
Pier Skew, UpSta & Num, DnSta & Num=  ,1050.7, 2 ,1050.7, 2 , 0 , 0 , 0 ,,
       1       1
       0     407
       1       1
       0     407
Pier Skew, UpSta & Num, DnSta & Num=  ,1063.8, 2 ,1063.8, 2 , 0 , 0 , 0 ,,
       1       1
       0     407
       1       1
       0     407
Pier Skew, UpSta & Num, DnSta & Num=  ,1077, 2 ,1077, 2 , 0 , 0 , 0 ,,
       1       1
       0     407
       1       1
       0     407
Pier Skew, UpSta & Num, DnSta & Num=  ,1090.3, 2 ,1090.3, 2 , 0 , 0 , 0 ,,
       1       1
       0     407
       1       1
       0     407
Pier Skew, UpSta & Num, DnSta & Num=  ,1099, 2 ,1099, 2 , 0 , 0 , 0 ,,
       6       6
       0     407
       6       6
       0     407
Pier Skew, UpSta & Num, DnSta & Num=  ,1300, 2 ,1300, 2 , 0 , 0 , 0 ,,
       6       6
       0     407
       6       6
       0     407
Pier Skew, UpSta & Num, DnSta & Num=  ,2013.8, 2 ,2013.8, 2 , 0 , 0 , 0 ,,
       1       1
       0     500
       1       1
       0     500
Pier Skew, UpSta & Num, DnSta & Num=  ,2027.5, 2 ,2027.5, 2 , 0 , 0 , 0 ,,
       1       1
       0     500
       1       1
       0     500
Pier Skew, UpSta & Num, DnSta & Num=  ,2041.5, 2 ,2041.5, 2 , 0 , 0 , 0 ,,
       1       1
       0     500
       1       1
       0     500
Pier Skew, UpSta & Num, DnSta & Num=  ,2041.5, 2 ,2041.5, 2 , 0 , 0 , 0 ,,
       1       1
       0     500
       1       1
       0     500
Pier Skew, UpSta & Num, DnSta & Num=  ,2055.5, 2 ,2055.5, 2 , 0 , 0 , 0 ,,
       1       1
       0     500
       1       1
       0     500
Pier Skew, UpSta & Num, DnSta & Num=  ,2069.2, 2 ,2069.2, 2 , 0 , 0 , 0 ,,
       1       1
       0     500
       1       1
       0     500
Pier Skew, UpSta & Num, DnSta & Num=  ,2083.7, 2 ,2083.7, 2 , 0 , 0 , 0 ,,
       1       1
       0     500
       1       1
       0     500
Pier Skew, UpSta & Num, DnSta & Num=  ,2097.1, 2 ,2097.1, 2 , 0 , 0 , 0 ,,
       1       1
       0     500
       1       1
       0     500
Pier Skew, UpSta & Num, DnSta & Num=  ,2111.3, 2 ,2111.3, 2 , 0 , 0 , 0 ,,
       1       1
       0     500
       1       1
       0     500
Pier Skew, UpSta & Num, DnSta & Num=  ,2125.3, 2 ,2125.3, 2 , 0 , 0 , 0 ,,
       1       1
       0     500
       1       1
       0     500
Pier Skew, UpSta & Num, DnSta & Num=  ,2136, 2 ,2136, 2 , 0 , 0 , 0 ,,
       1       1
       0     500
       1       1
       0     500
Pier Skew, UpSta & Num, DnSta & Num=  ,2149.2, 2 ,2149.2, 2 , 0 , 0 , 0 ,,
       1       1
       0     500
       1       1
       0     500
Pier Skew, UpSta & Num, DnSta & Num=  ,2163.8, 2 ,2163.8, 2 , 0 , 0 , 0 ,,
       1       1
       0     500
       1       1
       0     500
Pier Skew, UpSta & Num, DnSta & Num=  ,2177.5, 2 ,2177.5, 2 , 0 , 0 , 0 ,,
       1       1
       0     500
       1       1
       0     500
Pier Skew, UpSta & Num, DnSta & Num=  ,2188.4, 2 ,2188.4, 2 , 0 , 0 , 0 ,,
       1       1
       0     500
       1       1
       0     500
Pier Skew, UpSta & Num, DnSta & Num=  ,2192.3, 2 ,2192.3, 2 , 0 , 0 , 0 ,,
       1       1
       0     500
       1       1
       0     500
Pier Skew, UpSta & Num, DnSta & Num=  ,2204.8, 2 ,2204.8, 2 , 0 , 0 , 0 ,,
       1       1
       0     500
       1       1
       0     500
Pier Skew, UpSta & Num, DnSta & Num=  ,2219.1, 2 ,2219.1, 2 , 0 , 0 , 0 ,,
       1       1
       0     500
       1       1
       0     500
Pier Skew, UpSta & Num, DnSta & Num=  ,2229.1, 2 ,2229.1, 2 , 0 , 0 , 0 ,,
       1       1
       0     500
       1       1
       0     500
Pier Skew, UpSta & Num, DnSta & Num=  ,2233.4, 2 ,2233.4, 2 , 0 , 0 , 0 ,,
       1       1
       0     500
       1       1
       0     500
Pier Skew, UpSta & Num, DnSta & Num=  ,2246.6, 2 ,2246.6, 2 , 0 , 0 , 0 ,,
       1       1
       0     500
       1       1
       0     500
Pier Skew, UpSta & Num, DnSta & Num=  ,2260.9, 2 ,2260.9, 2 , 0 , 0 , 0 ,,
       1       1
       0     500
       1       1
       0     500
Pier Skew, UpSta & Num, DnSta & Num=  ,2274.9, 2 ,2274.9, 2 , 0 , 0 , 0 ,,
       1       1
       0     500
       1       1
       0     500
Pier Skew, UpSta & Num, DnSta & Num=  ,2288.4, 2 ,2288.4, 2 , 0 , 0 , 0 ,,
       1       1
       0     500
       1       1
       0     500
Pier Skew, UpSta & Num, DnSta & Num=  ,2302.4, 2 ,2302.4, 2 , 0 , 0 , 0 ,,
       1       1
       0     500
       1       1
       0     500
Pier Skew, UpSta & Num, DnSta & Num=  ,2316.8, 2 ,2316.8, 2 , 0 , 0 , 0 ,,
       1       1
       0     500
       1       1
       0     500
Pier Skew, UpSta & Num, DnSta & Num=  ,2330.1, 2 ,2330.1, 2 , 0 , 0 , 0 ,,
       1       1
       0     500
       1       1
       0     500
Pier Skew, UpSta & Num, DnSta & Num=  ,2342.8, 2 ,2342.8, 2 , 0 , 0 , 0 ,,
       1       1
       0     500
       1       1
       0     500
Pier Skew, UpSta & Num, DnSta & Num=  ,2356.2, 2 ,2356.2, 2 , 0 , 0 , 0 ,,
       1       1
       0     500
       1       1
       0     500
Pier Skew, UpSta & Num, DnSta & Num=  ,2370.9, 2 ,2370.9, 2 , 0 , 0 , 0 ,,
       1       1
       0     500
       1       1
       0     500
Pier Skew, UpSta & Num, DnSta & Num=  ,2385, 2 ,2385, 2 , 0 , 0 , 0 ,,
       1       1
       0     500
       1       1
       0     500
Pier Skew, UpSta & Num, DnSta & Num=  ,2398.2, 2 ,2398.2, 2 , 0 , 0 , 0 ,,
       1       1
       0     500
       1       1
       0     500
Pier Skew, UpSta & Num, DnSta & Num=  ,2412.3, 2 ,2412.3, 2 , 0 , 0 , 0 ,,
       1       1
       0     500
       1       1
       0     500
Pier Skew, UpSta & Num, DnSta & Num=  ,2426.6, 2 ,2426.6, 2 , 0 , 0 , 0 ,,
       1       1
       0     500
       1       1
       0     500
Pier Skew, UpSta & Num, DnSta & Num=  ,2439.9, 2 ,2439.9, 2 , 0 , 0 , 0 ,,
       1       1
       0     500
       1       1
       0     500
Pier Skew, UpSta & Num, DnSta & Num=  ,2450.6, 2 ,2450.6, 2 , 0 , 0 , 0 ,,
       1       1
       0     500
       1       1
       0     500
Pier Skew, UpSta & Num, DnSta & Num=  ,2454.9, 2 ,2454.9, 2 , 0 , 0 , 0 ,,
       1       1
       0     500
       1       1
       0     500
Pier Skew, UpSta & Num, DnSta & Num=  ,2467.4, 2 ,2467.4, 2 , 0 , 0 , 0 ,,
       1       1
       0     500
       1       1
       0     500
Pier Skew, UpSta & Num, DnSta & Num=  ,2481, 2 ,2481, 2 , 0 , 0 , 0 ,,
       1       1
       0     500
       1       1
       0     500
Pier Skew, UpSta & Num, DnSta & Num=  ,2492, 2 ,2492, 2 , 0 , 0 , 0 ,,
       1       1
       0     500
       1       1
       0     500
Pier Skew, UpSta & Num, DnSta & Num=  ,2495.8, 2 ,2495.8, 2 , 0 , 0 , 0 ,,
       1       1
       0     500
       1       1
       0     500
Pier Skew, UpSta & Num, DnSta & Num=  ,2509.6, 2 ,2509.6, 2 , 0 , 0 , 0 ,,
       1       1
       0     500
       1       1
       0     500
Pier Skew, UpSta & Num, DnSta & Num=  ,2523, 2 ,2523, 2 , 0 , 0 , 0 ,,
       1       1
       0     500
       1       1
       0     500
Pier Skew, UpSta & Num, DnSta & Num=  ,2532.9, 2 ,2532.9, 2 , 0 , 0 , 0 ,,
       1       1
       0     500
       1       1
       0     500
Pier Skew, UpSta & Num, DnSta & Num=  ,2537.3, 2 ,2537.3, 2 , 0 , 0 , 0 ,,
       1       1
       0     500
       1       1
       0     500
Pier Skew, UpSta & Num, DnSta & Num=  ,2547.9, 2 ,2547.9, 2 , 0 , 0 , 0 ,,
       1       1
       0     500
       1       1
       0     500
Pier Skew, UpSta & Num, DnSta & Num=  ,2551.6, 2 ,2551.6, 2 , 0 , 0 , 0 ,,
       1       1
       0     500
       1       1
       0     500
Pier Skew, UpSta & Num, DnSta & Num=  ,2559.6, 2 ,2559.6, 2 , 0 , 0 , 0 ,,
       1       1
       0     500
       1       1
       0     500
Pier Skew, UpSta & Num, DnSta & Num=  ,2563.1, 2 ,2563.1, 2 , 0 , 0 , 0 ,,
       1       1
       0     500
       1       1
       0     500
Pier Skew, UpSta & Num, DnSta & Num=  ,2577.4, 2 ,2577.4, 2 , 0 , 0 , 0 ,,
       1       1
       0     500
       1       1
       0     500
Pier Skew, UpSta & Num, DnSta & Num=  ,2590.4, 2 ,2590.4, 2 , 0 , 0 , 0 ,,
       1       1
       0     500
       1       1
       0     500
Pier Skew, UpSta & Num, DnSta & Num=  ,2601.6, 2 ,2601.6, 2 , 0 , 0 , 0 ,,
       1       1
       0     500
       1       1
       0     500
Pier Skew, UpSta & Num, DnSta & Num=  ,2605.6, 2 ,2605.6, 2 , 0 , 0 , 0 ,,
       1       1
       0     500
       1       1
       0     500
Pier Skew, UpSta & Num, DnSta & Num=  ,2616, 2 ,2616, 2 , 0 , 0 , 0 ,,
       1       1
       0     500
       1       1
       0     500
Pier Skew, UpSta & Num, DnSta & Num=  ,2619.4, 2 ,2619.4, 2 , 0 , 0 , 0 ,,
       1       1
       0     500
       1       1
       0     500
Pier Skew, UpSta & Num, DnSta & Num=  ,2629.4, 2 ,2629.4, 2 , 0 , 0 , 0 ,,
       1       1
       0     500
       1       1
       0     500
Pier Skew, UpSta & Num, DnSta & Num=  ,2632.9, 2 ,2632.9, 2 , 0 , 0 , 0 ,,
       1       1
       0     500
       1       1
       0     500
Pier Skew, UpSta & Num, DnSta & Num=  ,2646.5, 2 ,2646.5, 2 , 0 , 0 , 0 ,,
       1       1
       0     500
       1       1
       0     500
Pier Skew, UpSta & Num, DnSta & Num=  ,2646.5, 2 ,2646.5, 2 , 0 , 0 , 0 ,,
       1       1
       0     500
       1       1
       0     500
Pier Skew, UpSta & Num, DnSta & Num=  ,2660.6, 2 ,2660.6, 2 , 0 , 0 , 0 ,,
       1       1
       0     500
       1       1
       0     500
Pier Skew, UpSta & Num, DnSta & Num=  ,2674.4, 2 ,2674.4, 2 , 0 , 0 , 0 ,,
       1       1
       0     500
       1       1
       0     500
Pier Skew, UpSta & Num, DnSta & Num=  ,2688.9, 2 ,2688.9, 2 , 0 , 0 , 0 ,,
       1       1
       0     500
       1       1
       0     500
Pier Skew, UpSta & Num, DnSta & Num=  ,2699.1, 2 ,2699.1, 2 , 0 , 0 , 0 ,,
       1       1
       0     500
       1       1
       0     500
Pier Skew, UpSta & Num, DnSta & Num=  ,2702.5, 2 ,2702.5, 2 , 0 , 0 , 0 ,,
       1       1
       0     500
       1       1
       0     500
Pier Skew, UpSta & Num, DnSta & Num=  ,2715.9, 2 ,2715.9, 2 , 0 , 0 , 0 ,,
       1       1
       0     500
       1       1
       0     500
Pier Skew, UpSta & Num, DnSta & Num=  ,2730.5, 2 ,2730.5, 2 , 0 , 0 , 0 ,,
       1       1
       0     500
       1       1
       0     500
Pier Skew, UpSta & Num, DnSta & Num=  ,2740.9, 2 ,2740.9, 2 , 0 , 0 , 0 ,,
       1       1
       0     500
       1       1
       0     500
Pier Skew, UpSta & Num, DnSta & Num=  ,2744.5, 2 ,2744.5, 2 , 0 , 0 , 0 ,,
       1       1
       0     500
       1       1
       0     500
Pier Skew, UpSta & Num, DnSta & Num=  ,2758.6, 2 ,2758.6, 2 , 0 , 0 , 0 ,,
       1       1
       0     500
       1       1
       0     500
Pier Skew, UpSta & Num, DnSta & Num=  ,2768.3, 2 ,2768.3, 2 , 0 , 0 , 0 ,,
       1       1
       0     500
       1       1
       0     500
Pier Skew, UpSta & Num, DnSta & Num=  ,2772.3, 2 ,2772.3, 2 , 0 , 0 , 0 ,,
       1       1
       0     500
       1       1
       0     500
Pier Skew, UpSta & Num, DnSta & Num=  ,2779.4, 2 ,2779.4, 2 , 0 , 0 , 0 ,,
       1       1
       0     500
       1       1
       0     500
Pier Skew, UpSta & Num, DnSta & Num=  ,2783, 2 ,2783, 2 , 0 , 0 , 0 ,,
       1       1
       0     500
       1       1
       0     500
Pier Skew, UpSta & Num, DnSta & Num=  ,2796.8, 2 ,2796.8, 2 , 0 , 0 , 0 ,,
       1       1
       0     500
       1       1
       0     500
Pier Skew, UpSta & Num, DnSta & Num=  ,2810.9, 2 ,2810.9, 2 , 0 , 0 , 0 ,,
       1       1
       0     500
       1       1
       0     500
Pier Skew, UpSta & Num, DnSta & Num=  ,2824.7, 2 ,2824.7, 2 , 0 , 0 , 0 ,,
       1       1
       0     500
       1       1
       0     500
Pier Skew, UpSta & Num, DnSta & Num=  ,2838.4, 2 ,2838.4, 2 , 0 , 0 , 0 ,,
       1       1
       0     500
       1       1
       0     500
Pier Skew, UpSta & Num, DnSta & Num=  ,2852.5, 2 ,2852.5, 2 , 0 , 0 , 0 ,,
       1       1
       0     500
       1       1
       0     500
Pier Skew, UpSta & Num, DnSta & Num=  ,2866.1, 2 ,2866.1, 2 , 0 , 0 , 0 ,,
       1       1
       0     500
       1       1
       0     500
Pier Skew, UpSta & Num, DnSta & Num=  ,2879.7, 2 ,2879.7, 2 , 0 , 0 , 0 ,,
       1       1
       0     500
       1       1
       0     500
Pier Skew, UpSta & Num, DnSta & Num=  ,2894.7, 2 ,2894.7, 2 , 0 , 0 , 0 ,,
       1       1
       0     500
       1       1
       0     500
Pier Skew, UpSta & Num, DnSta & Num=  ,2907.2, 2 ,2907.2, 2 , 0 , 0 , 0 ,,
       1       1
       0     500
       1       1
       0     500
Pier Skew, UpSta & Num, DnSta & Num=  ,2921.7, 2 ,2921.7, 2 , 0 , 0 , 0 ,,
       1       1
       0     500
       1       1
       0     500
Pier Skew, UpSta & Num, DnSta & Num=  ,2932.1, 2 ,2932.1, 2 , 0 , 0 , 0 ,,
       1       1
       0     500
       1       1
       0     500
Pier Skew, UpSta & Num, DnSta & Num=  ,2936.3, 2 ,2936.3, 2 , 0 , 0 , 0 ,,
       1       1
       0     500
       1       1
       0     500
Pier Skew, UpSta & Num, DnSta & Num=  ,2948.8, 2 ,2948.8, 2 , 0 , 0 , 0 ,,
       1       1
       0     500
       1       1
       0     500
Pier Skew, UpSta & Num, DnSta & Num=  ,2963.2, 2 ,2963.2, 2 , 0 , 0 , 0 ,,
       1       1
       0     500
       1       1
       0     500
Pier Skew, UpSta & Num, DnSta & Num=  ,2976.8, 2 ,2976.8, 2 , 0 , 0 , 0 ,,
       1       1
       0     500
       1       1
       0     500
Pier Skew, UpSta & Num, DnSta & Num=  ,2989.1, 2 ,2989.1, 2 , 0 , 0 , 0 ,,
       1       1
       0     500
       1       1
       0     500
Pier Skew, UpSta & Num, DnSta & Num=  ,3002.9, 2 ,3002.9, 2 , 0 , 0 , 0 ,,
       1       1
       0     500
       1       1
       0     500
Pier Skew, UpSta & Num, DnSta & Num=  ,3017.3, 2 ,3017.3, 2 , 0 , 0 , 0 ,,
       1       1
       0     500
       1       1
       0     500
Pier Skew, UpSta & Num, DnSta & Num=  ,3031.3, 2 ,3031.3, 2 , 0 , 0 , 0 ,,
       1       1
       0     500
       1       1
       0     500
Pier Skew, UpSta & Num, DnSta & Num=  ,3045.2, 2 ,3045.2, 2 , 0 , 0 , 0 ,,
       1       1
       0     500
       1       1
       0     500
Pier Skew, UpSta & Num, DnSta & Num=  ,3058.8, 2 ,3058.8, 2 , 0 , 0 , 0 ,,
       1       1
       0     500
       1       1
       0     500
Pier Skew, UpSta & Num, DnSta & Num=  ,3073.1, 2 ,3073.1, 2 , 0 , 0 , 0 ,,
       1       1
       0     500
       1       1
       0     500
Pier Skew, UpSta & Num, DnSta & Num=  ,3087.2, 2 ,3087.2, 2 , 0 , 0 , 0 ,,
       1       1
       0     500
       1       1
       0     500
Pier Skew, UpSta & Num, DnSta & Num=  ,3101, 2 ,3101, 2 , 0 , 0 , 0 ,,
       1       1
       0     500
       1       1
       0     500
Pier Skew, UpSta & Num, DnSta & Num=  ,3111.5, 2 ,3111.5, 2 , 0 , 0 , 0 ,,
       1       1
       0     500
       1       1
       0     500
Pier Skew, UpSta & Num, DnSta & Num=  ,3115.2, 2 ,3115.2, 2 , 0 , 0 , 0 ,,
       1       1
       0     500
       1       1
       0     500
Pier Skew, UpSta & Num, DnSta & Num=  ,3128.4, 2 ,3128.4, 2 , 0 , 0 , 0 ,,
       1       1
       0     500
       1       1
       0     500
Pier Skew, UpSta & Num, DnSta & Num=  ,3142.5, 2 ,3142.5, 2 , 0 , 0 , 0 ,,
       1       1
       0     500
       1       1
       0     500
Pier Skew, UpSta & Num, DnSta & Num=  ,3156.9, 2 ,3156.9, 2 , 0 , 0 , 0 ,,
       1       1
       0     500
       1       1
       0     500
Pier Skew, UpSta & Num, DnSta & Num=  ,3166.6, 2 ,3166.6, 2 , 0 , 0 , 0 ,,
       1       1
       0     500
       1       1
       0     500
Pier Skew, UpSta & Num, DnSta & Num=  ,3170.3, 2 ,3170.3, 2 , 0 , 0 , 0 ,,
       1       1
       0     500
       1       1
       0     500
Pier Skew, UpSta & Num, DnSta & Num=  ,3184, 2 ,3184, 2 , 0 , 0 , 0 ,,
       1       1
       0     500
       1       1
       0     500
Abutment Skew #Up #Dn= , 2 , 2
    1025    1055
     405     395
    1025    1055
     405     395
Abutment Skew #Up #Dn= , 2 , 2
    1328    1344
     395     403
    1328    1344
     395     403
Abutment Skew #Up #Dn= , 2 , 2
    2001    2020
     402     395
    2001    2020
     402     395
Abutment Skew #Up #Dn= , 2 , 2
    3170    3197
     395     404
    3170    3197
     395     404
BR Coef= 1 , 1 , 1 ,2.5, 0 ,,,0.8,0,1.2,1,
WSPro=,,,, 1 ,,,, 0 ,,,, 0 ,,,,-1 ,-1 ,-1 , 0 , 0 , 0 , 0 , 0
BC Design=,, 0 ,, 0 ,,,,,,
BC HTab HWMax=424.1
BC Use User HTab Curves=0
BC User HTab FreeFlow(D)= 0

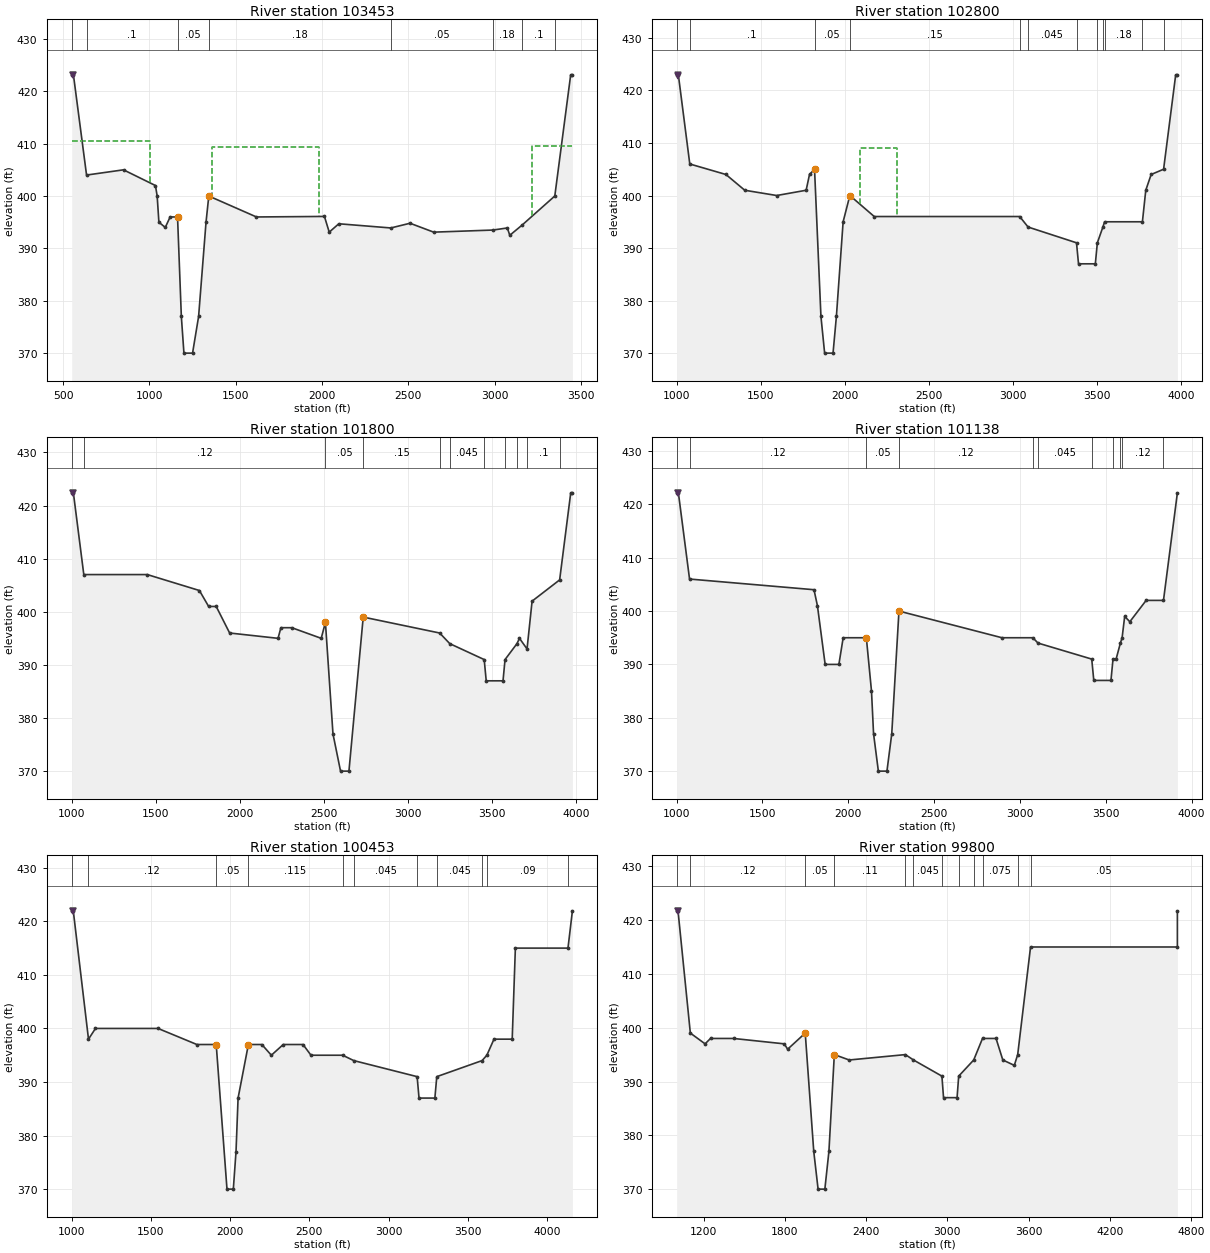
Type RM Length L Ch R = 1 ,103453  ,710,653,420
BEGIN DESCRIPTION:
Downstream bounding cross-section for Burlington Northern Santa Fe Railroad bridge.
Proposed Lamar Levee in LOB.
Proposed Cadillac Heights Levee in ROB.
Wetland Cell C in ROB.
END DESCRIPTION:
XS GIS Cut Line= 5
  2498247.953782 6960742.3324805 2498232.6671317 6960696.0261033
 2498025.4601494 6960068.3539851 2497336.8467917 6958177.8715374
  2497274.850517 6958010.7458655
#Sta/Elev= 30
     550  423.14     560  423.14     636     404     850     405    1035     402
    1045     400    1055     395    1092     394    1120     396    1163     396
    1185     377    1200     370    1250     370    1285     377    1328     395
    1344     400    1620     396  2013.8   396.1  2041.5   393.1  2097.1   394.7
  2398.2   393.9  2509.6   394.8  2646.5   393.1  2989.1   393.5  3073.1   393.9
  3087.2   392.5  3156.9   394.4    3348     400    3440  423.14    3450  423.14
#Mann= 8 ,-1,0
     550    .035       0     636      .1       0    1163     .05       0
    1344     .18       0  2398.2     .05       0  2989.1     .18       0
  3156.9      .1       0    3348    .035       0
Levee=-1,560,423.05,0,,,,
#XS Ineff= 3 ,-1
     550    1005   410.5    1364    1981   409.3    3217    3500   409.5
Permanent Ineff=
       F       F       F
Bank Sta=1163,1344
XS Rating Curve= 0 ,0
Exp/Cntr=0.5,0.3

Type RM Length L Ch R = 1 ,102800  ,650,1000,450
BEGIN DESCRIPTION:
Proposed Lamar Levee in LOB.
Proposed Cadillac Heights Levee in ROB.
Wetland Cell C in ROB.
END DESCRIPTION:
XS GIS Cut Line= 5
  2498934.098435 6960461.1773899 2498583.9807323 6959710.2029748
 2498501.2574682 6959645.6246745 2498418.5342041 6959581.0463743
 2497437.6254164 6957907.8480504
#Sta/Elev= 30
    1000  422.97    1010  422.97    1078     406    1293     404    1405     401
    1595     400    1770     401    1790     404    1820     405    1858     377
    1880     370    1930     370    1950     377    1990     395    2030     400
    2175     396    3040     396    3090     394    3378     391    3390     387
    3490     387    3502     391    3535     394    3545     395    3770     395
    3790     401    3822     404    3896     405    3968  422.97    3978  422.97
#Mann= 12 ,-1,0
    1000    .035       0    1078      .1       0    1820     .05       0
    2030     .15       0    3040    .035       0    3090    .045       0
    3378    .025       0    3502    .045       0    3535    .035       0
    3545     .18       0    3770      .1       0    3896    .035       0
Levee=-1,1010,422.82,0,,,,
#XS Ineff= 1 ,-1
    2090    2310     409
Permanent Ineff=
       F
Bank Sta=1820,2030
XS Rating Curve= 0 ,0
Exp/Cntr=0.3,0.1

Type RM Length L Ch R = 1 ,101800  ,480,662,500
BEGIN DESCRIPTION:
Proposed Lamar Levee in LOB.
Proposed Cadillac Heights Levee in ROB.
Wetland Cell C in ROB.
END DESCRIPTION:
XS GIS Cut Line= 6
  2499501.994674 6960004.6961214 2499490.6079812 6959989.1907072
 2498602.0513226 6958779.2311295 2498416.9730206 6958651.4884415
  2497707.353757 6957664.6777484 2497696.1225182 6957649.0593638
#Sta/Elev= 30
    1000  422.39    1010  422.39    1072     407    1450     407    1760     404
    1815     401    1860     401    1940     396    2228     395    2245     397
    2310     397    2485     395    2510     398    2555     377    2600     370
    2650     370    2735     399    3190     396    3250     394    3455     391
    3467     387    3567     387    3579     391    3650     394    3665     395
    3710     393    3740     402    3904     406    3970  422.39    3980  422.39
#Mann= 11 ,-1,0
    1000    .035       0    1072     .12       0    2510     .05       0
    2735     .15       0    3190    .035       0    3250    .045       0
    3455    .025       0    3579    .045       0    3650    .035       0
    3710      .1       0    3904    .035       0
Levee=-1,1010,422.37,0,,,,
Bank Sta=2510,2735
XS Rating Curve= 0 ,0
Exp/Cntr=0.3,0.1

Type RM Length L Ch R = 1 ,101138  ,660,685,570
BEGIN DESCRIPTION:
Proposed Lamar Levee in LOB.
Proposed Cadillac Heights Levee in ROB.
Wetland Cell C in ROB.
END DESCRIPTION:
XS GIS Cut Line= 2
  2499904.102095 6959551.8201397 2497989.1152712 6957351.4305236
#Sta/Elev= 30
    1000  422.16    1010  422.16    1075     406    1800     404    1820     401
    1865     390    1945     390    1970     395    2105     395    2135     385
    2147     377    2175     370    2225     370    2253     377    2295     400
    2895     395    3075     395    3105     394    3418     391    3430     387
    3530     387    3542     391    3560     391    3585     394    3595     395
    3610     399    3640     398    3735     402    3836     402    3917  422.16
#Mann= 11 ,-1,0
    1000    .035       0    1075     .12       0    2105     .05       0
    2295     .12       0    3075    .035       0    3105    .045       0
    3418    .025       0    3542    .045       0    3585    .035       0
    3595     .12       0    3836    .035       0
Levee=-1,1010,422.15,0,,,,
Bank Sta=2105,2295
XS Rating Curve= 0 ,0
Exp/Cntr=0.5,0.3

Type RM Length L Ch R = 1 ,100453  ,665,653,590
BEGIN DESCRIPTION:
Proposed Lamar Levee in LOB.
Proposed Cadillac Heights Levee in ROB.
Wetland Cell C in ROB.
END DESCRIPTION:
XS GIS Cut Line= 5
   2500389.11239 6959074.5956165 2499777.0538815 6958407.0007053
 2499701.2337503 6958338.0899429 2499625.4136191 6958269.1791805
 2498043.1042715 6956966.7704999
#Sta/Elev= 30
    1000  421.96    1010  421.96    1106     398    1150     400    1545     400
    1790     397    1912     397    1980     370    2020     370    2037     377
    2050     387    2115     397    2200     397    2260     395    2335     397
    2460     397    2510     395    2710     395    2780     394    3180     391
    3192     387    3292     387    3304     391    3590     394    3620     395
    3665     398    3780     398    3800     415    4132     415    4160  421.96
#Mann= 11 ,-1,0
    1000    .035       0    1106     .12       0    1912     .05       0
    2115    .115       0    2710    .035       0    2780    .045       0
    3180    .025       0    3304    .045       0    3590    .035       0
    3620     .09       0    4132    .035       0
Levee=-1,1010,421.96,0,,,,
Bank Sta=1912,2115
XS Rating Curve= 0 ,0
Exp/Cntr=0.3,0.1

Type RM Length L Ch R = 1 ,99800   ,515,633,510
BEGIN DESCRIPTION:
Proposed Lamar Levee in LOB.
Wetland Cell C in ROB.
Central Wastewater Treatment Plant in ROB.
END DESCRIPTION:
XS GIS Cut Line= 5
  2500839.910034 6958574.4414097 2500838.2624478 6958572.8419717
        2499592.        6957363. 2498138.3975435 6956050.4768362
 2498136.6932556 6956048.9379579
#Sta/Elev= 30
    1000  421.71    1010  421.71    1101     399    1210     397    1250     398
    1420     398    1795     397    1820     396    1950     399    2013     377
    2045     370    2095     370    2125     377    2165     395    2275     394
    2690     395    2750     394    2960     391    2972     387    3072     387
    3084     391    3195     394    3260     398    3360     398    3410     394
    3495     393    3520     395    3615     415    4700     415    4700  421.71
#Mann= 12 ,-1,0
    1000    .035       0    1101     .12       0    1950     .05       0
    2165     .11       0    2690    .035       0    2750    .045       0
    2960    .025       0    3084    .045       0    3195    .035       0
    3260    .075       0    3520    .035       0    3615     .05       0
Levee=-1,1010,421.72,0,,,,
Bank Sta=1950,2165
XS Rating Curve= 0 ,0
Exp/Cntr=0.3,0.1