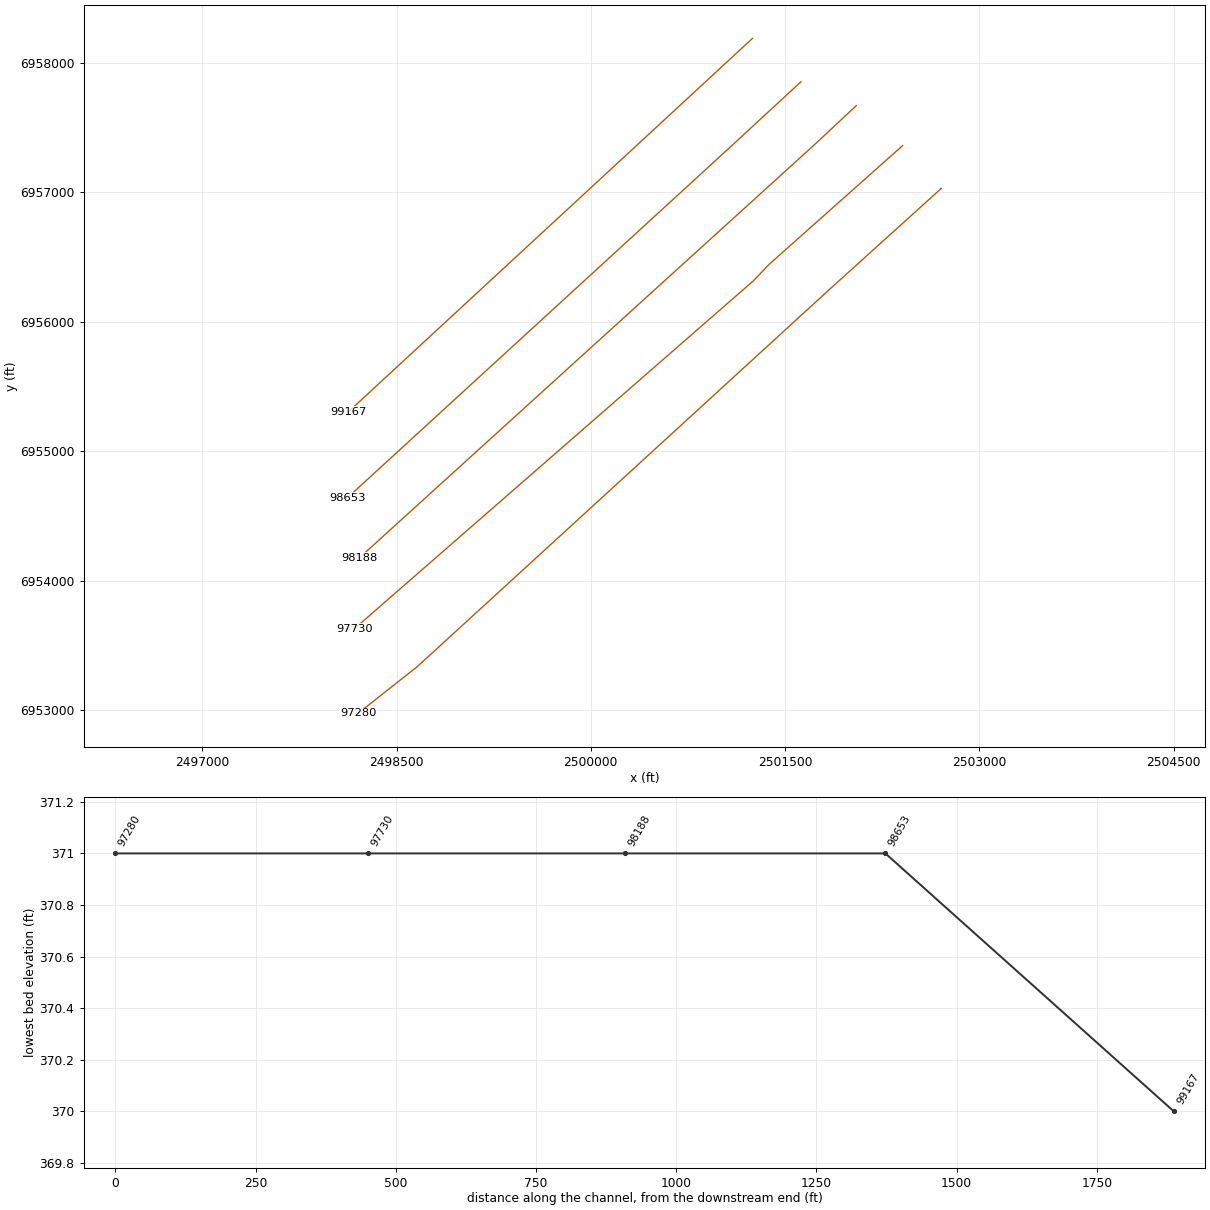
HEC-RAS study CDC_Consolidated_Model.prj: Upper Trinity CDC Consolidated Model

--- CDC_Consolidated_Model.g12 (geometry) --- (continued)

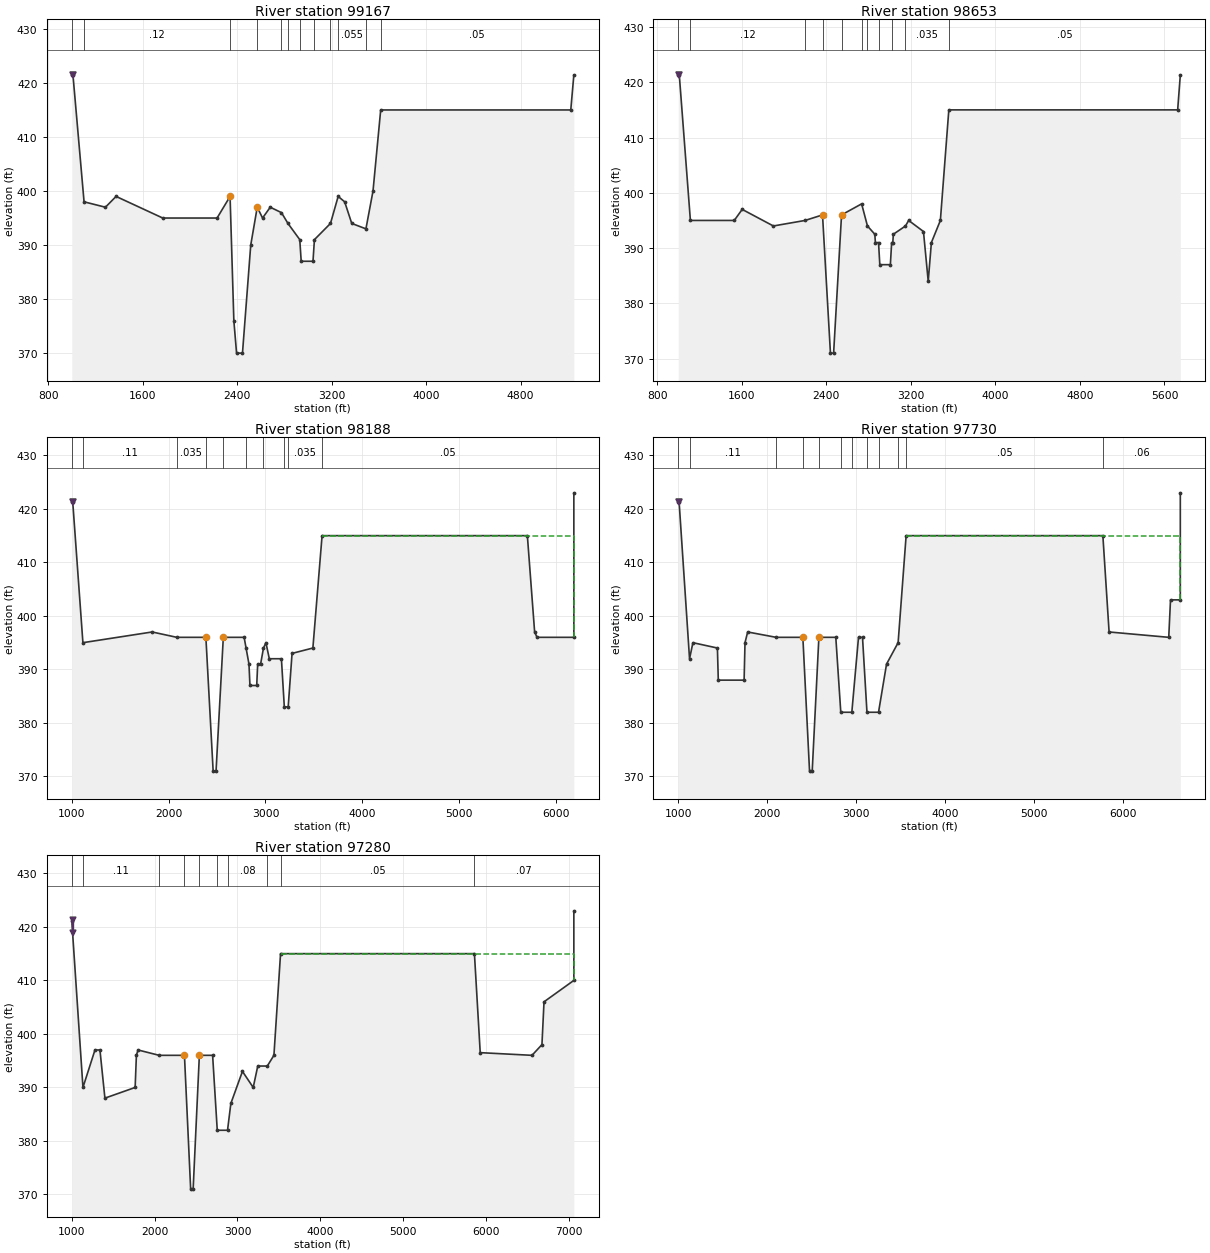
Type RM Length L Ch R = 1 ,99167   ,514,514,514
BEGIN DESCRIPTION:
Proposed Lamar Levee in LOB.
Wetland Cell C in ROB.
Central Wastewater Treatment Plant in ROB.
END DESCRIPTION:
XS GIS Cut Line= 2
  2501249.178369 6958187.4503001 2498127.4416112 6955303.4843482
#Sta/Elev= 30
    1000  421.48    1010  421.48    1104     398    1285     397    1375     399
    1770     395    2230     395    2340     399    2372     376    2395     370
    2445     370    2515     390    2570     397    2615     395    2680     397
    2775     396    2830     394    2930     391    2942     387    3042     387
    3054     391    3190     394    3255     399    3310     398    3370     394
    3490     393    3550     400    3615     415    5224     415    5250  421.48
#Mann= 12 ,-1,0
    1000    .035       0    1104     .12       0    2340     .05       0
    2570     .11       0    2775    .035       0    2830    .045       0
    2930    .025       0    3054    .045       0    3190    .035       0
    3255    .055       0    3490    .035       0    3615     .05       0
Levee=-1,1010,421.5,0,,,,
Bank Sta=2340,2570
XS Rating Curve= 0 ,0
Exp/Cntr=0.3,0.1

Type RM Length L Ch R = 1 ,98653   ,430,465,430
BEGIN DESCRIPTION:
Proposed Lamar Levee in LOB.
Wetland Cell C in ROB.
Central Wastewater Treatment Plant in ROB.
END DESCRIPTION:
XS GIS Cut Line= 5
   2501623.42822 6957852.7918731   2501622.61965 6957852.0450024
        2501104.        6957373. 2498123.3384938 6954643.2180134
 2498122.5267496 6954642.4745929
#Sta/Elev= 30
    1000  421.31    1010  421.31    1115     395    1530     395    1605     397
    1900     394    2200     395    2365     396    2440     371    2470     371
    2545     396    2735     398    2790     394    2860   392.5    2865     391
    2895     391    2907     387    3007     387    3019     391    3030     391
    3035   392.5    3150     394    3180     395    3320     393    3365     384
    3395     391    3480     395    3560     415    5725     415    5750  421.31
#Mann= 11 ,-1,0
    1000    .035       0    1115     .12       0    2200      .1       0
    2365     .05       0    2545      .1       0    2735    .035       0
    2790    .045       0    2895    .025       0    3019    .045       0
    3150    .035       0    3560     .05       0
Levee=-1,1010,421.34,0,,,,
#XS Ineff= 2 , 0
            1010  421.31
Permanent Ineff=
       F       F
Bank Sta=2365,2545
XS Rating Curve= 0 ,0
Exp/Cntr=0.3,0.1

Type RM Length L Ch R = 1 ,98188   ,458,458,458
BEGIN DESCRIPTION:
Proposed Lamar Levee in LOB.
Wetland Cell C in ROB.
Central Wastewater Treatment Plant in ROB.
END DESCRIPTION:
XS GIS Cut Line= 4
  2502049.602657 6957667.4940452        2501740.        6957378.
 2498231.8958875  6954194.091795 2498214.4059711 6954178.2181817
#Sta/Elev= 30
    1000  421.29    1010  421.29    1115     395    1830     397    2085     396
    2385     396    2460     371    2490     371    2565     396    2780     396
    2800     394    2830     391    2840     387    2910     387    2920     391
    2950     391    2980     394    3005     395    3040     392    3165     392
    3195     383    3235     383    3275     393    3490     394    3585     415
    5705     415    5780     397    5805     396    6185     396    6185     423
#Mann= 10 ,-1,0
    1000    .035       0    1115     .11       0    2085    .035       0
    2385     .05       0    2565    .035       0    2800    .045       0
    2980    .035       0    3195     .03       0    3235    .035       0
    3585     .05       0
Levee=-1,1010,421.32,0,,,,
#XS Ineff= 2 , 0
                            3585             415
Permanent Ineff=
       F       F
Bank Sta=2385,2565
XS Rating Curve= 0 ,0
Exp/Cntr=0.3,0.1

Type RM Length L Ch R = 1 ,97730   ,450,450,450
BEGIN DESCRIPTION:
Proposed Lamar Levee in LOB.
Central Wastewater Treatment Plant in ROB.
END DESCRIPTION:
XS GIS Cut Line= 6
  2502407.266459 6957358.6452579 2502398.4286302 6957350.7895976
 2501378.9196079 6956444.5810322 2501253.8237876  6956314.080517
 2498184.7458212 6953638.6087309 2498175.8326476 6953630.8386628
#Sta/Elev= 30
    1000  421.25    1010  421.25    1127     392    1165     395    1440     394
    1450     388    1740     388    1750     395    1780     397    2100     396
    2400     396    2475     371    2505     371    2580     396    2770     396
    2826     382    2950     382    3025     396    3070     396    3120     382
    3250     382    3340     391    3470     395    3560     415    5770     415
    5840     397    6510     396    6530     403    6640     403    6640     423
#Mann= 12 ,-1,0
    1000    .035       0    1127     .11       0    2100    .035       0
    2400     .05       0    2580    .035       0    2826     .03       0
    2950    .045       0    3120     .03       0    3250    .045       0
    3470    .035       0    3560     .05       0    5770     .06       0
Levee=-1,1010,421.27,0,,,,
#XS Ineff= 2 , 0
                            3560             415
Permanent Ineff=
       F       F
Bank Sta=2400,2580
XS Rating Curve= 0 ,0
Exp/Cntr=0.3,0.1

Type RM Length L Ch R = 1 ,97280   ,450,485,540
BEGIN DESCRIPTION:
Interstate Highway 45.  Location where the bridge crosses the Trinity River.
Proposed Lamar Levee in LOB.
Central Wastewater Treatment Plant in ROB.
END DESCRIPTION:
Node Name=IH 45
XS GIS Cut Line= 6
   2502706.97689 6957029.2964569 2502706.9768906 6957029.2964569
        2501833.        6956240.        2498661.        6953338.
 2498206.0817856 6952979.2088192 2498203.1164764 6952976.8700982
#Sta/Elev= 30
    1000  421.18    1135     390    1280     397    1340     397    1400     388
    1765     390    1780     396    1800     397    2055     396    2360     396
    2435     371    2465     371    2540     396    2700     396    2756     382
    2880     382    2920     387    3060     393    3190     390    3245     394
    3360     394    3440     396    3520     415    5860     415    5930   396.5
    6555     396    6675     398    6700     406    7060     410    7060     423
#Mann= 10 ,-1,0
    1000    .035       0    1135     .11       0    2055    .035       0
    2360     .05       0    2540    .035       0    2756     .03       0
    2880     .08       0    3360    .035       0    3520     .05       0
    5860     .07       0
Levee=-1,1010,421.21,0,,,,
#XS Ineff= 2 , 0
                            3520             415
Permanent Ineff=
       F       F
Bank Sta=2360,2540
XS Rating Curve= 0 ,0
Exp/Cntr=0.3,0.1