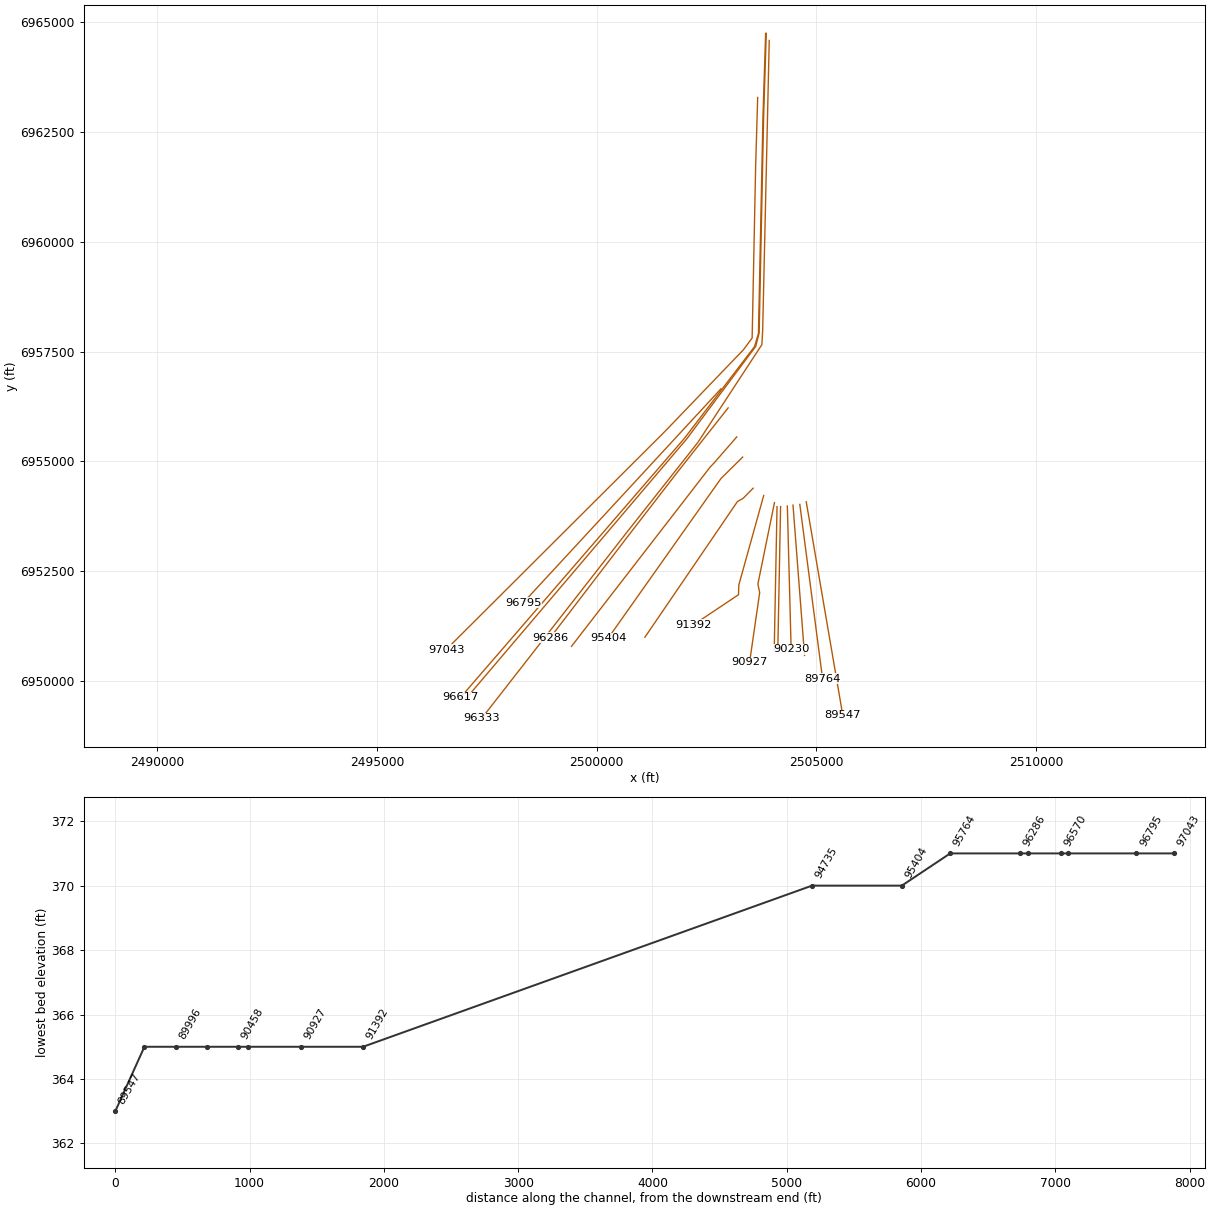
HEC-RAS study CDC_Consolidated_Model.prj: Upper Trinity CDC Consolidated Model

--- CDC_Consolidated_Model.g12 (geometry) --- (continued)

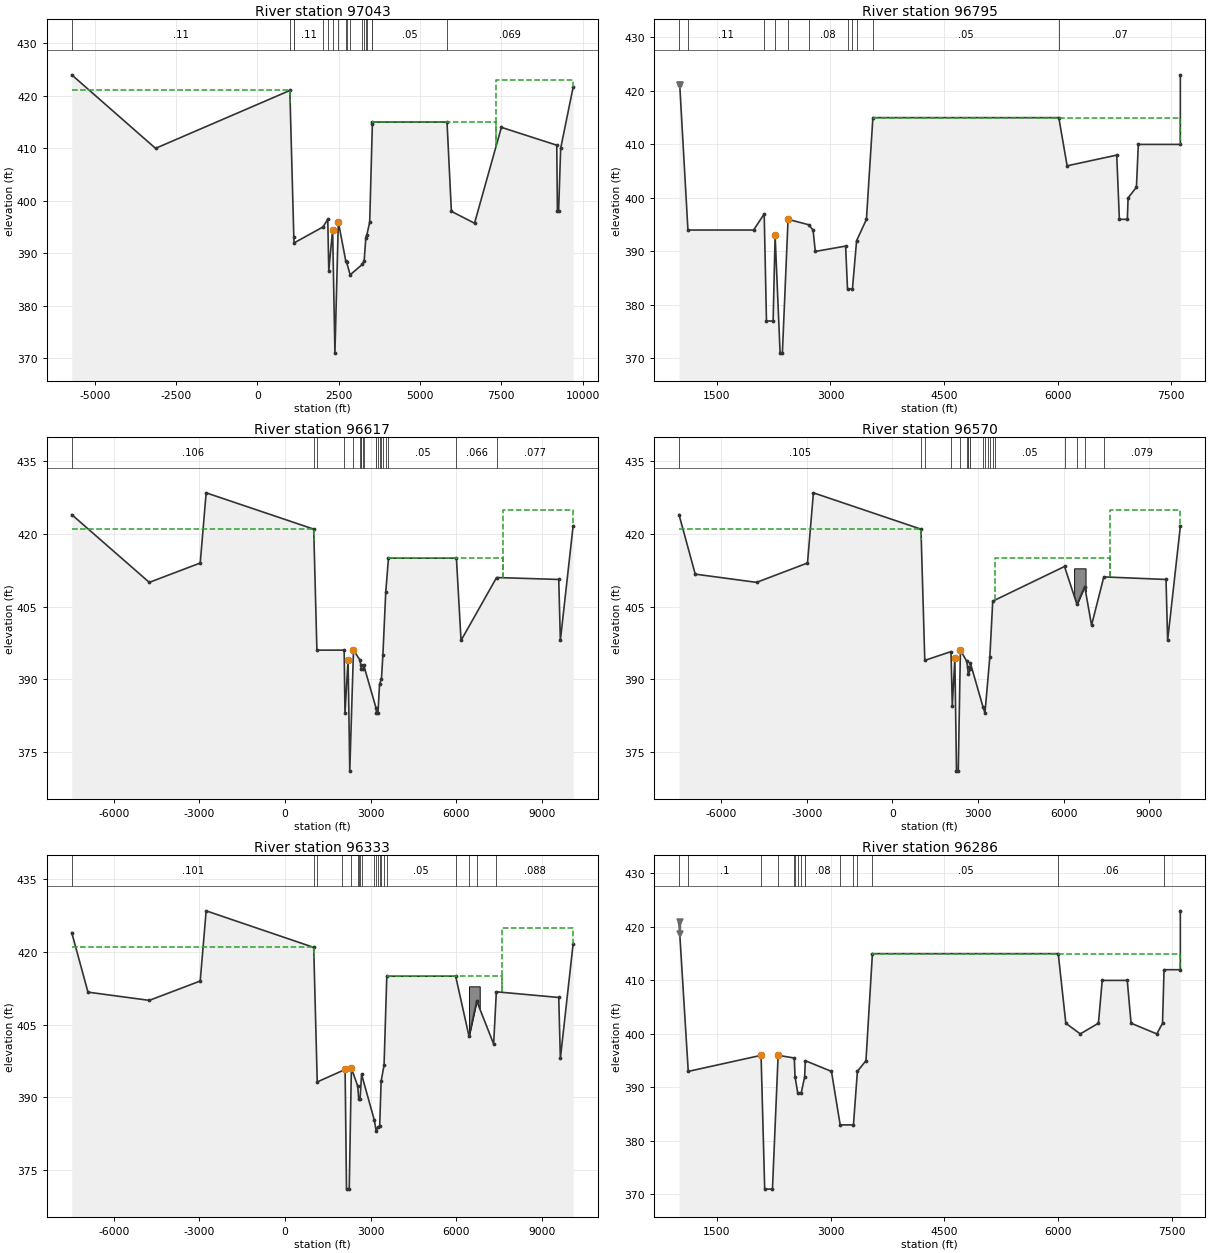
Type RM Length L Ch R = 1 ,97043   ,256,276,307
BEGIN DESCRIPTION:
This cross section corresponds to cross section 97043 of the non-georeferenced CDC model which was the source of this model.
Interpolated cross-section.
Valley storage site set at elev. 398.0
END DESCRIPTION:
XS GIS Cut Line= 6
2503664.699395696963280.515780052503618.062349836961696.86343555
2503539.001156246957808.523443222503343.114080856957542.85009006
2501556.796459266955684.176313972496575.17978209 6950716.0792948
#Sta/Elev= 30
 -5707.3     424 -3130.4     410    1000  421.02 1122.33  393.04 1130.59  391.99
  2020.5  395.03 2166.25  396.49 2197.35  386.72 2315.53  394.53 2386.13     371
 2491.13     396 2722.55  388.46 2743.54  388.35 2855.39  385.91 3224.99  387.88
 3285.76  388.62 3337.17  393.02 3369.64  393.56 3455.35  395.95 3538.16  414.67
 3541.06     415 5833.22     415    5968     398 6679.26  395.74  7505.1     414
    9208   410.6    9228     398  9264.5     398  9328.3     410  9709.9   421.6
#Mann= 18 ,-1,0
 -5707.3     .11       0    1000    .035       0 1122.33    .108       0
 1130.59     .11       0  2020.5    .046       0 2166.25    .046       0
 2315.53     .05       0 2491.13    .035       0 2722.55    .053       0
 2743.54    .058       0 2855.39    .074       0 3224.99    .039       0
 3285.76    .061       0 3337.17    .036       0 3369.64    .036       0
 3538.16     .05       0 3541.06     .05       0 5833.22    .069       0
#XS Ineff= 3 ,-1
 -5707.3 1010.37  421.02 3541.067333.649     4157333.649  9709.9     423
Permanent Ineff=
       F       F       F
Bank Sta=2315.53,2491.13
XS Rating Curve= 0 ,0
Exp/Cntr=0.3,0.1

Type RM Length L Ch R = 1 ,96795   ,480,509,560
BEGIN DESCRIPTION:
Proposed Lamar Levee in LOB.
Central Wastewater Treatment Plant in ROB.
END DESCRIPTION:
XS GIS Cut Line= 2
  2502828.570465 6956650.5566272 2498335.0185089 6951789.2408775
#Sta/Elev= 30
    1000  421.05    1010  421.05    1118     394    1985     394    2125     397
    2155     377    2243     377    2269     393    2335     371    2365     371
    2440     396    2710     395    2770     394    2800     390    3200     391
    3225     383    3290     383    3345     392    3475     396    3560     415
    6015     415    6125     406    6780     408    6815     396    6920     396
    6930     400    7040     402    7065     410    7620     410    7620     423
#Mann= 11 ,-1,0
    1000    .035       0    1118     .11       0    2125     .05       0
    2269     .05       0    2440    .035       0    2710     .08       0
    3225     .03       0    3290     .08       0    3345    .035       0
    3560     .05       0    6015     .07       0
Levee=-1,1010,421.08,0,,,,
#XS Ineff= 2 , 0
                            3560             415
Permanent Ineff=
       F       F
Bank Sta=2269,2440
XS Rating Curve= 0 ,0
Exp/Cntr=0.3,0.1

Type RM Length L Ch R = 1 ,96617   ,47,50,55
BEGIN DESCRIPTION:
This cross section corresponds to cross section 96617 of the non-georeferenced CDC model which was the source of this model.
Interpolated cross-section.
Valley storage site set at elev. 398.0
END DESCRIPTION:
XS GIS Cut Line= 6
 2503845.88341656964736.677237792503785.267067916962844.38640296
2503682.659005436957913.329007882503593.552884436957611.08650213
2502000.415650766955527.412519892496904.831681856949629.13527447
#Sta/Elev= 30
 -7474.3     424   -4758     410 -2974.4     414   -2767   428.5    1000     421
    1112     396    2067     396    2095     383    2204     394    2263     371
    2393     396    2613     394    2648     393    2666     392    2738     392
    2746     393    3185     384    3199     383    3251     383    3306     389
    3372     390    3423     395    3523     408    3618     415    5998     415
    6160     398    7405     411  9581.8   410.6  9638.3     398 10083.7   421.6
#Mann= 20 ,-1,0
 -7474.3    .106       0    1000    .035       0    1112    .106       0
    2067    .052       0    2393    .058       0    2613    .062       0
    2648    .059       0    2666    .066       0    2738     .06       0
    2746    .075       0    3185    .031       0    3199    .037       0
    3251    .068       0    3306    .044       0    3372    .054       0
    3423     .04       0    3523    .047       0    3618     .05       0
    5998    .066       0    7405    .077       0
#XS Ineff= 3 ,-1
 -7474.3    1011     421    3618    7617     415    7617 10083.7     425
Permanent Ineff=
       F       F       F
Bank Sta=2204,2393
XS Rating Curve= 0 ,0
Exp/Cntr=0.3,0.1

Type RM Length L Ch R = 1 ,96570   ,237,251,276
BEGIN DESCRIPTION:
This cross section corresponds to cross section 96570 of the non-georeferenced CDC model which was the source of this model.
Interpolated cross-section.
Project fill pad set at elev. 412.9
END DESCRIPTION:
XS GIS Cut Line= 6
2503860.322035916964739.850787882503800.795252086962866.05958797
2503698.475574856957923.246310892503621.083669256957618.44409896
2502050.502164756955511.377775042497000.907605176949570.62587705
#Sta/Elev= 30
 -7474.3     424 -6905.8   411.7   -4758     410 -2974.4     414   -2767   428.5
    1000  420.99  1133.8  393.88 2051.65   395.7 2096.74  384.48 2186.68  394.28
 2244.11     371 2305.79     371 2380.79     396 2601.26  393.71 2635.49  392.43
 2654.37  391.01 2726.31  392.02 2734.21  393.25 3174.49  384.21 3240.63     383
 3412.43  394.67 3513.22  406.12 6026.58  413.28    6464  405.43    6734  409.14
 6974.31  401.15 7403.55  411.13  9581.8   410.6  9638.3     398 10083.7   421.6
#Mann= 20 ,-1,0
 -7474.3    .105       0    1000    .035       0  1133.8    .105       0
2051.649    .053       0 2380.79    .064       0 2601.26     .06       0
 2635.49    .054       0 2654.37     .06       0 2726.31    .056       0
 2734.21    .075       0 3174.49    .031       0 3240.63    .065       0
3361.101    .058       0 3412.43    .039       0 3513.22    .046       0
3607.899     .05       0 6026.58    .066       0    6464    .045       0
    6734    .066       0 7403.55    .079       0
#XS Ineff= 3 ,-1
 -7474.3 1010.84  420.99 3608.42 7616.01     415 7616.01 10083.7     425
Permanent Ineff=
       F       F       F
#Block Obstruct= 1 ,-1
    6364    6764   412.9
Bank Sta=2186.68,2380.79
XS Rating Curve= 0 ,0
Exp/Cntr=0.3,0.1

Type RM Length L Ch R = 1 ,96333   ,52,55,61
BEGIN DESCRIPTION:
This cross section corresponds to cross section 96333 of the non-georeferenced CDC model which was the source of this model.
Interpolated cross-section.
Project fill pad set at elev. 412.9
END DESCRIPTION:
XS GIS Cut Line= 6
2503927.899656686964577.079459882503778.208026926957972.07889038
2503760.089296766957655.85806613 2502301.93013966955428.83430497
2500702.207289166953404.962040382497385.182099076949152.96923205
#Sta/Elev= 30
 -7474.3     424 -6905.8   411.7   -4758     410 -2974.4     414   -2767   428.5
    1000  420.94 1123.95  393.15 2099.32  395.72 2148.88     371 2244.21     371
 2319.21     396 2541.74  392.29 2576.66  389.57 2623.56  389.55 2676.45  394.71
 3121.49  385.28 3188.34     383 3244.06  383.85 3310.11  383.99    3362  393.28
 3463.88  396.64 3559.58  414.99 5970.98     415    6440  402.57    6710  409.86
 7301.65  400.99 7396.24  411.77  9581.8   410.6  9638.3     398 10083.7   421.6
#Mann= 20 ,-1,0
 -7474.3    .101       0    1000    .035       0 1123.95    .101       0
1974.229    .056       0 2319.21    .094       0 2541.74    .047       0
 2576.66     .03       0 2623.56    .048       0 2676.45    .079       0
 3121.49    .031       0 3188.34    .048       0 3244.06    .059       0
 3310.11    .076       0    3362    .036       0 3463.88    .043       0
 3559.58     .05       05970.979    .061       0    6440    .045       0
    6710    .061       0 7396.24    .088       0
#XS Ineff= 3 ,-1
 -7474.3 1010.16  420.94 3559.66 7610.99     415 7610.99 10083.7     425
Permanent Ineff=
       F       F       F
#Block Obstruct= 1 ,-1
    6440    6814   412.9
Bank Sta=2099.32,2319.21
XS Rating Curve= 0 ,0
Exp/Cntr=0.3,0.1

Type RM Length L Ch R = 1 ,96286   ,550,522,540
BEGIN DESCRIPTION:
Proposed Lamar Levee in LOB.
Wetland Cell D in ROB.
Central Wastewater Treatment Plant in ROB.
END DESCRIPTION:
XS GIS Cut Line= 6
  2502992.342325 6956217.0391761        2502986.        6956209.
        2501846.        6954764.        2500759.        6953358.
 2498952.2896825 6950998.4927837 2498946.0643404 6950990.3626814
#Sta/Elev= 30
    1000  420.93    1122     393    2082     396    2130     371    2232     371
    2307     396    2520   395.5    2530     392    2565     389    2612     389
    2657     392    2665     395    3010     393    3125     383    3300     383
    3352     393    3465     395    3550     415    6000     415    6100     402
    6290     400    6530     402    6580     410    6910     410    6960     402
    7300     400    7375     402    7395     412    7610     412    7610     423
#Mann= 16 ,-1,0
    1000    .035       0    1122      .1       0    2082     .05       0
    2307      .1       0    2520    .035       0    2530    .045       0
    2565    .025       0    2612    .045       0    2657    .035       0
    2665     .08       0    3125     .03       0    3300     .08       0
    3352    .035       0    3550     .05       0    6000     .06       0
    7395     .09       0
Levee=-1,1010,420.96,0,,,,
#XS Ineff= 2 , 0
                            3550             415
Permanent Ineff=
       F       F
Bank Sta=2082,2307
XS Rating Curve= 0 ,0
Exp/Cntr=0.3,0.1

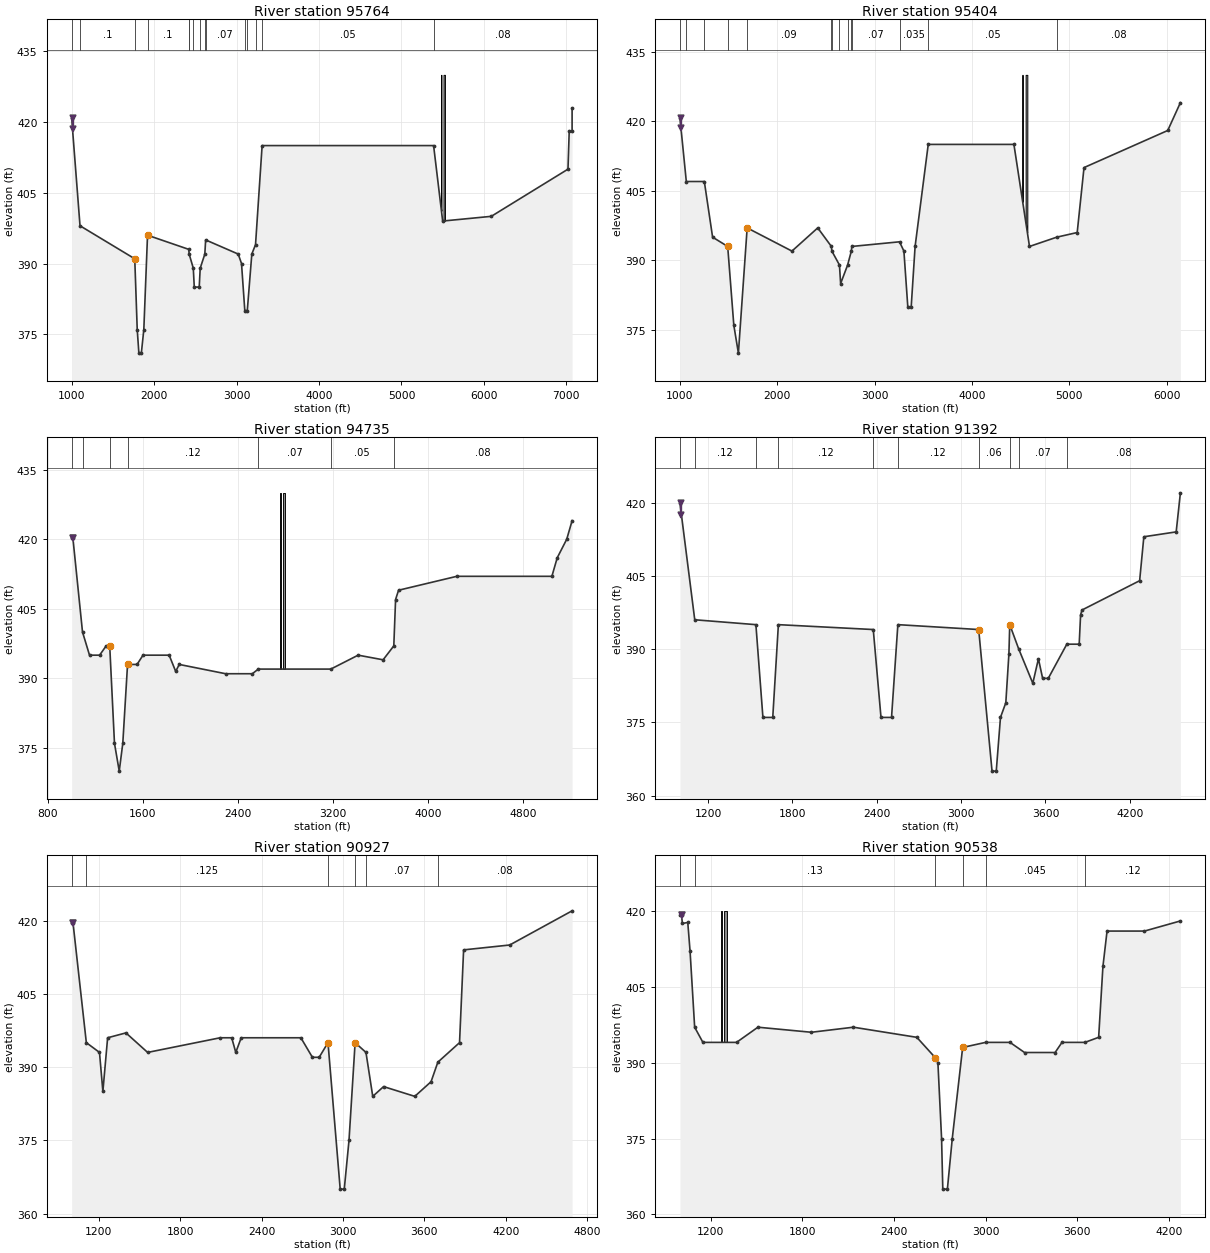
Type RM Length L Ch R = 1 ,95764   ,370,360,550
BEGIN DESCRIPTION:
Proposed Lamar Levee in LOB.
Wetland Cell D in ROB.
Central Wastewater Treatment Plant in ROB.
18' Oncor tower as blocked obstruction Sta 5510 to 5528.
Proposed 3.5' pole.
END DESCRIPTION:
XS GIS Cut Line= 6
  2503188.230113 6955556.5839577 2502683.4443938 6954976.5611002
 2502630.3826657 6954920.0070615 2502577.3209377 6954863.4530227
 2499444.7372956 6950813.0854513 2499429.0896492 6950792.8533597
#Sta/Elev= 30
    1000  420.77    1101     398    1765     391    1795     376    1815     371
    1845     371    1875     376    1920     396    2420     393    2425     392
    2475     389    2487     385    2547     385    2559     389    2615     392
    2625     395    3020     392    3060     390    3100     380    3130     380
    3185     392    3230     394    3310     415    5390     415    5500     399
    6090     400    7020     410    7035     418    7070     418    7070     423
#Mann= 15 ,-1,0
    1000    .035       0    1101      .1       0    1765     .05       0
    1920      .1       0    2420    .035       0    2425    .045       0
    2475    .025       0    2559    .045       0    2615    .035       0
    2625     .07       0    3100     .03       0    3130     .07       0
    3230    .035       0    3310     .05       0    5390     .08       0
Levee=-1,1010,420.8,0,,,,
#XS Ineff= 2 , 0
                            3310             414
Permanent Ineff=
       F       F
#Block Obstruct= 2 ,-1
  5481.5    5485     430    5510    5528     430
Bank Sta=1765,1920
XS Rating Curve= 0 ,0
Exp/Cntr=0.3,0.1

Type RM Length L Ch R = 1 ,95404   ,670,669,670
BEGIN DESCRIPTION:
Proposed Lamar Levee in LOB.
Wetland Cell D in ROB.
Central Wastewater Treatment Plant in ROB.
18' Oncor tower as blocked obstruction Sta 4550 to 4568.
Proposed 3.5' pole.
END DESCRIPTION:
XS GIS Cut Line= 4
  2503323.487309 6955097.9323046        2502829.        6954610.
 2500271.9761472 6950990.5081821 2500264.0669806 6950979.3126808
#Sta/Elev= 30
    1000  420.61    1065     407    1250     407    1335     395    1490     393
    1553     376    1600     370    1690     397    2150     392    2415     397
    2555     393    2560     392    2638     389    2650     385    2722     389
    2760     392    2765     393    3255     394    3300     392    3340     380
    3375     380    3415     393    3550     415    4430     415    4590     393
    4870     395    5080     396    5150     410    6010     418    6140     424
#Mann= 14 ,-1,0
    1000    .035       0    1065     .05       0    1250     .09       0
    1490     .05       0    1690     .09       0    2555    .035       0
    2560    .045       0    2638    .025       0    2722    .045       0
    2760    .035       0    2765     .07       0    3255    .035       0
    3550     .05       0    4870     .08       0
Levee=-1,1010,420.64,0,,,,
#XS Ineff= 2 , 0
                            3550             414
Permanent Ineff=
       F       F
#Block Obstruct= 2 ,-1
  4516.5    4520     430    4550    4568     430
Bank Sta=1490,1690
XS Rating Curve= 0 ,0
Exp/Cntr=0.3,0.1

Type RM Length L Ch R = 1 ,94735   ,400,3343,830
BEGIN DESCRIPTION:
Wetland Cell D in ROB.
Proposed Lamar Levee in LOB.
18' Oncor tower as blocked obstruction Sta 2779 to 2797.
Proposed 4' pole.
END DESCRIPTION:
XS GIS Cut Line= 6
  2503561.356695 6954389.8401697 2503334.3756824 6954160.1432558
 2503269.3027984 6954123.0997074 2503204.2299144  6954086.056159
 2501105.7745592  6951008.833422 2501098.6218408 6950998.3445127
#Sta/Elev= 30
    1000  420.29    1010  420.29    1091     400    1150     395    1235     395
    1290     397    1320     397    1360     376    1400     370    1430     376
    1470     393    1550     393    1600     395    1820     395    1875   391.5
    1905     393    2295     391    2520     391    2570     392    3180     392
    3410     395    3620     394    3710     397    3725     407    3750     409
    4240     412    5040     412    5085     416    5165     420    5210     424
#Mann= 7 ,-1,0
    1000    .035       0    1091      .1       0    1320     .05       0
    1470     .12       0    2570     .07       0    3180     .05       0
    3710     .08       0
Levee=-1,1010,420.32,0,,,,
#XS Ineff= 2 , 0
            1010  420.29
Permanent Ineff=
       F       F
#Block Obstruct= 2 ,-1
    2755    2759     430    2779    2797     430
Bank Sta=1320,1470
XS Rating Curve= 0 ,0
Exp/Cntr=0.3,0.1

Type RM Length L Ch R = 1 ,91392   ,390,465,480
BEGIN DESCRIPTION:
Wetland Cell E in ROB.
Proposed Lamar Levee in LOB.
END DESCRIPTION:
XS GIS Cut Line= 6
  2503802.136936 6954224.9118902 2503235.9765754 6952188.1932182
 2503232.5772706 6952077.7455168 2503229.1779658 6951967.2978155
 2502225.6192376 6951296.2457414  2502210.813738 6951286.3457117
#Sta/Elev= 30
    1000  419.83    1105     396    1540     395    1590     376    1660     376
    1700     395    2375     394    2430     376    2505     376    2550     395
    3125     394    3220     365    3250     365    3280     376    3318     379
    3340     389    3346     395    3410     390    3510     383    3550     388
    3580     384    3620     384    3752     391    3840     391    3850     397
    3860     398    4270     404    4300     413    4530     414    4560     422
#Mann= 10 ,-1,0
    1000    .035       0    1105     .12       0    1540     .06       0
    1700     .12       0    2375     .06       0    2550     .12       0
    3125     .06       0    3346     .08       0    3410     .07       0
    3752     .08       0
Levee=-1,1010,419.86,0,,,,
#XS Ineff= 2 , 0
            1010  419.83
Permanent Ineff=
       F       F
Bank Sta=3125,3346
XS Rating Curve= 0 ,0
Exp/Cntr=0.3,0.1

Type RM Length L Ch R = 1 ,90927   ,300,389,410
BEGIN DESCRIPTION:
Wetland Cell E in ROB.
Proposed Lamar Levee in LOB.
END DESCRIPTION:
XS GIS Cut Line= 5
  2504046.925964  6954061.768781 2503669.4706599 6952209.8434334
 2503689.9671756 6952111.9665064 2503710.4636914 6952014.0895794
 2503481.2898247 6950430.5873411
#Sta/Elev= 30
    1000  419.48    1010  419.48    1108     395    1205     393    1230     385
    1265     396    1400     397    1560     393    2095     396    2180     396
    2210     393    2250     396    2690     396    2775     392    2825     392
    2890     395    2980     365    3010     365    3045     375    3090     395
    3170     393    3220     384    3300     386    3530     384    3650     387
    3700     391    3860     395    3890     414    4230     415    4690     422
#Mann= 6 ,-1,0
    1000    .035       0    1108    .125       0    2890     .06       0
    3090     .08       0    3170     .07       0    3700     .08       0
Levee=-1,1010,419.51,0,,,,
#XS Ineff= 2 , 0
            1010  419.48
Permanent Ineff=
       F       F
Bank Sta=2890,3090
XS Rating Curve= 0 ,0
Exp/Cntr=0.3,0.1

Type RM Length L Ch R = 1 ,90538   ,80,80,80
BEGIN DESCRIPTION:
Upstream bounding cross-section for SH 310 bridge.
Proposed Lamar Levee in LOB.
18' Oncor tower as blocked obstruction Sta 1287 to 1305.
Proposed 4' pole.
END DESCRIPTION:
XS GIS Cut Line= 4
  2504105.275792 6953970.4471996 2504105.2496934 6953969.1135997
  2504041.220939 6950697.4077859 2504041.1948399 6950696.0741861
#Sta/Elev= 30
    1000  419.08    1010  419.08    1016   417.5    1051   417.7    1066     412
    1096     397    1150     394    1370     394    1510     397    1860     396
    2135     397    2550     395    2670     391    2688     390    2712     375
    2720     365    2750     365    2782     375    2850     393    3000     394
    3160     394    3255     392    3455     392    3500     394    3650     394
    3740     395    3768     409    3795     416    4040     416    4275     418
#Mann= 6 ,-1,0
    1000    .035       0    1096     .13       0    2670     .06       0
    2850     .18       0    3000    .045       0    3650     .12       0
Levee=-1,1010,419.11,0,,,,
#XS Ineff= 2 , 0
            1010  419.08
Permanent Ineff=
       F       F
#Block Obstruct= 2 ,-1
    1268    1272     420    1287    1305     420
Bank Sta=2670,2850
XS Rating Curve= 0 ,0
Exp/Cntr=0.5,0.3

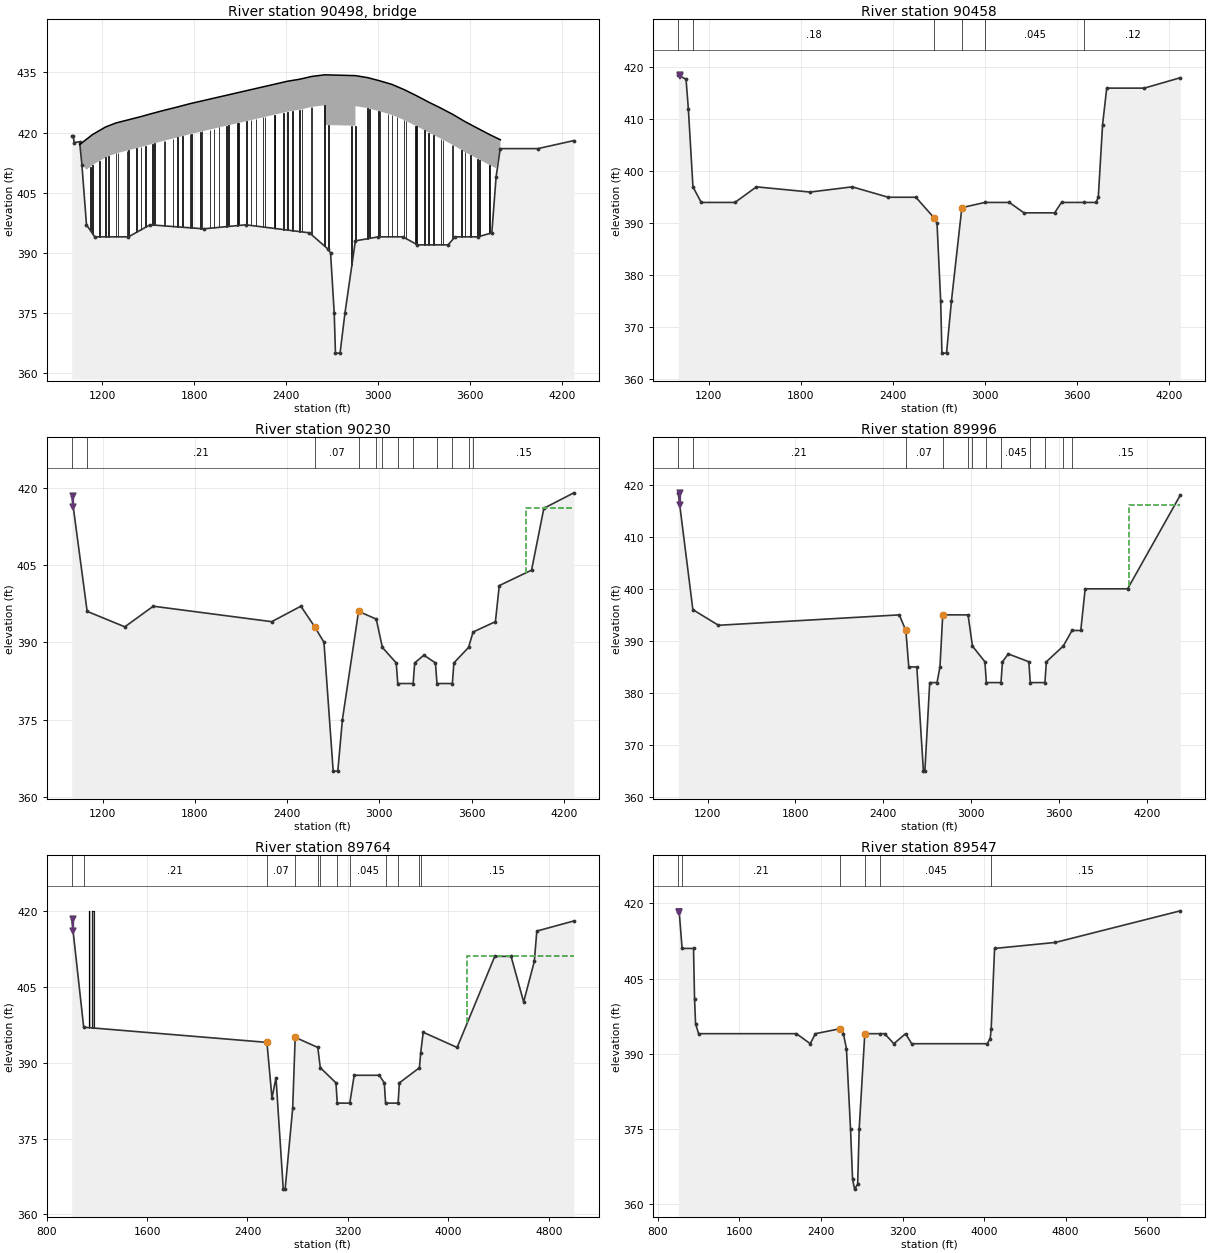
Type RM Length L Ch R = 3 ,90498   ,,,
BEGIN DESCRIPTION:
SH 310
END DESCRIPTION:
Node Name=SH 310
Bridge Culvert--1,0,-1,-1, 0
Deck Dist Width WeirC Skew NumUp NumDn MinLoCord MaxHiCord MaxSubmerge Is_Ogee
1,78,2.6,0, 36, 36, , , 0.95, 0, ,,,
    1051  1135.3  1220.6  1288.7  1370.7  1452.7  1527.3  1606.9  1690.6  1770.2
  1849.8  1929.3  2008.9  2088.4  2167.9  2247.5    2327  2406.6  2486.1  2565.7
  2649.4  2649.4  2850.5  2850.5  2930.1  3009.6  3089.2  3168.7  3248.3  3327.8
  3407.4  3486.9  3566.5    3646  3725.6  3796.1
     417   419.5   421.4   422.4   423.2     424   424.8   425.6   426.4   427.2
   427.9   428.6   429.3     430   430.7   431.4   432.1   432.8   433.3     434
   434.4   434.4   434.2   434.2   433.7   432.9     432   430.7   429.2   427.6
   426.1   424.5   422.7   421.1   419.5   418.2
   409.4   411.9   413.8   414.8   415.6   416.4   417.2     418   418.8   419.6
   420.3     421   421.7   422.4   423.1   423.8   424.5   425.2   425.7   426.4
   426.8   421.9   421.7   426.6   426.1   425.3   424.4   423.1   421.6     420
   418.5   416.9   415.1   413.5   411.9   410.6
    1051  1135.3  1220.6  1288.7  1370.7  1452.7  1527.3  1606.9  1690.6  1770.2
  1849.8  1929.3  2008.9  2088.4  2167.9  2247.5    2327  2406.6  2486.1  2565.7
  2649.4  2649.4  2850.5  2850.5  2930.1  3009.6  3089.2  3168.7  3248.3  3327.8
  3407.4  3486.9  3566.5    3646  3725.6  3796.1
     417   419.5   421.4   422.4   423.2     424   424.8   425.6   426.4   427.2
   427.9   428.6   429.3     430   430.7   431.4   432.1   432.8   433.3     434
   434.4   434.4   434.2   434.2   433.7   432.9     432   430.7   429.2   427.6
   426.1   424.5   422.7   421.1   419.5   418.2
   409.4   411.9   413.8   414.8   415.6   416.4   417.2     418   418.8   419.6
   420.3     421   421.7   422.4   423.1   423.8   424.5   425.2   425.7   426.4
   426.8   421.9   421.7   426.6   426.1   425.3   424.4   423.1   421.6     420
   418.5   416.9   415.1   413.5   411.9   410.6
Pier Skew, UpSta & Num, DnSta & Num=  ,1121, 2 ,1121, 2 , 0 , 0 , 0 ,,
       3       2
   384.3   414.3
       3       2
   384.3   414.3
Pier Skew, UpSta & Num, DnSta & Num=  ,1135.3, 2 ,1135.3, 2 , 0 , 0 , 0 ,,
     2.5     2.5
       0     419
     2.5     2.5
       0     419
Pier Skew, UpSta & Num, DnSta & Num=  ,1181, 2 ,1181, 2 , 0 , 0 , 0 ,,
       3       2
   384.8   414.8
       3       2
   384.8   414.8
Pier Skew, UpSta & Num, DnSta & Num=  ,1220.6, 2 ,1220.6, 2 , 0 , 0 , 0 ,,
     2.5     2.5
       0     419
     2.5     2.5
       0     419
Pier Skew, UpSta & Num, DnSta & Num=  ,1241, 2 ,1241, 2 , 0 , 0 , 0 ,,
       3       2
   385.4   415.4
       3       2
   385.4   415.4
Pier Skew, UpSta & Num, DnSta & Num=  ,1288.7, 2 ,1288.7, 2 , 0 , 0 , 0 ,,
     2.5     2.5
       0     419
     2.5     2.5
       0     419
Pier Skew, UpSta & Num, DnSta & Num=  ,1301, 2 ,1301, 2 , 0 , 0 , 0 ,,
       3       2
   385.9   415.9
       3       2
   385.9   415.9
Pier Skew, UpSta & Num, DnSta & Num=  ,1361, 2 ,1361, 2 , 0 , 0 , 0 ,,
       3       2
     386     416
       3       2
     386     416
Pier Skew, UpSta & Num, DnSta & Num=  ,1370.7, 2 ,1370.7, 2 , 0 , 0 , 0 ,,
     2.5     2.5
       0     419
     2.5     2.5
       0     419
Pier Skew, UpSta & Num, DnSta & Num=  ,1421, 2 ,1421, 2 , 0 , 0 , 0 ,,
       3       2
   386.9   416.9
       3       2
   386.9   416.9
Pier Skew, UpSta & Num, DnSta & Num=  ,1452.7, 2 ,1452.7, 2 , 0 , 0 , 0 ,,
     2.5     2.5
       0     419
     2.5     2.5
       0     419
Pier Skew, UpSta & Num, DnSta & Num=  ,1481, 2 ,1481, 2 , 0 , 0 , 0 ,,
       3       2
   387.5   417.5
       3       2
   387.5   417.5
Pier Skew, UpSta & Num, DnSta & Num=  ,1527.3, 2 ,1527.3, 2 , 0 , 0 , 0 ,,
     2.5     2.5
       0     419
     2.5     2.5
       0     419
Pier Skew, UpSta & Num, DnSta & Num=  ,1541, 2 ,1541, 2 , 0 , 0 , 0 ,,
       3       2
     388     418
       3       2
     388     418
Pier Skew, UpSta & Num, DnSta & Num=  ,1601, 2 ,1601, 2 , 0 , 0 , 0 ,,
       3       2
   388.5   418.5
       3       2
   388.5   418.5
Pier Skew, UpSta & Num, DnSta & Num=  ,1606.9, 2 ,1606.9, 2 , 0 , 0 , 0 ,,
     2.5     2.5
       0     419
     2.5     2.5
       0     419
Pier Skew, UpSta & Num, DnSta & Num=  ,1661, 2 ,1661, 2 , 0 , 0 , 0 ,,
       3       2
   388.6   418.6
       3       2
   388.6   418.6
Pier Skew, UpSta & Num, DnSta & Num=  ,1690.6, 2 ,1690.6, 2 , 0 , 0 , 0 ,,
     2.5     2.5
       0     426
     2.5     2.5
       0     426
Pier Skew, UpSta & Num, DnSta & Num=  ,1721, 2 ,1721, 2 , 0 , 0 , 0 ,,
       3       2
   389.5   419.5
       3       2
   389.5   419.5
Pier Skew, UpSta & Num, DnSta & Num=  ,1770.2, 2 ,1770.2, 2 , 0 , 0 , 0 ,,
     2.5     2.5
       0     426
     2.5     2.5
       0     426
Pier Skew, UpSta & Num, DnSta & Num=  ,1781, 2 ,1781, 2 , 0 , 0 , 0 ,,
       3       2
   390.1   420.1
       3       2
   390.1   420.1
Pier Skew, UpSta & Num, DnSta & Num=  ,1841, 2 ,1841, 2 , 0 , 0 , 0 ,,
       3       2
   390.6   420.6
       3       2
   390.6   420.6
Pier Skew, UpSta & Num, DnSta & Num=  ,1849.8, 2 ,1849.8, 2 , 0 , 0 , 0 ,,
     2.5     2.5
       0     426
     2.5     2.5
       0     426
Pier Skew, UpSta & Num, DnSta & Num=  ,1901, 2 ,1901, 2 , 0 , 0 , 0 ,,
       3       2
   391.1   421.1
       3       2
   391.1   421.1
Pier Skew, UpSta & Num, DnSta & Num=  ,1929.3, 2 ,1929.3, 2 , 0 , 0 , 0 ,,
     2.5     2.5
       0     426
     2.5     2.5
       0     426
Pier Skew, UpSta & Num, DnSta & Num=  ,1961, 2 ,1961, 2 , 0 , 0 , 0 ,,
       3       2
   391.2   421.4
       3       2
   391.2   421.4
Pier Skew, UpSta & Num, DnSta & Num=  ,2008.9, 2 ,2008.9, 2 , 0 , 0 , 0 ,,
     2.5     2.5
       0     426
     2.5     2.5
       0     426
Pier Skew, UpSta & Num, DnSta & Num=  ,2021, 2 ,2021, 2 , 0 , 0 , 0 ,,
       3       2
     392   422.1
       3       2
     392   422.1
Pier Skew, UpSta & Num, DnSta & Num=  ,2081, 2 ,2081, 2 , 0 , 0 , 0 ,,
       3       2
     392   422.7
       3       2
     392   422.7
Pier Skew, UpSta & Num, DnSta & Num=  ,2088.4, 2 ,2088.4, 2 , 0 , 0 , 0 ,,
     2.5     2.5
       0     426
     2.5     2.5
       0     426
Pier Skew, UpSta & Num, DnSta & Num=  ,2141, 2 ,2141, 2 , 0 , 0 , 0 ,,
       3       2
     392   423.2
       3       2
     392   423.2
Pier Skew, UpSta & Num, DnSta & Num=  ,2167.9, 2 ,2167.9, 2 , 0 , 0 , 0 ,,
     2.5     2.5
       0     426
     2.5     2.5
       0     426
Pier Skew, UpSta & Num, DnSta & Num=  ,2201, 2 ,2201, 2 , 0 , 0 , 0 ,,
       3       2
     392   423.7
       3       2
     392   423.7
Pier Skew, UpSta & Num, DnSta & Num=  ,2247.5, 2 ,2247.5, 2 , 0 , 0 , 0 ,,
     2.5     2.5
       0     426
     2.5     2.5
       0     426
Pier Skew, UpSta & Num, DnSta & Num=  ,2261, 2 ,2261, 2 , 0 , 0 , 0 ,,
       3       2
     392     424
       3       2
     392     424
Pier Skew, UpSta & Num, DnSta & Num=  ,2321, 2 ,2321, 2 , 0 , 0 , 0 ,,
       3       2
     392   424.7
       3       2
     392   424.7
Pier Skew, UpSta & Num, DnSta & Num=  ,2327, 2 ,2327, 2 , 0 , 0 , 0 ,,
     2.5     2.5
       0     426
     2.5     2.5
       0     426
Pier Skew, UpSta & Num, DnSta & Num=  ,2381, 2 ,2381, 2 , 0 , 0 , 0 ,,
       3       2
     392   425.3
       3       2
     392   425.3
Pier Skew, UpSta & Num, DnSta & Num=  ,2406.6, 2 ,2406.6, 2 , 0 , 0 , 0 ,,
     2.5     2.5
       0     426
     2.5     2.5
       0     426
Pier Skew, UpSta & Num, DnSta & Num=  ,2441, 2 ,2441, 2 , 0 , 0 , 0 ,,
       3       2
     392   425.8
       3       2
     392   425.8
Pier Skew, UpSta & Num, DnSta & Num=  ,2486.1, 2 ,2486.1, 2 , 0 , 0 , 0 ,,
     2.5     2.5
       0     426
     2.5     2.5
       0     426
Pier Skew, UpSta & Num, DnSta & Num=  ,2501, 2 ,2501, 2 , 0 , 0 , 0 ,,
       3       2
     392   426.3
       3       2
     392   426.3
Pier Skew, UpSta & Num, DnSta & Num=  ,2561, 2 ,2561, 2 , 0 , 0 , 0 ,,
       3       2
     392   426.5
       3       2
     392   426.5
Pier Skew, UpSta & Num, DnSta & Num=  ,2565.7, 2 ,2565.7, 2 , 0 , 0 , 0 ,,
     2.5     2.5
       0     434
     2.5     2.5
       0     434
Pier Skew, UpSta & Num, DnSta & Num=  ,2649.4, 2 ,2649.4, 2 , 0 , 0 , 0 ,,
       3       3
       0     434
       3       3
       0     434
Pier Skew, UpSta & Num, DnSta & Num=  ,2675, 2 ,2675, 2 , 0 , 0 , 0 ,,
       5     2.5
     368     422
       5     2.5
     368     422
Pier Skew, UpSta & Num, DnSta & Num=  ,2827, 2 ,2827, 2 , 0 , 0 , 0 ,,
       5     2.5
     368     422
       5     2.5
     368     422
Pier Skew, UpSta & Num, DnSta & Num=  ,2850.5, 2 ,2850.5, 2 , 0 , 0 , 0 ,,
       3       3
       0     434
       3       3
       0     434
Pier Skew, UpSta & Num, DnSta & Num=  ,2930.1, 2 ,2930.1, 2 , 0 , 0 , 0 ,,
     2.5     2.5
       0     427
     2.5     2.5
       0     427
Pier Skew, UpSta & Num, DnSta & Num=  ,2941, 2 ,2941, 2 , 0 , 0 , 0 ,,
       3       2
     392   426.3
       3       2
     392   426.3
Pier Skew, UpSta & Num, DnSta & Num=  ,3001, 2 ,3001, 2 , 0 , 0 , 0 ,,
       3       2
     392   426.2
       3       2
     392   426.2
Pier Skew, UpSta & Num, DnSta & Num=  ,3009.6, 2 ,3009.6, 2 , 0 , 0 , 0 ,,
     2.5     2.5
       0     427
     2.5     2.5
       0     427
Pier Skew, UpSta & Num, DnSta & Num=  ,3061, 2 ,3061, 2 , 0 , 0 , 0 ,,
       3       2
     392   425.5
       3       2
     392   425.5
Pier Skew, UpSta & Num, DnSta & Num=  ,3089.2, 2 ,3089.2, 2 , 0 , 0 , 0 ,,
     2.5     2.5
       0     427
     2.5     2.5
       0     427
Pier Skew, UpSta & Num, DnSta & Num=  ,3121, 2 ,3121, 2 , 0 , 0 , 0 ,,
       3       2
     392   424.5
       3       2
     392   424.5
Pier Skew, UpSta & Num, DnSta & Num=  ,3168.7, 2 ,3168.7, 2 , 0 , 0 , 0 ,,
     2.5     2.5
       0     427
     2.5     2.5
       0     427
Pier Skew, UpSta & Num, DnSta & Num=  ,3181, 2 ,3181, 2 , 0 , 0 , 0 ,,
       3       2
     392   423.4
       3       2
     392   423.4
Pier Skew, UpSta & Num, DnSta & Num=  ,3241, 2 ,3241, 2 , 0 , 0 , 0 ,,
       3       2
     392   421.8
       3       2
     392   421.8
Pier Skew, UpSta & Num, DnSta & Num=  ,3248.3, 2 ,3248.3, 2 , 0 , 0 , 0 ,,
     2.5     2.5
       0     427
     2.5     2.5
       0     427
Pier Skew, UpSta & Num, DnSta & Num=  ,3301, 2 ,3301, 2 , 0 , 0 , 0 ,,
       3       2
     391     421
       3       2
     391     421
Pier Skew, UpSta & Num, DnSta & Num=  ,3327.8, 2 ,3327.8, 2 , 0 , 0 , 0 ,,
     2.5     2.5
       0     420
     2.5     2.5
       0     420
Pier Skew, UpSta & Num, DnSta & Num=  ,3361, 2 ,3361, 2 , 0 , 0 , 0 ,,
       3       2
   389.8   419.8
       3       2
   389.8   419.8
Pier Skew, UpSta & Num, DnSta & Num=  ,3407.4, 2 ,3407.4, 2 , 0 , 0 , 0 ,,
     2.5     2.5
       0     420
     2.5     2.5
       0     420
Pier Skew, UpSta & Num, DnSta & Num=  ,3421, 2 ,3421, 2 , 0 , 0 , 0 ,,
       3       2
   388.6   418.6
       3       2
   388.6   418.6
Pier Skew, UpSta & Num, DnSta & Num=  ,3481, 2 ,3481, 2 , 0 , 0 , 0 ,,
       3       2
   387.4   417.4
       3       2
   387.4   417.4
Pier Skew, UpSta & Num, DnSta & Num=  ,3486.9, 2 ,3486.9, 2 , 0 , 0 , 0 ,,
     2.5     2.5
       0     420
     2.5     2.5
       0     420
Pier Skew, UpSta & Num, DnSta & Num=  ,3541, 2 ,3541, 2 , 0 , 0 , 0 ,,
       3       2
   385.8   415.8
       3       2
   385.8   415.8
Pier Skew, UpSta & Num, DnSta & Num=  ,3566.5, 2 ,3566.5, 2 , 0 , 0 , 0 ,,
     2.5     2.5
       0     420
     2.5     2.5
       0     420
Pier Skew, UpSta & Num, DnSta & Num=  ,3601, 2 ,3601, 2 , 0 , 0 , 0 ,,
       3       2
     385     415
       3       2
     385     415
Pier Skew, UpSta & Num, DnSta & Num=  ,3646, 2 ,3646, 2 , 0 , 0 , 0 ,,
     2.5     2.5
       0     420
     2.5     2.5
       0     420
Pier Skew, UpSta & Num, DnSta & Num=  ,3661, 2 ,3661, 2 , 0 , 0 , 0 ,,
       3       2
   383.8   413.8
       3       2
   383.8   413.8
Pier Skew, UpSta & Num, DnSta & Num=  ,3721, 2 ,3721, 2 , 0 , 0 , 0 ,,
       3       2
   382.6   412.6
       3       2
   382.6   412.6
Pier Skew, UpSta & Num, DnSta & Num=  ,3725.6, 2 ,3725.6, 2 , 0 , 0 , 0 ,,
     2.5     2.5
       0     412
     2.5     2.5
       0     412
BR Coef= 1 , 0 , 0 ,1.05, 0 ,,,0.8,-1,0.5,1,
WSPro=,,,, 1 ,,,, 0 ,,,, 0 ,,,,-1 ,-1 ,-1 , 0 , 0 , 0 , 0 , 0
BC Design=,, 0 ,, 0 ,,,,,,
BC HTab HWMax=422
BC Use User HTab Curves=0
BC User HTab FreeFlow(D)= 0

Type RM Length L Ch R = 1 ,90458   ,190,228,250
BEGIN DESCRIPTION:
Downstream bounding cross-section for SH 310 bridge.
Proposed Lamar Levee in LOB.
END DESCRIPTION:
XS GIS Cut Line= 4
  2504186.072665 6953971.3458783 2504185.9711026 6953966.0991072
 2504122.7913913 6950702.2060478 2504122.6898287 6950696.9592768
#Sta/Elev= 30
    1000  418.52    1051   417.7    1066     412    1096     397    1150     394
    1370     394    1510     397    1860     396    2135     397    2370     395
    2550     395    2670     391    2688     390    2712     375    2720     365
    2750     365    2782     375    2850     393    3000     394    3160     394
    3255     392    3455     392    3500     394    3650     394    3725     394
    3740     395    3768     409    3795     416    4040     416    4275     418
#Mann= 6 ,-1,0
    1000    .035       0    1096     .18       0    2670     .07       0
    2850     .18       0    3000    .045       0    3650     .12       0
Levee=-1,1010,418.56,0,,,,
#XS Ineff= 2 , 0
            1010  418.52
Permanent Ineff=
       F       F
Bank Sta=2670,2850
XS Rating Curve= 0 ,0
Exp/Cntr=0.5,0.3

Type RM Length L Ch R = 1 ,90230   ,190,234,260
BEGIN DESCRIPTION:
Wetland Cell E in ROB.
Proposed Lamar Levee in LOB.
END DESCRIPTION:
XS GIS Cut Line= 2
        2504340.        6953985. 2504426.3851684 6950721.1429868
#Sta/Elev= 30
    1000  418.43    1100     396    1345     393    1530     397    2300     394
    2490     397    2580     393    2640     390    2700     365    2730     365
    2760     375    2865     396    2980   394.5    3020     389    3110     386
    3120     382    3220     382    3230     386    3290   387.5    3365     386
    3375     382    3475     382    3485     386    3580     389    3610     392
    3755     394    3780     401    3990     404    4070     416    4265     419
#Mann= 12 ,-1,0
    1000    .035       0    1100     .21       0    2580     .07       0
    2865     .21       0    2980    .035       0    3020    .045       0
    3120    .025       0    3220    .045       0    3375    .025       0
    3475    .045       0    3580    .035       0    3610     .15       0
Levee=-1,1010,418.46,0,,,,
#XS Ineff= 2 , 0
                            3955             416
Permanent Ineff=
       F       F
Bank Sta=2580,2865
XS Rating Curve= 0 ,0
Exp/Cntr=0.3,0.1

Type RM Length L Ch R = 1 ,89996   ,200,232,280
BEGIN DESCRIPTION:
Wetland Cell E in ROB.
Proposed Lamar Levee in LOB.
END DESCRIPTION:
XS GIS Cut Line= 2
  2504468.472066 6954004.8082343 2504731.3283484 6950584.8949934
#Sta/Elev= 30
    1000   418.4    1100     396    1275     393    2510     395    2555     392
    2575     385    2630     385    2675     365    2685     365    2718     382
    2768     382    2788     385    2807     395    2980     395    3010     389
    3095     386    3105     382    3205     382    3215     386    3255   387.5
    3395     386    3405     382    3505     382    3515     386    3630     389
    3690     392    3750     392    3780     400    4070     400    4430     418
#Mann= 12 ,-1,0
    1000    .035       0    1100     .21       0    2555     .07       0
    2807     .21       0    2980    .035       0    3010    .045       0
    3105    .025       0    3205    .045       0    3405    .025       0
    3505    .045       0    3630    .035       0    3690     .15       0
Levee=-1,1010,418.43,0,,,,
#XS Ineff= 2 , 0
                            4080             416
Permanent Ineff=
       F       F
Bank Sta=2555,2807
XS Rating Curve= 0 ,0
Exp/Cntr=0.5,0.3

Type RM Length L Ch R = 1 ,89764   ,190,217,250
BEGIN DESCRIPTION:
Wetland Cell E in ROB.
Proposed Lamar Levee in LOB.
Rochester Park Levee in LOB.
18' Oncor tower as blocked obstruction Sta 1160 to 1178.
Proposed 4' pole.
END DESCRIPTION:
XS GIS Cut Line= 2
  2504623.679954 6954021.4838982 2505141.3037868 6950055.1171013
#Sta/Elev= 30
    1000  418.35    1095     397    2555     394    2595     383    2627     387
    2685     365    2700     365    2760     381    2780     395    2960     393
    2980     389    3105     386    3115     382    3215     382    3250   387.5
    3450   387.5    3490     386    3500     382    3600     382    3610     386
    3770     389    3780     392    3800     396    4070     393    4370     411
    4500     411    4600     402    4685     410    4705     416    5000     418
#Mann= 12 ,-1,0
    1000    .035       0    1095     .21       0    2555     .07       0
    2780     .21       0    2960    .035       0    2980    .045       0
    3115    .025       0    3215    .045       0    3500    .025       0
    3600    .045       0    3770    .035       0    3780     .15       0
Levee=-1,1010,418.39,0,,,,
#XS Ineff= 2 , 0
                            4150             411
Permanent Ineff=
       F       F
#Block Obstruct= 2 ,-1
    1136    1140     420    1160    1178     420
Bank Sta=2555,2780
XS Rating Curve= 0 ,0
Exp/Cntr=0.3,0.1

Type RM Length L Ch R = 1 ,89547   ,20,20,20
BEGIN DESCRIPTION:
Upstream bounding cross-section for Union Pacific Railroad bridge.
Rochester Park Levee in LOB.
END DESCRIPTION:
XS GIS Cut Line= 3
  2504769.671917 6954081.3284008 2505541.7329722 6949571.7267463
 2505599.8509573 6949226.8030204
#Sta/Elev= 30
    1000  418.17    1010  418.17    1038     411    1150     411    1160     401
    1170     396    1200     394    2160     394    2295     392    2345     394
    2590     395    2620     394    2650     391    2690     375    2710     365
    2730     363    2760     364    2775     375    2830     394    2980     394
    3025     394    3115     392    3230     394    3290     392    4030     392
    4060     393    4070     395    4103     411    4700   412.2    5925   418.5
#Mann= 6 ,-1,0
    1000    .035       0    1038     .21       0    2590     .07       0
    2830     .21       0    2980    .045       0    4070     .15       0
Levee=-1,1010,418.2,0,,,,
#XS Ineff= 2 , 0
            1010   417.9
Permanent Ineff=
       F       F
Bank Sta=2590,2830
XS Rating Curve= 0 ,0
Exp/Cntr=0.5,0.3