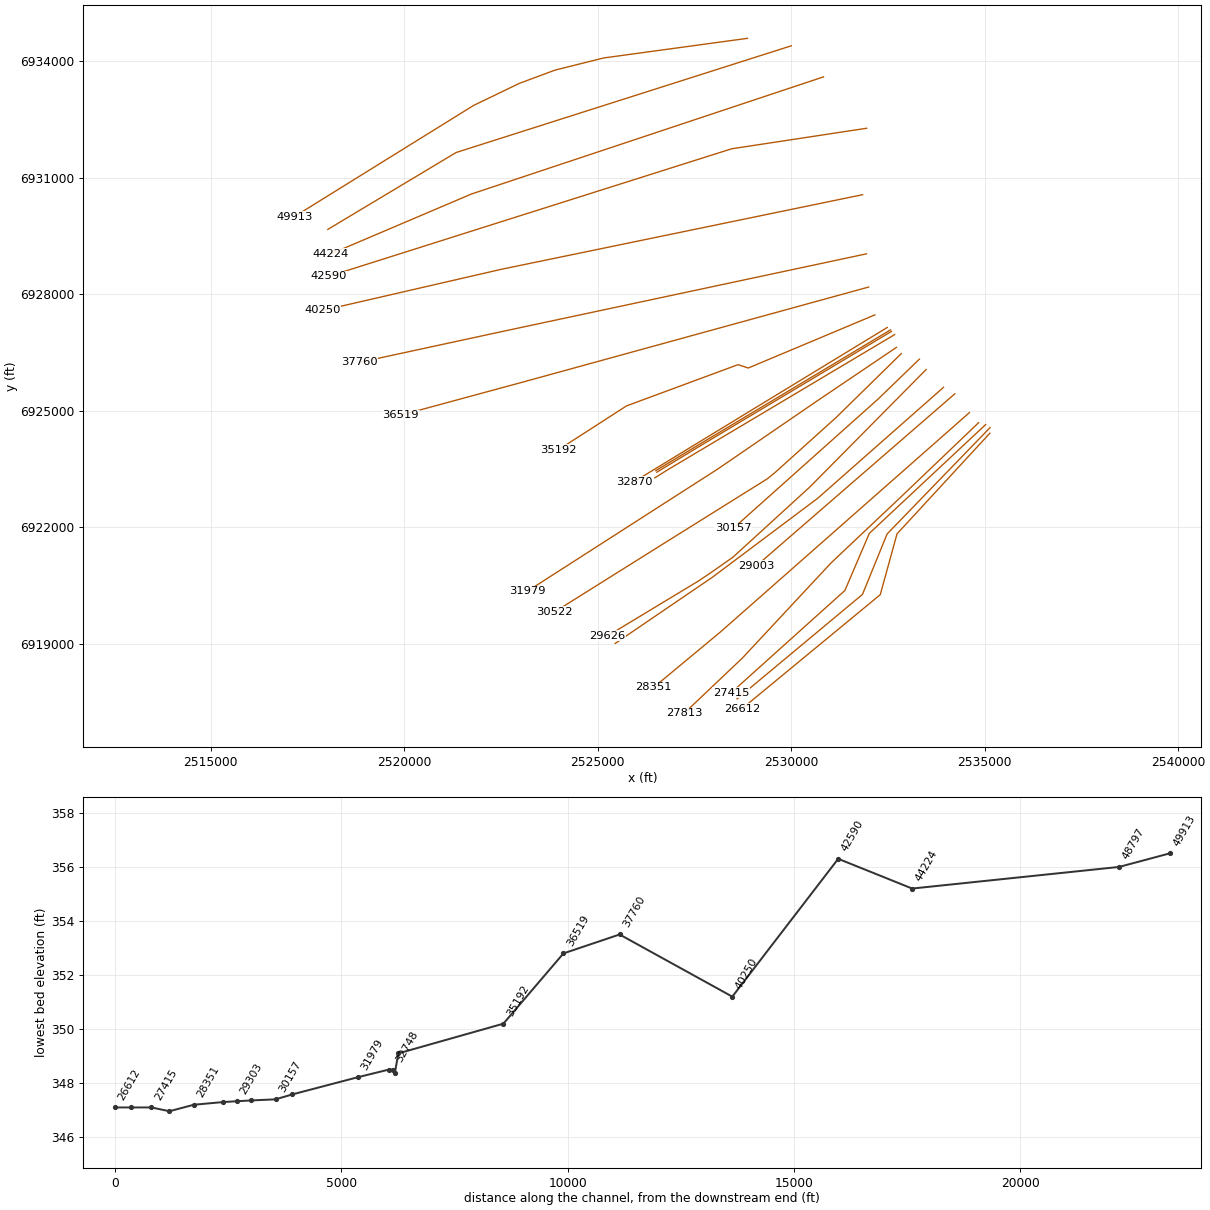
HEC-RAS study CDC_Consolidated_Model.prj: Upper Trinity CDC Consolidated Model

--- CDC_Consolidated_Model.g12 (geometry) --- (continued)

Type RM Length L Ch R = 3 ,50003   ,,,
BEGIN DESCRIPTION:
IH 20
Data from bridge plans.  Bridge length 2400 feet. Perched bridge - minimum low chord elev. 406.6.  Bridge width set at 178 feet.
END DESCRIPTION:
Node Name=IH 20
Bridge Culvert--1,0,-1,-1, 0
Deck Dist Width WeirC Skew NumUp NumDn MinLoCord MaxHiCord MaxSubmerge Is_Ogee
1,178,2.6,0, 26, 26, , , 0.95, 0, ,,,
    1000    1060    1410    1650    2130    2590    2820    2990    3060    3070
    3183    3333    3483    3633    3783    3893    4113    4423    4643    4758
    4908    5058    5208    5358    5470    5480
     410     408     407     406     405     406     408     410   411.6   411.6
   414.5     418   422.5   427.5   431.5     434     437     437     433     431
   427.5     423     419     415     412     412
     410     408     407     406     405     406     408     410   411.6   406.6
   409.5     413   417.5   422.5   426.5     429     426     426     423     426
   422.5     418     414     410     407     412
    1000    1060    1410    1650    2130    2590    2820    2990    3060    3070
    3183    3333    3483    3633    3783    3893    4113    4423    4643    4758
    4908    5058    5208    5358    5470    5480
     410     408     407     406     405     406     408     410   411.6   411.6
   414.5     418   422.5   427.5   431.5     434     437     437     433     431
   427.5     423     419     415     412     412
     410     408     407     406     405     406     408     410   411.6   406.6
   409.5     413   417.5   422.5   426.5     429     426     426     423     426
   422.5     418     414     410     407     412
Pier Skew, UpSta & Num, DnSta & Num=  ,3186, 2 ,3186, 2 , 0 , 0 , 0 ,,
       6       6
       0     410
       6       6
       0     410
Pier Skew, UpSta & Num, DnSta & Num=  ,3336, 2 ,3336, 2 , 0 , 0 , 0 ,,
       6       6
       0   413.5
       6       6
       0   413.5
Pier Skew, UpSta & Num, DnSta & Num=  ,3486, 2 ,3486, 2 , 0 , 0 , 0 ,,
       6       6
       0     418
       6       6
       0     418
Pier Skew, UpSta & Num, DnSta & Num=  ,3636, 2 ,3636, 2 , 0 , 0 , 0 ,,
       6       6
       0     423
       6       6
       0     423
Pier Skew, UpSta & Num, DnSta & Num=  ,3786, 2 ,3786, 2 , 0 , 0 , 0 ,,
       6       6
       0     427
       6       6
       0     427
Pier Skew, UpSta & Num, DnSta & Num=  ,3895, 2 ,3895, 2 , 0 , 0 , 0 ,,
       4       4
       0   429.5
       4       4
       0   429.5
Pier Skew, UpSta & Num, DnSta & Num=  ,4115, 2 ,4115, 2 , 0 , 0 , 0 ,,
       4       4
       0   426.5
       4       4
       0   426.5
Pier Skew, UpSta & Num, DnSta & Num=  ,4425, 2 ,4425, 2 , 0 , 0 , 0 ,,
       4       4
       0   426.5
       4       4
       0   426.5
Pier Skew, UpSta & Num, DnSta & Num=  ,4645, 2 ,4645, 2 , 0 , 0 , 0 ,,
       4       4
       0   423.5
       4       4
       0   423.5
Pier Skew, UpSta & Num, DnSta & Num=  ,4761, 2 ,4761, 2 , 0 , 0 , 0 ,,
       6       6
       0   426.5
       6       6
       0   426.5
Pier Skew, UpSta & Num, DnSta & Num=  ,4911, 2 ,4911, 2 , 0 , 0 , 0 ,,
       6       6
       0     423
       6       6
       0     423
Pier Skew, UpSta & Num, DnSta & Num=  ,5061, 2 ,5061, 2 , 0 , 0 , 0 ,,
       6       6
       0   418.5
       6       6
       0   418.5
Pier Skew, UpSta & Num, DnSta & Num=  ,5211, 2 ,5211, 2 , 0 , 0 , 0 ,,
       6       6
       0   414.5
       6       6
       0   414.5
Pier Skew, UpSta & Num, DnSta & Num=  ,5361, 2 ,5361, 2 , 0 , 0 , 0 ,,
       6       6
       0   410.5
       6       6
       0   410.5
BR Coef= 1 , 0 , 0 ,1.05, 0 ,,,0.8,-1,0.5,1,
WSPro=,,,, 1 ,,,, 0 ,,,, 0 ,,,,-1 ,-1 ,-1 , 0 , 0 , 0 , 0 , 0
BC Design=,, 0 ,, 0 ,,,,,,
BC HTab HWMax=412
BC Use User HTab Curves=0
BC User HTab FreeFlow(D)= 0

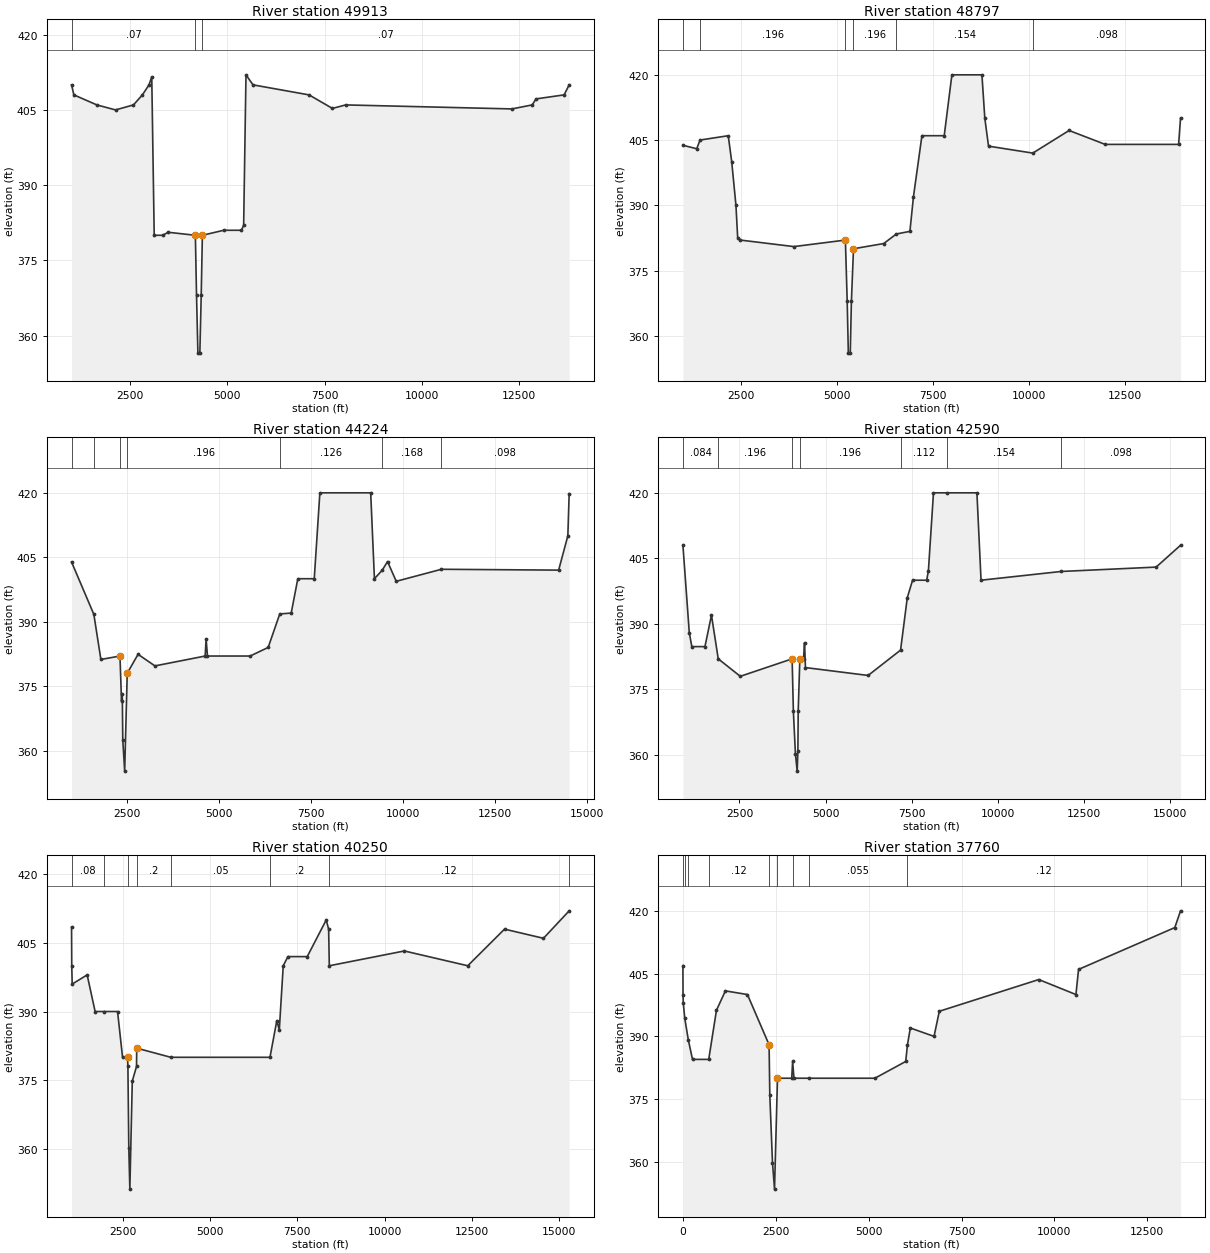
Type RM Length L Ch R = 1 ,49913   ,1000,1116,1220
BEGIN DESCRIPTION:
Downstream bounding cross-section for IH 20 bridge.
END DESCRIPTION:
XS GIS Cut Line= 6
  2528868.308224 6934590.0023417        2525156.        6934085.
        2523895.        6933771.        2522975.        6933430.
        2521795.        6932863. 2517167.0185856 6930000.6433261
#Sta/Elev= 30
    1000     410    1060     408    1650     406    2130     405    2590     406
    2820     408    2990     410    3060   411.6    3123     380    3339     380
    3483   380.6    4180     380    4210     368    4245   356.5    4295   356.5
    4330     368    4360     380    4908     381    5364     381    5420     382
    5480     412    5660     410    7100     408    7700   405.3    8040     406
   12310   405.2   12830     406   12930   407.2   13650     408   13780     410
#Mann= 3 ,0,0
    1000     .07       0    4180    .056       0    4360     .07       0
Bank Sta=4180,4360
XS Rating Curve= 0 ,0
Exp/Cntr=0.5,0.3

Type RM Length L Ch R = 1 ,48797   ,1200,4573,1100
BEGIN DESCRIPTION:
This cross section corresponds to cross section 48797 of the non-georeferenced CDC model which was the source of this model.
END DESCRIPTION:
XS GIS Cut Line= 3
        2530002.        6934398.        2521341.        6931649.
  2518024.709465 6929667.4509768
#Sta/Elev= 30
    1000   403.8    1360     403    1445     405    2180     406    2270     400
    2380     390  2425.4   382.5  2493.7     382  3887.9   380.5  5228.2     382
    5275     368    5305     356    5355     356    5385     368  5439.2     380
  6225.1   381.2    6555   383.4  6907.2     384    7000     392    7220     406
    7800     406    8000     420  8781.5     420  8856.6     410  8953.2   403.6
   10105     402   11050   407.2   11990     404   13900     404   13950     410
#Mann= 6 ,-1,0
    1000    .098       0    1445    .196       0  5228.2    .055       0
  5439.2    .196       0    6555    .154       0   10105    .098       0
Bank Sta=5228.2,5439.2
XS Rating Curve= 0 ,0
Exp/Cntr=0.5,0.3

Type RM Length L Ch R = 1 ,44224   ,1350,1634,1000
BEGIN DESCRIPTION:
This cross section corresponds to cross section 44224 of the non-georeferenced CDC model which was the source of this model.
END DESCRIPTION:
XS GIS Cut Line= 3
        2530833.        6933597.        2521737.        6930580.
  2518108.732608 6929040.4006048
#Sta/Elev= 30
    1000   403.9    1606   391.7  1797.3   381.2  2316.4     382    2358   371.5
    2379   373.1    2392   362.5    2444   355.2  2513.7     378  2808.1   382.4
  3266.3   379.7  4631.8     382    4657     386    4694     382    5854     382
    6344     384  6659.4   391.8    6970     392    7150     400  7596.6     400
    7749     420  9130.4     420  9232.1     400  9445.8     402  9587.5     404
  9824.8   399.4 11053.8   402.2 14238.8     402 14488.9     410 14524.7   419.8
#Mann= 7 ,-1,0
    1000   .0845       0    1606    .196       0  2316.4    .055       0
  2513.7    .196       0  6659.4    .126       0  9445.8    .168       0
 11053.8    .098       0
Bank Sta=2316.4,2513.7
XS Rating Curve= 0 ,0
Exp/Cntr=0.3,0.1

Type RM Length L Ch R = 1 ,42590   ,1800,2340,1500
BEGIN DESCRIPTION:
This cross section corresponds to cross section 42590 of the non-georeferenced CDC model which was the source of this model.
END DESCRIPTION:
XS GIS Cut Line= 4
  2531949.495492 6932273.9954373        2531811.        6932253.
        2528460.        6931745.        2518057.        6928462.
#Sta/Elev= 30
     860     408  1044.6     388    1118   384.8  1499.5   384.8  1688.6     392
  1884.9     382  2524.7     378  4028.7     382    4065     370    4125   360.2
    4175   356.3    4196     361    4205     370  4252.6     382  4358.9     382
  4388.9   385.7  4415.5     380  6233.5   378.2    7175     384  7370.4     396
  7523.4     400  7932.2     400  7982.1   402.1    8130     420    8515     420
    9390     420    9510     400   11835     402 14590.5     403 15298.1     408
#Mann= 7 ,-1,0
     860    .084       0  1884.9    .196       0  4028.7    .055       0
  4252.6    .196       0    7175    .112       0    8515    .154       0
   11835    .098       0
Bank Sta=4028.7,4252.6
XS Rating Curve= 0 ,0
Exp/Cntr=0.3,0.1

Type RM Length L Ch R = 1 ,40250   ,1550,2490,1600
BEGIN DESCRIPTION:
This cross section corresponds to cross section 40250 of the non-georeferenced CDC model which was the source of this model.
END DESCRIPTION:
XS GIS Cut Line= 4
   2531842.84604 6930562.9243886        2522496.        6928638.
 2517891.6324373 6927581.0800432 2517887.8485717 6927580.2114672
#Sta/Elev= 30
    1023   408.4  1028.9     400  1041.5     396  1470.5     398    1699     390
  1947.9     390  2342.5     390  2485.7     380  2628.7     380  2639.4     378
    2665   360.2    2695   351.2    2765   374.8  2886.2     378  2891.9     382
  3869.4     380    6714     380  6909.4     388  6981.3     386  7093.8     400
  7227.9     402  7782.2     402  8326.5     410  8396.1     408  8415.1     400
   10567  403.23   12386     400   13440     408   14557     406   15294     412
#Mann= 8 ,-1,0
    1023     .08       0  1947.9     .12       0  2628.7    .055       0
  2891.9      .2       0  3869.4     .05       0    6714      .2       0
  8415.1     .12       0   15294      .7       0
#XS Ineff= 2 , 0
          2628.7     380  2891.9             382
Permanent Ineff=
       F       F
Bank Sta=2628.7,2891.9
XS Rating Curve= 0 ,0
Exp/Cntr=0.3,0.1

Type RM Length L Ch R = 1 ,37760   ,1225.27,1241,1248.51
BEGIN DESCRIPTION:
Effective cross-section 37760
END DESCRIPTION:
XS GIS Cut Line= 3
  2531942.572074 6929038.9960888        2522566.        6927046.
 2518842.4224762 6926244.0293787
#Sta/Elev= 30
       0   406.9       3     400     9.6     398   49.63   394.3  146.49   389.1
  258.21   384.5  694.68   384.5  903.13  396.25  1143.7  400.87  1736.7     400
  2319.6     388  2338.8     376    2411   359.8    2466   353.5  2545.5     380
  2929.3     380  2952.8     384  2989.4     380  3395.5     380  5167.5     380
    5997     384  6044.3     388  6121.8     392  6759.8     390  6902.1     396
    9579  403.58   10579     400   10650     406   13241     416   13395     420
#Mann= 10 ,-1,0
       0     .03       0   49.63    .085       0  146.49    .055       0
  694.68     .12       0  2319.6    .055       0  2545.5      .2       0
  2952.8     .05       0  3395.5    .055       0  6044.3     .12       0
   13395      .2       0
#XS Ineff= 2 , 0
          2319.6     388  2545.5             380
Permanent Ineff=
       F       F
Bank Sta=2319.6,2545.5
XS Rating Curve= 0 ,0
Exp/Cntr=0.3,0.1

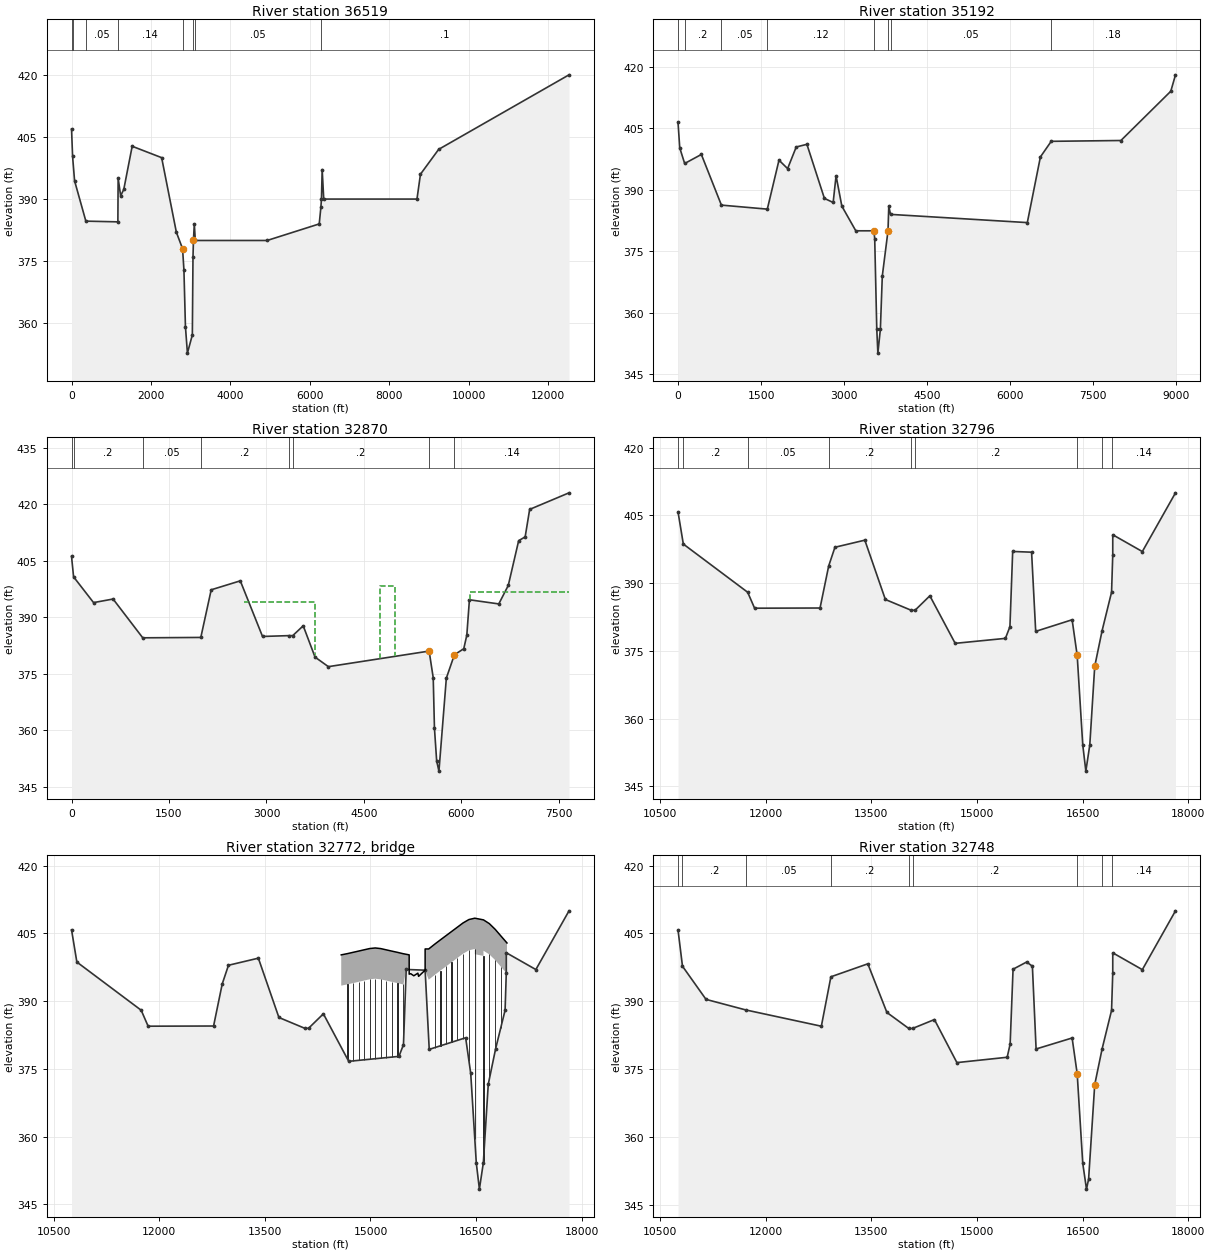
Type RM Length L Ch R = 1 ,36519   ,1364.71,1327,1266.1
BEGIN DESCRIPTION:
Effective cross-section 36519
END DESCRIPTION:
XS GIS Cut Line= 3
  2531999.271077 6928183.9640017        2523073.        6925738.
 2519909.7428233  6924882.984923
#Sta/Elev= 30
       0   406.9   26.44  400.28   76.65   394.4  360.62  384.67 1167.19   384.5
  1173.7  395.04 1236.97  390.79 1315.74  392.32 1527.48  402.75  2269.8     400
  2640.5     382    2797     378  2831.1   372.9  2869.1   359.2  2919.1   352.8
  3043.1   357.2  3059.4     376  3070.9     380  3092.8     384  3117.6     380
  4926.6     380  6239.7     384  6280.9     388  6295.9     390  6313.5  397.13
  6352.9     390  8701.9     390  8789.5     396  9248.1     402 12532.1     420
#Mann= 8 ,-1,0
       0     .03       0   26.44      .1       0  360.62     .05       0
  1173.7     .14       0    2797    .055       0  3070.9      .2       0
  3117.6     .05       0  6280.9      .1       0
#XS Ineff= 2 , 0
            2797     378  3070.9             380
Permanent Ineff=
       F       F
Bank Sta=2797,3070.9
XS Rating Curve= 0 ,0
Exp/Cntr=0.3,0.1

Type RM Length L Ch R = 1 ,35192   ,2276.66,2322,2404.44
BEGIN DESCRIPTION:
Effective cross-section 35192
END DESCRIPTION:
XS GIS Cut Line= 5
        2532161.        6927467.        2528889.        6926098.
        2528626.        6926185.        2525745.        6925123.
 2523984.8469307 6923992.5029987
#Sta/Elev= 30
       0   406.5   31.49   400.2   120.3   396.4  421.87   398.6  783.87  386.26
 1613.17  385.28 1824.16  397.21 1979.79  395.15 2135.37  400.42 2328.38  401.07
  2644.4   387.9 2802.43   386.9  2855.1   393.4  2959.7     386  3211.6     380
  3539.8     380  3553.3     378  3590.3   356.1  3610.3   350.2  3655.3     356
  3690.3     369  3793.3     380  3807.3     386  3838.8     384  6309.7     382
  6546.2     398  6741.6   401.8  8000.4     402  8901.3     414  8986.3     418
#Mann= 8 ,-1,0
       0     .03       0   120.3      .2       0  783.87     .05       0
 1613.17     .12       0  3539.8    .055       0  3793.3      .2       0
  3838.8     .05       0  6741.6     .18       0
#XS Ineff= 2 , 0
          3539.8     380  3793.3             380
Permanent Ineff=
       F       F
Bank Sta=3539.8,3793.3
XS Rating Curve= 0 ,0
Exp/Cntr=0.3,0.1

Type RM Length L Ch R = 1 ,32870   ,82.48,74,92.56
BEGIN DESCRIPTION:
Effective cross-section 32870
END DESCRIPTION:
XS GIS Cut Line= 2
        2532481.        6927143. 2525937.2663285 6923168.8478091
#Sta/Elev= 30
       0   406.1   31.43  400.69  338.78  393.85  639.31   394.8 1095.75   384.5
  1989.4   384.6 2149.35  397.25 2597.06  399.63 2939.04  384.86  3344.5  385.08
 3404.07  385.08 3565.31  387.69  3747.7  379.37 3952.43  376.84 5503.13  380.98
    5566   373.9    5585   360.5    5619   351.8    5654   349.1    5768   373.8
    5892     380    6036   381.6    6083   385.2    6123   394.6    6575   393.5
    6721   398.4    6881   410.3    6981   411.3    7050   418.6    7656     423
#Mann= 8 ,-1,0
       0     .03       0   31.43      .2       0 1095.75     .05       0
  1989.4      .2       0  3344.5    .035       0 3404.07      .2       0
 5503.13    .055       0    5892     .14       0
#XS Ineff= 3 ,-1
    2659    3744     394    4744    4979   398.3    6139    7656   396.6
Permanent Ineff=
       F       F       F
Bank Sta=5503.13,5892
XS Rating Curve= 0 ,0
Exp/Cntr=0.3,0.1

Type RM Length L Ch R = 1 ,32796   ,59.02,48,72.03
BEGIN DESCRIPTION:
Effective cross-section 32796
END DESCRIPTION:
XS GIS Cut Line= 4
  2532565.244241 6927080.8812985 2527617.4591369 6924126.3696965
 2526566.2021101 6923494.5010397 2526501.3432065 6923455.5169405
#Sta/Elev= 30
   10755   405.810830.55  398.6611744.28  387.9911842.52  384.4612772.13   384.5
 12894.9  393.8112983.62  397.9513408.12  399.5213699.82  386.3914066.54     384
14121.15     38414331.56   387.214691.13  376.6815404.73  377.7815468.81  380.37
15507.78  397.0215776.37  396.8615834.64  379.33   16352   381.9   16424     374
   16503   354.216546.97  348.39   16603   354.2   16673   371.6   16778   379.5
   16912     388   16929  396.27   16929  400.72   17349     397   17820     410
#Mann= 9 ,-1,0
   10755     .03       010830.55      .2       011744.28     .05       0
 12894.9      .2       014066.54    .035       014121.15      .2       0
   16424    .055       0   16778      .2       0   16912     .14       0
Bank Sta=16424,16673
XS Rating Curve= 0 ,0
Exp/Cntr=0.3,0.1

Type RM Length L Ch R = 3 ,32772   ,,,
BEGIN DESCRIPTION:
Dowdy-Ferry Road
Bridge data revised May 2002 from bridge plans dated 12-98 supplied by TXDOT.  Bridge plans supplied in metric, therefore stationing and elevations were converted to english prior to input.  Main bridge length is 1092.2 ft. (333.0 m) and relief bridge length is 944.6 ft (288.0m).
END DESCRIPTION:
Node Name=Dowdy-Ferry Road
Bridge Culvert--1,0,-1,-1, 0
Deck Dist Width WeirC Skew NumUp NumDn MinLoCord MaxHiCord MaxSubmerge Is_Ogee
2,44,2.6,0, 36, 36, , , 0.95, 0, ,,,
   14585   14674   14753   14832   14910   14989   15068   15146   15225   15304
   15383   15461   15550   15550   1557115615.7415673.3915683.5315776.3715776.37
   15827   15916   15994   16073   16152   16231   16314   16398   16482   16482
   16605   16605   16688   16772   16851   16939
  400.25  400.53  400.81  401.09  401.37  401.65  401.78  401.64  401.36  401.08
  400.81  400.52  400.25  395.97  396.09  395.62   396.2  395.49  396.86  401.56
  401.56  402.66  403.58   404.5  405.42  406.34  407.31  408.07  408.37  408.37
     408     408  407.17  405.89  404.46  402.88
  393.44  393.72     394  394.28  394.56  394.84  394.97  394.83  394.55  394.27
     394  393.71  393.44  393.44  396.09  395.62   396.2  395.49  396.86  394.75
  394.75  395.85  396.77  397.69  398.61  399.53   400.5  401.26  401.56   400.4
  400.02  401.17  400.36  399.08  397.65  396.07
   14585   14674   14753   14832   14910   14989   15068   15146   15225   15304
   15383   15461   15550   15550   15571   1570315720.62 15766.615787.7615787.76
   15827   15916   15994   16073   16152   16231   16314   16398   16482   16482
   16605   16605   16688   16772   16851   16939
  400.25  400.53  400.81  401.09  401.37  401.65  401.78  401.64  401.36  401.08
  400.81  400.52  400.25  393.44  398.31  398.34  398.05  398.29  397.76  401.56
  401.56  402.66  403.58   404.5  405.42  406.34  407.31  408.07  408.37  408.37
     408     408  407.17  405.89  404.46  402.88
  393.44  393.72     394  394.28  394.56  394.84  394.97  394.83  394.55  394.27
     394  393.71  393.44  393.44  398.31  398.34  398.05  398.29  397.76  394.75
  394.75  395.85  396.77  397.69  398.61  399.53   400.5  401.26  401.56   400.4
  400.02  401.17  400.36  399.08  397.65  396.07
Pier Skew, UpSta & Num, DnSta & Num=  ,14674, 2 ,14674, 2 , 0 , 0 , 0 ,,
     2.5     2.5
       0     396
     2.5     2.5
       0     396
Pier Skew, UpSta & Num, DnSta & Num=  ,14753, 2 ,14753, 2 , 0 , 0 , 0 ,,
     2.5     2.5
       0     396
     2.5     2.5
       0     396
Pier Skew, UpSta & Num, DnSta & Num=  ,14832, 2 ,14832, 2 , 0 , 0 , 0 ,,
     2.5     2.5
       0     396
     2.5     2.5
       0     396
Pier Skew, UpSta & Num, DnSta & Num=  ,14910, 2 ,14910, 2 , 0 , 0 , 0 ,,
     2.5     2.5
       0     396
     2.5     2.5
       0     396
Pier Skew, UpSta & Num, DnSta & Num=  ,14989, 2 ,14989, 2 , 0 , 0 , 0 ,,
     2.5     2.5
       0     396
     2.5     2.5
       0     396
Pier Skew, UpSta & Num, DnSta & Num=  ,15068, 2 ,15068, 2 , 0 , 0 , 0 ,,
     2.5     2.5
       0     396
     2.5     2.5
       0     396
Pier Skew, UpSta & Num, DnSta & Num=  ,15146, 2 ,15146, 2 , 0 , 0 , 0 ,,
     2.5     2.5
       0     396
     2.5     2.5
       0     396
Pier Skew, UpSta & Num, DnSta & Num=  ,15225, 2 ,15225, 2 , 0 , 0 , 0 ,,
     2.5     2.5
       0     396
     2.5     2.5
       0     396
Pier Skew, UpSta & Num, DnSta & Num=  ,15304, 2 ,15304, 2 , 0 , 0 , 0 ,,
     2.5     2.5
       0     396
     2.5     2.5
       0     396
Pier Skew, UpSta & Num, DnSta & Num=  ,15383, 2 ,15383, 2 , 0 , 0 , 0 ,,
     2.5     2.5
       0     396
     2.5     2.5
       0     396
Pier Skew, UpSta & Num, DnSta & Num=  ,15461, 2 ,15461, 2 , 0 , 0 , 0 ,,
     2.5     2.5
       0     396
     2.5     2.5
       0     396
Pier Skew, UpSta & Num, DnSta & Num=  ,15916, 2 ,15916, 2 , 0 , 0 , 0 ,,
     2.5     2.5
       0     400
     2.5     2.5
       0     400
Pier Skew, UpSta & Num, DnSta & Num=  ,15994, 2 ,15994, 2 , 0 , 0 , 0 ,,
     2.5     2.5
       0     400
     2.5     2.5
       0     400
Pier Skew, UpSta & Num, DnSta & Num=  ,16073, 2 ,16073, 2 , 0 , 0 , 0 ,,
     2.5     2.5
       0     400
     2.5     2.5
       0     400
Pier Skew, UpSta & Num, DnSta & Num=  ,16152, 2 ,16152, 2 , 0 , 0 , 0 ,,
     2.5     2.5
       0     401
     2.5     2.5
       0     401
Pier Skew, UpSta & Num, DnSta & Num=  ,16231, 2 ,16231, 2 , 0 , 0 , 0 ,,
     2.5     2.5
       0     401
     2.5     2.5
       0     401
Pier Skew, UpSta & Num, DnSta & Num=  ,16314, 2 ,16314, 2 , 0 , 0 , 0 ,,
     2.5     2.5
       0     402
     2.5     2.5
       0     402
Pier Skew, UpSta & Num, DnSta & Num=  ,16398, 2 ,16398, 2 , 0 , 0 , 0 ,,
     2.5     2.5
       0     403
     2.5     2.5
       0     403
Pier Skew, UpSta & Num, DnSta & Num=  ,16482, 2 ,16482, 2 , 0 , 0 , 0 ,,
     3.5     3.5
       0     403
     3.5     3.5
       0     403
Pier Skew, UpSta & Num, DnSta & Num=  ,16605, 2 ,16605, 2 , 0 , 0 , 0 ,,
     3.5     3.5
       0     403
     3.5     3.5
       0     403
Pier Skew, UpSta & Num, DnSta & Num=  ,16688, 2 ,16688, 2 , 0 , 0 , 0 ,,
     2.5     2.5
       0     403
     2.5     2.5
       0     403
Pier Skew, UpSta & Num, DnSta & Num=  ,16772, 2 ,16772, 2 , 0 , 0 , 0 ,,
     2.5     2.5
       0     403
     2.5     2.5
       0     403
Pier Skew, UpSta & Num, DnSta & Num=  ,16851, 2 ,16851, 2 , 0 , 0 , 0 ,,
     2.5     2.5
       0     403
     2.5     2.5
       0     403
BR Coef= 1 , 0 , 0 ,1.05, 0 ,,,0.8,-1,0.5,1,
WSPro=,,,, 1 ,,,, 0 ,,,, 0 ,,,,-1 ,-1 ,-1 , 0 , 0 , 0 , 0 , 0
BC Design=,, 0 ,, 0 ,,,,,,
BC HTab HWMax=410
BC Use User HTab Curves=0
BC User HTab FreeFlow(D)= 0

Type RM Length L Ch R = 1 ,32748   ,79.13,90,75.71
BEGIN DESCRIPTION:
Effective cross-section 32748
END DESCRIPTION:
XS GIS Cut Line= 5
  2532589.226859 6927040.9092907 2527625.4270302 6924079.3891722
 2526593.2980008 6923454.9935626 2526529.5102946 6923416.4046241
 2526526.0730274 6923414.3252188
#Sta/Elev= 30
   10755   405.8 10818.5  397.7611152.92  390.4311719.55  388.0912790.71   384.5
12926.12  395.4213450.67  398.2913721.77  387.54 14032.4     384 14085.4     384
14396.27  385.9714715.65  376.4615429.65  377.6415471.81  380.5615513.23   397.1
15706.31  398.6915787.76  397.7615840.32  379.47   16352   381.9   16424     374
   16503   354.2   16556   348.5   16586   350.7   16673   371.6   16778   379.5
   16912     388   16929  396.27   16929  400.72   17349     397   17820     410
#Mann= 9 ,-1,0
   10755     .03       0 10818.5      .2       011719.55     .05       0
12926.12      .2       0 14032.4    .035       0 14085.4      .2       0
   16424    .055       0   16778      .2       0   16912     .14       0
Bank Sta=16424,16673
XS Rating Curve= 0 ,0
Exp/Cntr=0.3,0.1

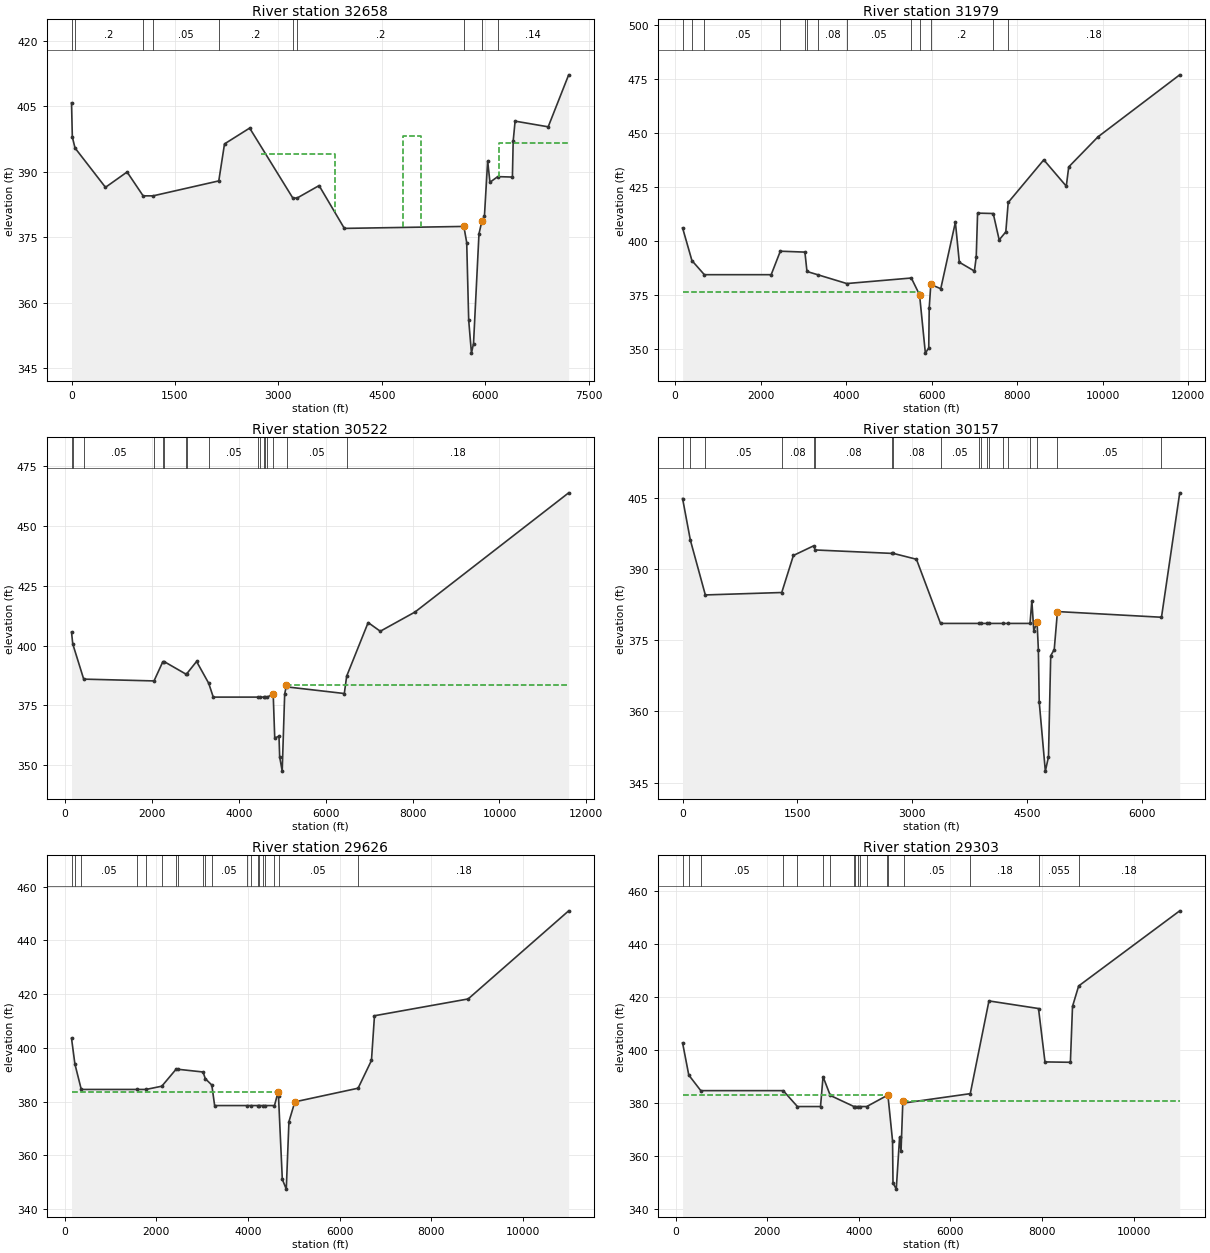
Type RM Length L Ch R = 1 ,32658   ,715.11,679,731.59
BEGIN DESCRIPTION:
Effective cross-section 32658
END DESCRIPTION:
XS GIS Cut Line= 3
  2532671.702667 6926959.3543574        2526803.        6923474.
 2526475.8884191 6923270.2843058
#Sta/Elev= 30
       0   405.8   11.78  397.96      51395.4489  492.51  386.45  805.88  389.96
 1038.59   384.5  1182.8   384.5    2136387.9213 2219.06  396.39 2583.79  400.01
 3209.84     384 3272.23     384 3590.83  386.85 3957.12  377.05    5691   377.5
    5732   373.8    5761     356    5801   348.5    5831   350.7    5910   375.8
    5952   378.7    5989   379.8    6036   392.5    6069   387.6    6182   388.9
    6395   388.8    6406     397    6434   401.6    6914   400.3    7211   412.2
#Mann= 10 ,-1,0
       0     .03       0      51      .2       0 1038.59     .07       0
  1182.8     .05       0    2136      .2       0 3209.84    .035       0
 3272.23      .2       0    5691    .055       0    5952      .2       0
    6182     .14       0
#XS Ineff= 3 ,-1
    2745    3820     394    4805    5062   398.3    6195    7211   396.5
Permanent Ineff=
       F       F       F
Bank Sta=5691,5952
XS Rating Curve= 0 ,0
Exp/Cntr=0.3,0.1

Type RM Length L Ch R = 1 ,31979   ,1521.57,1457,1478.75
XS GIS Cut Line= 4
2532718.407701396926630.176926482530658.45840922 6925243.4726789
2528106.199406136923499.98305565 2523178.6193663 6920346.3564889
#Sta/Elev= 30
  174.92  406.14  393.71  391.02  683.83   384.5 2247.15   384.5 2460.65  395.36
 3035.92  394.94    3084  385.98 3343.64  384.43 4015.18   380.4 5524.48  382.96
 5716.96   375.2 5852.95  348.22 5931.76  350.62 5942.49     369 5980.14  379.97
 6212.98  378.01 6554.93  408.75 6646.91  390.25  6999.5  386.18 7042.27  392.58
 7074.35  412.97 7440.12  412.79 7579.37  400.59 7734.17  404.29 7790.39  417.91
 8622.23  437.61 9148.75  425.43 9205.58  434.34 9890.55  448.2611801.46  476.93
#Mann= 13 ,-1,0
  174.92     .03       0  393.71      .2       0  683.83     .05       0
 2460.65     .08       0 3035.92    .035       0    3084    .055       0
 3343.64     .08       0 4015.18     .05       0 5524.48      .2       0
 5716.96    .055       0 5980.14      .2       0 7440.12    .055       0
 7790.39     .18       0
#XS Ineff= 2 , 0
         5716.96  376.29 5980.14          379.97
Permanent Ineff=
       F       F
Bank Sta=5716.96,5980.14
XS Rating Curve= 0 ,0
Exp/Cntr=0.3,0.1

Type RM Length L Ch R = 1 ,30522   ,356.63,365,375.78
XS GIS Cut Line= 6
2532843.582975976926470.118519562531161.084700556924825.26255731
2529584.695792976923409.030153562529380.702762636923244.09938106
2526660.278741556921549.593583732523884.332193726919815.32736723
#Sta/Elev= 30
  150.34  405.64  178.64  400.71  430.61  386.01 2048.98  385.26 2252.34   393.3
 2285.94   393.3 2774.13   388.2 2800.13   388.2 3028.67  393.39  3308.2  384.26
 3412.37   378.5 4449.75   378.5 4488.57   378.5 4573.93   378.5 4607.66   378.5
 4657.63   378.5 4791.75  379.89 4827.41  361.41 4925.13  362.17 4940.95   353.5
 4999.25  347.58 5056.13  379.76 5097.74  383.46 5104.94  382.77 6428.61     380
 6483.45  387.27 6977.29  409.64 7256.37  406.01 8057.55  414.06 11592.5  463.83
#Mann= 17 ,-1,0
  150.34     .03       0  178.64      .2       0  430.61     .05       0
 2048.98     .08       0 2252.34    .035       0 2285.94     .08       0
 2774.13    .035       0 2800.13     .08       0  3308.2     .05       0
 4449.75     .07       0 4488.57     .05       0 4573.93     .07       0
 4607.66     .05       0 4657.63     .18       0 4791.75    .055       0
 5104.94     .05       0 6483.45     .18       0
#XS Ineff= 2 , 0
                         5097.65          383.46
Permanent Ineff=
       F       F
Bank Sta=4791.75,5097.74
XS Rating Curve= 0 ,0
Exp/Cntr=0.3,0.1

Type RM Length L Ch R = 1 ,30157   ,537.7,531,552.05
BEGIN DESCRIPTION:
Effective cross-section 30157
END DESCRIPTION:
XS GIS Cut Line= 3
        2533311.        6926327.        2532244.        6925299.
 2528503.9272321 6921969.5171439
#Sta/Elev= 30
       0   404.8   101.6  396.04  297.04   384.5 1294.39  385.01 1446.49  392.81
 1711.77  394.85  1730.4  393.97 2728.77  393.25 2749.77  393.25 3052.64  392.01
 3366.76   378.5 3867.22   378.5 3901.32   378.5  3970.8   378.5 4005.34   378.5
 4182.34   378.5 4241.23   378.5 4534.98   378.5  4558.9  383.29 4583.98  376.99
    4627   378.7    4644     373    4655     362    4735   347.4    4776   350.4
    4805   371.7    4851     373    4893     381    6251   379.8    6489     406
#Mann= 19 ,-1,0
       0     .03       0   101.6      .2       0  297.04     .05       0
 1294.39     .08       0 1711.77    .035       0  1730.4     .08       0
 2728.77    .035       0 2749.77     .08       0 3366.76     .05       0
 3867.22     .07       0 3901.32     .05       0  3970.8     .07       0
 4005.34     .05       0 4182.34     .07       0 4241.23     .05       0
 4534.98     .18       0    4627    .055       0    4893     .05       0
    6251     .18       0
#XS Ineff= 2 , 0
            4627   378.7    4893             381
Permanent Ineff=
       F       F
Bank Sta=4627,4893
XS Rating Curve= 0 ,0
Exp/Cntr=0.3,0.1

Type RM Length L Ch R = 1 ,29626   ,347.71,323,323.63
XS GIS Cut Line= 6
 2533486.10268836926060.092436732530471.761604136923025.57225905
2528495.038195396921227.044031982527924.886776646920827.65572314
2527596.761776726920608.905504482525255.859962466919199.00806181
#Sta/Elev= 30
  151.96  403.55  226.04  393.95  364.61   384.5 1585.81   384.5 1777.56   384.5
 2121.56  385.71 2431.54     392 2483.02     392 3021.83     391 3070.33  388.51
 3212.83  386.14 3274.15   378.5 3973.24   378.5 4058.24   378.5 4210.13   378.5
 4245.83   378.5 4330.33   378.5 4364.22   378.5 4579.89   378.5 4656.67  383.44
 4667.64  381.91 4750.72  351.02 4837.16  347.36 4895.11   372.5  5024.4  379.88
 6403.96  384.96 6695.67  395.32 6761.48  411.96 8805.15  418.2210998.04  451.05
#Mann= 20 ,-1,0
  151.96     .03       0  226.04      .2       0  364.61     .05       0
 1585.81     .07       0 1777.56     .05       0 2121.56     .08       0
 2431.54    .035       0 2483.02     .08       0 3021.83    .035       0
 3070.33     .08       0 3212.83     .05       0 3973.24     .07       0
 4058.24     .05       0 4210.13     .07       0 4245.83     .05       0
 4330.33     .07       0 4364.22     .05       0 4579.89     .18       0
 4667.64     .05       0 6403.96     .18       0
#XS Ineff= 2 , 0
         4656.65  383.44  5024.6          379.88
Permanent Ineff=
       F       F
Bank Sta=4656.67,5024.4
XS Rating Curve= 0 ,0
Exp/Cntr=0.3,0.1

Type RM Length L Ch R = 1 ,29303   ,281.84,300,294.45
XS GIS Cut Line= 4
2533933.73860405 6925600.15897342530684.075155886922743.62630065
2527964.410319646920710.220262482525451.17256397 6919003.6954603
#Sta/Elev= 30
  147.96  402.54  283.53  390.38  545.55   384.5 2346.82   384.5 2656.89   378.5
 3161.76   378.5 3216.59  389.76 3375.05  382.69 3892.67   378.5 3925.77   378.5
 3986.74   378.5 4018.84   378.5 4171.84   378.5 4610.48  382.63 4634.12  382.78
 4735.39  365.56 4745.29  349.68 4816.66  347.33 4888.94  366.83 4920.63  361.63
 4960.49  380.56 4982.23  379.82 6433.51  383.36 6841.52  418.36 7924.32  415.49
 8065.63  395.34 8621.06   395.2 8667.23  416.29 8801.55  424.0111009.59  452.36
#Mann= 18 ,-1,0
  147.96     .03       0  283.53    .085       0  545.55     .05       0
 2346.82    .085       0 2656.89     .05       0 3216.59    .085       0
 3375.05     .05       0 3892.67     .07       0 3925.77     .05       0
 3986.74     .07       0 4018.84     .05       0 4171.84     .07       0
 4610.48      .2       0 4634.12    .055       0 4982.23     .05       0
 6433.51     .18       0 7924.32    .055       0 8801.55     .18       0
#XS Ineff= 2 , 0
         4636.56  382.78 4961.01          380.56
Permanent Ineff=
       F       F
Bank Sta=4634.12,4960.49
XS Rating Curve= 0 ,0
Exp/Cntr=0.3,0.1

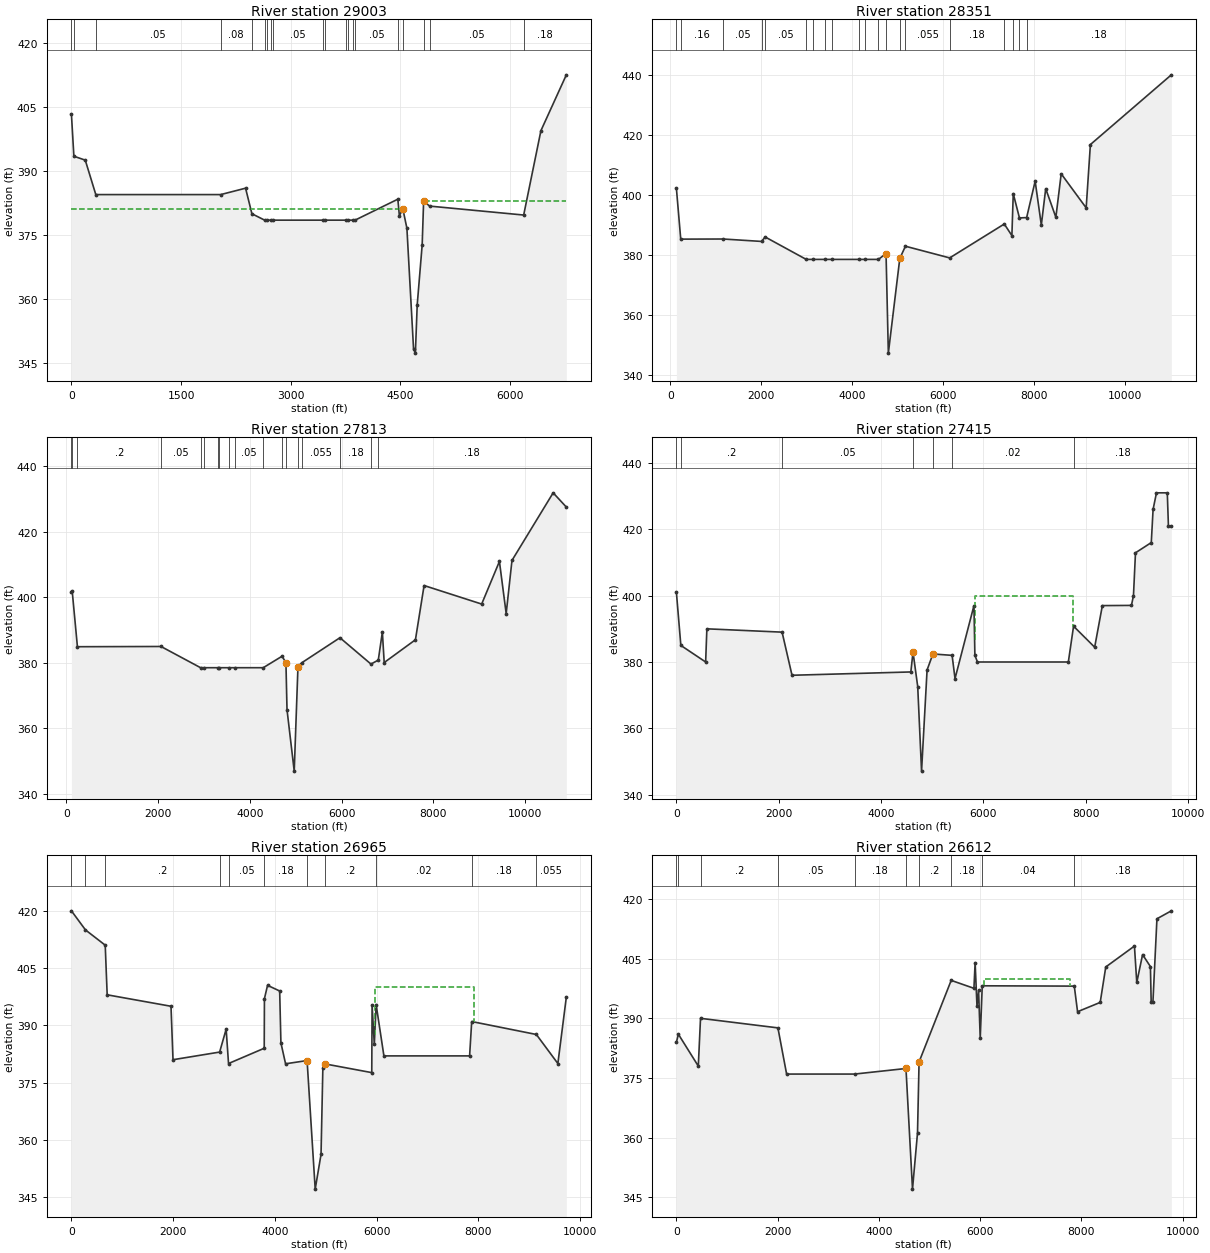
Type RM Length L Ch R = 1 ,29003   ,698.48,652,666.01
BEGIN DESCRIPTION:
Effective cross-section 29003
END DESCRIPTION:
XS GIS Cut Line= 2
        2534225.        6925433. 2529100.9702698 6921003.7959717
#Sta/Elev= 30
       0   403.4   33.76   393.5  189.61  392.58  333.76   384.5 2042.95   384.5
 2383.26     386    2470     380 2644.58   378.5 2677.58   378.5 2730.58   378.5
 2763.58   378.5 3439.98   378.5 3474.35   378.5 3757.94   378.5 3790.94   378.5
 3847.94   378.5 3880.94   378.5 4467.16  383.42  4487.8  379.55    4536   381.1
    4591   376.6    4682   348.3    4707   347.3    4732   358.6    4800   372.7
    4820     383    4901   381.8    6189   379.7    6425   399.5    6773   412.6
#Mann= 20 ,-1,0
       0     .03       0   33.76     .16       0  333.76     .05       0
 2042.95     .08       0    2470     .05       0 2644.58     .07       0
 2677.58     .05       0 2730.58     .07       0 2763.58     .05       0
 3439.98     .07       0 3474.35     .05       0 3757.94     .07       0
 3790.94     .05       0 3847.94     .07       0 3880.94     .05       0
 4467.16      .2       0    4536    .055       0    4820      .2       0
    4901     .05       0    6189     .18       0
#XS Ineff= 2 , 0
         4535.92   381.1 4819.92             383
Permanent Ineff=
       F       F
Bank Sta=4536,4820
XS Rating Curve= 0 ,0
Exp/Cntr=0.3,0.1

Type RM Length L Ch R = 1 ,28351   ,530.09,538,536.72
XS GIS Cut Line= 3
2534603.393432726924950.323986982528166.88432413 6919296.1578019
2526449.436315486917875.22330782
#Sta/Elev= 30
  135.37  402.22  230.82  385.27 1166.11  385.31 2010.26   384.5 2087.72     386
  2992.4   378.5 3140.52   378.5 3412.83   378.5 3557.77   378.5 4155.89   378.5
 4288.89   378.5 4580.78   378.5  4748.8  380.46 4799.41   347.2 5051.49  378.82
 5175.25   382.9 6149.13     379 7350.76  390.32 7518.27  386.45  7548.2  400.47
 7684.43  392.35 7842.76  392.47 8030.23  404.61 8165.85  389.97  8262.6  402.12
 8485.98  392.56  8603.3  407.08 9152.93  395.71 9245.61  416.8511027.14  440.14
#Mann= 20 ,-1,0
  135.37     .03       0  230.82     .16       0 1166.11     .05       0
 2010.26     .18       0 2087.72     .05       0  2992.4    .058       0
 3140.52     .05       0 3412.83    .058       0 3557.77     .05       0
 4155.89     .07       0 4288.89     .05       0 4580.78     .18       0
  4748.8    .055       0 5051.49      .2       0 5175.25    .055       0
 6149.13     .18       0 7350.76    .055       0  7548.2     .18       0
 7684.43    .055       0 7842.76     .18       0
#XS Ineff= 2 , 0
          4748.8  380.46 5051.49          378.82
Permanent Ineff=
       F       F
Bank Sta=4748.8,5051.49
XS Rating Curve= 0 ,0
Exp/Cntr=0.3,0.1

Type RM Length L Ch R = 1 ,27813   ,347.3,398,428.04
XS GIS Cut Line= 5
2534840.960542896924690.39110789 2532803.16901486922748.41467689
2531035.807720146921085.220496732528739.150568056918629.39174698
2527230.686393386917202.48023073
#Sta/Elev= 30
  108.42  401.69  125.45  401.89  239.37   384.9 2062.54  384.97 2925.47   378.5
 3006.12   378.5 3294.85   378.5 3329.85   378.5 3553.35   378.5 3665.07   378.5
 4291.83   378.5 4702.44     382 4786.78  380.03 4810.11   365.7 4967.44  346.96
 5049.14  378.83 5131.64     380  5964.5  387.64  6640.7  379.61 6800.76  380.82
 6889.58  389.37 6929.67  380.07 7610.79  387.02  7799.5  403.56 9055.27  397.91
 9442.42   410.9 9589.75  395.02 9716.31  411.2210614.28  431.8310902.06  427.48
#Mann= 18 ,-1,0
  108.42     .03       0  125.45     .08       0  239.37      .2       0
 2062.54     .05       0 2925.47     .07       0 3006.12     .05       0
 3294.85     .07       0 3329.85     .05       0 3553.35     .07       0
 3665.07     .05       0 4291.83     .07       0 4702.44      .2       0
 4786.78    .055       0 5049.14      .2       0 5131.64    .055       0
  5964.5     .18       0  6640.7    .055       0 6800.76     .18       0
#XS Ineff= 2 , 0
         4786.78  380.03 5049.14          378.83
Permanent Ineff=
       F       F
Bank Sta=4786.78,5049.14
XS Rating Curve= 0 ,0
Exp/Cntr=0.3,0.1

Type RM Length L Ch R = 1 ,27415   ,441.3778,449.8918,539.0187
BEGIN DESCRIPTION:
Effective cross-section 27415
Modified by NDM 2024 for 1700 Fulghum Site
Proposed Condition
END DESCRIPTION:
XS GIS Cut Line= 4
   2535022.52237 6924641.6895774        2532017.        6921839.
        2531386.        6920368. 2528441.5228829 6917729.2609209
#Sta/Elev= 30
       0     401   86.76     385  571.31     380  595.37     390 2064.92     389
 2258.85     376 4580.84     377 4622.98     383    4715   372.6    4790   347.1
    4898   377.6 5012.06  382.42 5386.85     382 5443.95     375 5813.91     397
 5832.14     382 5882.39     380 7658.17     380 7760.07  390.79 8172.46  384.46
 8322.67     397    8891  397.06 8930.65     400 8969.97  412.92  9278.7     416
 9313.94     426 9380.03     431  9591.5     431 9613.53  421.08 9670.66     421
#Mann= 7 ,-1,0
       0     .03       0   86.76      .2       0 2064.92     .05       0
 4622.98    .055       0 5012.06      .2       0 5386.85     .02       0
 7760.07     .18       0
#XS Ineff= 3 ,-1
       0 4622.98     383 5012.06 5826.66  382.42 5826.66 7757.88     400
Permanent Ineff=
       F       F       F
Bank Sta=4622.98,5012.06
XS Rating Curve= 0 ,0
Exp/Cntr=0.3,0.1

Type RM Length L Ch R = 1 ,26965   ,321.1337,353.5231,380.5892
BEGIN DESCRIPTION:
Modified by NDM 2024 for 1701 Fulghum Site
END DESCRIPTION:
XS GIS Cut Line= 4
  2535138.332333 6924565.0005527 2532476.0001636 6921822.8098162
 2531839.9089238 6920266.7023348 2528600.5272945 6917576.1869997
#Sta/Elev= 30
       0     420  276.19     415  664.45     411  702.85     398 1957.22     395
 1996.61     381 2912.93     383 3040.93     389 3087.86     380 3789.31     384
 3793.38     397 3854.64  400.48 4092.93     399 4117.27  385.42 4208.83  379.93
 4631.68  380.78 4791.12   347.1 4905.78   356.2 4941.54  378.79 4980.08  379.91
 5902.73  377.62 5909.14  395.37 5952.51     385 5988.51  395.44 6141.47     382
 7825.63     382 7866.77     391 9137.47  387.61 9560.16     380    9727  397.44
#Mann= 11 ,-1,0
       0     .03       0  276.19     .08       0  664.45      .2       0
 2912.93     .07       0 3087.86     .05       0 3789.31     .18       0
 4631.68    .055       0 4980.08      .2       0 5988.51     .02       0
 7866.77     .18       0 9137.47    .055       0
#XS Ineff= 3 ,-1
       0 4631.68  380.78 4980.08 5960.65  379.91 5960.65 7915.52     400
Permanent Ineff=
       F       F       F
Bank Sta=4631.68,4980.08
XS Rating Curve= 0 ,0
Exp/Cntr=0.3,0.1

Type RM Length L Ch R = 1 ,26612   ,400.7354,425.0659,447.1391
BEGIN DESCRIPTION:
added XS by Cardinal Strategies 10-2021
Modified by NDM for 1701 Fulghum
END DESCRIPTION:
XS GIS Cut Line= 4
  2535131.423444 6924419.2804212 2532732.9642668 6921827.2369813
 2532299.0937098  6920259.192654 2528725.2462838 6917322.2194897
#Sta/Elev= 30
       0     384    39.4     386  432.63     378  476.55     390 2005.54   387.6
 2177.57     376 3520.36     376 4535.71   377.4 4664.64   347.1  4763.6   361.2
 4794.46  379.05 5429.17  399.53 5878.45  397.54 5902.07     404 5938.56   393.1
 5970.23     397 6002.77     385 6042.74  398.17 7861.29  398.09 7925.83  391.66
 8373.15     394 8483.24   402.9 9049.62  408.15 9095.75     399 9210.35     406
 9365.16     403 9380.64     394 9414.54     394 9494.16     415 9778.77     417
#Mann= 10 ,-1,0
       0     .03       0    39.4     .08       0  476.55      .2       0
 2005.54     .05       0 3520.36     .18       0 4535.71    .055       0
 4794.46      .2       0 5429.17     .18       0 6042.74     .04       0
 7861.29     .18       0
#XS Ineff= 3 ,-1
       0 4535.71   377.4 4794.46 6084.44  379.05 6084.44  7777.1     400
Permanent Ineff=
       F       F       F
Bank Sta=4535.71,4794.46
XS Rating Curve= 0 ,0
Exp/Cntr=0.3,0.1