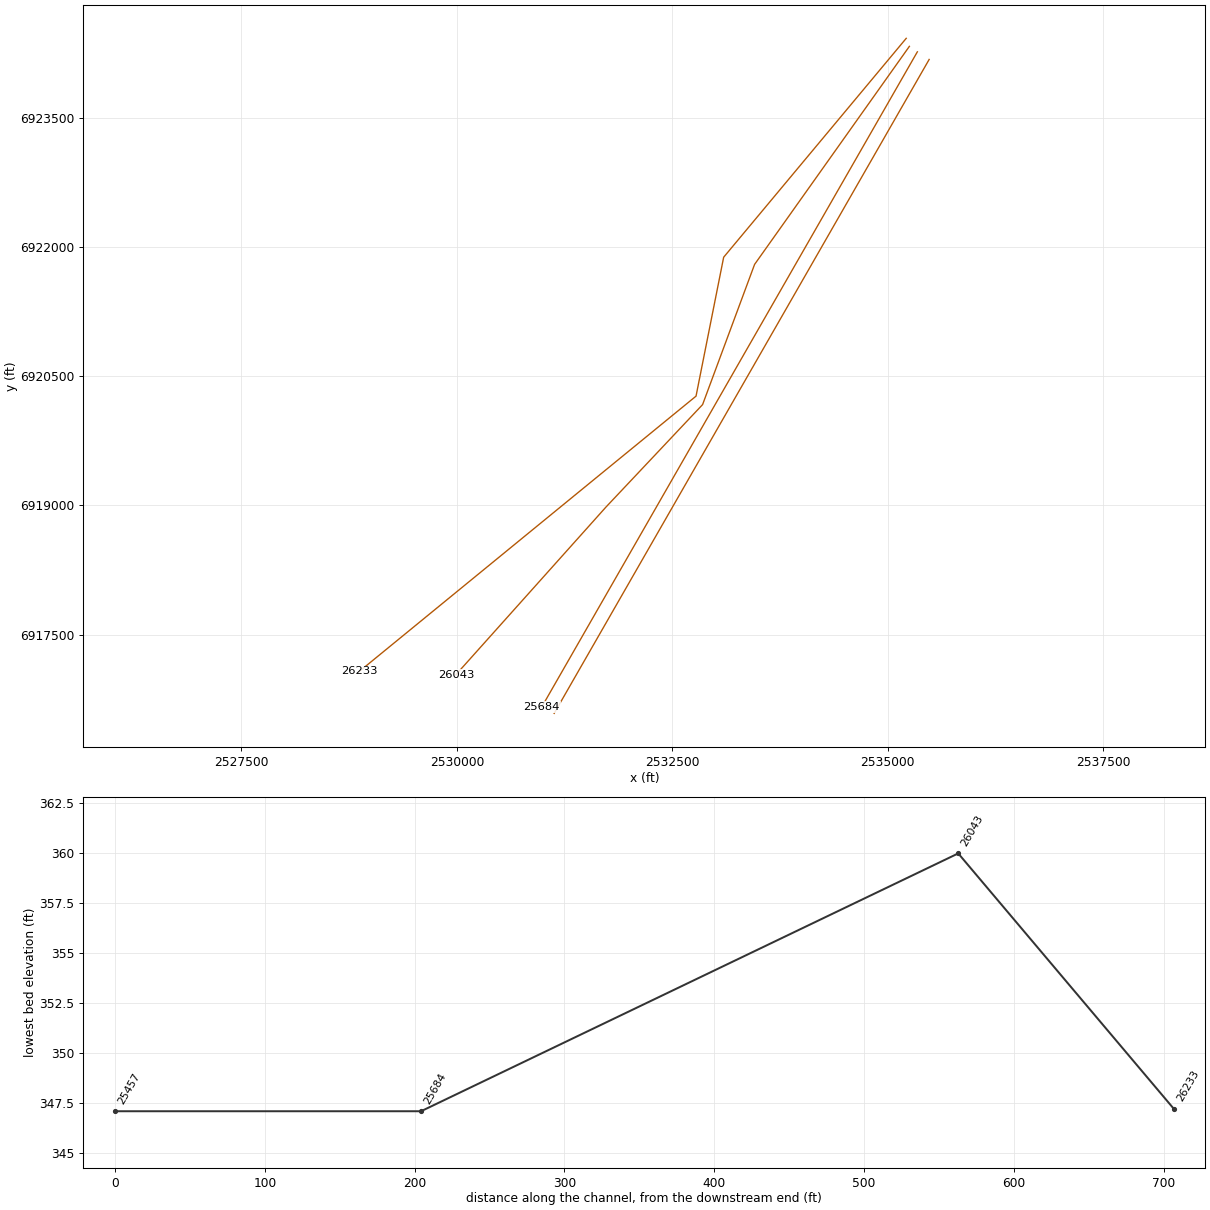
HEC-RAS study CDC_Consolidated_Model.prj: Upper Trinity CDC Consolidated Model

--- CDC_Consolidated_Model.g12 (geometry) --- (continued)

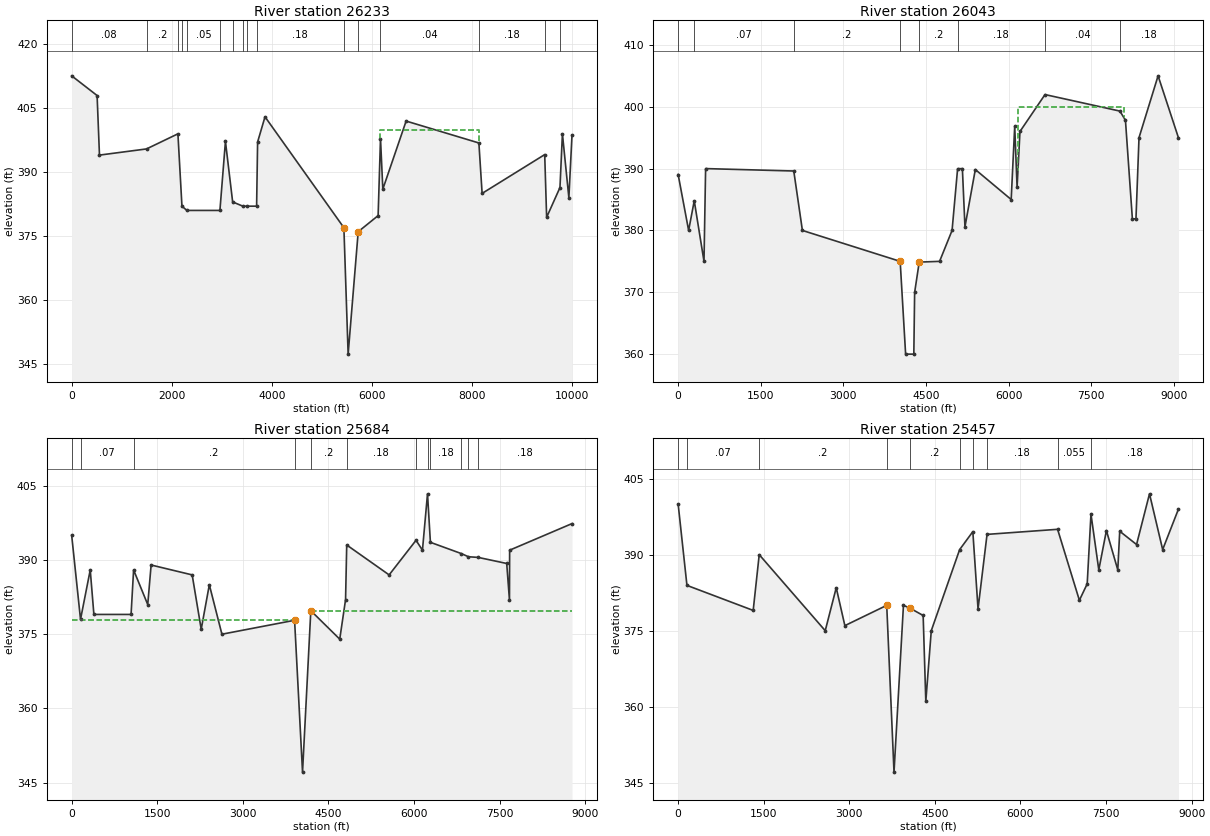
Type RM Length L Ch R = 1 ,26233   ,332.39,143.84,166.94
XS GIS Cut Line= 4
  2535214.736042  6924424.505813  2533096.035227  6921882.642786
  2532775.328519  6920269.295947  2528871.617823  6917075.765261
#Sta/Elev= 30
       0  412.63  507.79     408  555.25     394 1495.43  395.45 2122.78     399
 2203.31     382  2301.4     381 2962.06     381 3072.27  397.22 3216.39     383
 3419.85     382 3500.39     382  3695.3     382 3715.13  397.08 3862.94     403
 5439.15  376.94 5524.06  347.23 5725.19     376 6123.24  379.786170.689   397.9
 6217.18     386 6682.65     402 8136.72  396.85 8201.08     385 9451.97  394.12
 9490.41  379.38 9756.85  386.38 9805.77     399 9934.61     384 9997.56  398.74
#Mann= 16 ,-1,0
       0     .08       0 1495.43      .2       0 2122.78     .05       0
 2203.31     .07       0  2301.4     .05       0 2962.06     .18       0
 3216.39     .05       0 3419.85     .07       0 3500.39     .05       0
  3695.3     .18       0 5439.15    .055       0 5725.19      .2       0
6170.689     .04       0 8136.72     .18       0 9451.97    .055       0
 9756.85     .18       0
#XS Ineff= 3 ,-1
       0 5439.15  376.94 5725.196170.689     3766170.689 8136.72     400
Permanent Ineff=
       F       F       F
Bank Sta=5439.15,5725.19
XS Rating Curve= 0 ,0
Exp/Cntr=0.3,0.1

Type RM Length L Ch R = 1 ,26043   ,294.18,358.7,205.08
BEGIN DESCRIPTION:
Section Added by NDMC for 1701 Fulghum
END DESCRIPTION:
XS GIS Cut Line= 5
    2535251.4426    6924331.3702    2533454.8066    6921799.0721
    2532851.5183    6920171.2832    2531728.3776    6918979.2894
    2529989.1528    6917035.0303
#Sta/Elev= 30
       0  389.04190.3496     380292.4395   384.8469.4902     375498.8496     390
 2100.08  389.61 2256.61     380 4032.47     375 4131.39     360 4280.42     360
  4295.2  369.97 4378.24  374.88 4748.27     375 4975.06     380 5075.65  389.98
 5162.42  389.995209.189  380.58 5397.33  389.85 6048.74     3856112.939  396.83
 6155.85     387 6208.43     3966663.209  401.97 8022.35   399.3 8123.93  397.83
 8250.05  381.85 8315.21  381.89 8370.39     395 8716.79     405  9087.3  394.97
#Mann= 8 ,-1,0
       0     .03       0292.4395     .07       0 2100.08      .2       0
 4032.47    .055       0 4378.24      .2       0 5075.65     .18       0
6663.209     .04       0 8022.35     .18       0
#XS Ineff= 3 ,-1
       0 4032.47     375 4378.24 6171.22  374.88 6171.22 8095.03     400
Permanent Ineff=
       F       F       F
Bank Sta=4032.47,4378.24
XS Rating Curve= 0 ,0
Exp/Cntr=0.3,0.1

Type RM Length L Ch R = 1 ,25684   ,169.2233,204.2341,196.8335
BEGIN DESCRIPTION:
CDC DC06122024 Zenith Industrial Storage
Cross-sections 25684 - 27415
Project located in ROB.
END DESCRIPTION:
XS GIS Cut Line= 2
  2535343.927384 6924267.8499582 2530984.7156307 6916659.3392566
#Sta/Elev= 30
       0  394.99  154.99     378  325.14     388  389.17     379 1040.79     379
 1085.16     388 1332.92     381 1392.31     389 2111.67     387 2270.06     376
 2412.35     385 2633.04     375 3906.49  377.82 4045.85   347.1 4190.99  379.76
 4697.98     374 4800.08     382 4820.35  393.05 5563.64     387 6034.84     394
 6147.66     392 6236.16   403.4 6286.87  393.59 6829.84  391.316953.851  390.67
 7124.04  390.54 7624.34  389.31 7672.62  381.89 7675.73     392 8768.82  397.38
#Mann= 12 ,-1,0
       0     .03       0  154.99     .07       0 1085.16      .2       0
 3906.49    .055       0 4190.99      .2       0 4820.35     .18       0
 6034.84    .055       0 6236.16     .18       0 6286.87     .18       0
 6829.84    .055       06953.851       0       0 7124.04     .18       0
#XS Ineff= 2 , 0
         3906.31  377.82 4191.12          379.76
Permanent Ineff=
       F       F
Bank Sta=3906.49,4190.99
XS Rating Curve= 0 ,0
Exp/Cntr=0.3,0.1

Type RM Length L Ch R = 1 ,25457   ,270.7442,289.5838,335.122
BEGIN DESCRIPTION:
CDC DC071217-1 Dallas County Hunting and Fishing Club
Cross-section 25457 - 37760
Project located in ROB.
CDC DC1220221 The Organic Recycler
Cross-section 25167 - 27415
Project located in ROB.
END DESCRIPTION:
XS GIS Cut Line= 3
   2535480.92289 6924179.4126904        2533614.        6920921.
 2531128.9973272 6916585.1880449
#Sta/Elev= 30
       0  399.97  154.07  383.94  1315.2     379 1420.76     390 2577.79     375
 2770.63  383.47 2921.88     376 3655.43     380  3783.3   347.1  3948.7     380
 4056.18  379.49    4294     378 4340.51  361.04 4436.22     375 4933.53     391
 5164.67  394.54 5255.79  379.31  5413.8     394 6650.11     395 7032.01     381
 7169.04  384.24 7235.04     398 7372.32     387 7505.62  394.75 7705.06     387
 7739.09  394.62 8034.02     392 8260.89     402 8491.55     391 8768.84     399
#Mann= 10 ,-1,0
       0     .03       0  154.07     .07       0 1420.76      .2       0
 3655.43    .055       0 4056.18      .2       0 4933.53     .18       0
 5164.67    .055       0  5413.8     .18       0 6650.11    .055       0
 7235.04     .18       0
#XS Ineff= 2 , 0
         3655.43     3804056.178          379.49
Permanent Ineff=
       F       F
Bank Sta=3655.43,4056.18
XS Rating Curve= 0 ,0
Exp/Cntr=0.3,0.1
Stream Node=Elm Fork        ,ef6             , 0 , 0 ,Upstream end
Stream Node=Elm Fork        ,ef6             , 0 , 1 ,Downstream end
Stream Node=Elm Fork        ,ef5             , 0 , 0 ,Upstream end
Stream Node=Elm Fork        ,ef5             , 0 , 1 ,Downstream end
Stream Node=Elm Fork        ,ef4             , 0 , 0 ,Upstream end
Stream Node=Elm Fork        ,ef4             , 0 , 1 ,Downstream end
Stream Node=Elm Fork        ,ef3             , 0 , 0 ,Upstream end
Stream Node=Elm Fork        ,ef3             , 0 , 1 ,Downstream end
Stream Node=Elm Fork        ,ef2             , 0 , 0 ,Upstream end
Stream Node=Elm Fork        ,ef2             , 0 , 1 ,Downstream end
Stream Node=Elm Fork        ,ef1             , 0 , 0 ,Upstream end
Stream Node=Elm Fork        ,ef1             , 0 , 1 ,Downstream end
Stream Node=Elm Fork L-Spill,efl             , 0 , 0 ,Upstream end
Stream Node=Elm Fork L-Spill,efl             , 0 , 1 ,Downstream end
Stream Node=Elm Fork Split1 ,efs1            , 0 , 0 ,Upstream end
Stream Node=Elm Fork Split1 ,efs1            , 0 , 1 ,Downstream end
Stream Node=Elm Fork Split2 ,efs2            , 0 , 0 ,Upstream end
Stream Node=Elm Fork Split2 ,efs2            , 0 , 1 ,Downstream end
Stream Node=Main Stem       ,ms              , 0 , 0 ,Upstream end
Stream Node=Main Stem       ,ms              , 0 , 1 ,Downstream end
Stream Node=West Fork       ,wf3             , 0 , 0 ,Upstream end
Stream Node=West Fork       ,wf3             , 0 , 1 ,Downstream end
Stream Node=West Fork       ,wf3f            , 0 , 0 ,Upstream end
Stream Node=West Fork       ,wf3f            , 0 , 1 ,Downstream end
Stream Node=West Fork       ,wf3e            , 0 , 0 ,Upstream end
Stream Node=West Fork       ,wf3e            , 0 , 1 ,Downstream end
Stream Node=West Fork       ,wf3d            , 0 , 0 ,Upstream end
Stream Node=West Fork       ,wf3d            , 0 , 1 ,Downstream end
Stream Node=West Fork       ,wf3b            , 0 , 0 ,Upstream end
Stream Node=West Fork       ,wf3b            , 0 , 1 ,Downstream end
Stream Node=West Fork       ,wf3c            , 0 , 0 ,Upstream end
Stream Node=West Fork       ,wf3c            , 0 , 1 ,Downstream end
Stream Node=West Fork       ,wf3a            , 0 , 0 ,Upstream end
Stream Node=West Fork       ,wf3a            , 0 , 1 ,Downstream end
Stream Node=West Fork       ,wf2             , 0 , 0 ,Upstream end
Stream Node=West Fork       ,wf2             , 0 , 1 ,Downstream end
Stream Node=West Fork       ,wf1             , 0 , 0 ,Upstream end
Stream Node=West Fork       ,wf1             , 0 , 1 ,Downstream end
Stream Node=West Fork Split ,wfs             , 0 , 0 ,Upstream end
Stream Node=West Fork Split ,wfs             , 0 , 1 ,Downstream end
LCMann Table=0

Chan Stop Cuts=-1
Use User Specified Reach Order=0
User Specified Reach Order=Main Stem       ,ms
User Specified Reach Order=West Fork Split ,wfs
User Specified Reach Order=Elm Fork Split1 ,efs1
User Specified Reach Order=West Fork       ,wf1
User Specified Reach Order=West Fork       ,wf2
User Specified Reach Order=West Fork       ,wf3
User Specified Reach Order=West Fork       ,wf4
User Specified Reach Order=Clear Fork      ,cf
User Specified Reach Order=Elm Fork Split2 ,efs2
User Specified Reach Order=Elm Fork        ,ef1
User Specified Reach Order=Elm Fork        ,ef2
User Specified Reach Order=Elm Fork        ,ef3
User Specified Reach Order=Elm Fork        ,ef4
User Specified Reach Order=Elm Fork        ,ef5
User Specified Reach Order=Elm Fork        ,ef6
User Specified Reach Order=Elm Fork L-Spill,efl
Composite Channel Slope=5

--- CDC_Consolidated_Model.g13 (geometry) ---

Geom Title=CDC: 0.2% AEP, SPF [WF/EF/TRMS]
Program Version=6.10
BEGIN GEOM DESCRIPTION:
CDC: Geometry file for use with 0.2% AEP and SPF peak flows for the WF/EF/TRMS
END GEOM DESCRIPTION:

Junct Name=ef-wf
Junct Desc=, 0 , 0 , 0 ,0
Up River,Reach=Elm Fork        ,ef3 ds
Up River,Reach=West Fork       ,wf
Dn River,Reach=Main Stem       ,ms
Junc L&A=3087.05,20
Junc L&A=1493.66,0

Junct Name=J2
Junct Desc=, 0 , 0 ,-1 ,0
Up River,Reach=Elm Fork        ,ef3
Dn River,Reach=Elm Fork        ,PGBT split west
Dn River,Reach=Elm Fork        ,PGBT split east
Junc L&A=616.31,0
Junc L&A=1108.43,0

Junct Name=J1
Junct Desc=, 0 , 0 ,-1 ,0
Up River,Reach=Elm Fork        ,PGBT split west
Up River,Reach=Elm Fork        ,PGBT split east
Dn River,Reach=Elm Fork        ,ef3 ds
Junc L&A=1066.66,0
Junc L&A=4395.74,0

Junct Name=Junction 1
Junct Desc=, 0 , 0 ,-1 ,0
Up River,Reach=Elm Fork L-Spill,efl
Up River,Reach=Elm Fork        ,ef6
Dn River,Reach=Elm Fork        ,ef4
Junc L&A=374.09,0
Junc L&A=622.83,0

Junct Name=ef4-efs2-ef3
Junct Desc=, 0 , 0 ,-1 ,0
Up River,Reach=Elm Fork Split2 ,efs2
Up River,Reach=Elm Fork        ,ef4
Dn River,Reach=Elm Fork        ,ef3
Junc L&A=971.04,
Junc L&A=264.86,

River Reach=Elm Fork L-Spill,efl
Reach XY= 30
2451731.022068587074640.456710862451151.760795647070662.98039573
2450845.225647557070288.502470152449714.250875387069831.48435532
2449387.497591887069340.52077031 2448346.99147087068965.47886948
2447272.27478822 7069420.97369342446497.765510477069465.51592715
 2446113.51168587069771.989395562445393.744752637069849.51647148
2443355.478816057069500.97779848 2442726.48105837069038.01514173
2442454.769987557069151.490964652441886.481097897069033.51711923
2441561.260947817069254.480916142440898.257024477068922.50060898
2440879.515264057068708.496115732440653.739468897068824.97849432
2440507.483855897068577.01967265 2441236.50569187068363.49910231
2441162.515026147068102.508482562440921.991228977067994.97917005
2441144.259485217067848.496851472440883.522801977067770.49897598
2440922.248774387067434.980290062440639.514103647067360.99060865
2440463.728694057067616.486160652440310.519026737067421.98031606
2439948.019095557067322.49101372 2439781.73808557066985.48846395

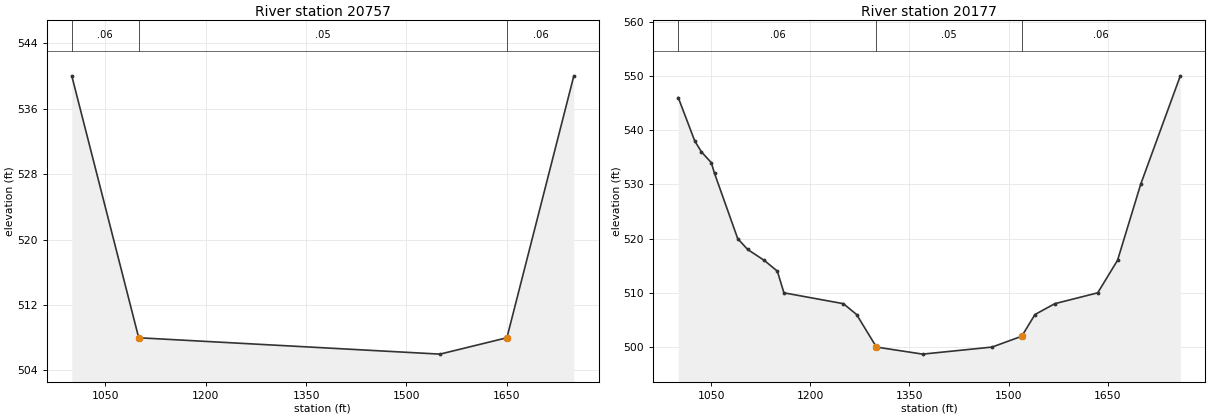
Type RM Length L Ch R = 1 ,20757   ,580,580,580
BEGIN DESCRIPTION:
15590
Cross-section surveyed December 1990.
END DESCRIPTION:
XS GIS Cut Line= 2
2452120.868883627074470.158571182451373.760863037074518.00828429
#Sta/Elev= 5
    1000     540    1100     508    1550     506    1650     508    1750     540
#Mann= 3 ,0,0
    1000     .06       0    1100     .05       0    1650     .06       0
Bank Sta=1100,1650
XS Rating Curve= 0 ,0
Exp/Cntr=0.3,0.1

Type RM Length L Ch R = 1 ,20177   ,1430,1430,1430
BEGIN DESCRIPTION:
15010
Cross-section surveyed December 1990.
END DESCRIPTION:
XS GIS Cut Line= 2
2452072.513160077073925.240004622451317.245406937073990.14582716
#Sta/Elev= 22
    1000     546    1025     538    1035     536    1050     534    1055     532
    1090     520    1105     518    1130     516    1150     514    1160     510
    1250     508    1270     506    1300     500    1370   498.7    1475     500
    1520     502    1540     506    1570     508    1635     510    1665     516
    1700     530    1760     550
#Mann= 3 ,0,0
    1000     .06       0    1300     .05       0    1520     .06       0
Bank Sta=1300,1520
XS Rating Curve= 0 ,0
Exp/Cntr=0.3,0.1