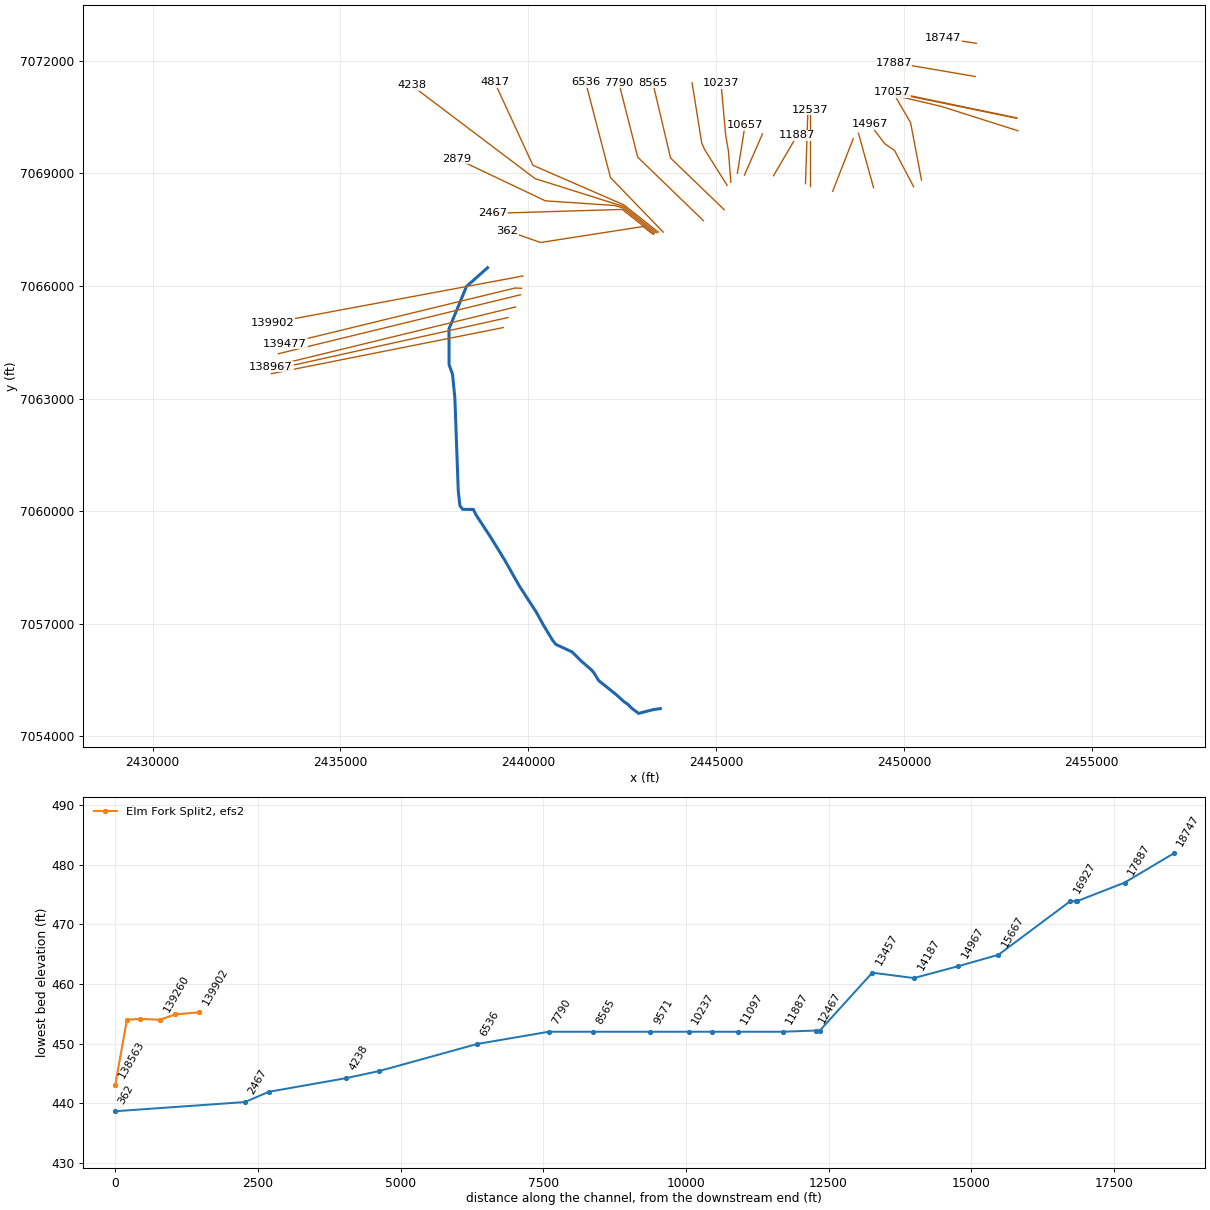
HEC-RAS study CDC_Consolidated_Model.prj: Upper Trinity CDC Consolidated Model

--- CDC_Consolidated_Model.g13 (geometry) --- (continued)

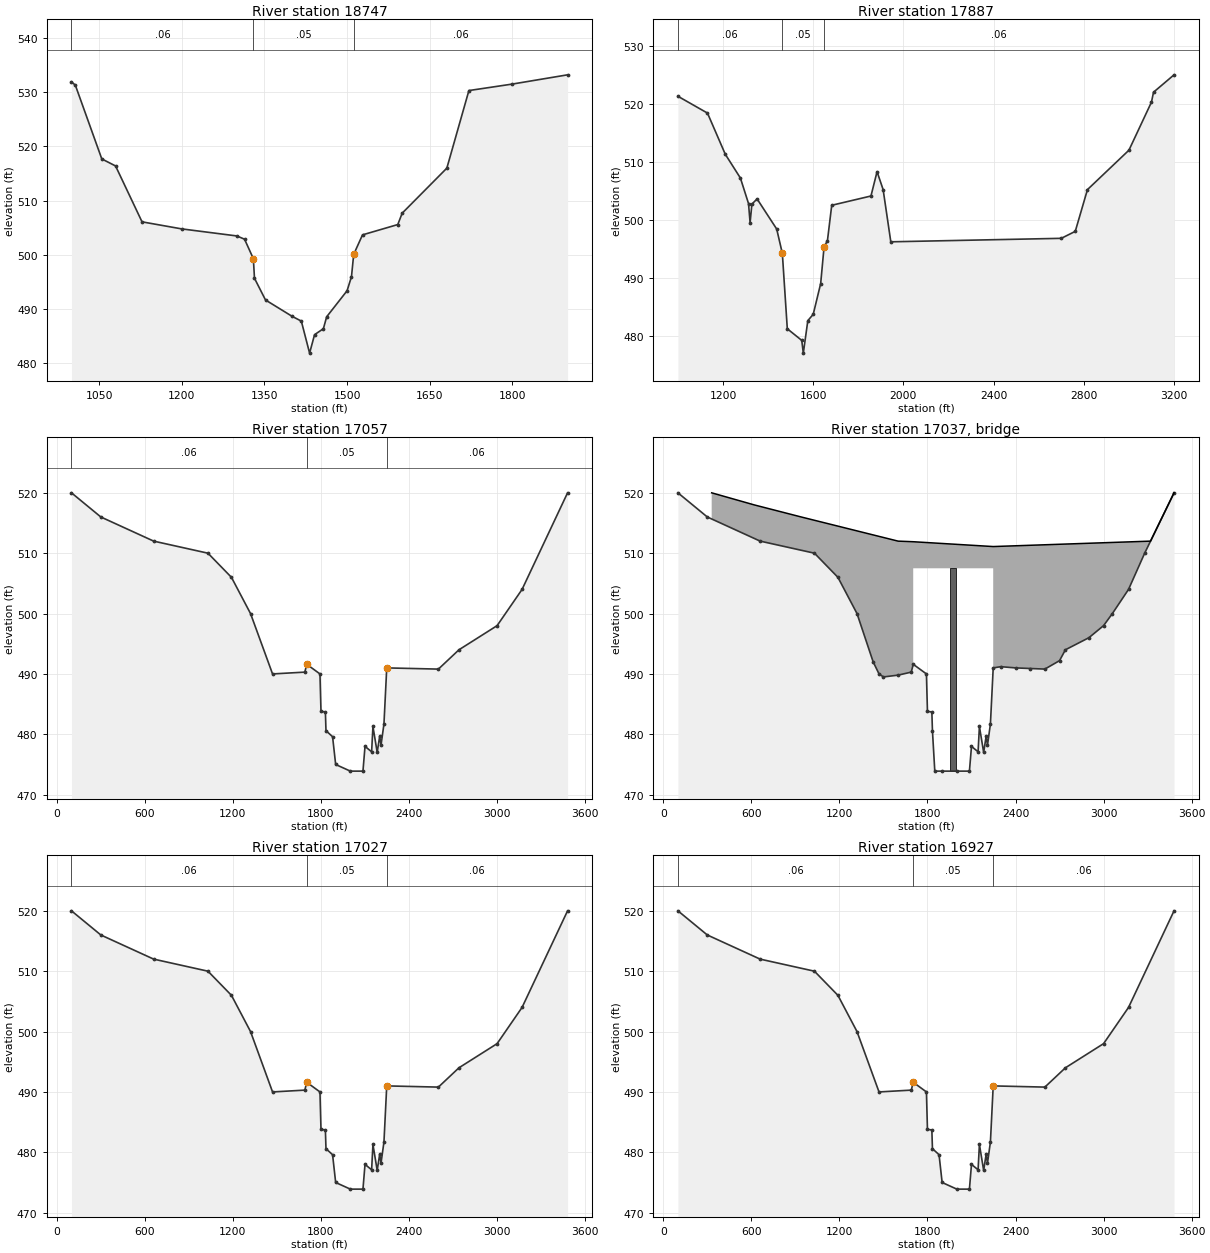
Type RM Length L Ch R = 1 ,18747   ,850,860,870
BEGIN DESCRIPTION:
13580
Cross-section surveyed December 1990.
END DESCRIPTION:
XS GIS Cut Line= 2
2451926.207545137072464.820604362451032.287904787072596.40731541
#Sta/Elev= 27
    1000   531.9    1007   531.3    1055   517.7    1080   516.4    1128   506.1
    1200   504.8    1300   503.5    1314   502.9    1330   499.3    1332   495.7
    1352   491.7    1400   488.7    1417   487.8    1432   481.9    1441   485.3
    1457   486.4    1463   488.6    1500   493.4    1508     496    1512   500.1
    1528   503.7    1592   505.6    1600   507.7    1681     516    1721   530.3
    1800   531.5    1900   533.2
#Mann= 3 ,0,0
    1000     .06       0    1330     .05       0    1512     .06       0
Bank Sta=1330,1512
XS Rating Curve= 0 ,0
Exp/Cntr=0.3,0.1

Type RM Length L Ch R = 1 ,17887   ,820,830,840
BEGIN DESCRIPTION:
12720
Cross-section surveyed December 1990.
END DESCRIPTION:
XS GIS Cut Line= 2
2451898.447547427071579.779564592449727.052757157071951.51291184
#Sta/Elev= 30
    1000   521.3    1131   518.4    1210   511.3    1277   507.2    1313   502.8
    1320   499.5    1328   502.7    1351   503.6    1438   498.4    1463   494.2
    1485   481.2    1549   479.2    1556     477    1576   482.6    1600   483.7
    1633     489    1648   495.3    1663   496.4    1682   502.5    1856   504.1
    1883   508.3    1910   505.2    1944   496.2    2700   496.8    2762     498
    2816   505.2    3000     512    3100   520.3    3109     522    3200     525
#Mann= 3 ,0,0
    1000     .06       0    1463     .05       0    1648     .06       0
Bank Sta=1463,1648
XS Rating Curve= 0 ,0
Exp/Cntr=0.5,0.3

Type RM Length L Ch R = 1 ,17057   ,20,20,20
BEGIN DESCRIPTION:
11890
Cross-section surveyed December 1990.
END DESCRIPTION:
XS GIS Cut Line= 2
2453005.220931317070476.516030742449684.912676077071167.76417064
#Sta/Elev= 30
     100     520     300     516     660     512    1030     510    1190     506
    1320     500    1470     490    1690   490.3    1703   491.6    1793     490
    1800   483.8    1830   483.7    1834   480.6    1879   479.6    1900     475
    2000   473.9    2086   473.9    2100     478    2145   477.1    2154   481.3
    2183     477    2200   479.7    2209   478.2    2229   481.7    2248     491
    2600   490.8    2740     494    3000     498    3170     504    3480     520
#Mann= 3 ,0,0
     100     .06       0    1703     .05       0    2248     .06       0
#XS Ineff= 2 , 0
            1703            2248
Permanent Ineff=
       F       F
Bank Sta=1703,2248
XS Rating Curve= 0 ,0
Exp/Cntr=0.5,0.3

Type RM Length L Ch R = 3 ,17037   ,,,
BEGIN DESCRIPTION:
Atchinson, Topeka, and Sante Fe Railroad
END DESCRIPTION:
Node Name=ATSF Railroad
Bridge Culvert--1,0,-1,-1, 0
Deck Dist Width WeirC Skew NumUp NumDn MinLoCord MaxHiCord MaxSubmerge Is_Ogee
1,18,2.7,0, 10, 10, 511.1, , 0.95, 0, 0,0,,
     330     620     940    1600    1703    1703    2248    2248    3320    3480
     520     518     516     512   511.9   511.9   511.1   511.1     512     520
   473.9   473.9   473.9   473.9   473.9   507.5   507.5   473.9   473.9   473.9
     330     620     940    1600    1703    1703    2248    2248    3320    3480
     520     518     516     512   511.9   511.9   511.1   511.1     512     520
   473.9   473.9   473.9   473.9   473.9   507.5   507.5   473.9   473.9   473.9
Pier Skew, UpSta & Num, DnSta & Num=  ,1975.5, 2 ,1975.5, 2 , 0 , 0 , 0 ,,
      38      38
   473.9   507.5
      38      38
   473.9   507.5
Abutment Skew #Up #Dn= , 2 , 2
    1703    1898
   507.5   473.9
    1703    1898
   507.5   473.9
Abutment Skew #Up #Dn= , 2 , 2
    2053    2248
   473.9   507.5
    2053    2248
   473.9   507.5
BR Coef= 0 , 0 ,-1 ,1.05, 0 ,,,0.7905694,0,2,2,507.5
WSPro=,,,, 1 ,,,, 0 ,,,, 0 ,,,,-1 ,-1 ,-1 , 0 , 0 , 0 , 0 , 0
BR U #Sta/Elev= 40
     100     520     300     516     660     512    1030     510    1190     506
    1320     500    1430     492    1470     490    1500   489.5    1600   489.8
    1690   490.3    1703   491.6    1793     490    1800   483.8    1830   483.7
    1834   480.6    1850   473.9    1900   473.9    2000   473.9    2086   473.9
    2100     478    2145   477.1    2154   481.3    2183     477    2200   479.7
    2209   478.2    2229   481.7    2248     491    2300   491.2    2400     491
    2500   490.9    2600   490.8    2700   492.2    2740     494    2900     496
    3000     498    3060     500    3170     504    3280     510    3480     520
BR U #Mann= 3
     100     .06    1703     .05    2248     .06
BR D #Sta/Elev= 40
     100     520     300     516     660     512    1030     510    1190     506
    1320     500    1430     492    1470     490    1500   489.5    1600   489.8
    1690   490.3    1703   491.6    1793     490    1800   483.8    1830   483.7
    1834   480.6    1850   473.9    1900   473.9    2000   473.9    2086   473.9
    2100     478    2145   477.1    2154   481.3    2183     477    2200   479.7
    2209   478.2    2229   481.7    2248     491    2300   491.2    2400     491
    2500   490.9    2600   490.8    2700   492.2    2740     494    2900     496
    3000     498    3060     500    3170     504    3280     510    3480     520
BR D #Mann= 3
     100     .06    1703     .05    2248     .06
BC Design=,, 0 ,, 0 ,,,,,,
BC HTab HWMax=520
BC Use User HTab Curves=0
BC User HTab FreeFlow(D)= 0

Type RM Length L Ch R = 1 ,17027   ,100,100,100
BEGIN DESCRIPTION:
11870
Cross-section surveyed December 1990.
END DESCRIPTION:
XS GIS Cut Line= 2
2453002.391998887070466.669530612449681.868435297071151.76130327
#Sta/Elev= 30
     100     520     300     516     660     512    1030     510    1190     506
    1320     500    1470     490    1690   490.3    1703   491.6    1793     490
    1800   483.8    1830   483.7    1834   480.6    1879   479.6    1900     475
    2000   473.9    2086   473.9    2100     478    2145   477.1    2154   481.3
    2183     477    2200   479.7    2209   478.2    2229   481.7    2248     491
    2600   490.8    2740     494    3000     498    3170     504    3480     520
#Mann= 3 ,0,0
     100     .06       0    1703     .05       0    2248     .06       0
#XS Ineff= 2 , 0
            1703            2248
Permanent Ineff=
       F       F
Bank Sta=1703,2248
XS Rating Curve= 0 ,0
Exp/Cntr=0.5,0.3

Type RM Length L Ch R = 1 ,16927   ,1300,1260,1200
BEGIN DESCRIPTION:
11770
Cross-section surveyed December 1990.
END DESCRIPTION:
XS GIS Cut Line= 3
2453034.299441227070134.149864012450996.779024987070782.72190619
2449803.759637757071063.48323213
#Sta/Elev= 30
     100     520     300     516     660     512    1030     510    1190     506
    1320     500    1470     490    1690   490.3    1703   491.6    1793     490
    1800   483.8    1830   483.7    1834   480.6    1879   479.6    1900     475
    2000   473.9    2086   473.9    2100     478    2145   477.1    2154   481.3
    2183     477    2200   479.7    2209   478.2    2229   481.7    2248     491
    2600   490.8    2740     494    3000     498    3170     504    3480     520
#Mann= 3 ,0,0
     100     .06       0    1703     .05       0    2248     .06       0
Bank Sta=1703,2248
XS Rating Curve= 0 ,0
Exp/Cntr=0.5,0.3

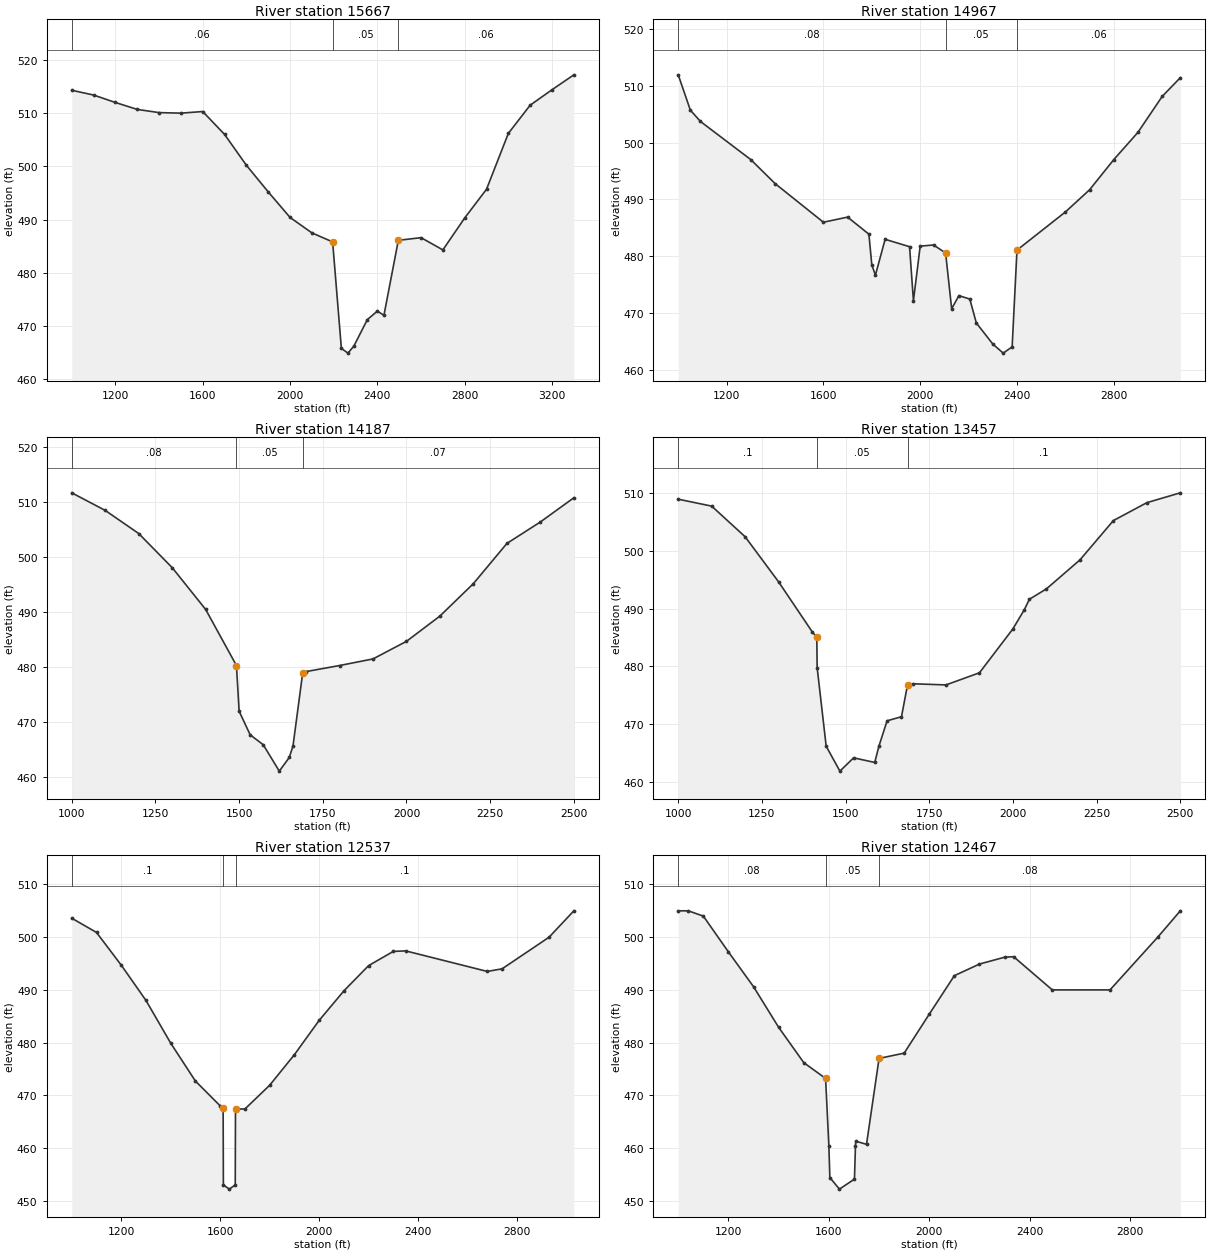
Type RM Length L Ch R = 1 ,15667   ,850,700,720
BEGIN DESCRIPTION:
10510
Cross-section surveyed December 1990.
END DESCRIPTION:
XS GIS Cut Line= 3
2450467.569171527068821.282054892450178.183611567070348.32479818
 2449800.80935827070998.57737448
#Sta/Elev= 28
    1000   514.3    1100   513.4    1200     512    1300   510.7    1400   510.1
    1500     510    1600   510.3    1700     506    1800   500.2    1900   495.2
    2000   490.4    2100   487.5    2195   485.8    2235   465.8    2265   464.9
    2292   466.2    2354   471.2    2400   472.8    2430     472    2496   486.1
    2600   486.6    2700   484.3    2800   490.3    2900   495.7    3000   506.2
    3100   511.5    3200   514.4    3300   517.2
#Mann= 3 ,0,0
    1000     .06       0    2195     .05       0    2496     .06       0
Bank Sta=2195,2496
XS Rating Curve= 0 ,0
Exp/Cntr=0.3,0.1

Type RM Length L Ch R = 1 ,14967   ,900,780,500
BEGIN DESCRIPTION:
9810
Cross-section surveyed December 1990.
END DESCRIPTION:
XS GIS Cut Line= 5
2450258.700186657068643.290745942449750.048614747069611.26457518
 2449619.93817767069699.869565582449489.827740477069788.47455597
2449091.737719527070315.60450099
#Sta/Elev= 30
    1000   511.9    1050   505.7    1092   503.7    1300     497    1400   492.8
    1600     486    1700   486.9    1788   483.9    1800   478.5    1815   476.7
    1855     483    1956   481.7    1972   472.2    2000   481.8    2055     482
    2105   480.6    2130   470.8    2160   473.1    2205   472.5    2232   468.3
    2300   464.6    2343     463    2380   464.1    2400   481.1    2600   487.8
    2700   491.7    2800     497    2900   501.8    3000   508.1    3075   511.4
#Mann= 3 ,0,0
    1000     .08       0    2105     .05       0    2400     .06       0
Bank Sta=2105,2400
XS Rating Curve= 0 ,0
Exp/Cntr=0.3,0.1

Type RM Length L Ch R = 1 ,14187   ,800,730,550
BEGIN DESCRIPTION:
9030
Cross-section surveyed December 1990.
END DESCRIPTION:
XS GIS Cut Line= 2
2449192.25447184 7068616.56966822448790.615445067070066.38859415
#Sta/Elev= 22
    1000   511.6    1100   508.4    1200   504.2    1300     498    1400   490.4
    1492   480.2    1500   471.9    1533   467.6    1572   465.8    1620     461
    1650   463.5    1661   465.6    1690   478.9    1700   479.1    1800   480.2
    1900   481.4    2000   484.6    2100   489.2    2200   495.1    2300   502.4
    2400   506.3    2500   510.7
#Mann= 3 ,0,0
    1000     .08       0    1492     .05       0    1690     .07       0
Bank Sta=1492,1690
XS Rating Curve= 0 ,0
Exp/Cntr=0.3,0.1

Type RM Length L Ch R = 1 ,13457   ,910,920,980
BEGIN DESCRIPTION:
8300
Cross-section surveyed December 1990.
END DESCRIPTION:
XS GIS Cut Line= 2
2448104.407189687068523.305319532448650.20615191 7069921.7307687
#Sta/Elev= 26
    1000   508.9    1100   507.7    1200   502.4    1300   494.6    1400     486
    1414     485    1415   479.8    1442   466.2    1483   461.9    1524   464.2
    1587   463.4    1600   466.3    1624   470.6    1667   471.3    1685   476.8
    1700     477    1800   476.8    1900   478.9    2000   486.5    2034   489.8
    2049   491.6    2100   493.4    2200   498.4    2300   505.2    2400   508.3
    2500     510
#Mann= 3 ,0,0
    1000      .1       0    1414     .05       0    1685      .1       0
Bank Sta=1414,1685
XS Rating Curve= 0 ,0
Exp/Cntr=0.3,0.1

Type RM Length L Ch R = 1 ,12537   ,70,70,70
BEGIN DESCRIPTION:
7380-US of Hatchery Road
Cross-section surveyed December 1990.
END DESCRIPTION:
XS GIS Cut Line= 2
2447490.752159517068664.918032652447490.752159517070697.65038387
#Sta/Elev= 24
    1000   503.6    1100   500.9    1200   494.7    1300     488    1400   479.9
    1500   472.7    1600     468    1612   467.5    1613     453    1637   452.2
    1661     453    1662   467.4    1700   467.4    1800   471.9    1900   477.7
    2000   484.2    2100   489.8    2200   494.6    2300   497.3    2350   497.4
    2680   493.5    2740     494    2930     500    3030     505
#Mann= 3 ,0,0
    1000      .1       0    1612     .05       0    1662      .1       0
Bank Sta=1612,1662
XS Rating Curve= 0 ,0
Exp/Cntr=0.3,0.1

Type RM Length L Ch R = 1 ,12467   ,580,580,580
BEGIN DESCRIPTION:
7310-DS Hatchery Road
Cross-section surveyed December 1990.
END DESCRIPTION:
XS GIS Cut Line= 2
2447379.862883547068724.975605792447446.214549237070729.65223046
#Sta/Elev= 26
    1000     505    1040     505    1100     504    1200   497.2    1300   490.6
    1400   482.9    1500   476.2    1587   473.2    1600   460.4    1604   454.4
    1642   452.2    1702   454.1    1706   460.4    1707   461.3    1750   460.7
    1800     477    1900     478    2000   485.4    2100   492.7    2200   494.9
    2300   496.2    2336   496.3    2490     490    2720     490    2910     500
    3000     505
#Mann= 3 ,0,0
    1000     .08       0    1587     .05       0    1800     .08       0
Bank Sta=1587,1800
XS Rating Curve= 0 ,0
Exp/Cntr=0.3,0.1

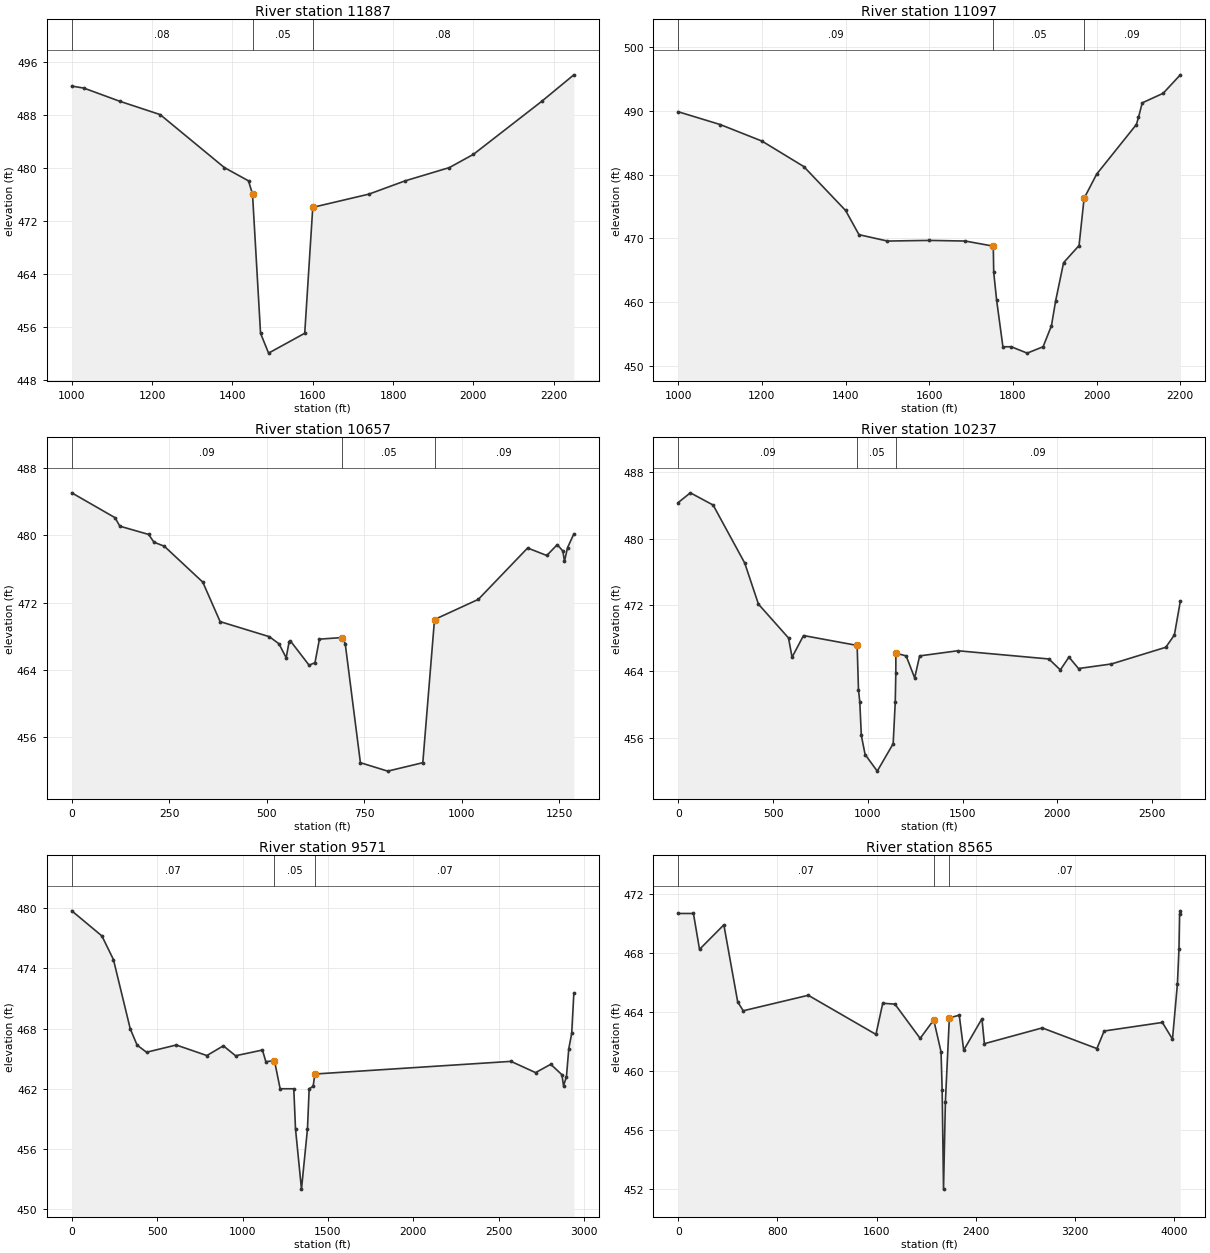
Type RM Length L Ch R = 1 ,11887   ,650,790,670
BEGIN DESCRIPTION:
6730
Cross-section surveyed December 1990.
END DESCRIPTION:
XS GIS Cut Line= 2
2446529.696861847068937.086467862447160.54669862 7070013.1020385
#Sta/Elev= 17
    1000   492.3    1030     492    1120     490    1220     488    1380     480
    1440     478    1450     476    1470     455    1490     452    1580     455
    1600     474    1740     476    1830     478    1940     480    2000     482
    2170     490    2250     494
#Mann= 3 ,0,0
    1000     .08       0    1450     .05       0    1600     .08       0
Bank Sta=1450,1600
XS Rating Curve= 0 ,0
Exp/Cntr=0.3,0.1

Type RM Length L Ch R = 1 ,11097   ,420,440,360
BEGIN DESCRIPTION:
5940
Cross-section surveyed December 1990.
END DESCRIPTION:
XS GIS Cut Line= 2
2445755.996541657068954.043972422446233.939416687070048.59216154
#Sta/Elev= 27
    1000   489.9    1100   487.9    1200   485.3    1300   481.3    1400   474.4
    1432   470.6    1500   469.6    1600   469.7    1686   469.6    1753   468.8
    1754   464.7    1761   460.3    1776     453    1796     453    1834     452
    1872     453    1892   456.3    1902   460.2    1921   466.2    1958   468.9
    1970   476.3    2000   480.1    2095   487.9    2100     489    2109   491.3
    2159   492.8    2200   495.7
#Mann= 3 ,0,0
    1000     .09       0    1753     .05       0    1970     .09       0
Bank Sta=1753,1970
XS Rating Curve= 0 ,0
Exp/Cntr=0.3,0.1

Type RM Length L Ch R = 1 ,10657   ,304.15,420,1021.26
BEGIN DESCRIPTION:
5500-Begin Modifications to CDC model- Left and Right Overbank from 2009 Lidar. Channel from CDC
Cross-section surveyed December 1990.
END DESCRIPTION:
XS GIS Cut Line= 2
2445567.948472477069006.122817052445770.296492967070277.34468406
#Sta/Elev= 30
       0  485.04   110.9  482.09  123.25  481.08  197.06   480.1  210.69  479.18
  237.26   478.7  335.88  474.44  380.34  469.75  506.61  467.96  531.17  467.12
  549.72  465.46  557.26  467.36  560.72  467.45  608.54  464.57  623.55  464.88
  634.95  467.67     694  467.86  701.06  467.14     740     453     810     452
     900     453     930     470  1042.3  472.39 1168.72  478.49 1217.84   477.6
 1244.74  478.89 1259.01  478.13 1263.26  476.92 1271.12  478.54 1287.23  480.16
#Mann= 3 ,0,0
       0     .09       0     694     .05       0     930     .09       0
Bank Sta=694,930
XS Rating Curve= 0 ,0
Exp/Cntr=0.3,0.1

Type RM Length L Ch R = 1 ,10237   ,396.53,666.47,997.49
BEGIN DESCRIPTION:
5080-Left and Right Overbank from 2009 Lidar. Channel from CDC
Cross-section surveyed December 1990.
END DESCRIPTION:
XS GIS Cut Line= 5
2445393.113848397068759.326394652445329.388582147069593.05471405
2445292.348629977069806.780008392445255.308677817070020.50530273
 2445131.87191687071394.02814622
#Sta/Elev= 30
       0  484.33      64   485.5  184.07  484.03  350.75  477.05  423.19   472.1
  581.88  468.03   600.5  465.71  660.99  468.32  943.94  467.13     951   461.8
     958   460.3     966   456.3     986     454    1050     452    1134   455.3
    1145   460.3    1148   463.8 1148.29   466.2  1202.6  465.87 1247.46  463.22
 1273.69  465.87 1475.27  466.49 1955.77   465.5 2015.89  464.18 2061.47  465.73
 2111.88  464.35 2285.95   464.9 2572.59  466.91 2617.76  468.39 2649.04  472.45
#Mann= 3 ,0,0
       0     .09       0  943.94     .05       0 1148.29     .09       0
Bank Sta=943.94,1148.29
XS Rating Curve= 0 ,0
Exp/Cntr=0.3,0.1

Type RM Length L Ch R = 1 ,9571    ,615.14,1005.99,1028.41
BEGIN DESCRIPTION:
4420-Left and Right Overbank from 2009 Lidar. Channel from CDC
Cross-section surveyed December 1990.
END DESCRIPTION:
XS GIS Cut Line= 5
2445294.949018467068679.712380652444703.886880387069620.22362298
2444661.151401557069713.059067232444618.415922727069805.89451148
2444361.382972237071409.92936115
#Sta/Elev= 30
       0  479.73  176.25  477.23   243.9  474.88  342.26  467.98  382.53  466.35
  437.79  465.64   611.7  466.36   791.1  465.31  887.48  466.28  959.12  465.29
 1116.39  465.86 1136.34   464.7 1186.79   464.8    1220     462    1300     462
    1310     458    1345     452    1380     458    1390     462 1413.26  462.24
 1423.24  463.47 2571.71  464.73  2715.7  463.61  2804.5  464.44 2869.99   463.4
  2879.3   462.3 2896.35   463.2 2910.13     466 2927.06  467.51 2939.71  471.51
#Mann= 3 ,0,0
       0     .07       0 1186.79     .05       0 1423.24     .07       0
Bank Sta=1186.79,1423.24
XS Rating Curve= 0 ,0
Exp/Cntr=0.3,0.1

Type RM Length L Ch R = 1 ,8565    ,594.36,775.32,900.2
BEGIN DESCRIPTION:
CDC XSEC 3500
Lewisville Lake Spillway Reach
This reach represents discharge from Lewisville Lake uncontrolled spillway for rare flood events: 50 year, 100 year, 500 year. During these rare events the Lewisville Lake outlet works are closed per normal lake regulation plan for flood control.  10-year flood event not considered since no flow occurs.  Cross-section river stations from this point upstream represent distance from McWhorter Creek/Stewart Creek confluence. Cross-section surveyed December 1990.
END DESCRIPTION:
XS GIS Cut Line= 3
2445217.867807817068030.068338722443789.137069467069407.23061064
2443314.35685106 7071417.6170098
#Sta/Elev= 30
       0  470.67  122.58  470.67  171.74  468.24  367.93   469.9  479.73  464.68
   524.2  464.08 1048.93  465.13 1594.89  462.48 1649.75  464.59  1748.1  464.53
 1951.41  462.21 2061.04  463.46    2120   461.3    2129   458.7    2140     452
    2155   457.9    2187   463.6 2266.97  463.78 2302.74  461.41 2449.91  463.54
 2469.82  461.85 2936.25  462.92 3377.23  461.52 3435.57  462.71 3905.29  463.29
 3986.95  462.16 4026.87  465.91 4039.26  468.29 4044.34  470.63 4050.09  470.85
#Mann= 3 ,0,0
       0     .07       0 2061.04     .05       0    2187     .07       0
Bank Sta=2061.04,2187
XS Rating Curve= 0 ,0
Exp/Cntr=0.3,0.1

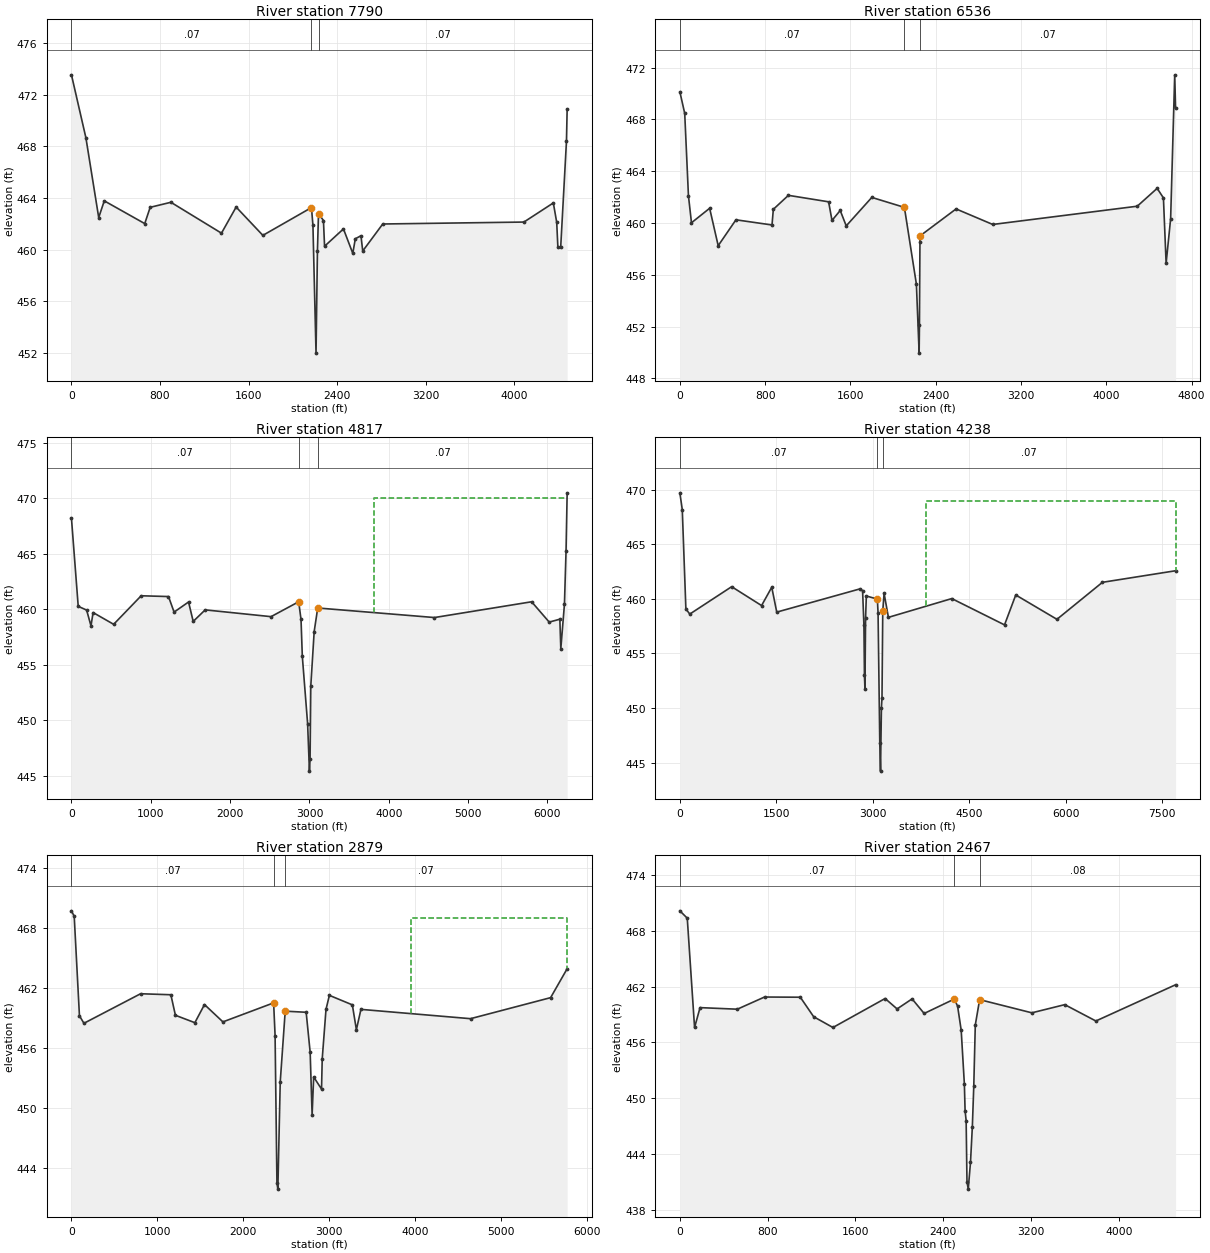
Type RM Length L Ch R = 1 ,7790    ,1034.7,1253.62,878.94
BEGIN DESCRIPTION:
Lidar XS
END DESCRIPTION:
XS GIS Cut Line= 3
2444660.142217227067741.439650892442915.350431227069429.80799331
2442410.142124067071418.08912173
#Sta/Elev= 30
       0  473.53  130.56  468.66  246.32  462.49  296.65  463.78   662.3  462.02
  711.41  463.28  898.62  463.67 1355.66  461.28 1488.12   463.3 1729.71  461.11
 2168.85  463.26  2182.2  461.88 2210.06     452 2222.84  459.93 2232.48   462.8
  2277.1  462.26 2287.27  460.27 2457.89  461.61 2542.28  459.72 2565.21  460.85
 2616.14  461.08 2632.12   459.9 2812.94  461.99 4088.64  462.14  4354.5  463.62
    4385  462.12 4395.54  460.19 4420.92  460.18 4473.06  468.38  4479.4  470.89
#Mann= 3 ,0,0
       0     .07       0 2168.85     .05       0 2232.48     .07       0
Bank Sta=2168.85,2232.48
XS Rating Curve= 0 ,0
Exp/Cntr=0.3,0.1

Type RM Length L Ch R = 1 ,6536    ,147.91,1718.61,2375.96
BEGIN DESCRIPTION:
Lidar XS
END DESCRIPTION:
XS GIS Cut Line= 3
2443592.838905637067434.640067642442189.627145147068886.46295139
2441526.432605397071431.60188998
#Sta/Elev= 30
       0  470.14   45.58  468.47   80.49  462.11  108.89  460.02  279.28  461.14
  359.53  458.25  526.02  460.25  864.26  459.85  876.69  461.06 1018.01  462.14
 1395.15  461.64 1426.83   460.2 1504.03  460.97 1560.38  459.78 1800.29  461.98
 2105.94  461.21 2218.43  455.28  2244.2  449.95 2247.11  452.14 2251.81  458.57
  2256.5  459.03 2590.65  461.09 2934.37  459.89 4290.04   461.3 4476.59  462.68
  4535.4  461.94 4560.63  456.89 4602.96  460.33 4641.22  471.45 4649.23   468.9
#Mann= 3 ,0,0
       0     .07       0 2105.94     .05       0  2256.5     .07       0
Bank Sta=2105.94,2256.5
XS Rating Curve= 0 ,0
Exp/Cntr=0.3,0.1

Type RM Length L Ch R = 1 ,4817    ,47.76,578.54,1233.78
XS GIS Cut Line= 4
2443463.529781067067432.594468062442543.960425977068160.43520398
2440124.493152057069214.871415322439104.701556477071427.71869564
#Sta/Elev= 30
       0  468.18    85.3  460.25  191.33  459.91  246.22  458.49  272.81  459.69
  531.95  458.63  878.82   461.2  1223.3  461.13 1293.81  459.73 1476.17  460.64
 1534.72  458.89 1685.65  459.93 2515.91  459.32 2864.28  460.66 2893.81  459.07
 2910.13  455.75 2977.01  449.67 2999.92  445.41 3007.93  446.51  3016.8  453.06
 3059.57  457.97 3104.25   460.1 4575.75  459.24 5800.69  460.66 6022.21  458.83
 6156.35  459.09 6168.58  456.43 6214.27  460.43  6234.5  465.23 6248.54  470.47
#Mann= 3 ,0,0
       0     .07       0 2864.28     .05       0 3104.25     .07       0
#XS Ineff= 2 , 0
                            3810             470
Permanent Ineff=
       F       F
Bank Sta=2864.28,3104.25
XS Rating Curve= 0 ,0
Exp/Cntr=0.3,0.1

Type RM Length L Ch R = 1 ,4238    ,46.19,1359.12,642.17
XS GIS Cut Line= 4
2443414.976400467067417.849090732442530.553956727068120.00746331
2440182.504847057068859.156903642436895.845409897071343.32352322
#Sta/Elev= 30
       0  469.72    37.6  468.18   93.74  459.08  154.41  458.61  805.93  461.12
  1271.1  459.39  1429.4  461.07 1507.23  458.79 2802.53  460.92 2842.51  460.76
 2863.11  457.59 2871.14  453.03  2878.8  451.78 2888.93  458.23 2900.54  460.27
 3072.41  459.98 3083.17  458.69 3109.89  446.76 3121.25  444.22 3135.25     450
 3144.23  450.94 3156.09  458.88 3176.75  460.51 3243.97  458.31 4229.76  460.03
  5050.2  457.62 5224.88  460.36 5865.72  458.13 6572.79  461.52 7710.76  462.58
#Mann= 3 ,0,0
       0     .07       0 3072.41     .05       0 3156.09     .07       0
#XS Ineff= 2 , 0
                            3835             469
Permanent Ineff=
       F       F
Bank Sta=3072.41,3156.09
XS Rating Curve= 0 ,0
Exp/Cntr=0.3,0.1

Type RM Length L Ch R = 1 ,2879    ,46.29,412.15,979.16
XS GIS Cut Line= 5
2443361.644158057067409.265774562442517.147815567068079.57939456
2442293.931070397068144.325984222440457.132906727068267.35854656
2438094.072016067069389.88845372
#Sta/Elev= 30
       0  469.71   32.21  469.16   93.01  459.23  145.11  458.48  804.36  461.43
 1156.65  461.33 1209.66  459.28 1435.92  458.54 1547.87  460.35 1762.42  458.62
 2352.42  460.52 2369.32  457.26 2390.87  442.55  2401.5  441.92 2429.24  452.63
 2487.05  459.69 2730.98  459.58 2777.36  455.59 2800.18  449.34 2818.28  453.12
 2909.73  451.91 2917.75  454.93 2961.77  459.87 3000.96  461.27 3268.26  460.32
 3315.25  457.84 3368.24  459.87 4643.13  458.94 5575.12  461.04 5767.65  463.93
#Mann= 3 ,0,0
       0     .07       0 2352.42     .05       0 2487.05     .07       0
#XS Ineff= 2 , 0
                            3955             469
Permanent Ineff=
       F       F
Bank Sta=2352.42,2487.05
XS Rating Curve= 0 ,0
Exp/Cntr=0.3,0.1

Type RM Length L Ch R = 1 ,2467    ,11.57,2275.95,600.03
XS GIS Cut Line= 3
2443336.776097557067377.93578473 2442503.7413463 7068039.1516539
2439052.336831817067933.80081473
#Sta/Elev= 30
       0  470.17    67.4  469.38  134.06  457.61  184.01  459.75  523.57  459.58
  771.28  460.89 1097.46  460.87 1219.06  458.77 1394.76  457.61  1870.1  460.73
 1979.35  459.61  2115.9  460.69 2225.87  459.12 2500.28  460.67 2530.53  459.91
 2563.33  457.32 2592.39   451.5 2598.83  448.65 2608.48  447.59 2616.02     441
 2627.58  440.21 2648.01  443.08 2664.82  446.89 2677.98   451.3 2691.82  457.88
 2731.35  460.61 3207.07  459.19 3507.01  460.07 3790.43  458.31 4516.57  462.21
#Mann= 3 ,0,0
       0     .07       0 2500.28     .05       0 2731.35     .08       0
Bank Sta=2500.28,2731.35
XS Rating Curve= 0 ,0
Exp/Cntr=0.3,0.1

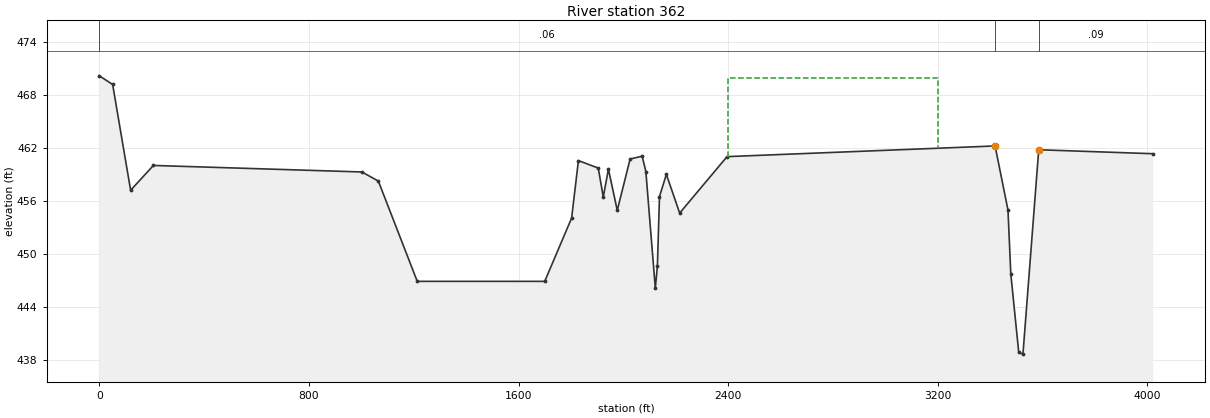
Type RM Length L Ch R = 1 ,362     ,16.31,359.89,235.67
XS GIS Cut Line= 4
2443310.861451227067385.737934472443060.796990727067584.22507031
2440327.250292477067157.626514062439445.524037557067468.25220515
#Sta/Elev= 30
       0  470.22   50.77  469.24  119.43  457.25  206.42  460.06 1002.25  459.32
 1064.91  458.29 1213.47  446.92    1700  446.92  1802.7   454.1 1828.59  460.61
 1904.35  459.76  1923.5  456.48 1943.12  459.64 1976.87  454.97 2025.92  460.79
 2071.89  461.11 2085.99  459.37 2122.11  446.15 2130.02  448.63 2138.04  456.53
 2164.26  459.05 2215.11  454.66 2395.88  461.06 3418.96  462.27 3468.17  455.01
 3478.97  447.76 3509.25  438.86 3525.34  438.67 3585.57  461.84 4020.74  461.39
#Mann= 3 ,0,0
       0     .06       0 3418.96     .05       0 3585.57     .09       0
#XS Ineff= 1 ,-1
    2400    3200     470
Permanent Ineff=
       F
Bank Sta=3418.96,3585.57
XS Rating Curve= 0 ,0
Exp/Cntr=0.3,0.1

River Reach=Elm Fork Split2 ,efs2
Reach XY= 30
2438916.72621064 7066484.92247892438355.550167647065985.51370081
 2437890.51238387064857.339776052437893.527141567063903.21077882
2437984.672956637063645.398302322438047.172831647063013.45370007
2438137.501063057060539.812978062438181.693231887060146.47485398
2438255.911915477060048.818553222438538.998619637060047.65516973
2438610.518489727059901.703689982439019.197462387059276.85684256
2439376.18723397 7058695.05420042439764.042101317058006.41581389
2440213.762002397057312.223960822440413.31704947 7056949.6009984
2440649.422548387056561.776314722440730.897122967056454.94746014
2441171.58521797 7056249.27169042441401.516516647056016.90010789
2441685.213127727055769.888134732441743.878036637055701.39844231
2441877.534265387055485.121315812442333.995294727055120.49376422
2442542.755375897054931.003985732442653.232845227054854.98281232
2442751.275300067054754.503354472442938.240477317054614.52824073
2443337.731476227054716.973245812443517.219249117054741.06940538

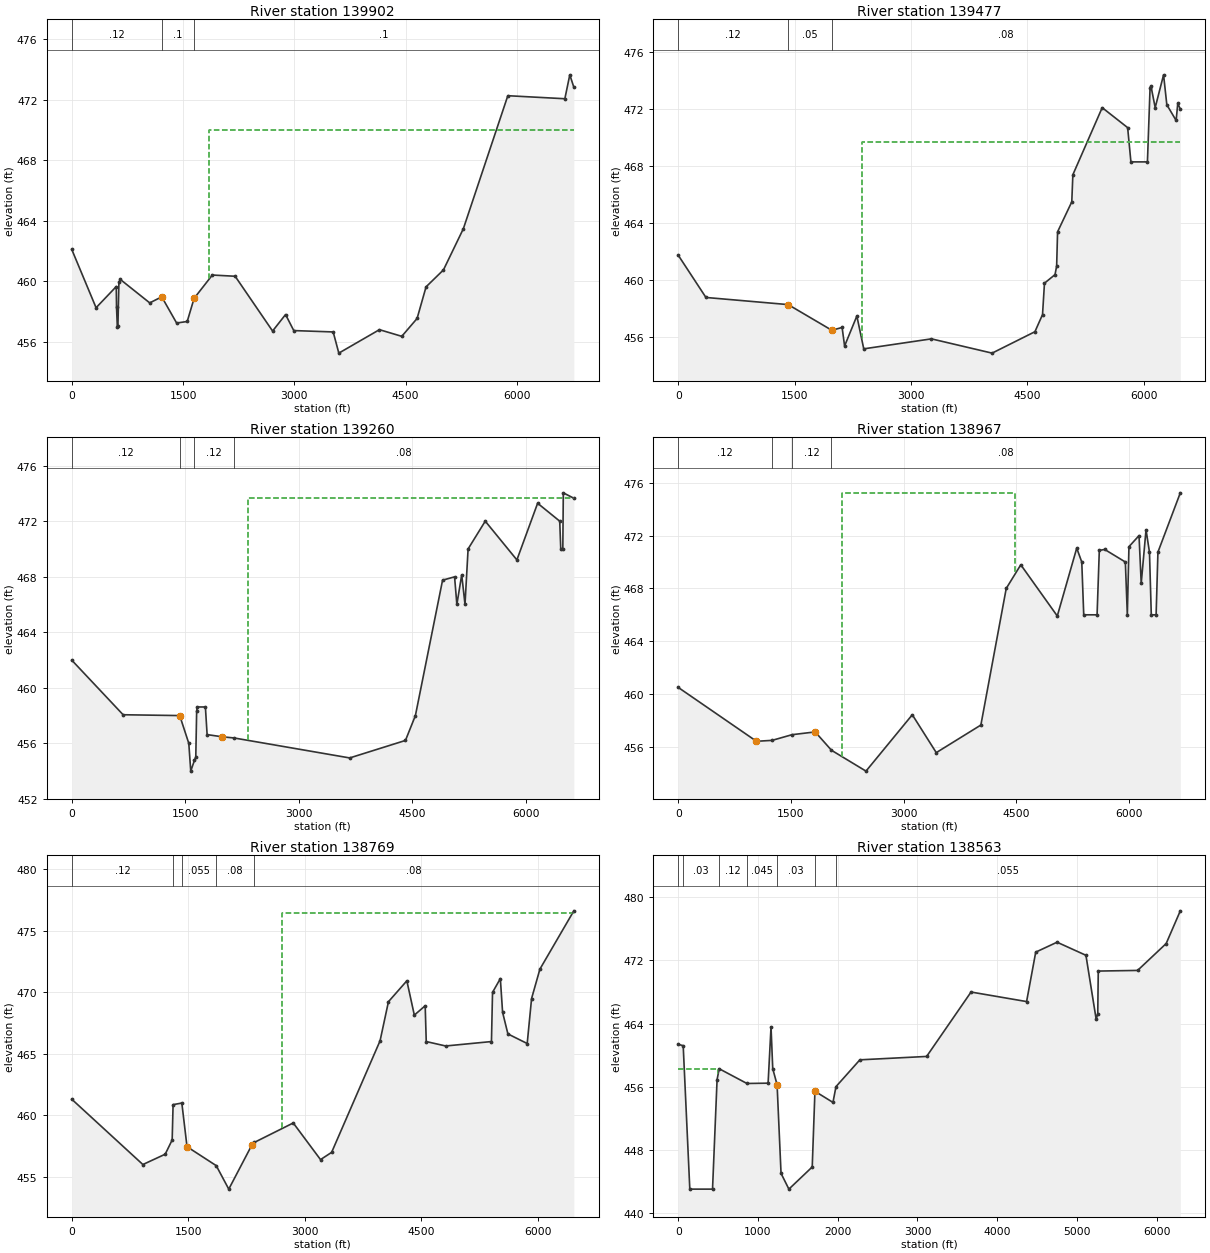
Type RM Length L Ch R = 1 ,139902  ,341.14,425.69,942.49
BEGIN DESCRIPTION:
147204-From Right Overbank Effective model
END DESCRIPTION:
XS GIS Cut Line= 2
2439858.112451237066266.04102689 2433205.5571868 7065024.0139834
#Sta/Elev= 30
       0  462.11   327.6  458.26  599.89  459.66  603.28   458.3  614.32  456.96
  622.09  457.06  635.39  459.94  654.11  460.13 1050.85  458.58 1212.68  458.98
 1413.25  457.25 1556.03  457.35 1648.92  458.88  1894.6  460.42 2202.04  460.34
 2706.82  456.72  2881.7  457.81 2992.41  456.75  3523.7  456.66 3599.58  455.26
 4147.06  456.81    4448  456.37 4654.61  457.55 4775.61  459.64 5010.05  460.76
 5278.15  463.48 5877.61  472.27 6646.26  472.07 6712.94  473.65  6767.5  472.83
#Mann= 3 ,0,0
       0     .12       0 1212.68      .1       0 1648.92      .1       0
#XS Ineff= 2 , 0
                            1850             470
Permanent Ineff=
       F       F
Bank Sta=1212.68,1648.92
XS Rating Curve= 0 ,0
Exp/Cntr=0.3,0.1

Type RM Length L Ch R = 1 ,139477  ,241.06,260.45,210.93
BEGIN DESCRIPTION:
146373-From Right Overbank Effective model
END DESCRIPTION:
XS GIS Cut Line= 4
2439821.828731137065937.634531482439651.26804863 7065945.1637159
2439153.406511567065825.574716232433529.534229137064457.04300448
#Sta/Elev= 30
       0  461.76     357   458.8    1417   458.3    1980   456.5    2112   456.7
    2144   455.4    2302   457.5    2391   455.2    3263   455.9    4045   454.9
    4597   456.4    4695   457.6    4720   459.8    4856   460.4    4877     461
    4889   463.4    5072   465.5    5086   467.4    5464   472.1    5792   470.7
    5834   468.3    6047   468.3    6081   473.5    6093   473.6    6147   472.1
    6255   474.4    6297   472.3    6417   471.2    6438   472.4 6470.74     472
#Mann= 3 ,0,0
       0     .12       0    1417     .05       0    1980     .08       0
#XS Ineff= 2 , 0
                         2365.54         469.725
Permanent Ineff=
       F       F
Bank Sta=1417,1980
XS Rating Curve= 0 ,0
Exp/Cntr=0.3,0.1

Type RM Length L Ch R = 1 ,139260  ,326.97,352.55,284.95
BEGIN DESCRIPTION:
146190-From Right Overbank Effective model
END DESCRIPTION:
XS GIS Cut Line= 2
2439792.498081137065765.186385562433348.94207063 7064194.3935954
#Sta/Elev= 30
       0  461.99  678.18  458.06 1426.16     458 1545.93     456 1571.69     454
 1620.71  454.78 1638.17  455.01 1649.73  458.33 1659.74  458.62 1765.17  458.62
 1787.86  456.63 1989.98  456.47 2141.88  456.39  3671.2  454.95 4408.12  456.21
 4539.26     458 4898.14  467.75 5056.75  467.99 5086.99     466 5151.12  468.14
 5194.48     466 5235.36     470 5462.03     472  5879.9  469.21 6153.82  473.29
 6445.67     472 6459.47     470 6486.59     470 6493.04  474.04 6632.26  473.65
#Mann= 4 ,-1,0
       0     .12       0 1426.16    .045       0 1620.71     .12       0
 2141.88     .08       0
#XS Ineff= 2 , 0
                          2331.8         473.652
Permanent Ineff=
       F       F
Bank Sta=1426.16,1989.98
XS Rating Curve= 0 ,0
Exp/Cntr=0.3,0.1

Type RM Length L Ch R = 1 ,138967  ,245.45,228.79,182.57
BEGIN DESCRIPTION:
145775-From Right Overbank Effective model
END DESCRIPTION:
XS GIS Cut Line= 2
2439665.802140317065440.98854314 2433155.5727521 7063854.4129887
#Sta/Elev= 30
       0   460.5 1042.14  456.42 1250.12  456.49 1515.65  456.92 1823.92  457.13
 2040.84  455.74 2500.38  454.16  3117.1  458.43 3436.27  455.56 4030.19  457.65
 4368.16     468 4561.82  469.79    5048  465.91 5306.87  471.05 5373.94     470
 5400.18     466 5577.86     466 5607.57  470.88  5679.6  470.95 5954.33     470
 5980.66     466 6002.25  471.16 6136.49     472  6165.6  468.38 6229.71  472.44
 6275.63  470.74  6299.8     466 6364.06     466 6388.25  470.75 6686.27  475.24
#Mann= 4 ,-1,0
       0     .12       0 1250.12    .045       0 1515.65     .12       0
 2040.84     .08       0
#XS Ineff= 1 ,-1
 2184.52 4485.09 475.238
Permanent Ineff=
       F
Bank Sta=1042.14,1823.92
XS Rating Curve= 0 ,0
Exp/Cntr=0.3,0.1

Type RM Length L Ch R = 1 ,138769  ,252.25,206.06,191.57
BEGIN DESCRIPTION:
145405-From Right Overbank Effective model.
END DESCRIPTION:
XS GIS Cut Line= 2
2439464.193619647065159.219093562433150.965104397063758.55686864
#Sta/Elev= 30
       0  461.31  915.86     456  1203.4  456.84 1293.22     458 1304.95  460.87
 1417.61     461 1484.45  457.45 1860.74  455.91 2022.16     454 2317.36  457.56
 2351.79   457.8 2852.71  459.38 3203.87   456.4 3346.95  456.99 3970.77  466.06
 4078.75  469.24 4315.91  470.94  4412.2  468.15 4552.05  468.91 4565.58     466
 4815.64  465.64  5405.6     466  5419.4     470 5520.09  471.12 5548.94  468.38
 5617.38  466.62 5865.98  465.84 5922.37   469.5 6029.67  471.89 6466.74  476.63
#Mann= 5 ,-1,0
       0     .12       0 1304.95    .045       0 1417.61    .055       0
 1860.74     .08       0 2351.79     .08       0
#XS Ineff= 2 , 0
                         2711.17         476.489
Permanent Ineff=
       F       F
Bank Sta=1484.45,2317.36
XS Rating Curve= 0 ,0
Exp/Cntr=0.3,0.1

Type RM Length L Ch R = 1 ,138563  ,265.25,229.39,220.04
BEGIN DESCRIPTION:
145143-From Right Overbank Effective model
END DESCRIPTION:
XS GIS Cut Line= 2
2439337.236196387064891.939772472433161.146842557063662.24866231
#Sta/Elev= 30
       0  461.37   62.28  461.19  145.18     443  430.13     443  487.19  456.89
  513.54  458.27  861.94   456.4 1127.16  456.44  1163.8  463.58 1185.43  458.27
 1239.84  456.25 1289.42     445 1387.97     443 1680.57  445.81 1714.62  455.41
 1940.72     454 1978.52     456 2278.02   459.4 3115.38  459.83 3672.59     468
 4369.33  466.79 4483.79  473.06 4751.43  474.32 5113.61  472.66 5242.26  464.53
 5261.86  465.27 5268.22  470.66 5761.47  470.74 6119.99  474.15 6297.31   478.3
#Mann= 7 ,-1,0
       0     .12       0   62.28     .03       0  513.54     .12       0
  861.94    .045       0 1239.84     .03       0 1714.62     .08       0
 1978.52    .055       0
#XS Ineff= 2 , 0
             500 458.184
Permanent Ineff=
       F       F
Bank Sta=1239.84,1714.62
XS Rating Curve= 0 ,0
Exp/Cntr=0.3,0.1