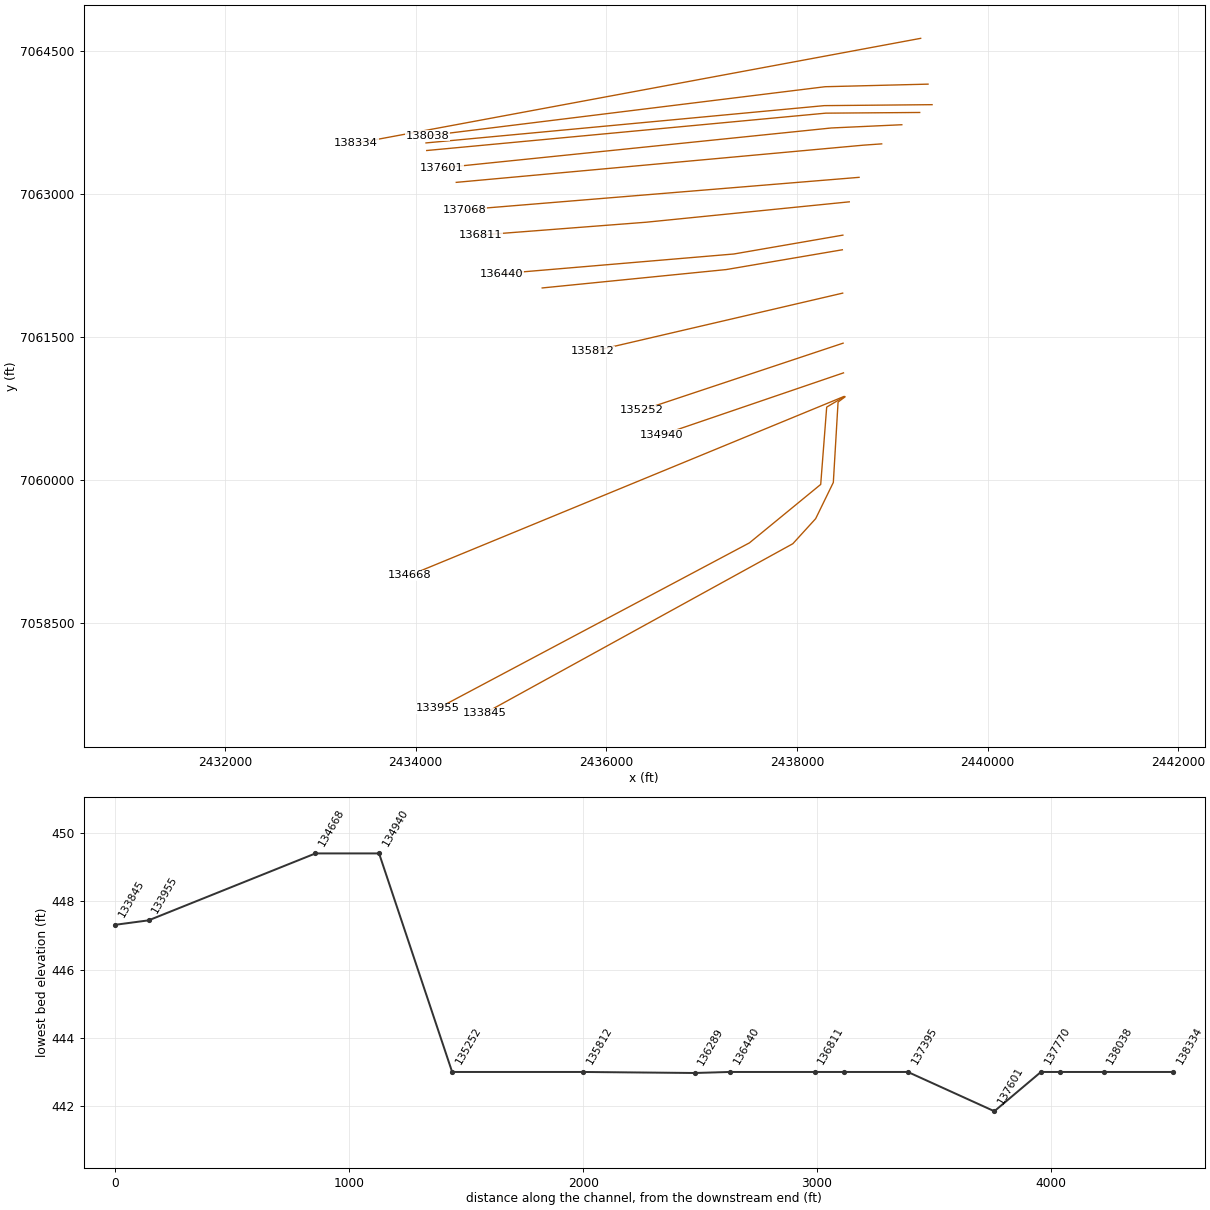
HEC-RAS study CDC_Consolidated_Model.prj: Upper Trinity CDC Consolidated Model

--- CDC_Consolidated_Model.g13 (geometry) --- (continued)

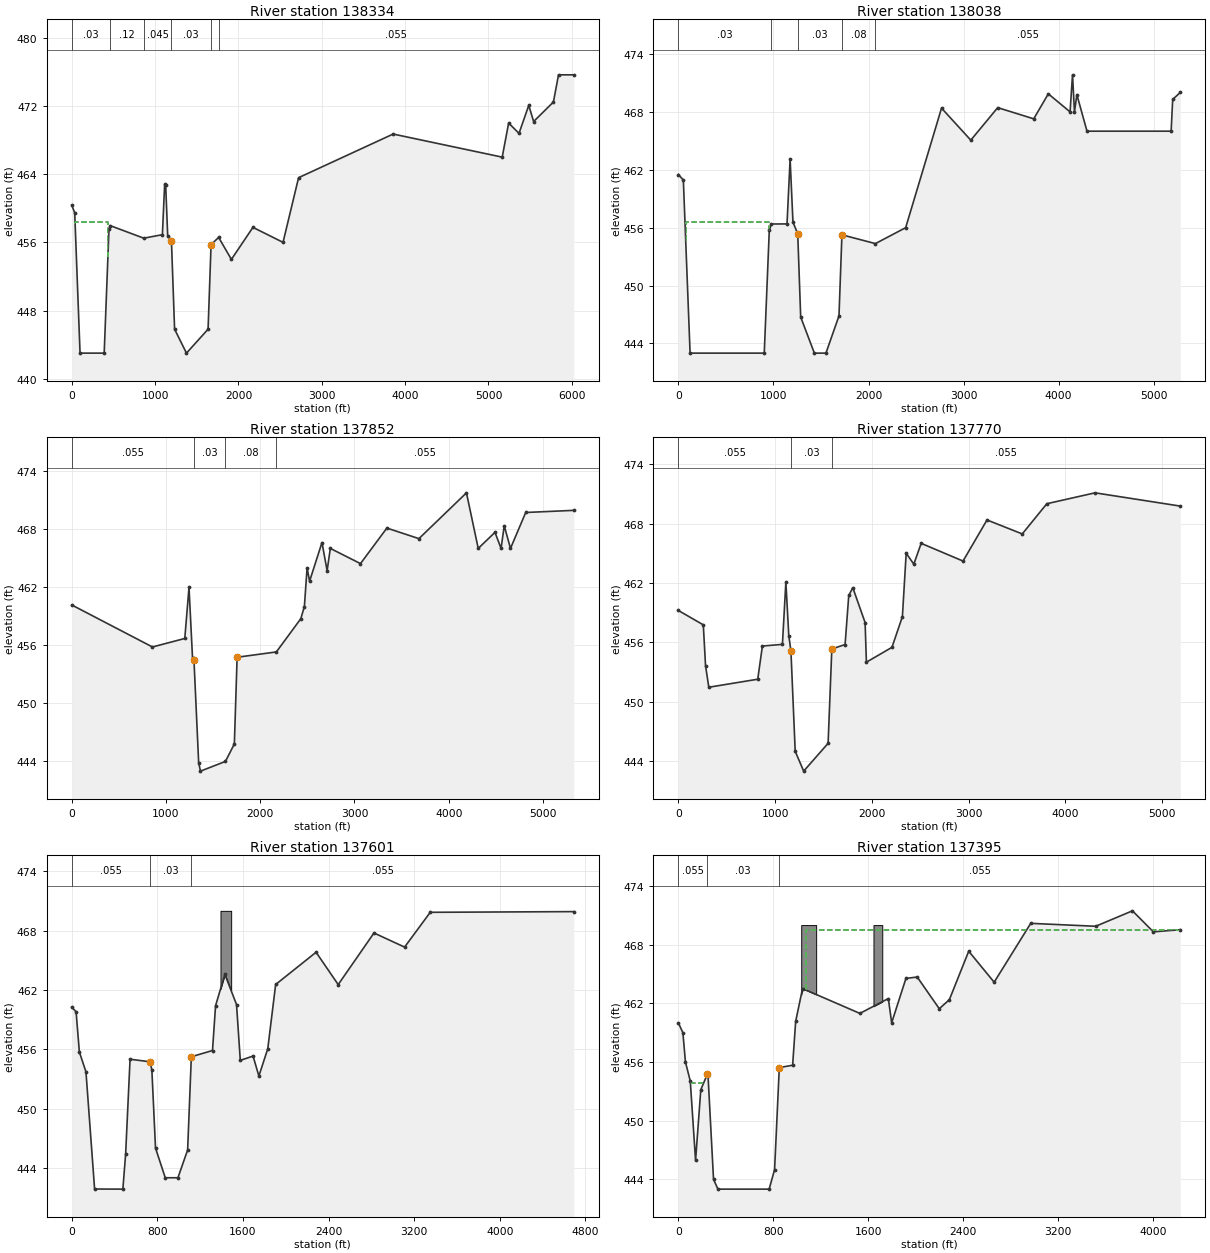
Type RM Length L Ch R = 1 ,138334  ,413.49,295.76,270.15
BEGIN DESCRIPTION:
144901-From Right Overbank Effective model
END DESCRIPTION:
XS GIS Cut Line= 2
2439298.78154889 7064636.26475892433377.850805487063535.20134422
#Sta/Elev= 30
       0  460.36   35.39  459.47   99.42     443  389.05     443   446.5  457.52
  459.27  457.97  864.14  456.49 1087.35   456.9 1114.46  462.79 1126.68  462.77
 1150.93  456.79 1196.04  456.17 1233.77  445.81 1376.26     443 1635.56  445.81
 1671.48  455.74 1762.24  456.58 1915.33     454 2173.81  457.76 2534.84     456
 2721.51  463.59 3855.88  468.71 5164.59     466 5241.84     470 5366.17  468.79
 5483.23  472.08 5541.61  470.18 5779.11  472.47 5840.21  475.66 6022.44  475.66
#Mann= 6 ,-1,0
       0     .03       0  459.27     .12       0  864.14    .045       0
 1196.04     .03       0 1671.48     .08       0 1762.24    .055       0
#XS Ineff= 1 ,-1
   40.53  433.48 458.355
Permanent Ineff=
       F
Bank Sta=1196.04,1671.48
XS Rating Curve= 0 ,0
Exp/Cntr=0.3,0.1

Type RM Length L Ch R = 1 ,138038  ,212.43,185.79,175.86
BEGIN DESCRIPTION:
144676-From Right Overbank Effective model
END DESCRIPTION:
XS GIS Cut Line= 3
2439376.129163227064155.759486322438295.875418227064128.63322823
2434127.947402397063614.20348281
#Sta/Elev= 30
       0  461.51   52.25  460.94  123.28     443  903.47     443  956.27  455.71
  978.11  456.38 1142.87  456.39 1175.44  463.12 1205.33  456.58 1255.64  455.35
 1286.69  446.74 1430.63     443 1552.33     443 1689.56  446.86 1720.47  455.26
 2072.77  454.35 2390.94     456 2768.27  468.39 3076.13  465.07 3359.37  468.44
 3738.03  467.28 3891.59  469.87 4120.39     468 4146.15  471.84 4166.78     468
 4191.85  469.79 4298.44     466 5183.54     466 5199.98  469.29 5280.15  470.02
#Mann= 5 ,-1,0
       0     .03       0  978.11    .045       0 1255.64     .03       0
 1720.47     .08       0 2072.77    .055       0
#XS Ineff= 1 ,-1
   77.24  955.55456.5858
Permanent Ineff=
       F
Bank Sta=1255.64,1720.47
XS Rating Curve= 0 ,0
Exp/Cntr=0.3,0.1

Type RM Length L Ch R = 1 ,137852  ,82.85,82.48,80.51
BEGIN DESCRIPTION:
144554 From Right Overbank Effective model
END DESCRIPTION:
XS GIS Cut Line= 3
 2439418.36365887063940.340625812438287.666773217063930.28716823
2434110.367713147063539.08617897
#Sta/Elev= 30
       0  460.16  856.35  455.82 1199.35   456.7 1244.09  461.97 1281.32  454.71
 1296.67  454.48  1346.6  443.87 1365.81     443 1630.53     444 1725.39  445.81
 1754.66  454.76  2171.1  455.31 2430.33  458.74 2468.53     460 2497.14     464
 2523.49  462.61 2655.23  466.61 2709.57   463.7 2743.85     466 3063.73  464.43
 3343.82   468.1 3683.95  467.01  4188.2  471.74 4313.15     466    4491  467.66
 4555.45     466 4589.14  468.34 4655.37     466 4817.12  469.71 5326.32  469.93
#Mann= 4 ,-1,0
       0    .055       0 1296.67     .03       0 1630.53     .08       0
  2171.1    .055       0
Bank Sta=1296.67,1754.66
XS Rating Curve= 0 ,0
Exp/Cntr=0.3,0.1

Type RM Length L Ch R = 1 ,137770  ,199.6,199.26,205.62
BEGIN DESCRIPTION:
144474-From Right Overbank Effective model
END DESCRIPTION:
XS GIS Cut Line= 3
2439288.521070727063858.444136072438302.439381477063851.33260173
2434117.826031557063459.44657448
#Sta/Elev= 30
       0  459.22  257.72  457.77  280.81  453.65  314.63  451.47  820.57  452.28
  868.62  455.63 1075.69   455.8 1111.28   462.1 1141.48  456.67 1163.51  455.16
 1207.78     445 1295.35     443 1547.97  445.81 1586.37  455.34 1723.45  455.78
 1761.49  460.74 1803.26  461.52 1930.39     458 1943.79     454    2208   455.5
    2316   458.6    2355     465    2434   463.9    2510     466 2942.78  464.21
 3190.59  468.36 3555.06  466.95 3809.01     470 4307.54   471.1 5189.03  469.76
#Mann= 3 ,0,0
       0    .055       0 1163.51     .03       0 1586.37    .055       0
Bank Sta=1163.51,1586.37
XS Rating Curve= 0 ,0
Exp/Cntr=0.3,0.1

Type RM Length L Ch R = 1 ,137601  ,370.43,369.8,381.59
BEGIN DESCRIPTION:
144314-From Right Overbank Effective model
END DESCRIPTION:
XS GIS Cut Line= 3
2439100.907600817063729.899773732438361.666625227063695.86473681
2434272.570472727063276.98171631
#Sta/Elev= 30
       0  460.25   40.48  459.79   71.08  455.72  132.71  453.71  213.48  441.86
  477.63  441.85  503.57  445.41  544.94  454.99  731.58  454.73  748.74  453.89
  782.85     446  873.95     443  992.32     443    1083  445.81 1117.59  455.24
 1315.44  455.87 1344.05   460.4 1431.08  463.57 1540.08  460.52 1575.22  454.87
 1694.48  455.31 1748.97  453.29 1832.04  456.05  1905.8  462.55 2283.55  465.81
  2490.3  462.54 2824.77  467.76 3110.92  466.33 3350.61  469.85 4691.57  469.92
#Mann= 3 ,0,0
       0    .055       0  731.58     .03       0 1117.59    .055       0
#XS Ineff= 2 , 0
          640.05 454.323
Permanent Ineff=
       F       F
#Block Obstruct= 1 ,-1
 1390.05 1490.05     470
Bank Sta=731.58,1117.59
XS Rating Curve= 0 ,0
Exp/Cntr=0.3,0.1

Type RM Length L Ch R = 1 ,137395  ,272.64,272.18,280.86
BEGIN DESCRIPTION:
144148-From Right Overbank Effective model
END DESCRIPTION:
XS GIS Cut Line= 3
2438889.892930977063529.102603142438700.414963477063515.68596332
2434427.706317317063125.33963114
#Sta/Elev= 30
       0     460   38.03     459    59.6     456  100.34  454.05   144.9  445.93
  188.93  453.16   243.6  454.74  250.06  454.58  296.26     444  333.54     443
  764.94     443  810.88     445  850.56  455.43  962.83  455.67  988.41  460.15
 1046.35  463.51 1529.76  460.97 1769.39  462.49 1797.47  460.01  1917.8  464.55
 2012.65  464.69 2198.57  461.45 2283.49  462.37 2446.84  467.33 2661.13  464.16
 2969.41  470.18 3516.51  469.88 3826.51  471.46 4002.92  469.31 4229.96  469.53
#Mann= 3 ,0,0
       0    .055       0   243.6     .03       0  850.56    .055       0
#XS Ineff= 2 ,-1
     100     210 453.876 1075.26 4229.96  469.53
Permanent Ineff=
       F       F
#Block Obstruct= 2 ,-1
 1035.25 1161.28     470  1644.1 1718.28     470
Bank Sta=243.6,850.56
XS Rating Curve= 0 ,0
Exp/Cntr=0.3,0.1

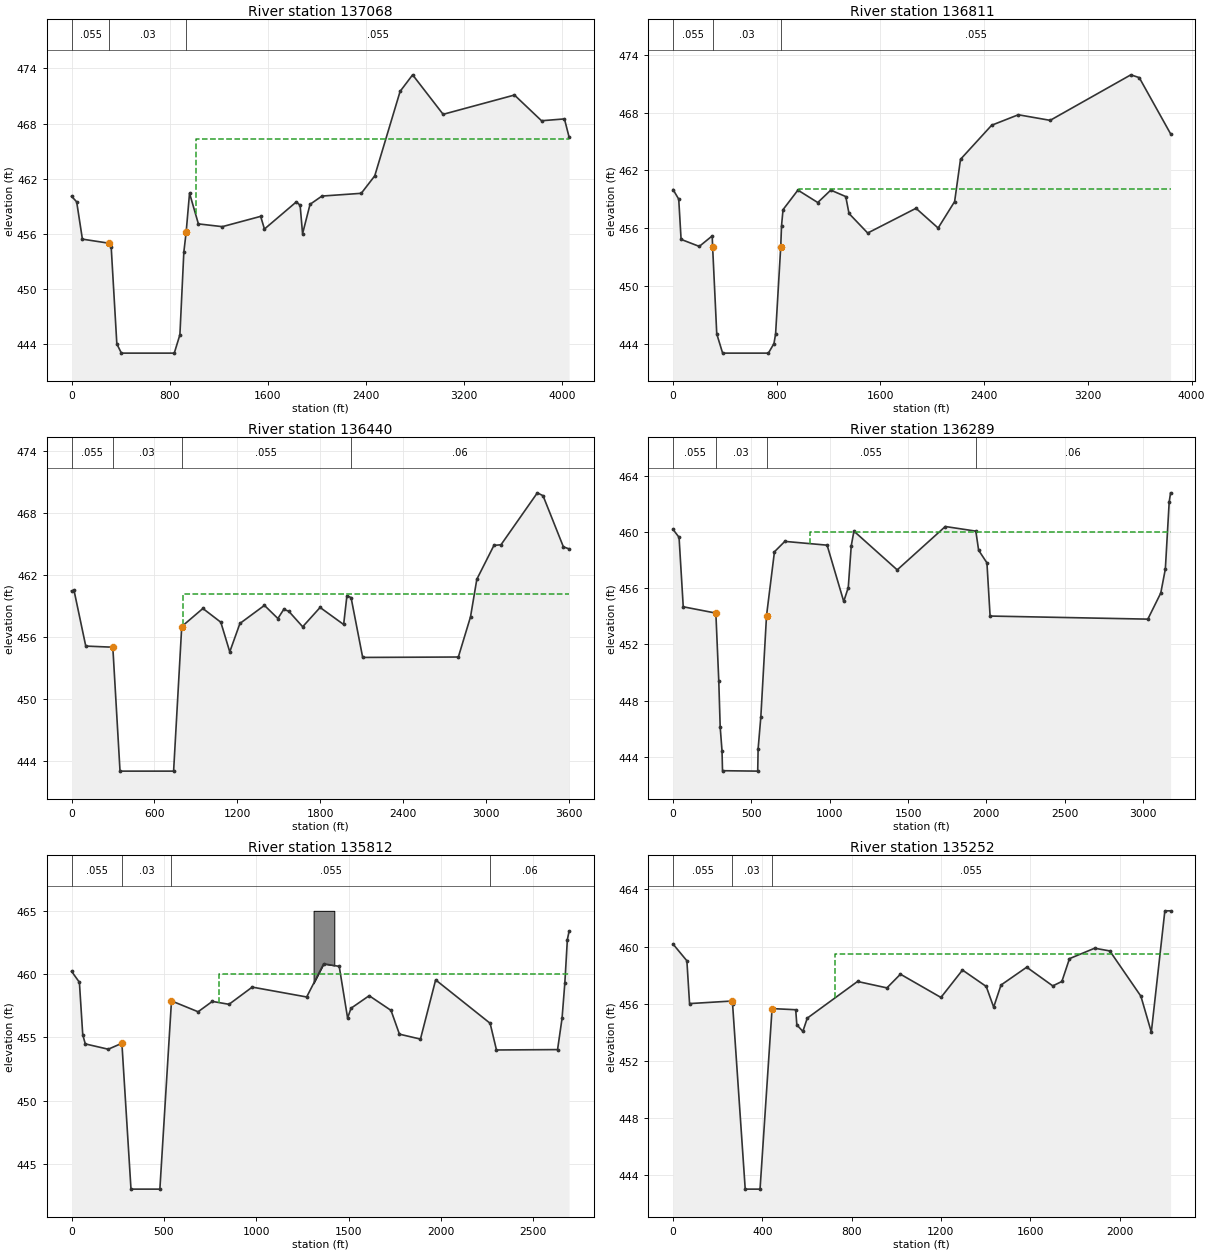
Type RM Length L Ch R = 1 ,137068  ,127.02,126.81,130.85
BEGIN DESCRIPTION:
143756-From Right Overbank Effective model
END DESCRIPTION:
XS GIS Cut Line= 2
 2438652.36322237063177.973056062434517.585074567062838.20700331
#Sta/Elev= 30
       0  460.08   41.87  459.47   88.58  455.41  308.83  454.96  323.42  454.58
  369.62     444   406.9     443   838.3     443  884.24     445  916.39     454
  935.22  456.17  962.87  460.41 1035.17  457.07  1230.4  456.77 1543.24  457.89
 1574.15  456.51 1834.73  459.47 1865.34  459.09  1885.2     456 1946.25   459.2
 2043.25   460.1 2364.25   460.4 2474.25   462.3 2681.25   471.5 2783.25   473.3
 3032.25     469 3614.25   471.1 3835.25   468.3 4022.17   468.5 4060.18  466.52
#Mann= 3 ,0,0
       0    .055       0  308.83     .03       0  935.22    .055       0
#XS Ineff= 2 , 0
                         1011.91         466.291
Permanent Ineff=
       F       F
Bank Sta=308.83,935.22
XS Rating Curve= 0 ,0
Exp/Cntr=0.3,0.1

Type RM Length L Ch R = 1 ,136811  ,362.71,362.09,373.64
BEGIN DESCRIPTION:
143265-From Right Overbank Effective model
END DESCRIPTION:
XS GIS Cut Line= 4
2438549.622286057062921.01195581 2438114.43319587062877.32175447
2436417.209228057062706.931347222434686.575550217062573.29152264
#Sta/Elev= 30
       0     460   43.93     459   62.11  454.82  202.49  454.09  302.07  455.18
  305.45     454  337.17     445  382.49     443  735.46     443  778.52     444
  791.01     445  830.38     454  836.84  456.23  848.35  457.91  963.16  459.94
  1116.2  458.65  1216.7  459.94 1332.04  459.27 1357.21  457.51  1501.4  455.48
 1873.94  458.05 2044.55     456 2171.81  458.75 2217.17  463.14 2457.32  466.68
 2663.06  467.77 2908.61  467.19 3530.98  471.92  3595.8  471.63 3837.48  465.79
#Mann= 3 ,0,0
       0    .055       0  305.45     .03       0  830.38    .055       0
#XS Ineff= 2 , 0
                          968.92         460.079
Permanent Ineff=
       F       F
Bank Sta=305.45,830.38
XS Rating Curve= 0 ,0
Exp/Cntr=0.3,0.1

Type RM Length L Ch R = 1 ,136440  ,153.14,150.76,152.2
BEGIN DESCRIPTION:
142900-From Right Overbank Effective model
END DESCRIPTION:
XS GIS Cut Line= 3
2438482.719532717062571.696709562437339.328118737062373.83358823
2434904.216847237062167.62927623
#Sta/Elev= 30
       0  460.46      18   460.5     103  455.11     299     455  351.17     443
  739.32     443  798.18     457  951.44  458.75 1081.35  457.42 1146.12  454.55
 1219.71   457.3 1397.29  459.05 1494.73  457.78 1537.02  458.66 1572.99  458.49
 1674.29  456.98 1800.48  458.85 1971.05   457.2 1994.93     460 2024.97   459.8
 2108.97  454.01 2801.94  454.05 2890.07  457.94 2935.81  461.58 3059.75  464.86
 3110.84  464.92 3374.29  469.95 3415.46  469.67 3562.83  464.72 3604.21  464.52
#Mann= 4 ,-1,0
       0    .055       0     299     .03       0  798.18    .055       0
 2024.97     .06       0
#XS Ineff= 2 , 0
                          810.97          460.14
Permanent Ineff=
       F       F
Bank Sta=299,798.18
XS Rating Curve= 0 ,0
Exp/Cntr=0.3,0.1

Type RM Length L Ch R = 1 ,136289  ,467.11,477.16,517.19
BEGIN DESCRIPTION:
142702- From Right Overbank Effective model
END DESCRIPTION:
XS GIS Cut Line= 3
2438477.144740727062418.047410562437259.592057727062210.56160507
2435329.014225977062017.56363148
#Sta/Elev= 30
       0  460.19   38.42  459.63   65.12  454.68  273.26  454.23  291.83  449.42
  300.98   446.1   312.7   444.4  315.68     443  540.45  442.97  542.91  444.54
  560.35  446.84  596.66  454.05  647.21   458.6  713.42  459.34   983.3  459.07
 1089.31  455.06 1118.33  456.05 1137.22  459.02  1154.4  460.07 1430.64  457.31
 1737.52   460.4 1932.45  460.07  1950.2  458.71 2003.19  457.81 2023.45  454.02
 3030.13   453.8 3112.63  455.66 3141.85  457.37 3166.37  462.15 3175.31   462.8
#Mann= 4 ,-1,0
       0    .055       0  273.26     .03       0  596.66    .055       0
 1932.45     .06       0
#XS Ineff= 2 , 0
                          872.18             460
Permanent Ineff=
       F       F
Bank Sta=273.26,596.66
XS Rating Curve= 0 ,0
Exp/Cntr=0.3,0.1

Type RM Length L Ch R = 1 ,135812  ,546.71,559.23,594.27
BEGIN DESCRIPTION:
141891-From Right Overbank Effective model
END DESCRIPTION:
XS GIS Cut Line= 2
2438480.731347727061963.320629732435857.493155887061352.45735015
#Sta/Elev= 30
       0  460.22   42.52  459.35   60.68   455.2   74.46  454.48  198.69  454.06
  272.55  454.53   321.8     443  478.17     443     541  457.88  685.08  457.02
  761.99  457.84  852.47  457.61   978.1  458.97  1272.8  458.19 1364.82  460.81
 1448.99  460.61 1494.34  456.53    1513   457.3 1611.23  458.29 1729.35  457.13
 1774.99  455.25 1888.73  454.86 1971.01  459.54 2265.87  456.11 2300.27     454
 2631.01  454.03 2655.21  456.49 2670.38   459.3 2684.04  462.73 2693.42  463.39
#Mann= 4 ,-1,0
       0    .055       0  272.55     .03       0     541    .055       0
 2265.87     .06       0
#XS Ineff= 2 , 0
                          800.92             460
Permanent Ineff=
       F       F
#Block Obstruct= 1 ,-1
 1310.28 1422.38     465
Bank Sta=272.55,541
XS Rating Curve= 0 ,0
Exp/Cntr=0.3,0.1

Type RM Length L Ch R = 1 ,135252  ,317.56,312.42,308.11
BEGIN DESCRIPTION:
141518-From Right Overbank Effective model
END DESCRIPTION:
XS GIS Cut Line= 2
2438484.872415567061438.317086562436370.415358387060734.05569981
#Sta/Elev= 30
       0  460.17      62     459      74     456  263.41  456.18  266.58     456
  323.35     443  389.72     443  443.59  455.65  549.49  455.57   554.5  454.51
  581.46  454.05  601.25  454.98  826.43  457.55  958.08   457.1 1018.56  458.06
 1200.05  456.43 1296.49  458.35 1402.92   457.2 1436.16  455.75 1469.05   457.3
 1584.19  458.55 1700.94  457.24 1741.66  457.55 1775.82  459.15 1888.44  459.88
 1956.34  459.69 2095.61  456.52 2142.37     454    2203   462.5 2228.66   462.5
#Mann= 3 ,0,0
       0    .055       0  263.41     .03       0  443.59    .055       0
#XS Ineff= 2 , 0
                          723.97           459.5
Permanent Ineff=
       F       F
Bank Sta=263.41,443.59
XS Rating Curve= 0 ,0
Exp/Cntr=0.3,0.1

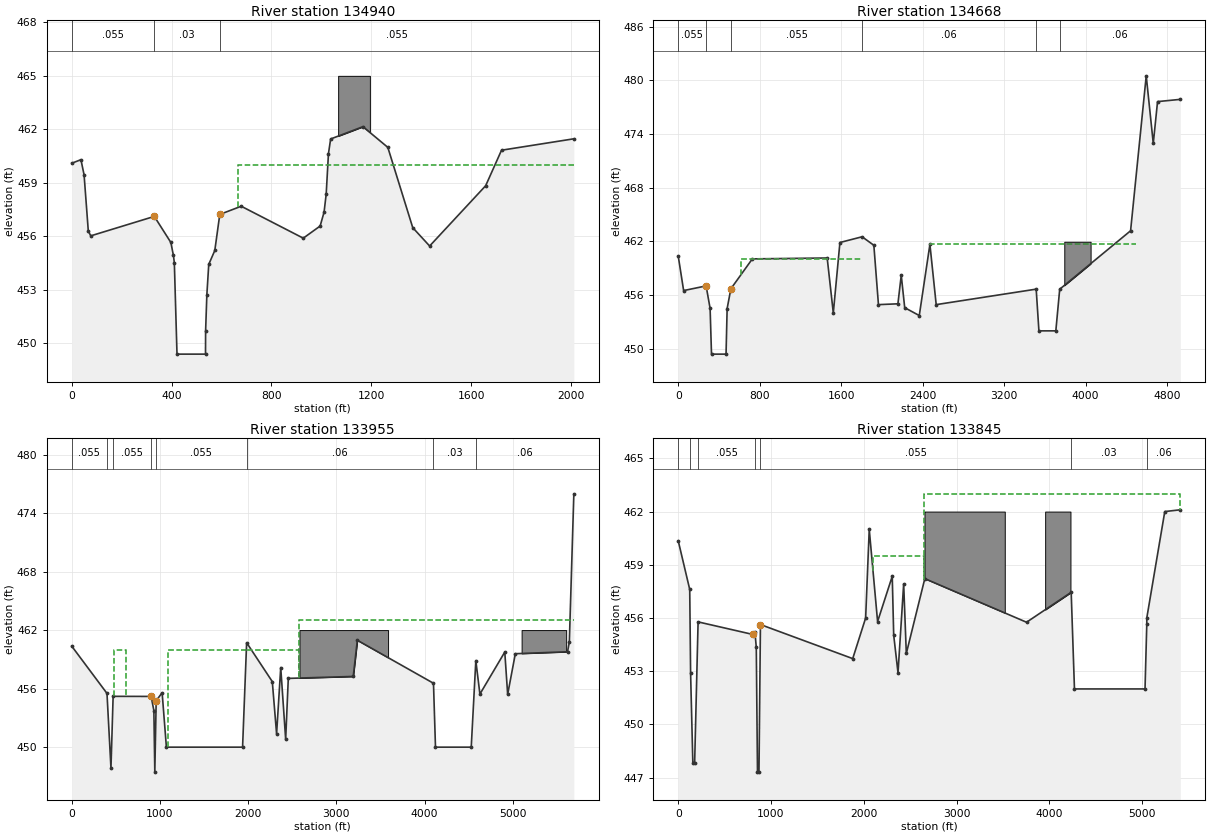
Type RM Length L Ch R = 1 ,134940  ,265.83,271.87,290.76
BEGIN DESCRIPTION:
141274-From Right Overbank Effective model
END DESCRIPTION:
XS GIS Cut Line= 2
2438489.057446557061126.74881206 2436585.26105737060476.89348447
#Sta/Elev= 30
       0   460.1   36.71   460.3   49.33  459.45   66.24   456.3   76.14  456.03
  330.72  457.12  396.98  455.66   407.3  454.93  410.97  454.52  421.62   449.4
  535.86   449.4  536.25   450.7  541.26  452.73  548.82  454.43  573.09  455.21
  593.01  457.23  678.96  457.69  927.56   455.9  995.13  456.58 1010.92  457.36
 1019.38  458.37 1028.47  460.64 1037.25  461.46 1166.64  462.15  1266.3  460.99
 1366.18  456.49 1433.84  455.46 1658.35  458.84 1721.89  460.83 2011.65  461.47
#Mann= 3 ,0,0
       0    .055       0  330.72     .03       0  593.01    .055       0
#XS Ineff= 2 , 0
                           666.9             460
Permanent Ineff=
       F       F
#Block Obstruct= 1 ,-1
 1067.32 1194.41     465
Bank Sta=330.72,593.01
XS Rating Curve= 0 ,0
Exp/Cntr=0.3,0.1

Type RM Length L Ch R = 1 ,134668  ,22.26,713.47,805.77
BEGIN DESCRIPTION:
141084-
END DESCRIPTION:
XS GIS Cut Line= 4
 2438492.9478587 7060878.5383505 2436823.3311192 7060190.9701718
  2436823.331119 7060190.9701718 2433933.8546147 7059001.0493233
#Sta/Elev= 30
       0  460.35   52.99   456.5  273.74  457.02  312.96  454.51  326.72   449.4
  469.49   449.4  480.22  454.49  516.89   456.7  727.67  460.04 1462.79  460.14
 1522.81     454 1587.76  461.87 1805.65  462.51    1921  461.56 1966.19  454.93
 2157.22  455.02 2190.02  458.21    2224  454.59 2367.04  453.71  2471.5  461.66
 2533.22  454.93 3515.15  456.66 3541.98     452 3708.09     452 3746.15  456.65
 4442.21  463.18 4595.84  480.49 4664.98  472.94 4707.03  477.61 4930.55  477.86
#Mann= 6 ,-1,0
       0    .055       0  273.74     .05       0  516.89    .055       0
 1805.65     .06       0 3515.15     .03       0 3746.15     .06       0
#XS Ineff= 3 ,-1
  616.98 1805.65     460 1805.65    2470     461    2470    4500   461.7
Permanent Ineff=
       F       F       F
#Block Obstruct= 1 ,-1
 3791.13  4049.6 461.956
Bank Sta=273.74,516.89
XS Rating Curve= 0 ,0
Exp/Cntr=0.3,0.1

Type RM Length L Ch R = 1 ,133955  ,99.43,141.96,130.31
BEGIN DESCRIPTION:
Lidar xsec  ROB ineff based on upstream xsec lat overflow at elev 462, and ineff from Corporate ROW embankement
END DESCRIPTION:
XS GIS Cut Line= 5
  2438497.966549 7060877.1069229 2438312.9459221 7060767.5979556
     2438250.167     7059956.349     2437502.668     7059343.305
     2434238.518     7057608.665
#Sta/Elev= 30
       0  460.35  399.39  455.51  444.45  447.85  468.94  455.21     900   455.2
     931  453.75  941.63  447.44  957.27  454.76 1024.73  455.58 1073.04     450
 1936.93     450  1982.9  460.71    2274  456.72 2322.69  451.36  2369.6  458.16
 2425.67  450.79 2455.31  457.05 3191.92  457.25 3238.27  460.96 4101.75  456.55
 4124.48     450 4529.87     450  4581.9  458.87 4628.21  455.44 4910.22  459.75
 4942.97  455.41 5029.95  459.58 5621.98  459.78 5642.36  460.78 5693.45  475.97
#Mann= 8 ,-1,0
       0    .055       0  399.39     .05       0  468.94    .055       0
     900     .05       0  957.27    .055       0  1982.9     .06       0
 4101.75     .03       0  4581.9     .06       0
#XS Ineff= 4 ,-1
     480     613     460    1096    1983     460    1983    2582     460
    2582 5693.45     463
Permanent Ineff=
       F       F       F       F
#Block Obstruct= 2 ,-1
    2582    3587     462    5101  5606.5     462
Bank Sta=900,957.27
XS Rating Curve= 0 ,0
Exp/Cntr=0.5,0.3

Type RM Length L Ch R = 1 ,133845  ,118.17,134.58,148.61
BEGIN DESCRIPTION:
Embankment US-gis7858
END DESCRIPTION:
XS GIS Cut Line= 6
  2438505.062335 7060875.0819926   2438432.32298 7060820.6683875
 2438382.5655336 7059976.9253243 2438197.1489096 7059597.0642074
 2437957.7340341 7059334.2806122 2434724.0285593 7057554.5102217
#Sta/Elev= 30
       0  460.35  123.81  457.61  133.25  452.89  157.35  447.85  176.96  447.85
  214.09  455.78  806.08  455.07  826.59  455.22   841.4  454.35  854.42  447.31
  870.45  447.31  886.33  455.63 1881.16  453.71 2020.43     456 2059.17     461
 2149.28   455.8 2307.22  458.35 2322.94  455.03 2369.42  452.91 2430.38  457.92
  2458.9     454 2658.31  458.22 3755.12  455.76 4236.42  457.45  4271.7     452
 5032.47     452 5051.47  455.65 5051.47     456 5245.47     462 5412.89   462.1
#Mann= 7 ,-1,0
       0    .055       0  123.81     .05       0  214.09    .055       0
  826.59     .05       0  886.33    .055       0 4236.42     .03       0
 5051.47     .06       0
#XS Ineff= 2 ,-1
    2100 2654.77   459.5 2654.77 5412.89     463
Permanent Ineff=
       F       F
#Block Obstruct= 2 ,-1
 2654.77  3520.3     462 3955.82 4228.71     462
Bank Sta=806.08,886.33
XS Rating Curve= 0 ,0
Exp/Cntr=0.5,0.3