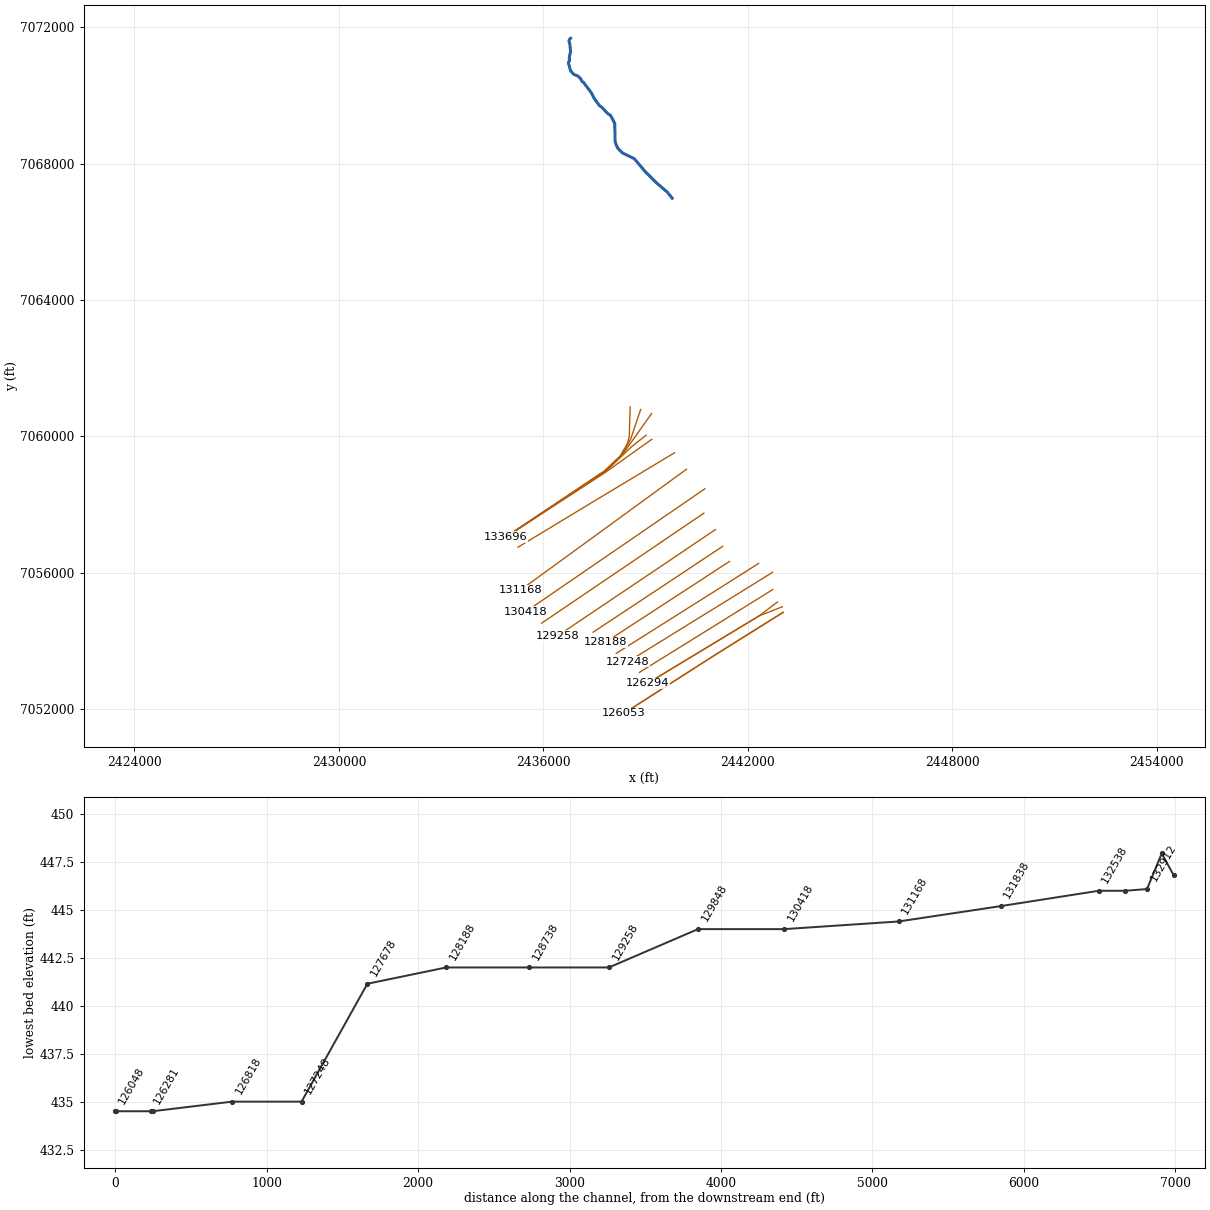
HEC-RAS study CDC_Consolidated_Model.prj: Upper Trinity CDC Consolidated Model

--- CDC_Consolidated_Model.g13 (geometry) --- (continued)

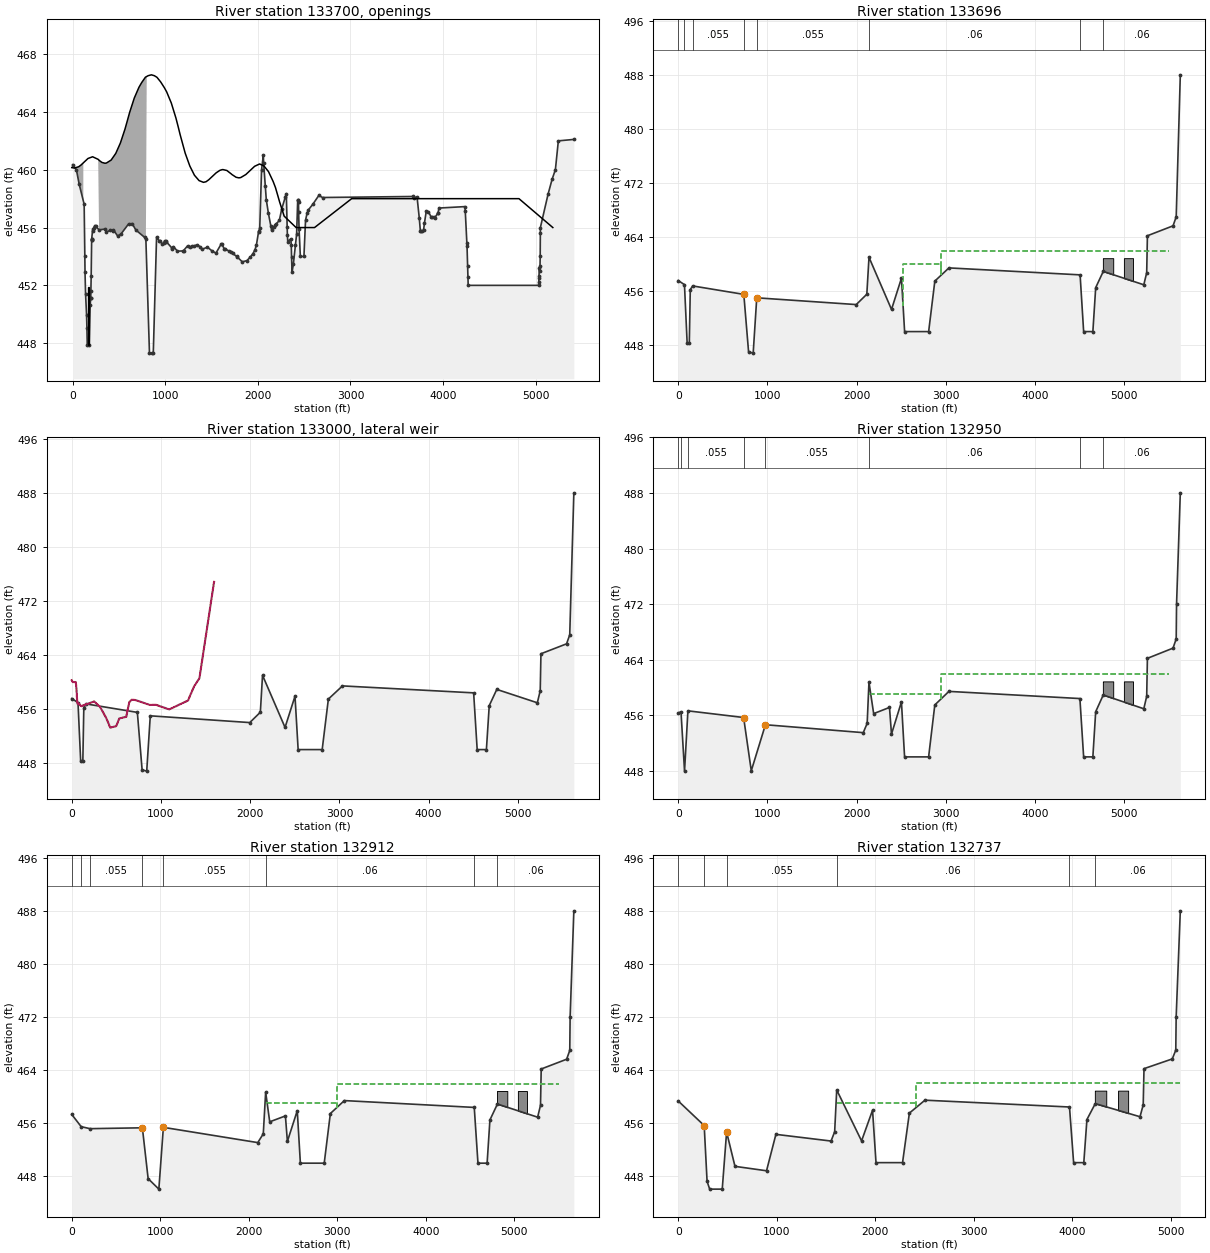
Type RM Length L Ch R = 4 ,133700  ,,,
Bridge Culvert--1,0,-1,-1, 0
Deck Dist Width WeirC Skew NumUp NumDn MinLoCord MaxHiCord MaxSubmerge Is_Ogee
24,83,2.6,0, 83, 81, , , 0.98, 0, 0,0,,
     -10      15   19.05      65      90     115     155     165     215     275
     290     315  349.16     365     415     465     515     565     590     615
     665     715     740     750  784.89   786.9     815     850   881.6   909.7
     915     950     965     990    1015    1065    1115    1140    1160    1215
    1265    1315    1365 1412.24    1440    1470    1515    1550    1590    1615
    1625    1665    1715    1720    1765    1795    1815    1870    1915    1965
 2018.33    2065    2115    2165    2190    2215    2235 2284.07 2413.03 2474.03
 2499.03 2531.03 2547.03 2559.03 2567.03 2600.03 2606.03 2612.03 3013.03 3527.03
 4297.03 4820.03 5186.03
  460.15  460.12  460.12  460.21  460.33  460.48  460.72  460.78   460.9  460.72
  460.63  460.51  460.45  460.47  460.67  461.13  461.85  462.82  463.39  463.97
  464.96   465.7  465.98  466.08   466.4  466.41  466.51  466.57  466.51   466.4
  466.36  466.08  465.93  465.68  465.39  464.62  463.58  462.96  462.44  461.15
  460.26  459.62  459.25  459.13  459.17  459.31  459.58  459.79  459.96  460.01
  460.01  459.95   459.7  459.67  459.48  459.44  459.46  459.67  459.94  460.24
   460.4  460.27  459.87  459.19  458.77  458.22  457.77  456.79     456     456
     456     456     456     456     456     456     456     456     458     458
     458     458     456
                                         460.876 461.014  461.08 461.014 460.898
     -40     -15  -10.95      35      60      85     125     135     185     245
     260     285  319.16     335     385     435     485     535     560     585
     635     685     710     720  754.89   756.9     785     820   851.6   879.7
     885     920     935     960     985    1035    1085    1110    1130    1185
    1235    1285    1335 1382.24    1410    1440    1485    1520    1560    1585
    1595    1635    1685    1690    1735    1765    1785    1840    1885    1935
 1988.33    2035    2085    2135    2160    2185    2205 2254.07    2313    2374
    2399    2459    2467    2500    2506    2512    2913    3427    4197    4720
    5086
  460.15  460.12  460.12  460.21  460.33  460.48  460.72  460.78   460.9  460.72
  460.63  460.51  460.45  460.47  460.67  461.13  461.85  462.82  463.39  463.97
  464.96   465.7  465.98  466.08   466.4  466.41  466.51  466.57  466.51   466.4
  466.36  466.08  465.93  465.68  465.39  464.62  463.58  462.96  462.44  461.15
  460.26  459.62  459.25  459.13  459.17  459.31  459.58  459.79  459.96  460.01
  460.01  459.95   459.7  459.67  459.48  459.44  459.46  459.67  459.94  460.24
   460.4  460.27  459.87  459.19  458.77  458.22  457.77  456.79     456     456
     456     456     456     456     456     456     458     458     458     458
     456
                                         460.876 461.014  461.08 461.014 460.898
Abutment Skew #Up #Dn= , 2 , 2
   786.9  815.01
   460.2  450.83
   756.9     800
   460.2  445.83
Abutment Skew #Up #Dn= , 2 , 2
  879.04   909.7
     450  460.22
     838   879.7
  446.32  460.22
BR Coef=-1 , 0 , 0 ,, 0 ,,,0.8,0,,0,
WSPro=,,,, 1 ,,,, 0 ,,,, 0 ,,,,-1 ,-1 ,-1 , 0 , 0 , 0 , 0 , 0
Culvert=2,4,3,120,0.015,0.5,1,8,3,447.87,170,448.26,110,Existing3'x4, 0 ,1
     170     110
BC Culvert Barrel=1,,0
Culvert Bottom n=0.015
BC Mult= 2 ,0,603.59,0,573.25
BC Mult= 3 ,345.47,5412.89,314.62,5627.17
BR U #Sta/Elev= 161
       0  460.35      40     460      70     459  123.81  457.61  131.07  454.02
  133.25  452.89  138.95  451.42  149.86  449.96  153.54  449.07  157.35  447.85
  176.96  447.85  188.45  450.64  194.66  451.11  195.07  451.15  196.64  451.59
  199.54  452.62  204.63  455.15  204.69  455.17  204.72  455.18  204.74  455.18
  214.09  455.78  220.56  455.88  226.09  455.96  238.71  456.14   249.8  456.09
  284.39  455.84  345.47  455.89  364.78  455.69  405.87  455.81  432.31  455.78
  440.11  455.84  485.95  455.41  522.21  455.56  603.59  456.25  642.57  456.27
  682.01  455.83  776.98  455.32  790.46  455.18  829.27  447.31  854.42  447.31
  870.45  447.31  905.97  455.35  937.55  455.04  946.52   455.1  964.64  454.88
  982.33  454.92  992.28  455.09 1004.31  455.08 1012.88  455.01 1070.64  454.59
 1077.93  454.55 1088.35  454.68 1131.47  454.37  1188.4  454.38  1197.7  454.41
 1240.42  454.73 1264.92  454.63 1291.12  454.73 1311.48  454.73 1345.34  454.81
 1378.71  454.66 1397.07   454.5 1455.32  454.64 1504.35  454.39  1546.9  454.23
 1602.25  454.84 1609.84  454.86 1638.05  454.52 1643.13  454.53 1687.26  454.38
 1710.54  454.34  1727.5  454.21 1772.01     454 1779.64  453.95 1831.59  453.63
 1881.16  453.71 1920.34  453.97 1947.51   454.2 1969.51  454.47  1984.8  454.81
 2008.14  455.74 2012.24   455.7 2020.43     456 2039.88     460 2059.17     461
 2062.09  460.48 2080.08  458.86 2091.05  457.92 2114.04  456.98 2139.95  456.14
 2149.28   455.8 2169.92  456.02 2185.94  456.17 2194.78  456.23 2231.81  456.49
 2257.93  457.29 2297.73  458.13 2307.22  458.35  2316.5  456.02 2318.87  455.46
 2322.94  455.03 2355.49  455.22 2361.01  454.79 2363.79  453.98 2369.42  452.91
 2383.93   453.5 2405.32  454.78 2418.57  455.54 2430.38  457.92 2436.47  457.92
 2438.99  457.74 2440.16  457.11 2445.03  455.91  2458.9     454 2497.63     454
 2514.97  456.51  2532.8  457.03 2546.48  457.23 2593.39  457.61 2658.31  458.22
 2698.62  458.08 3679.01  458.15 3687.51  458.06 3719.25  458.13 3743.67  456.64
 3755.12  455.76 3757.48  455.78    3769  455.77 3789.46  455.81 3799.68  456.33
 3819.13  457.14 3841.18   457.1  3871.2  456.74 3875.79  456.71 3898.64   456.7
 3908.42  456.66 3943.27  456.99 3946.22  457.01 3955.93  457.35 4236.42  457.45
 4240.32  457.12 4257.74  454.92 4259.26  454.69 4265.09  453.33 4268.14  452.61
  4271.7     452 5032.47     452 5033.47   452.2 5035.47  452.53 5036.47  452.66
 5040.47  453.21 5044.47  453.01 5047.47  453.35 5049.47     454 5051.47  455.65
 5051.47     456 5134.47  458.31 5178.47  459.35 5213.47     460 5245.47     462
 5412.89   462.1
BR U #Mann= 7
       0    .055  123.81     .05  214.09    .055  776.98     .05  905.97    .055
 4236.42     .03 5051.47     .06
BR U Banks=776.98,905.97
BC Design=,, 0 ,, 0 ,,,,,,
BC Use User HTab Curves=0
BC User HTab FreeFlow(D)= 0

Type RM Length L Ch R = 1 ,133696  ,307.27,78.95,87.43
BEGIN DESCRIPTION:
Embankment DS face-gis xsec 7724-right overbank from filed surveys 2015
END DESCRIPTION:
XS GIS Cut Line= 6
  2438549.278126 7060862.4278184 2438520.2903237 7059978.0791934
 2438457.4184022 7059768.7439822 2438254.5136243 7059418.6620051
 2437792.2944044 7058984.3899078     2434900.175     7057043.996
#Sta/Elev= 30
       0  457.56   69.85  456.95     100  448.26     124  448.26     135  456.22
  161.75  456.76     735  455.51  788.37     447     840  446.81     880     455
    1995     454  2113.6  455.53 2138.03     461 2390.37  453.28 2501.93  457.91
 2537.12     450 2806.57     450 2875.93  457.48 3034.07  459.43  4504.1   458.4
 4543.74     450 4647.14     450 4678.88  456.51  4763.6  458.91 5217.94  456.93
 5250.42  458.72 5258.41  464.19 5545.64  465.66 5581.11  466.99 5627.17  488.02
#Mann= 8 ,-1,0
       0    .055       0   69.85     .05       0  161.75    .055       0
     735     .05       0     880    .055       0 2138.03     .06       0
  4504.1     .03       0  4763.6     .06       0
#XS Ineff= 2 ,-1
    2520    2945     460    2945    5500     462
Permanent Ineff=
       F       F
#Block Obstruct= 2 ,-1
 4759.31 4875.17  460.87 4994.98 5097.29  460.87
Bank Sta=735,880
XS Rating Curve= 0 ,0
Exp/Cntr=0.5,0.3

Type RM Length L Ch R = 6 ,133000  ,,,
Lateral Weir Pos= 0
Lateral Weir End=Elm Fork        ,ef4             ,139890  ,
Lateral Weir Distance=0
Lateral Weir TW Multiple XS=0
Lateral Weir WD=5
Lateral Weir Coef=2.6
Lateral Weir Is ZeroHeight=-1
LW OverFlow Method 2D=0
LW OverFlow Use Velocity Into 2D=0
Lateral Weir WSCriteria=-1
Lateral Weir Flap Gates= 0
Lateral Weir Hagers EQN= 0 ,,,,,
Lateral Weir SS=0.05,0.05,
Lateral Weir Type= 0
Lateral Weir Connection Pos and Dist= 3 ,-318
Lateral Weir SE= 25
       0  460.26   10.83     460   45.15     460   52.74     459   56.93     458
   61.14     457   61.29  456.91  106.46  456.43  251.47  457.13     318   456.3
  384.84  454.71  431.32  453.25  498.15  453.47  532.49  454.61   610.3  454.85
  644.39  457.02   670.9  457.38     713  457.34  874.86  456.61  946.56  456.62
  1092.2  455.95 1302.29  457.26    1371  459.36 1430.83  460.57 1594.73  474.83
Lateral Weir Centerline= 0
Lateral Weir HW RS User Defined=-1
Lateral Weir HW RS Station=133696  ,0
Lateral Weir HW RS Station=132950  ,318
Lateral Weir HW RS Station=132912  ,713
Lateral Weir HW RS Station=132737  ,1371
Lateral Weir HW RS Station=132538  ,1595
LW Div RC= 0 ,False,,

Type RM Length L Ch R = 1 ,132950  ,357.03,96.83,76.43
BEGIN DESCRIPTION:
132950 new lidar gis xsec7645,  inef based on upstream embankment
This section is lined with rock rap rip in the graded portion.
END DESCRIPTION:
XS GIS Cut Line= 5
  2438856.738141 7060787.8131382 2438562.3522475 7059913.8404767
 2438303.5758621 7059454.7291902 2437799.8278539 7058974.4827754
     2434900.175     7057043.996
#Sta/Elev= 30
       0   456.3   30.94   456.5   70.63  447.95  108.48  456.63  732.75  455.67
  818.53     448  977.12  454.63 2073.58  453.49 2117.32  454.83 2137.43  460.77
 2190.06  456.23 2367.48  457.12 2389.77  453.28 2501.33  457.91 2536.52     450
 2805.97     450 2875.33  457.48 3033.47  459.43 4501.24   458.4 4543.14     450
 4646.54     450 4678.28  456.51    4763  458.91 5217.34  456.93 5249.82  458.72
 5257.81  464.19 5545.04  465.66 5580.51  466.99 5584.42  471.99 5626.57  488.02
#Mann= 8 ,-1,0
       0    .055       0   30.94    .045       0  108.48    .055       0
  732.75     .05       0  977.12    .055       0 2137.43     .06       0
 4501.24     .03       0    4763     .06       0
#XS Ineff= 2 ,-1
    2140    2945     459    2945    5500     462
Permanent Ineff=
       F       F
#Block Obstruct= 2 ,-1
 4758.71 4874.57  460.87 4994.38 5096.69  460.87
Bank Sta=732.75,977.12
XS Rating Curve= 0 ,0
Exp/Cntr=0.5,0.3

Type RM Length L Ch R = 1 ,132912  ,530.11,144.07,109.17
BEGIN DESCRIPTION:
New Lidar xsec gis 7548- right inef based on us embankment
END DESCRIPTION:
XS GIS Cut Line= 4
  2439174.835274 7060665.7277525 2438312.9213159 7059448.8883227
 2437806.6992312 7058965.9506402     2434900.175     7057043.996
#Sta/Elev= 30
       0  457.34   106.3   455.5  205.82   455.2   797.8  455.33  862.92  447.67
  984.06  446.09 1034.97   455.4 2101.56   453.1    2164  454.42 2190.81  460.72
 2236.63  456.23 2414.05  457.12 2436.34  453.28  2547.9  457.91 2583.09     450
 2852.54     450  2921.9  457.48 3080.04  459.43 4547.81   458.4 4589.71     450
 4693.11     450 4724.85  456.51 4809.57  458.91 5263.91  456.93 5296.39  458.72
 5304.38  464.19 5591.61  465.66 5627.08  466.99 5630.99  471.99 5673.14  488.02
#Mann= 8 ,-1,0
       0    .055       0   106.3    .045       0  205.82    .055       0
   797.8     .05       0 1034.97    .055       0 2190.81     .06       0
 4547.81     .03       0 4809.57     .06       0
#XS Ineff= 2 ,-1
    2200    2992     459    2992    5500     462
Permanent Ineff=
       F       F
#Block Obstruct= 2 ,-1
 4805.28 4921.14  460.87 5040.95 5143.26  460.87
Bank Sta=797.8,1034.97
XS Rating Curve= 0 ,0
Exp/Cntr=0.3,0.1

Type RM Length L Ch R = 1 ,132737  ,202.12,175.82,171.29
BEGIN DESCRIPTION:
New Lidar xsec gis 7404- inef at 610 based on upstream existing embankment
END DESCRIPTION:
XS GIS Cut Line= 5
  2439016.964527 7060032.1604501 2438582.7101464 7059686.6047107
 2438324.6030511 7059440.7108456 2437814.5286119 7058956.1986912
     2434900.175     7057043.996
#Sta/Elev= 30
       0  459.31  263.55   455.6  292.85  447.17  319.31     446  446.88     446
  491.19  454.62  576.18  449.44  896.55  448.77  991.76  454.27  1551.9  453.26
 1588.45  454.66 1609.23  460.98 1861.57  453.28 1973.13  457.91 2008.32     450
 2277.77     450 2347.13  457.48 2505.27  459.43 3973.04   458.4 4014.94     450
 4118.34     450 4150.08  456.51  4234.8  458.91 4689.14  456.93 4721.62  458.72
 4729.61  464.19 5016.84  465.66 5052.31  466.99 5056.22  471.99 5098.37  488.02
#Mann= 6 ,-1,0
       0    .055       0  263.55     .05       0  491.19    .055       0
 1609.23     .06       0 3973.04     .03       0  4234.8     .06       0
#XS Ineff= 2 ,-1
    1610    2417     459    2417 5098.37     462
Permanent Ineff=
       F       F
#Block Obstruct= 2 ,-1
 4230.51 4346.37  460.87 4466.18 4568.49  460.87
Bank Sta=263.55,491.19
XS Rating Curve= 0 ,0
Exp/Cntr=0.3,0.1

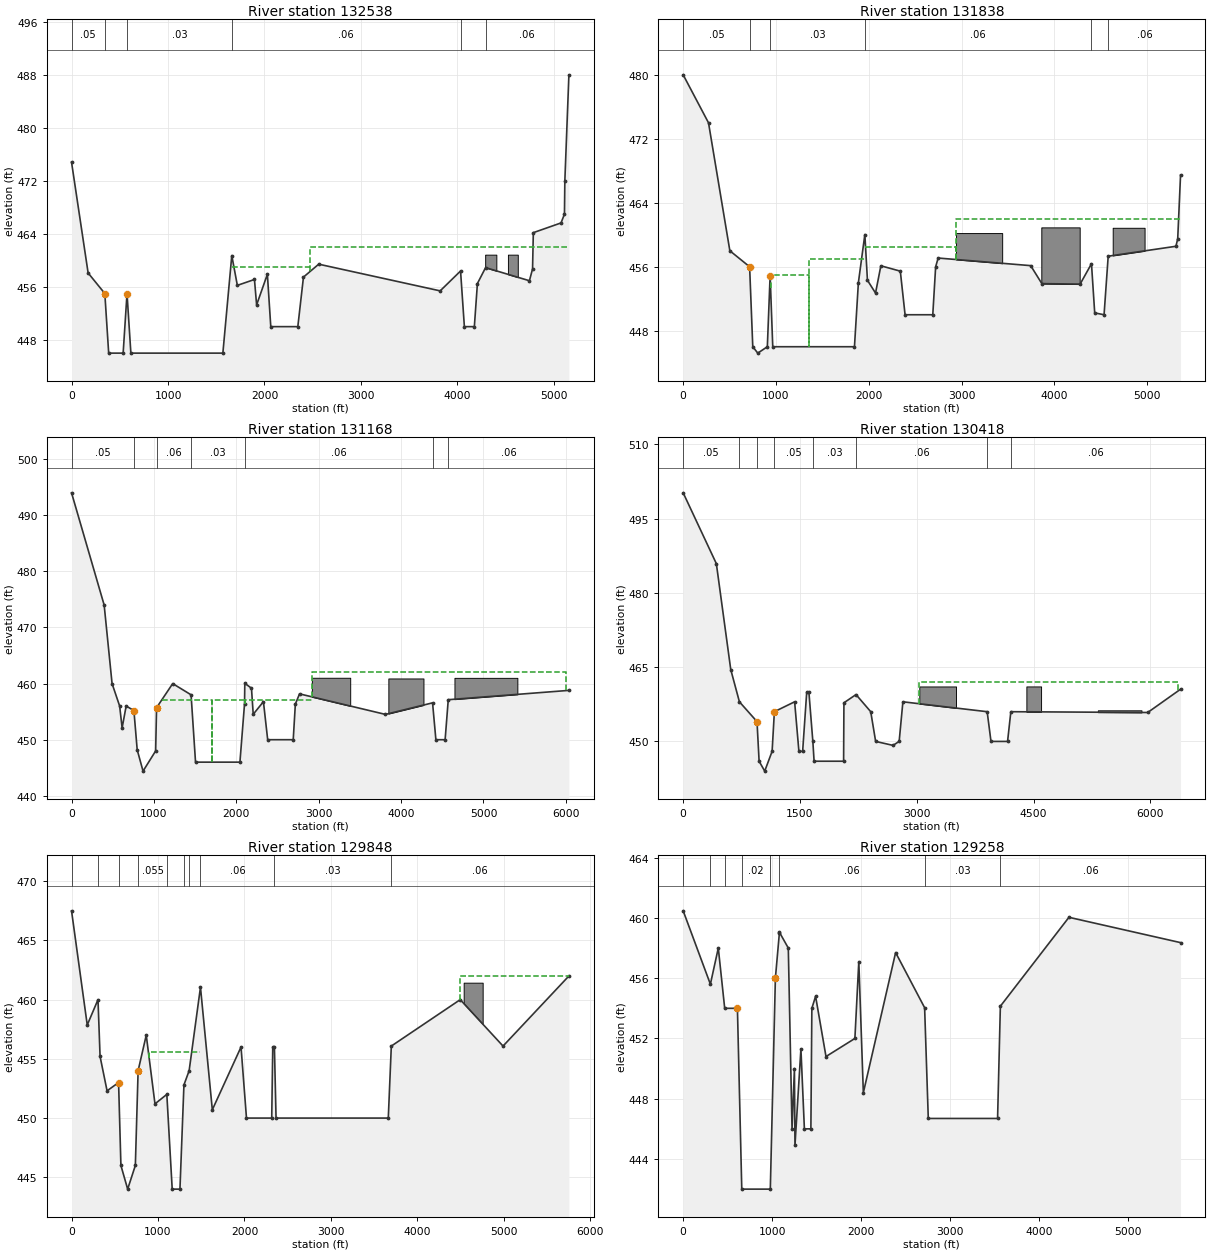
Type RM Length L Ch R = 1 ,132538  ,666.33,646.78,633.1
BEGIN DESCRIPTION:
132538-gis 7228 Normal pool 446
NOTE: Inef at 741 from Corp ROW existing embankment
NOTE: topo east of railroad tracks updated Feb 2002 by Freese & Nichols, Inc.
END DESCRIPTION:
XS GIS Cut Line= 3
  2439183.281123 7059910.8834616 2437824.6214395 7058943.0658435
     2434900.175     7057043.996
#Sta/Elev= 30
       0  474.83     172   458.1     345     455     385     446     535     446
     575     455     615     446  1568.5     446 1660.97  460.73 1718.57  456.23
 1895.99  457.12 1918.28  453.28 2029.84  457.91 2065.03     450 2345.38     450
 2403.84  457.48 2561.98  459.43 3820.77   455.4 4032.01   458.4 4071.65     450
 4175.05     450 4206.79  456.51 4291.51  458.91 4745.85  456.93 4778.33  458.72
 4786.32  464.19 5073.55  465.66 5109.02  466.99 5112.93  471.99 5155.08  488.02
#Mann= 6 ,-1,0
       0     .05       0     345     .05       0     575     .03       0
 1660.97     .06       0 4032.01     .03       0 4291.51     .06       0
#XS Ineff= 2 ,-1
    1660    2474     459    2474 5155.08     462
Permanent Ineff=
       F       F
#Block Obstruct= 2 ,-1
 4287.22 4403.08  460.87 4522.89  4625.2  460.87
Bank Sta=345,575
XS Rating Curve= 0 ,0
Exp/Cntr=0.5,0.3

Type RM Length L Ch R = 1 ,131838  ,663.78,673.18,689.22
BEGIN DESCRIPTION:
131838- inef at 1360 based on upstream existing embankment, linear channel n value changed from .03 to .05 based on image
n value changed to CDC 12/18/15
131838
NOTE: topo east of railroad tracks updated Feb 2002 by Freese & Nichols, Inc.
CDC model uses 0.5 for the channel and the warehouses blocked out in this model.
END DESCRIPTION:
XS GIS Cut Line= 5
 2439849.4293977 7059515.1680457 2438172.0928574  7058505.505695
  2438172.092857  7058505.505695 2437518.6748729 7058112.2338437
 2435259.9106896 7056746.8533724
#Sta/Elev= 30
       0     480     273     474     503     458     716     456     750     446
     804   445.2     907     446     937   454.9  965.33     446 1845.86     446
    1888     454 1957.77  460.03 1985.71  454.31 2072.87  452.71  2130.3  456.12
 2339.91  455.45 2391.28     450 2689.81     450 2720.66  455.99 2747.59  457.09
 3744.74  456.14 3865.28  453.89  4277.5  453.83    4400  456.38 4434.75  450.23
 4535.62     450 4580.08  457.32 5309.89  458.56 5329.27   459.5 5359.78  467.46
#Mann= 6 ,-1,0
       0     .05       0     716     .05       0     937     .03       0
 1957.77     .06       0    4400     .03       0 4580.08     .06       0
#XS Ineff= 4 ,-1
  941.88    1360     455    1360    1950     457    1960 2940.24   458.5
 2940.24 5359.78     462
Permanent Ineff=
       F       F       F       F
#Block Obstruct= 3 ,-1
 2940.24 3437.72 460.212 3859.28 4272.91 460.925 4628.58 4972.16 460.875
Bank Sta=716,937
XS Rating Curve= 0 ,0
Exp/Cntr=0.3,0.1

Type RM Length L Ch R = 1 ,131168  ,757.56,756.14,750.47
BEGIN DESCRIPTION:
131168-inef at 1710 based on upstream existing embankment, linear channel n value changed from .03 to .05 based on image
n values updated to CDC 12/18/15 BG
131168
NOTE: topo east of railroad tracks updated Feb 2002 by Freese & Nichols, Inc.
CDC model uses n=0.12 for large warehouses that are blocked out in this model. 12/18/15
END DESCRIPTION:
XS GIS Cut Line= 4
 2440199.9040905 7059031.0981477  2438499.669302 7057793.3168307
  2438499.874026 7057791.9687362 2435318.6769763 7055477.5357011
#Sta/Elev= 30
       0     494     396     474     492     460     584     456     614   452.1
     663     456     757   455.2     797   448.2     868   444.4    1021     448
    1032   455.7    1228     460    1451     458 1505.11     446    2044     446
    2100  456.42 2103.07  460.06 2184.18  459.17 2205.26  454.53 2329.23  456.78
 2380.87     450 2690.95     450 2716.66  456.34 2767.36  458.17 3810.06  454.51
 4382.11  456.57 4422.49     450  4534.6     450 4572.64  457.13  6037.1  458.79
#Mann= 7 ,-1,0
       0     .05       0     757     .05       0    1032     .06       0
    1451     .03       0 2103.07     .06       0 4382.11     .03       0
 4572.64     .06       0
#XS Ineff= 4 ,-1
    1100    1710     457    1710    2100     457    2100 2916.79     457
 2916.79    6000     462
Permanent Ineff=
       F       F       F       F
#Block Obstruct= 3 ,-1
 2916.79 3382.65 461.042 3845.55 4271.83 460.915 4647.84 5411.58 461.026
Bank Sta=757,1032
XS Rating Curve= 0 ,0
Exp/Cntr=0.3,0.1

Type RM Length L Ch R = 1 ,130418  ,570.32,569.38,569.31
BEGIN DESCRIPTION:
130418 linear channel n value changed from .03 to .05 based on image
NOTE: topo east of railroad tracks updated Feb 2002 by Freese & Nichols, Inc.
END DESCRIPTION:
XS GIS Cut Line= 4
 2440739.2976967 7058457.3971954 2438909.8577861 7057201.1398654
  2438909.857786 7057201.1398654  2435473.013938 7054844.9454308
#Sta/Elev= 30
       0   500.2     426   485.9     611   464.5     722     458     948     454
     975     446    1047     444    1142     448    1171     456    1431     458
    1486     448    1534     448    1586   459.9    1614     460    1665     450
 1681.01     446    2060     446    2064   457.8 2219.24  459.46 2408.24     456
 2471.24     450 2694.24   449.2 2773.24     450 2821.24     458 3903.24     456
 3952.24     450 4165.24     450 4207.24     456 5964.63  455.84  6386.2  460.54
#Mann= 8 ,-1,0
       0     .05       0     722     .06       0     948     .03       0
    1171     .05       0    1665     .03       0 2219.24     .06       0
 3903.24     .03       0 4207.24     .06       0
#XS Ineff= 2 ,-1
 2219.24 3031.86  456.84 3031.86    6350     462
Permanent Ineff=
       F       F
#Block Obstruct= 3 ,-1
 3031.86 3503.32 461.099 4406.69 4595.48 461.104 5324.05 5884.76 456.281
Bank Sta=948,1171
XS Rating Curve= 0 ,0
Exp/Cntr=0.3,0.1

Type RM Length L Ch R = 1 ,129848  ,587.39,588.53,586.79
BEGIN DESCRIPTION:
129848- linear channel n value changed from .03 to .05 based on image
NOTE: topo east of railroad tracks updated Feb 2002 by Freese & Nichols, Inc.
END DESCRIPTION:
XS GIS Cut Line= 4
 2440710.7078589 7057742.6532181 2439476.5505503 7056905.8409153
  2439477.235916 7056905.6450496 2435950.4463821 7054514.9893978
#Sta/Elev= 30
       0   467.5  181.67  457.86     306     460     330   455.2     411   452.3
     544     453     571     446     649     444     738     446     770     454
     864     457     965   451.2 1101.96     452  1164.2     444  1253.8     444
 1299.89   452.8    1360     454 1491.11  461.05 1628.11   450.7 1960.11     456
 2023.11     450 2315.11     450 2327.11     456 2346.11     456 2365.11     450
 3663.11     450 3698.11  456.08 4495.11     460 4990.11  456.08  5751.8     462
#Mann= 10 ,-1,0
       0     .05       0     306     .06       0     544     .03       0
     770    .055       0 1101.96     .03       0 1299.89    .055       0
    1360     .03       0 1491.11     .06       0 2346.11     .03       0
 3698.11     .06       0
#XS Ineff= 4 ,-1
   11.23  311.24 458.178  897.69  1488.8 455.599 1491.11    4495  455.27
    4495  5751.8     462
Permanent Ineff=
       F       F       F       F
#Block Obstruct= 1 ,-1
 4534.69 4754.44 461.434
Bank Sta=544,770
XS Rating Curve= 0 ,0
Exp/Cntr=0.3,0.1

Type RM Length L Ch R = 1 ,129258  ,524.18,527.87,522.14
BEGIN DESCRIPTION:
129258- ROB pond n=.02 changed to n=.03 es jan2016
NOTE: topo east of railroad tracks updated Feb 2002 by Freese & Nichols, Inc.
END DESCRIPTION:
XS GIS Cut Line= 4
 2441051.8787645 7057262.3454516 2440154.1515573 7056658.0504004
  2440156.413691 7056656.4926607 2436412.6314813 7054139.4875241
#Sta/Elev= 30
       0  460.47     306   455.6     395     458     467     454     610     454
     659     442     980     442    1037     456 1082.17  459.01 1082.17  459.05
 1182.17     458 1224.17     446 1251.17     450 1257.17   444.9 1324.17   451.3
 1363.17     446 1436.17     446 1447.17     454 1489.17   454.8 1606.17   450.8
 1931.17     452 1975.17   457.1 2026.17   448.4 2389.17   457.7 2715.28  454.04
 2756.53  446.69 3535.77  446.69 3567.11  454.14 4338.39  460.04  5593.4  458.36
#Mann= 8 ,-1,0
       0     .05       0     306     .06       0     467     .03       0
     659     .02       0     980     .03       0 1082.17     .06       0
 2715.28     .03       0 3567.11     .06       0
#XS Ineff= 1 ,-1
 1082.17 2382.17  456.05
Permanent Ineff=
       F
Bank Sta=610,1037
XS Rating Curve= 0 ,0
Exp/Cntr=0.5,0.3

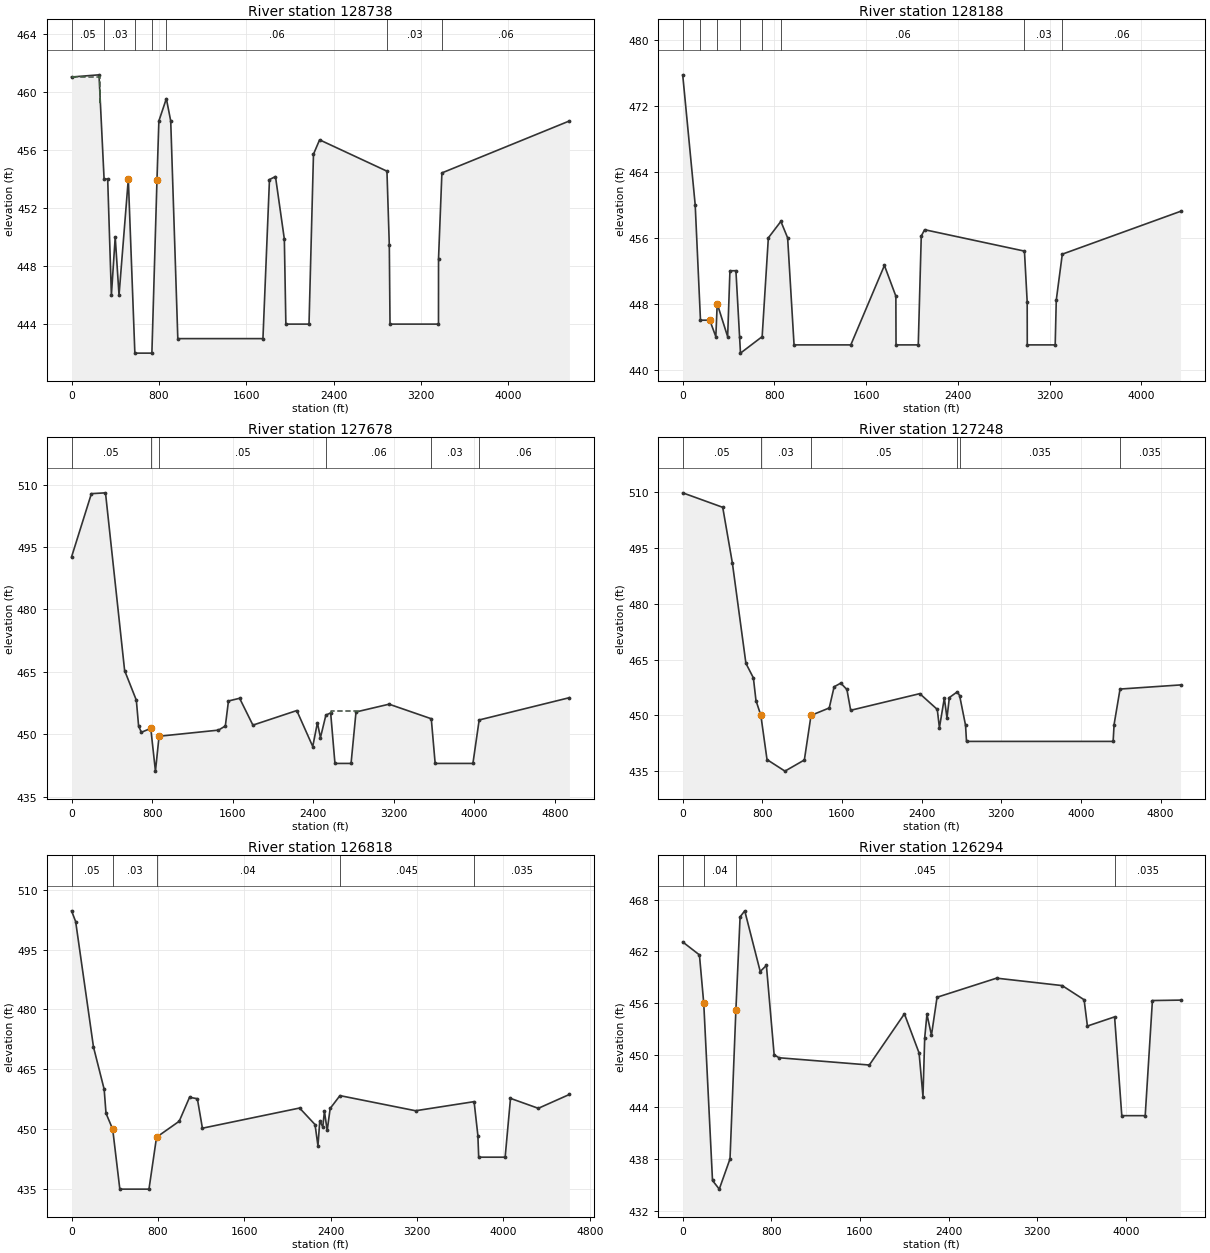
Type RM Length L Ch R = 1 ,128738  ,504.83,546.51,475.07
BEGIN DESCRIPTION:
128738-ROB pond n=.02 changed to n=.03 es jan2016  left overbank changed to .05
128738
NOTE: topo east of railroad tracks updated Feb 2002 by Freese & Nichols, Inc.
END DESCRIPTION:
XS GIS Cut Line= 4
 2441263.4429739 7056768.6958484 2440538.7442921 7056289.8667536
   2440539.62946 7056288.6206931 2437460.8081907 7054249.9682743
#Sta/Elev= 30
       0  461.03   251.5  461.18     298     454     331     454     365     446
     400     450     435     446     520     454     580     442     736     442
  782.53  453.91     800     458  868.55  459.54  908.55     458  973.55     443
 1753.55     443  1813.3  453.96 1868.36  454.17 1949.54  449.86 1963.55     444
 2175.65     444 2216.56  455.71 2272.55   456.7 2889.72  454.54 2911.34  449.42
 2917.81     444 3361.89     444 3362.28  448.51 3393.22  454.42 4561.14     458
#Mann= 7 ,-1,0
       0     .05       0     298     .03       0     580     .02       0
     736     .03       0  868.55     .06       0 2889.72     .03       0
 3393.22     .06       0
#XS Ineff= 2 ,-1
       0  264.31 461.032  874.32 2252.33 454.287
Permanent Ineff=
       F       F
Bank Sta=520,782.53
XS Rating Curve= 0 ,0
Exp/Cntr=0.3,0.1

Type RM Length L Ch R = 1 ,128188  ,539.15,520.5,519.99
BEGIN DESCRIPTION:
128188 -ROB pond n=.02 changed to n=.03 es jan2016
NOTE: topo east of railroad tracks updated Feb 2002 by Freese & Nichols, Inc.
CDC has n=0.5 for overbank and n=0.35 for channel
END DESCRIPTION:
XS GIS Cut Line= 4
 2441463.3553037 7056327.7551292  2440746.263234 7055860.3538331
  2440746.761264 7055859.0533107 2437825.6604794 7053956.7018005
#Sta/Elev= 30
       0   475.8     109     460     155     446     236     446     289     444
     301     448     392     444     412     452  464.19  452.01     496     444
     504     442     693     444     747     456  856.26     458  915.26     456
  971.26     443 1466.26     443 1759.42  452.65 1859.24  448.92 1860.71     443
 2054.62     443 2080.83  456.22 2110.04  456.99 2980.84  454.39 3004.78   448.2
 3005.45     443 3249.03     443 3258.39  448.44 3311.04  454.02  4342.2  459.22
#Mann= 8 ,-1,0
       0     .05       0     155     .07       0     301     .03       0
     496     .02       0     693     .03       0  856.26     .06       0
 2980.84     .03       0 3311.04     .06       0
#XS Ineff= 1 ,-1
  856.26 2110.26  456.22
Permanent Ineff=
       F
Bank Sta=236,301
XS Rating Curve= 0 ,0
Exp/Cntr=0.3,0.1

Type RM Length L Ch R = 1 ,127678  ,460.35,434.56,444.55
BEGIN DESCRIPTION:
n updated to CDC 12/18/15
127678
NOTE: topo east of railroad tracks updated Feb 2002 by Freese & Nichols, Inc.
END DESCRIPTION:
XS GIS Cut Line= 4
 2442318.9552986 7056267.6732284 2440908.5811508 7055375.7580175
  2440183.811603 7054919.2487599 2438139.6168725 7053628.2621687
#Sta/Elev= 30
       0   492.6     197   507.8     337     508     527   465.3  643.31  458.18
  665.73  451.97   693.5  450.48  786.54  451.42  832.95  441.15  868.85  449.53
    1459     451    1527     452    1558     458 1668.73  458.65 1800.63   452.2
 2236.34   455.7  2394.9  447.06  2441.1  452.77 2471.41   449.2 2525.29   454.6
 2572.75  455.14 2615.29     443 2775.29     443 2824.39  455.36 3152.88  457.23
 3571.86  453.73 3610.29     443 3985.29     443 4047.34  453.44 4943.01  458.79
#Mann= 6 ,-1,0
       0     .05       0  786.54     .03       0  868.85     .05       0
 2525.29     .06       0 3571.86     .03       0 4047.34     .06       0
#XS Ineff= 1 ,-1
 2571.72 2853.25   455.5
Permanent Ineff=
       F
Bank Sta=786.54,868.85
XS Rating Curve= 0 ,0
Exp/Cntr=0.3,0.1

Type RM Length L Ch R = 1 ,127248  ,447.37,459.41,453.01
BEGIN DESCRIPTION:
n updated to CDC 12/18/15 BG
127248
NOTE: topo east of railroad tracks updated Feb 2002 by Freese & Nichols, Inc.
XS is a pond until ROB which is multifamily residential.12/18/15.
END DESCRIPTION:
XS GIS Cut Line= 4
 2442728.5315791 7056008.1120677 2441388.6087341 7055177.4040835
  2440382.105825 7054557.0782244 2438475.3816209 7053377.9559107
#Sta/Elev= 30
       0   509.9     402     506     499     491     635     464     710   460.1
     736     454     785     450     847   438.1    1027     435    1222     438
    1289     450    1472     452    1521   457.7 1587.51  458.68 1649.51  456.97
  1687.1  451.37  2381.2  455.85 2557.22  451.61 2578.67  446.66 2628.12  454.66
 2654.77  449.33 2678.71  454.81 2758.84  456.35 2781.76  455.32 2841.15  447.34
 2850.84     443 4323.84     443 4333.33  447.54 4393.19  457.09  5000.7   458.2
#Mann= 6 ,-1,0
       0     .05       0     785     .03       0    1289     .05       0
 2758.84    .035       0 2781.76    .035       0 4393.19    .035       0
Bank Sta=785,1289
XS Rating Curve= 0 ,0
Exp/Cntr=0.3,0.1

Type RM Length L Ch R = 1 ,126818  ,550.96,524.39,586.6
BEGIN DESCRIPTION:
126818
NOTE: topo east of railroad tracks updated Feb 2002 by Freese & Nichols, Inc.
n value reflects CDC 12/18/15 BG
END DESCRIPTION:
XS GIS Cut Line= 4
 2442734.4301894 7055501.7367681 2441806.3270587 7054925.2799158
  2440623.169976 7054190.4057294 2438818.0184028 7053069.5713569
#Sta/Elev= 30
       0   504.7      38     502     203   470.6     302     460     319     454
     381     450     447     435     717     435     787     448     997     452
 1092.56     458 1165.04  457.64 1211.86  450.26 2111.86  455.31 2254.75  451.17
  2281.8  445.85 2298.71  452.06 2326.64  450.58 2341.82  454.49  2367.4  449.69
 2394.92   455.2 2485.35  458.42 3185.88  454.63 3727.83  456.91 3762.89  448.41
 3770.35     443 4015.35     443  4064.9  457.73 4322.47  455.24 4610.17  458.71
#Mann= 5 ,-1,0
       0     .05       0     381     .03       0     787     .04       0
 2485.35    .045       0 3727.83    .035       0
Bank Sta=381,787
XS Rating Curve= 0 ,0
Exp/Cntr=0.3,0.1

Type RM Length L Ch R = 1 ,126294  ,9.13,12.75,17.92
BEGIN DESCRIPTION:
126293
NOTE: topo east of railroad tracks updated Feb 2002 by Freese & Nichols, Inc.
END DESCRIPTION:
XS GIS Cut Line= 3
      2442866.03     7055134.711      2442335.62      7054730.36
     2439057.304     7052748.887
#Sta/Elev= 30
       0   463.1     151   461.6     190     456     269   435.5     330   434.5
     427     438     480   455.2     518     466     560   466.7  699.77  459.68
  755.44  460.39  825.46  450.03  869.98   449.7 1684.53  448.86 2001.25  454.78
 2133.77  450.25 2168.81  445.21 2184.42     452 2204.69  454.73  2245.4  452.31
 2295.91   456.7 2833.33  458.91 3425.42  458.05 3623.26  456.41 3653.05  453.37
 3898.51  454.43 3963.45     443 4174.81     443 4239.88  456.32 4493.63  456.37
#Mann= 4 ,-1,0
       0    .045       0     190     .04       0     480    .045       0
 3898.51    .035       0
Bank Sta=190,480
XS Rating Curve= 0 ,0
Exp/Cntr=0.5,0.3

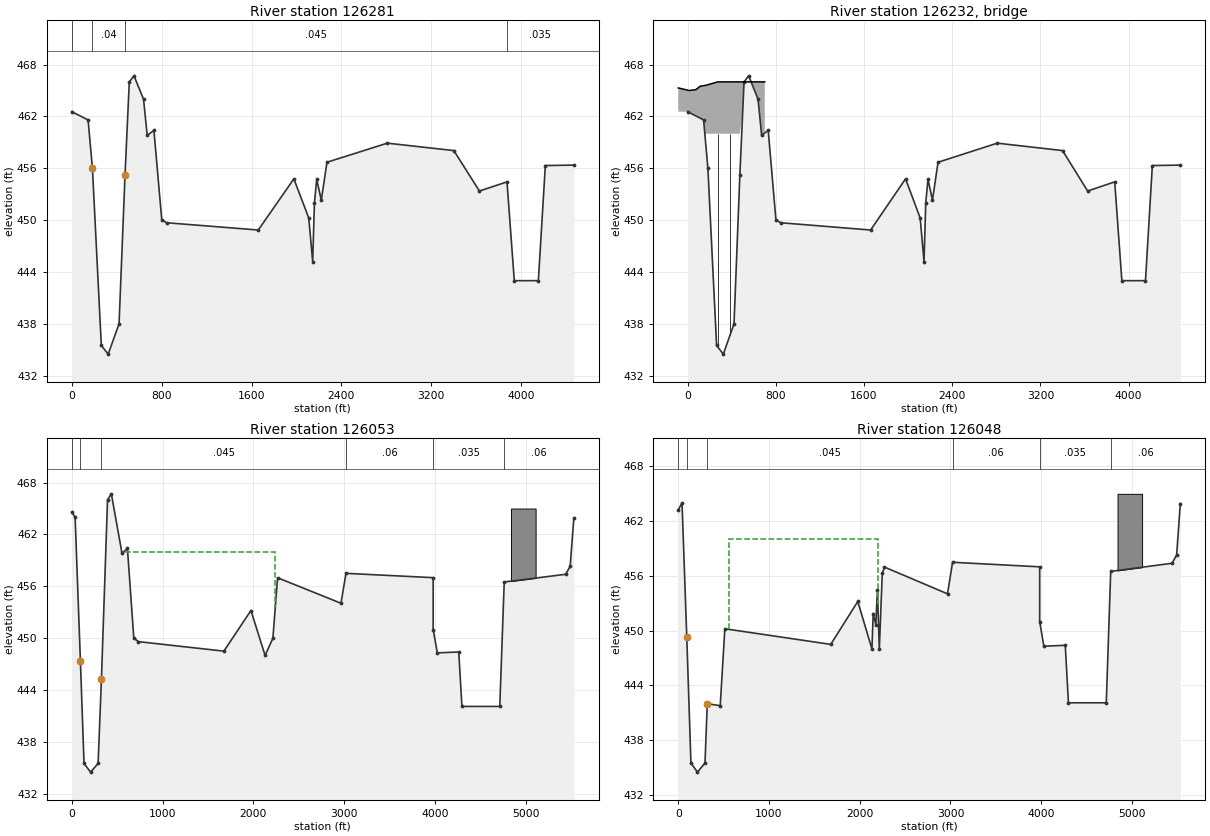
Type RM Length L Ch R = 1 ,126281  ,188.63,228.43,238.43
BEGIN DESCRIPTION:
126292
NOTE: topo east of railroad tracks updated Feb 2002 by Freese & Nichols, Inc.
END DESCRIPTION:
XS GIS Cut Line= 3
     2443009.446     7054994.521      2442335.62      7054730.36
     2439057.304     7052748.887
#Sta/Elev= 30
       0  462.55     145   461.6     184     456     263   435.5     324   434.5
     421     438     474   455.2     512     466     554   466.7  638.81     464
  671.56  459.81  731.23  460.39  801.25  450.03  845.77   449.7 1660.32  448.86
 1977.04  454.78 2109.56  450.25  2144.6  445.21 2160.21     452 2180.48  454.73
 2221.19  452.31  2271.7   456.7 2809.12  458.91 3401.21  458.05 3628.84  453.37
  3874.3  454.43 3939.24     443 4153.48     443 4215.67  456.32 4469.42  456.37
#Mann= 4 ,-1,0
       0    .045       0     184     .04       0     474    .045       0
  3874.3    .035       0
Bank Sta=184,474
XS Rating Curve= 0 ,0
Exp/Cntr=0.5,0.3

Type RM Length L Ch R = 3 ,126232  ,,,
BEGIN DESCRIPTION:
Hebron Parkway
END DESCRIPTION:
Node Name=Hebron Parkway
Bridge Culvert--1,0,-1,-1, 0
Deck Dist Width WeirC Skew NumUp NumDn MinLoCord MaxHiCord MaxSubmerge Is_Ogee
1,118,2.6,0, 13, 13, , , 0.95, 0, 0,0,,
     -85      15      75     115     165     165     274   276.5     384   386.5
     500     500     700
   465.3     465   465.1   465.5   465.6   465.6     466     466     466     466
     466     466     466
                                             460     460     460     460     460
     460
    -303    -203    -143    -103     -53     -53      56    58.5     166   168.5
     382     382     582
   465.3     465   465.1   465.5   465.6   465.6     466     466     466     466
     466     466     466
                                             460     460     460     460     460
     460
Pier Skew, UpSta & Num, DnSta & Num=  ,275.25, 2 ,175.25, 2 , 0 , 0 , 0 ,,
     2.5     2.5
       0     461
     2.5     2.5
       0     461
Pier Skew, UpSta & Num, DnSta & Num=  ,385.25, 2 ,285.25, 2 , 0 , 0 , 0 ,,
     2.5     2.5
       0     461
     2.5     2.5
       0     461
BR Coef=-1 , 0 , 0 ,, 0 ,,,0.8,-1,,1,
WSPro=,,,, 1 ,,,, 0 ,,,, 0 ,,,,-1 ,-1 ,-1 , 0 , 0 , 0 , 0 , 0
BC Design=,, 0 ,, 0 ,,,,,,
BC HTab HWMax=465.84
BC Use User HTab Curves=0
BC User HTab FreeFlow(D)= 0

Type RM Length L Ch R = 1 ,126053  ,5.12,5.17,4.82
BEGIN DESCRIPTION:
126172
NOTE: topo east of railroad tracks updated Feb 2002 by Freese & Nichols, Inc.
LOB and ROB changed to 0.6 to reflect development. n=0.35 in CDC for the whole cross section. 12/18/1
END DESCRIPTION:
XS GIS Cut Line= 4
 2443033.2461928 7054832.8365312 2441097.8901554 7053621.0341647
  2440475.473421  7053222.055632  2438362.303435 7051867.4828818
#Sta/Elev= 30
       0  464.58      37     464      95   447.4     135   435.5     207   434.5
     290   435.5     327   445.3     394     466     436   466.7  553.56  459.81
  613.23  460.39  683.25  450.03     732   449.6    1676   448.5    1974   453.2
    2130     448    2216     450 2267.18  456.99  2965.8  454.04 3021.51   457.5
 3981.51     457 3981.51     451 4027.51   448.3 4263.51   448.4 4298.51   442.1
 4715.51   442.1 4764.51   456.5 5440.76  457.39 5491.06   458.3 5531.56  463.92
#Mann= 6 ,-1,0
       0    .045       0      95     .03       0     327    .045       0
 3021.51     .06       0 3981.51    .035       0 4764.51     .06       0
#XS Ineff= 1 ,-1
  585.53 2242.41     460
Permanent Ineff=
       F
#Block Obstruct= 1 ,-1
 4839.55 5110.31     465
Bank Sta=95,327
XS Rating Curve= 0 ,0
Exp/Cntr=0.5,0.3

Type RM Length L Ch R = 1 ,126048  ,68.85,734.66,279.63
BEGIN DESCRIPTION:
126171
NOTE: topo east of railroad tracks updated Feb 2002 by Freese & Nichols, Inc.
LOB and ROB changed to 0.6 to reflect development. n=0.35 in CDC for the whole cross section. 12/18/1
END DESCRIPTION:
XS GIS Cut Line= 4
 2443035.8977623 7054828.5973664 2441179.8256871 7053667.6170768
  2440475.473421  7053222.055632  2438362.303435 7051867.4828818
#Sta/Elev= 30
       0  463.24      42     464      94   449.3     140   435.5     212   434.5
     295   435.5     320     442  462.81  441.78   513.8  450.21    1681   448.5
    1979   453.2    2135     448 2148.96  451.87 2177.58  450.66 2195.44  454.42
 2216.24  447.97  2248.8  456.27 2273.31  456.97 2968.04  454.04 3023.75   457.5
 3983.75     457 3983.75     451 4029.75   448.3 4265.75   448.4 4300.75   442.1
 4717.75   442.1 4766.75   456.5    5443  457.39  5493.3   458.3  5533.8  463.92
#Mann= 6 ,-1,0
       0    .045       0      94     .03       0     320    .045       0
 3023.75     .06       0 3983.75    .035       0 4766.75     .06       0
#XS Ineff= 1 ,-1
   555.1 2200.09     460
Permanent Ineff=
       F
#Block Obstruct= 1 ,-1
 4841.79 5112.55     465
Bank Sta=94,320
XS Rating Curve= 0 ,0
Exp/Cntr=0.5,0.3

River Reach=Elm Fork        ,ef6
Reach XY= 30
2436799.505379477071677.498051732436765.235434897071646.50172265
2436750.237761477071596.998212722436777.978191557071512.00822523
2436798.261943647071293.510958812436762.725925487071116.47161473
2436766.743633977071027.476057812436735.739430897070959.01523672
 2436798.52244187070728.51012032 2436891.51635037070620.98572905
2437008.74774313 7070574.01666292437091.517262647070498.48991106
2437137.00962572 7070411.50123992437179.00822939 7070384.4816089
2437406.502853147070081.473684732437492.500384557069914.98812531
2437653.224800637069696.525963812437707.244705727069662.48436522
2437875.497321967069480.974229562437970.519769717069418.01011665
2438095.724899897069180.488281982438106.24751663 7068659.9811209
2438138.497452147068547.975767482438198.477975227068433.01996064
2438330.742146397068310.518893322438669.008530217068144.97526114
2438969.979056887067789.986141732439327.999994387067429.97734731
2439638.733952977067163.52020305 2439781.73808557066985.48846395