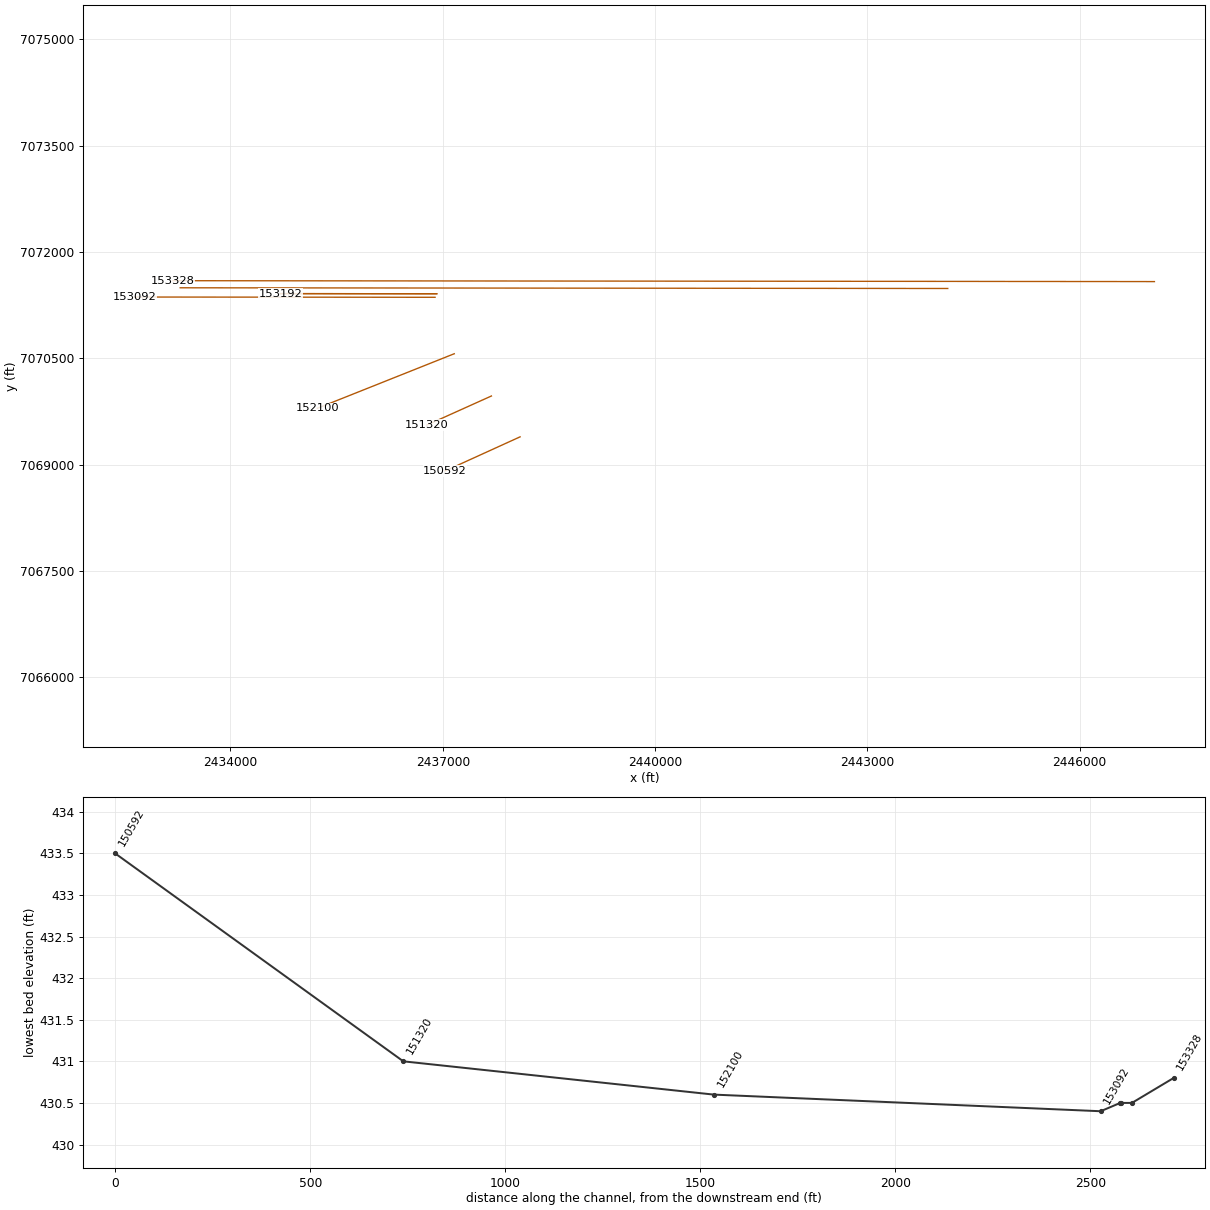
HEC-RAS study CDC_Consolidated_Model.prj: Upper Trinity CDC Consolidated Model

--- CDC_Consolidated_Model.g13 (geometry) --- (continued)

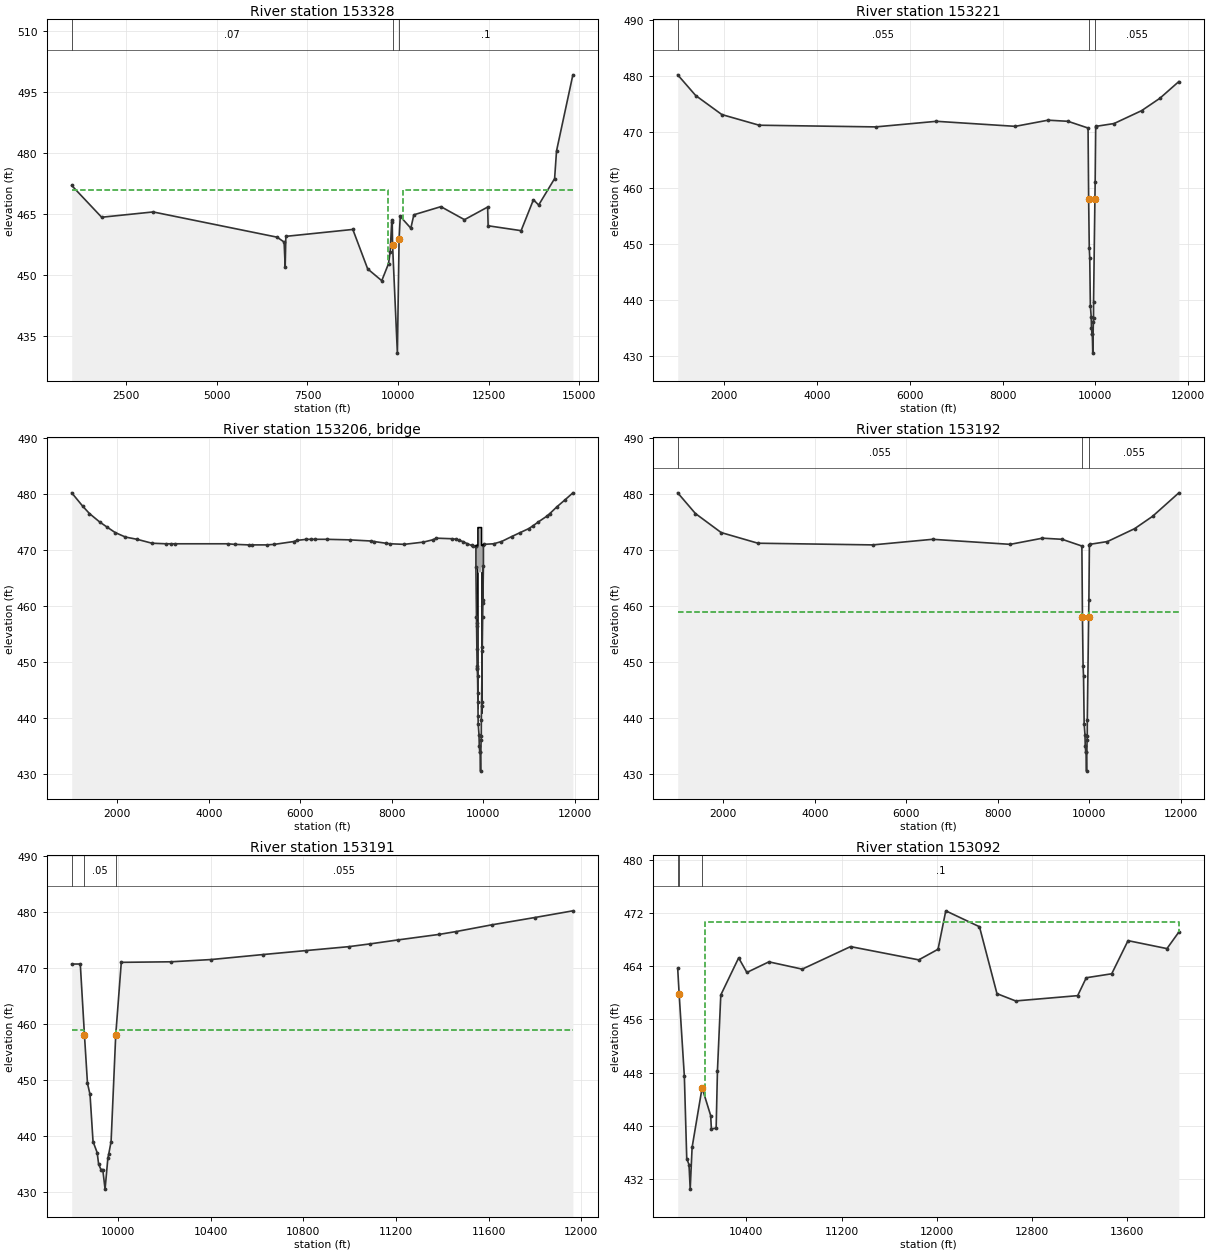
Type RM Length L Ch R = 1 ,153328  ,107,107,107
BEGIN DESCRIPTION:
153328
Cross-section EF182.  108 feet upstream of Atchinson, Topeka, and Sante Fe Railroad.  Lewisville Dam at river sta 158878, river mile 30.09.  Effective flow limit set at sta 9710 in LOB, at sta 10060 in ROB. Channel data from USACOE Elm Fork channel survey.
END DESCRIPTION:
XS GIS Cut Line= 4
 2447057.3897572 7071581.4986455 2445859.3902517 7071582.5871795
 2445728.7106181 7071582.70591852433186.903780797071594.10173616
#Sta/Elev= 30
    1000     472    1825   464.2    3245   465.5    6664   459.3    6857   458.1
    6887     452    6905   459.5    8752   461.2    9162   451.5    9550   448.6
    9737   452.8    9781   455.6    9827   463.4    9839   463.1    9848   457.4
    9981   430.8   10028   458.8   10060   464.4   10352   461.5   10435   464.8
   11181   466.8   11831   463.6   12470   466.7   12484   462.1   13393   460.9
   13733   468.5   13877   467.2   14317   473.7   14370   480.5   14821   499.2
#Mann= 3 ,-1,0
    1000     .07       0    9848     .05       0   10028      .1       0
#XS Ineff= 2 , 0
            9735     471   10146             471
Permanent Ineff=
       F       F
Bank Sta=9848,10028
XS Rating Curve= 0 ,0
Exp/Cntr=0.5,0.3

Type RM Length L Ch R = 1 ,153221  ,29,29,29
BEGIN DESCRIPTION:
153221-US RR
END DESCRIPTION:
XS GIS Cut Line= 2
 2444136.8801618 7071484.15241072433289.495600997071494.00860056
#Sta/Elev= 30
    1000   480.2    1388   476.5    1952   473.1    2756   471.2    5267   470.9
    6575   471.9    8275     471    8980   472.1    9410   471.9  9842.4   470.7
    9855     458  9868.5  449.31    9879   447.4    9892     439    9910     437
    9916     435    9926     434    9934     434    9944   430.5    9956     436
    9960   436.8    9961  439.63    9990     458  9995.5     461 10006.8   470.9
   10014     471   10402   471.5   10996   473.8   11388     476   11799     479
#Mann= 3 ,0,0
    1000    .055       0    9855     .05       0    9990    .055       0
#XS Ineff= 2 , 0
            9785     470   10040             470
Permanent Ineff=
       F       F
Bank Sta=9855,9990
XS Rating Curve= 0 ,0
Exp/Cntr=0.5,0.3

Type RM Length L Ch R = 3 ,153206  ,,,
BEGIN DESCRIPTION:
Atchinson, Topeka, and Santa Fe Railroad
Data from bridge plans.  Minimum low chord elev. 466.0.
END DESCRIPTION:
Node Name=ATSF Railroad
Bridge Culvert--1,0,-1,-1, 0
Deck Dist Width WeirC Skew NumUp NumDn MinLoCord MaxHiCord MaxSubmerge Is_Ogee
2,26,2.6,0, 18, 18, , , 0.95, 0, ,,,
  9842.4  9856.5  9857.5  9870.5  9871.5    9886    9886    9886    9890    9961
    9965    9966    9966  9980.5  9981.5  9994.5  9995.5 10006.8
   470.7  470.74  470.74  470.77  470.77   470.8     474     474     474     474
     474     474   470.8  470.86  470.86  470.92  470.92   470.9
  466.92  466.94  466.94  466.97  466.97     467     466     466     466     466
     466     466     467  467.03  467.03  467.06  467.06   467.1
  9842.4  9856.5  9857.5  9870.5  9871.5    9886    9886    9886    9890    9961
    9965    9966    9966  9980.5  9981.5  9994.5  9995.5 10006.8
   470.7  470.74  470.74  470.77  470.77   470.8     474     474     474     474
     474     474   470.8  470.86  470.86  470.92  470.92   470.9
  466.92  466.94  466.94  466.97  466.97     467     466     466     466     466
     466     466     467  467.03  467.03  467.06  467.06   467.1
Pier Skew, UpSta & Num, DnSta & Num=  ,9857, 2 ,9857, 2 , 0 , 0 , 0 ,,
       1       1
     435     469
       1       1
     435     469
Pier Skew, UpSta & Num, DnSta & Num=  ,9871, 2 ,9871, 2 , 0 , 0 , 0 ,,
       1       1
     435     469
       1       1
     435     469
Pier Skew, UpSta & Num, DnSta & Num=  ,9888, 2 ,9888, 2 , 0 , 0 , 0 ,,
       4       4
     435     469
       4       4
     435     469
Pier Skew, UpSta & Num, DnSta & Num=  ,9963, 2 ,9963, 2 , 0 , 0 , 0 ,,
       4       4
     435     469
       4       4
     435     469
Pier Skew, UpSta & Num, DnSta & Num=  ,9981, 2 ,9981, 2 , 0 , 0 , 0 ,,
       1       1
     435     469
       1       1
     435     469
Pier Skew, UpSta & Num, DnSta & Num=  ,9995, 2 ,9995, 2 , 0 , 0 , 0 ,,
       1       1
     435     469
       1       1
     435     469
BR Coef= 1 , 0 , 0 ,1.05, 0 ,,,0.8,-1,0.5,1,
WSPro=,,,, 1 ,,,, 0 ,,,, 0 ,,,,-1 ,-1 ,-1 , 0 , 0 , 0 , 0 , 0
BR U #Sta/Elev= 85
    1000   480.2    1242   477.8    1388   476.5    1611     475    1770   474.1
    1952   473.1    2176   472.3    2430   471.9    2756   471.2    3063   471.1
    3161   471.1    3256   471.1    4410   471.1    4562     471    4881   470.9
    4944   470.9    5267   470.9    5436     471    5856   471.5    5925   471.7
    6136   471.9    6229   471.9    6315   471.9    6575   471.9    7081   471.8
    7538   471.6    7617   471.5    7872   471.2    7965   471.1    8275     471
    8694   471.4    8893   471.8    8980   472.1    9323     472    9410   471.9
    9481   471.7    9560   471.5    9657   471.1    9750   470.8    9780   470.7
    9837   470.7  9842.4   470.7  9842.4   466.9    9855     458  9856.5  457.01
  9857.5   456.4  9863.5  452.38  9868.5  449.31  9870.5  448.95  9871.5  448.76
    9879   447.4  9883.5  444.49    9886  442.88    9890  440.29    9892     439
    9910     437    9916     435    9926     434    9934     434    9944   430.5
    9956     436    9960   436.8    9961  439.63    9965  442.17    9966   442.8
  9980.5  451.98  9981.5  452.62    9990     458  9994.5  460.44  9995.5     461
 10006.8   467.1 10006.8   470.9   10014     471   10230   471.1   10402   471.5
   10628   472.4   10811   473.1   10996   473.8   11089   474.3   11208     475
   11388     476   11460   476.5   11614   477.7   11799     479   11964   480.2
BR U #Mann= 3
    1000    .055    9855     .05    9990    .055
BR U Banks=9855,9990
BR D #Sta/Elev= 85
    1000   480.2    1242   477.8    1388   476.5    1611     475    1770   474.1
    1952   473.1    2176   472.3    2430   471.9    2756   471.2    3063   471.1
    3161   471.1    3256   471.1    4410   471.1    4562     471    4881   470.9
    4944   470.9    5267   470.9    5436     471    5856   471.5    5925   471.7
    6136   471.9    6229   471.9    6315   471.9    6575   471.9    7081   471.8
    7538   471.6    7617   471.5    7872   471.2    7965   471.1    8275     471
    8694   471.4    8893   471.8    8980   472.1    9323     472    9410   471.9
    9481   471.7    9560   471.5    9657   471.1    9750   470.8    9780   470.7
    9837   470.7  9842.4   470.7  9842.4   466.9    9855     458  9856.5  457.01
  9857.5   456.4  9863.5  452.38  9868.5  449.31  9870.5  448.95  9871.5  448.76
    9879   447.4  9883.5  444.49    9886  442.88    9890  440.29    9892     439
    9910     437    9916     435    9926     434    9934     434    9944   430.5
    9956     436    9960   436.8    9961  439.63    9965  442.17    9966   442.8
  9980.5  451.98  9981.5  452.62    9990     458  9994.5  460.44  9995.5     461
 10006.8   467.1 10006.8   470.9   10014     471   10230   471.1   10402   471.5
   10628   472.4   10811   473.1   10996   473.8   11089   474.3   11208     475
   11388     476   11460   476.5   11614   477.7   11799     479   11964   480.2
BR D #Mann= 3
    1000    .055    9855     .05    9990    .055
BR D Banks=9855,9990
BC Design=,, 0 ,, 0 ,,,,,,
BC HTab HWMax=480.2
BC Use User HTab Curves=0
BC User HTab FreeFlow(D)= 0

Type RM Length L Ch R = 1 ,153192  ,1,1,1
BEGIN DESCRIPTION:
153192-DS RR
END DESCRIPTION:
XS GIS Cut Line= 2
  2436915.564858 7071409.8758836 2434705.2473171 7071411.8839371
#Sta/Elev= 30
    1000   480.2    1388   476.5    1952   473.1    2756   471.2    5267   470.9
    6575   471.9    8275     471    8980   472.1    9410   471.9  9842.4   470.7
    9855     458  9868.5  449.31    9879   447.4    9892     439    9910     437
    9916     435    9926     434    9934     434    9944   430.5    9956     436
    9960   436.8    9961  439.63    9990     458  9995.5     461 10006.8   470.9
   10014     471   10402   471.5   10996   473.8   11388     476   11964   480.2
#Mann= 3 ,0,0
    1000    .055       0    9855     .05       0    9990    .055       0
#XS Ineff= 2 , 0
            9855     459    9990             459
Permanent Ineff=
       F       F
Bank Sta=9855,9990
XS Rating Curve= 0 ,0
Exp/Cntr=0.5,0.3

Type RM Length L Ch R = 1 ,153191  ,52.81,50.2,50.03
BEGIN DESCRIPTION:
153191- From STA9800-11964
One-foot downstream of Atchinson, Topeka, and Sante Fe Railroad.  Duplication of following bridge cross-section (153192) without bridge piers.
Channel data from USACOE Elm Fork channel survey.
END DESCRIPTION:
XS GIS Cut Line= 2
  2436915.564858 7071409.8758836 2434705.2473171 7071411.8839371
#Sta/Elev= 28
    9800   470.7    9837   470.7    9855     458    9868   449.4    9879   447.4
    9892     439    9910     437    9916     435    9926     434    9934     434
    9944   430.5    9956     436    9960   436.8    9970     439    9990     458
   10014     471   10230   471.1   10402   471.5   10628   472.4   10811   473.1
   10996   473.8   11089   474.3   11208     475   11388     476   11460   476.5
   11614   477.7   11799     479   11964   480.2
#Mann= 3 ,0,0
    9800    .055       0    9855     .05       0    9990    .055       0
#XS Ineff= 2 , 0
            9855     459    9990             459
Permanent Ineff=
       F       F
Bank Sta=9855,9990
XS Rating Curve= 0 ,0
Exp/Cntr=0.3,0.1

Type RM Length L Ch R = 1 ,153092  ,894.46,991.78,1084.97
BEGIN DESCRIPTION:
153092-From Sta 9833-14884
Cross-section EF180.  100 feet downstream of Atchinson, Topeka, and Sante Fe Road.  At Elm Fork/Prairie Creek confluence. Channel data from USACOE Elm Fork channel survey - cross-section EF#6 surveyed March 1983.
END DESCRIPTION:
XS GIS Cut Line= 3
2436891.561625817071359.897308982433126.240744387071363.31823389
2432642.460914757071363.75776468
#Sta/Elev= 30
    9823   463.7    9835   459.9    9879   447.4    9899     435    9918   434.1
    9928   430.4    9944   436.7   10028   445.7   10100   441.5   10106   439.5
   10146   439.6   10157   448.3   10185   459.7   10335   465.3   10404   463.1
   10589   464.7   10869   463.6   11275     467   11848     465   12010   466.6
   12075   472.4   12358     470   12505   459.9   12662   458.8   13183   459.6
   13255   462.3   13469   462.9   13606   467.9   13933   466.7   14033   469.2
#Mann= 3 ,0,0
    9823     .09       0    9835     .05       0   10028      .1       0
#XS Ineff= 2 , 0
                           10052           470.7
Permanent Ineff=
       F       F
Bank Sta=9835,10028
XS Rating Curve= 0 ,0
Exp/Cntr=0.3,0.1

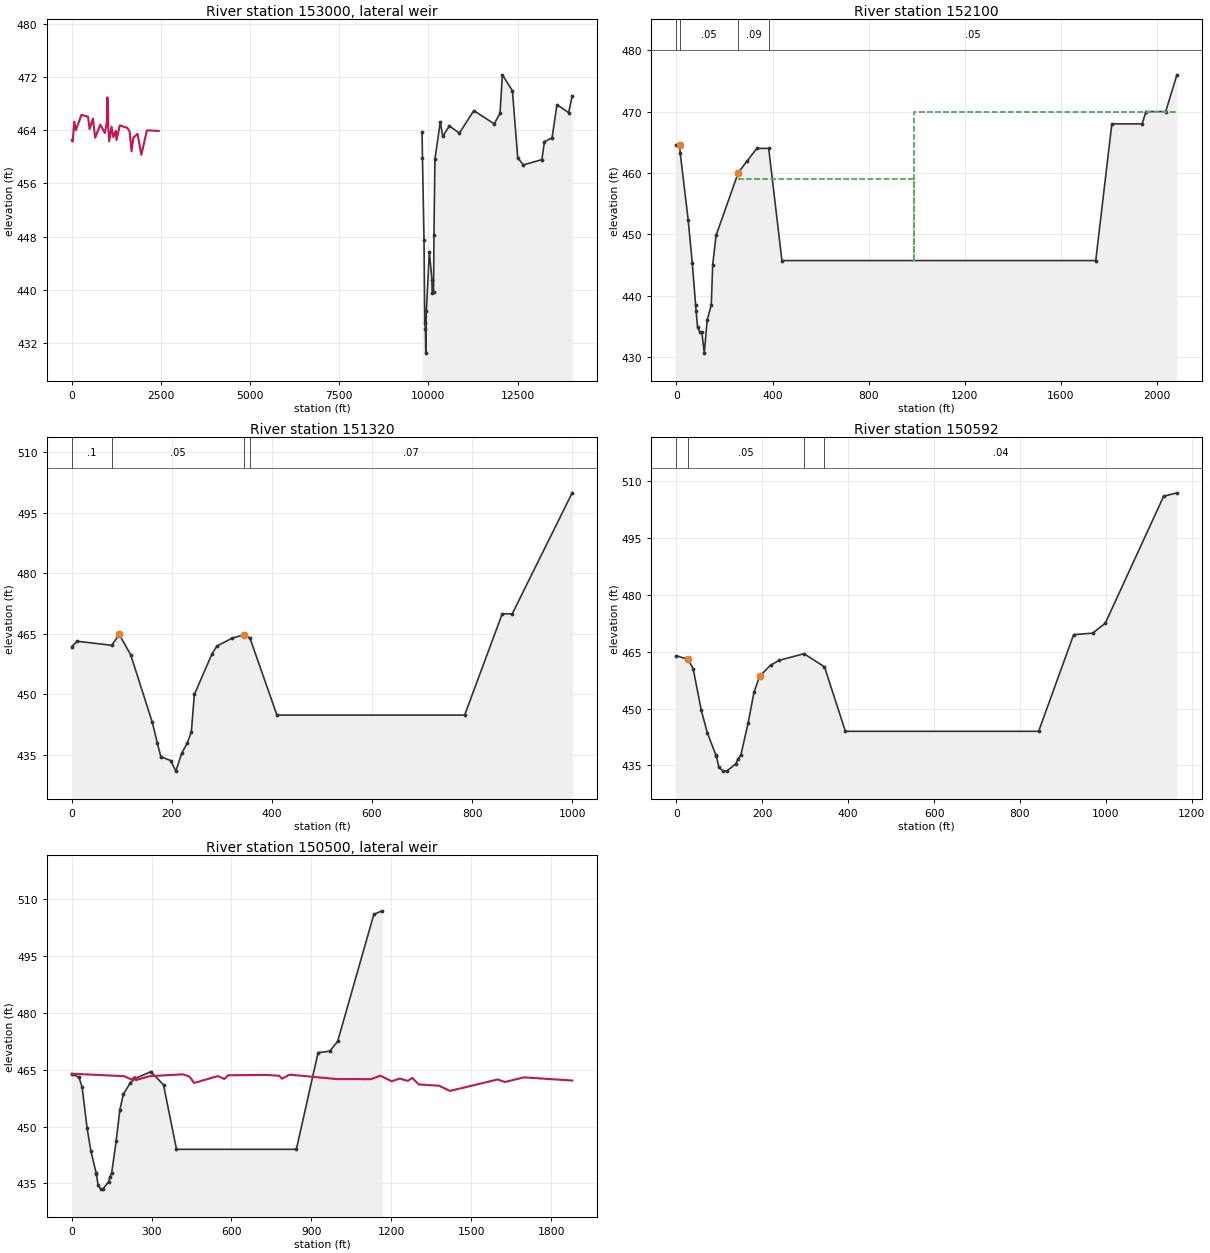
Type RM Length L Ch R = 6 ,153000  ,,,
Lateral Weir Pos= 0
Lateral Weir End=Elm Fork L-Spill,efl             ,4238    ,
Lateral Weir Distance=0
Lateral Weir TW Multiple XS=-1
Lateral Weir WD=5
Lateral Weir Coef=2
LW OverFlow Method 2D=0
LW OverFlow Use Velocity Into 2D=0
Lateral Weir WSCriteria=-1
Lateral Weir Flap Gates= 0
Lateral Weir Hagers EQN= 0 ,,,,,
Lateral Weir SS=0.05,0.05,
Lateral Weir Type= 0
Lateral Weir Connection Pos and Dist= 3 ,0
Lateral Weir SE= 30
       0  462.58   27.65  462.33   72.36  465.35  118.04  464.05  273.77  466.37
  459.15  466.06  502.46  464.21  595.23   465.8  657.15   462.9  802.33  464.89
  929.96  463.62  980.26  465.03  990.12  465.96  997.07  469.01 1014.95  468.16
 1028.53   464.2 1051.47  462.36 1116.84  464.58  1168.1  462.99 1236.19  463.95
 1256.38  462.58 1348.58  464.76 1564.94  464.38 1624.77  463.82 1677.38  460.86
 1727.86  462.93 1847.34  463.49 1952.02  460.32 2109.02  464.02 2440.82  463.93
Lateral Weir Centerline= 0
Lateral Weir HW RS User Defined=-1
Lateral Weir HW RS Station=153092  ,0
Lateral Weir HW RS Station=152100  ,901
Lateral Weir HW RS Station=151320  ,1709
Lateral Weir HW RS Station=150592  ,2440.82
Lateral Weir TW RS User Defined=-1
Lateral Weir TW RS Station=4238,0
Lateral Weir TW RS Station=2879,2440.82
LW Div RC= 0 ,False,,

Type RM Length L Ch R = 1 ,152100  ,792.17,796.05,798.45
BEGIN DESCRIPTION:
152100- From STA 3163-5186
Cross-section EF179.  Effective flow limit set at sta 2400 in LOB, at sta 4140 in ROB.  Riverpark project in ROB.
Channel data from NDM Elm Fork channel survey.
END DESCRIPTION:
XS GIS Cut Line= 2
2437162.65589988 7070563.93170932435227.294285067069794.17242207
#Sta/Elev= 26
       0   464.5      13   464.5      16   463.2      49   452.3      66   445.3
      80   438.4      82   437.5      88   434.8      98     434     106     434
     116   430.6     128     436     145   438.4     151     445     165   449.8
     257     460     295     462     335     464     384     464     439   445.7
    1745   445.7    1812     468    1938     468    1954     470    2036     470
 2082.82     476
#Mann= 4 ,-1,0
       0     .09       0      13     .05       0     257     .09       0
     384     .05       0
#XS Ineff= 2 ,-1
     257     990     459     990    2082     470
Permanent Ineff=
       T       F
Bank Sta=13,257
XS Rating Curve= 0 ,0
Exp/Cntr=0.3,0.1

Type RM Length L Ch R = 1 ,151320  ,711.79,738.76,700.35
BEGIN DESCRIPTION:
151320 From STA 4340-end
END DESCRIPTION:
XS GIS Cut Line= 2
2437687.588905147069968.043793482436775.691122647069558.18864205
#Sta/Elev= 24
       0  461.88      11   463.2      80   462.2      95   464.9     118   459.8
     161   443.1     171     438     178   434.6     198   433.6     208     431
     220   435.5     231     438     239   440.7     245     450     280     460
     290     462     321     464     344   464.8     356     464     410   444.9
     785   444.9     860     470     880     470  999.77     500
#Mann= 4 ,-1,0
       0      .1       0      80     .05       0     344     .09       0
     356     .07       0
#XS Ineff= 2 , 0
                             345             459
Permanent Ineff=
       F       T
Bank Sta=95,344
XS Rating Curve= 0 ,0
Exp/Cntr=0.3,0.1

Type RM Length L Ch R = 1 ,150592  ,964.2,1010.3,998.06
BEGIN DESCRIPTION:
150592- ROB modified using 2009Lidar-CDC pond is shifted but still the same
END DESCRIPTION:
XS GIS Cut Line= 2
2438092.835798057069391.868436652437031.596778817068909.89367881
#Sta/Elev= 27
       0  463.92      27     463      39   460.5      58   449.5      72   443.6
      92   437.7      93   437.5      99   434.5     109   433.5     117   433.5
     139   435.5     143   436.7     150   437.7     167   446.2  180.81   454.4
  193.76   458.5  219.32  461.45   239.1  462.72  297.24  464.47  344.81     461
  393.51     444  843.51     444  925.08  469.49  969.27  469.89  998.71  472.51
 1134.57  505.98 1165.56   506.9
#Mann= 4 ,-1,0
       0     .09       0      27     .05       0  297.24     .08       0
  344.81     .04       0
#XS Ineff= 2 , 0
                             300             459
Permanent Ineff=
       F       T
Bank Sta=27,193.76
XS Rating Curve= 0 ,0
Exp/Cntr=0.3,0.1

Type RM Length L Ch R = 6 ,150500  ,,,
Lateral Weir Pos= 0
Lateral Weir End=Elm Fork L-Spill,efl             ,2879    ,
Lateral Weir Distance=0
Lateral Weir TW Multiple XS=0
Lateral Weir WD=5
Lateral Weir Coef=2
LW OverFlow Method 2D=0
LW OverFlow Use Velocity Into 2D=0
Lateral Weir WSCriteria=-1
Lateral Weir Flap Gates= 0
Lateral Weir Hagers EQN= 0 ,,,,,
Lateral Weir SS=0.05,0.05,
Lateral Weir Type= 0
Lateral Weir Connection Pos and Dist= 3 ,
Lateral Weir SE= 30
       0  463.93  197.53  463.29  223.48  462.43  238.25  463.08  241.22  462.26
  291.06  463.27  419.13  463.78  442.53  463.15  459.75   461.5  549.11  463.32
  573.11  462.56  587.72  463.53  729.26  463.62  779.58  463.39  789.27  462.61
   817.9   463.7  993.96  462.53  1124.2  462.51 1158.82  463.42  1201.5  461.94
 1231.57  462.66 1262.41  462.05 1278.91  462.83 1303.44  461.11 1379.92  460.77
 1420.21   459.4 1599.41  462.42 1626.96  461.76 1697.91  462.98 1879.23  462.14
Lateral Weir Centerline= 0
Lateral Weir HW RS User Defined=-1
Lateral Weir HW RS Station=150592  ,0
Lateral Weir HW RS Station=149594  ,1060
Lateral Weir HW RS Station=148723  ,1879.23
LW Div RC= 0 ,False,,