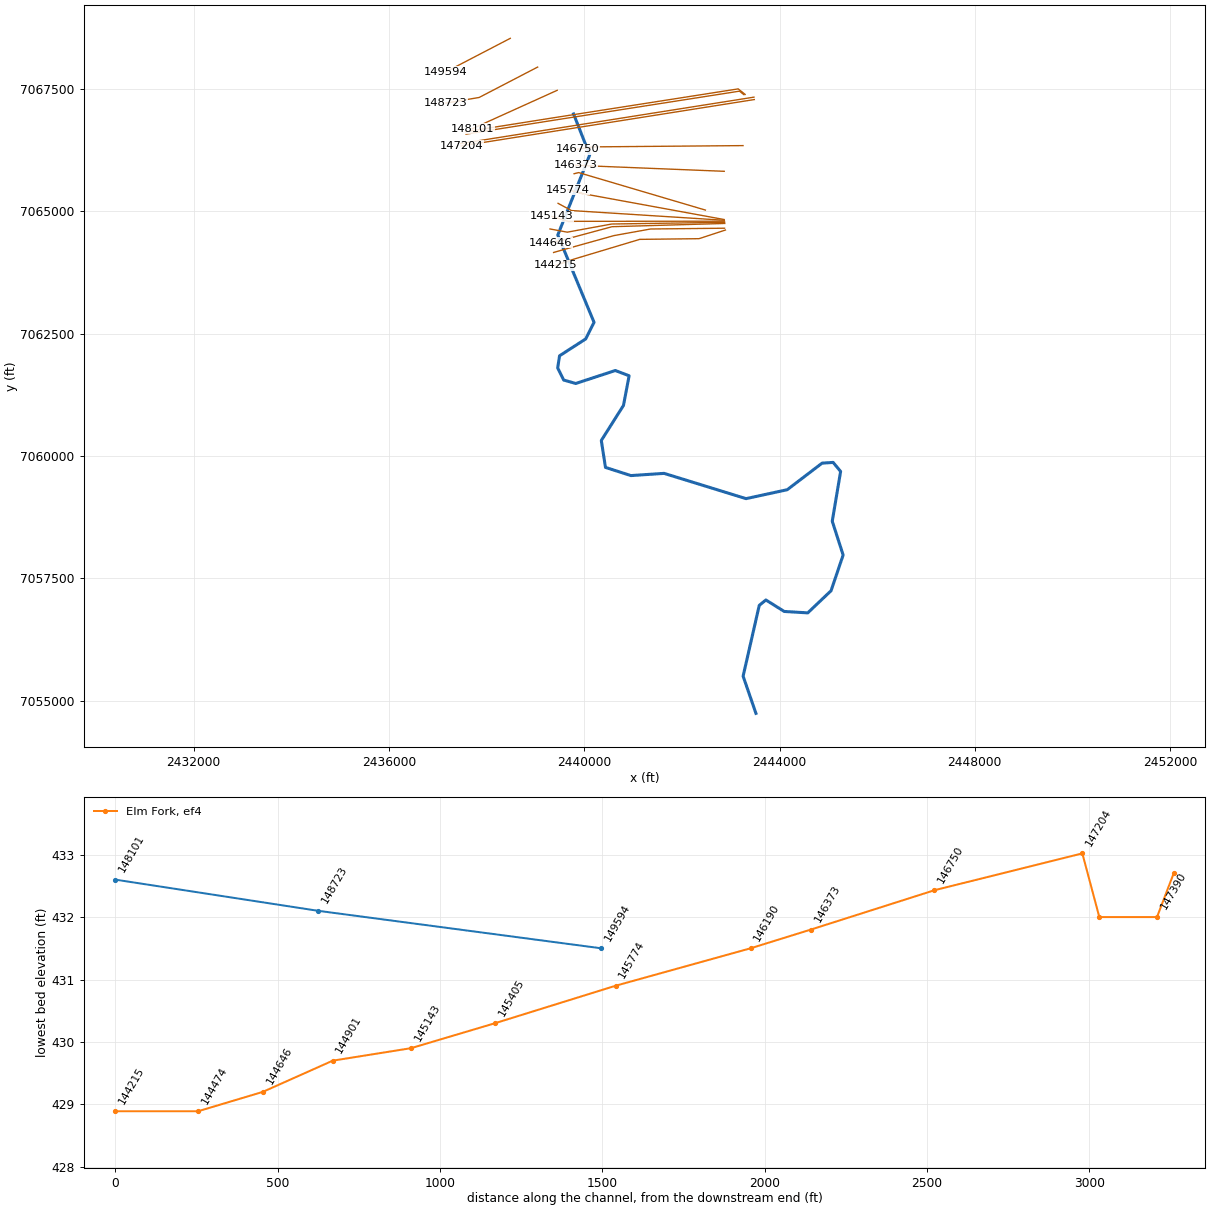
HEC-RAS study CDC_Consolidated_Model.prj: Upper Trinity CDC Consolidated Model

--- CDC_Consolidated_Model.g13 (geometry) --- (continued)

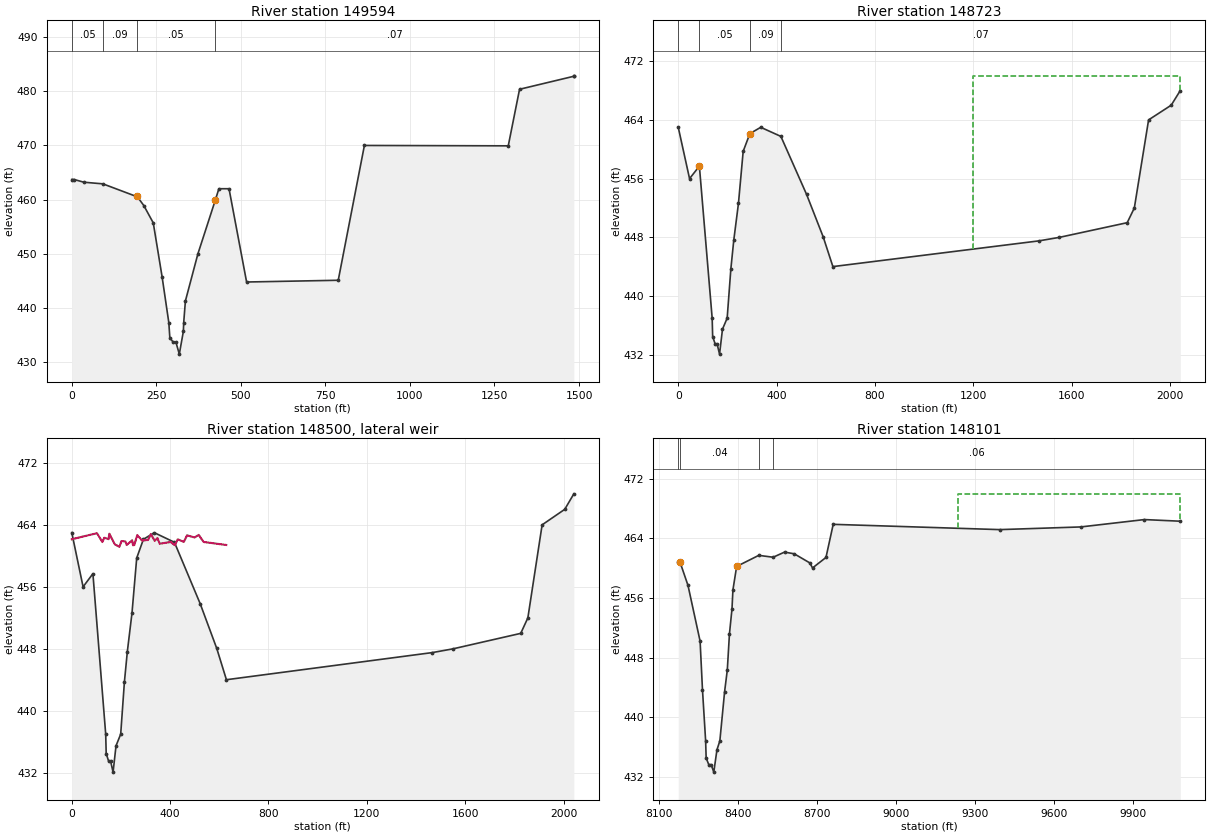
Type RM Length L Ch R = 1 ,149594  ,845.49,871.23,780.18
BEGIN DESCRIPTION:
149594-LOB stationing past station 1500 not in CDC XS.Taken from 2009 Lidar
END DESCRIPTION:
XS GIS Cut Line= 2
 2438485.2438059 7068530.0991628     2437167.254     7067846.661
#Sta/Elev= 28
       0   463.7       7   463.7      36   463.2      92   462.9     190   460.6
     193   460.6     213   458.9     241   455.7     267   445.8     287   437.3
     290   434.5     300   433.7     308   433.7     318   431.5     330   435.7
     331   437.3     336   441.3     373     450     425     460     435     462
     465     462     517   444.8  787.97  445.12  865.31  469.98 1290.71  469.91
 1324.11  480.34 1483.95  482.73 1484.65  482.82
#Mann= 4 ,-1,0
       0     .05       0      92     .09       0     193     .05       0
     425     .07       0
#XS Ineff= 1 ,-1
     425    1044     459
Permanent Ineff=
       F
Bank Sta=193,425
XS Rating Curve= 0 ,0
Exp/Cntr=0.3,0.1

Type RM Length L Ch R = 1 ,148723  ,622.79,625.44,545.07
BEGIN DESCRIPTION:
148723 - from sta 1550 ground from  Lewisville topo
END DESCRIPTION:
XS GIS Cut Line= 3
2439045.45889281 7067943.28767242437847.343506897067322.24134231
2437164.613479577067206.39454717
#Sta/Elev= 27
       0     463      46     456      86   457.7     138     437     140   434.5
     150   433.5     158   433.5     168   432.1     180   435.5     199     437
     214   443.7  225.86  447.61  244.91  452.62  264.14  459.72  291.35  462.13
  335.56  462.99   417.5  461.75     522  453.85  589.64  448.06     629  444.02
 1466.22  447.52    1550     448    1826     450    1855     452    1913     464
    2005     466    2042     468
#Mann= 4 ,-1,0
       0     .09       0      86     .05       0  291.35     .09       0
   417.5     .07       0
#XS Ineff= 2 , 0
                         1200.71             470
Permanent Ineff=
       F       F
Bank Sta=86,291.35
XS Rating Curve= 0 ,0
Exp/Cntr=0.3,0.1

Type RM Length L Ch R = 6 ,148500  ,,,
Lateral Weir Pos= 0
Lateral Weir End=Elm Fork L-Spill,efl             ,2467    ,
Lateral Weir Distance=0
Lateral Weir TW Multiple XS=0
Lateral Weir WD=5
Lateral Weir Coef=2
LW OverFlow Method 2D=0
LW OverFlow Use Velocity Into 2D=0
Lateral Weir WSCriteria=-1
Lateral Weir Flap Gates= 0
Lateral Weir Hagers EQN= 0 ,,,,,
Lateral Weir SS=0.05,0.05,
Lateral Weir Type= 0
Lateral Weir Connection Pos and Dist= 3 ,0
Lateral Weir SE= 30
       0  462.14  102.39  462.92  124.56  461.78  132.29  462.34  149.86  462.15
  152.62  462.86  175.06  461.48  193.72  461.17  202.21  461.91  218.14  461.85
  223.36   461.4  245.57  462.01  249.33  461.36  254.11  461.39  266.21  462.67
  286.02  461.97  309.98  462.05  321.38  462.79  337.42  461.94  348.67  462.29
  357.66  461.56  402.23  461.79  419.23  461.36  431.01  462.13   455.7   461.8
  468.81  462.65  499.21  462.37   516.2   462.7  536.21  461.79  628.34   461.4
Lateral Weir Centerline= 0
Lateral Weir HW RS User Defined=-1
Lateral Weir HW RS Station=148723,0
Lateral Weir HW RS Station=148101,628.34
LW Div RC= 0 ,False,,

Type RM Length L Ch R = 1 ,148101  ,595.76,637.23,262.06
BEGIN DESCRIPTION:
148101-Are mods to left bank and LOB pond built? as shown in CDC?
148101----CDC LEW012804-01 Lewisville Landfill
Cross-section 148101-152100 Located in LOB.----EF u/s of Stewart Creek. The 2, 5, 10, 25-year discharges are discharge-frequency releases from Lewisville Lake and are considered critical discharges as they exceed the local discharges.  7000 cfs is released from the Lewisville Lake outlet per normal lake regulation plan for flood control. During the 50-year and 100-year flood events,the
END DESCRIPTION:
XS GIS Cut Line= 2
2439445.524037557067468.252205152437708.173181557066684.12549256
#Sta/Elev= 30
    8172   460.8    8179   460.8    8209   457.7    8255   450.2    8264   443.7
    8276   436.8    8278   434.5    8288   433.6    8297   433.6    8307   432.6
    8319   435.6    8330   436.8    8348   443.4  8358.3  446.33 8366.43  451.18
 8376.03  454.52 8379.64  457.09 8393.75  460.24 8477.75  461.73 8532.34  461.48
 8575.65  462.17 8612.35  461.94 8671.35  460.72 8681.94  460.04 8732.89  461.45
 8760.36   465.9 9392.84  465.19 9700.03  465.55  9941.6  466.5410078.11  466.32
#Mann= 4 ,-1,0
    8172     .09       0    8179     .04       0 8477.75     .08       0
 8532.34     .06       0
#XS Ineff= 2 , 0
                         9234.74             470
Permanent Ineff=
       F       F
Bank Sta=8179,8393.75
XS Rating Curve= 0 ,0
Exp/Cntr=0.3,0.1

River Reach=Elm Fork        ,ef4
Reach XY= 30
 2439781.73808557066985.488463952440111.736615887066147.97367772
 2439458.02302837064512.010414232440200.975610647062729.49101339
2440029.730874397062389.492349572439494.728335477062045.51206639
2439455.756956737061797.970238642439578.995883467061549.99599706
2439826.239155387061479.505652472440637.019029897061745.00774615
2440919.494514817061636.980731232440803.481951557061030.99309807
 2440349.74762287060315.507324312440434.985969387059765.47856873
2440956.50100248 7059598.49727542441635.477662897059643.48045315
2443314.770564147059127.477220062444158.771172727059309.99194689
2444872.267121057059852.486268732445098.231236067059867.48164555
2445252.019642387059683.476764232445080.496363397058667.00471582
2445303.47623238 7057975.01430192445055.747069057057245.98557623
2444578.728338057056794.024865982444096.750299387056823.01102848
2443721.246129147057057.48431282 2443585.25493137056947.51537265
2443254.480658477055501.003829972443517.219249117054741.06940538

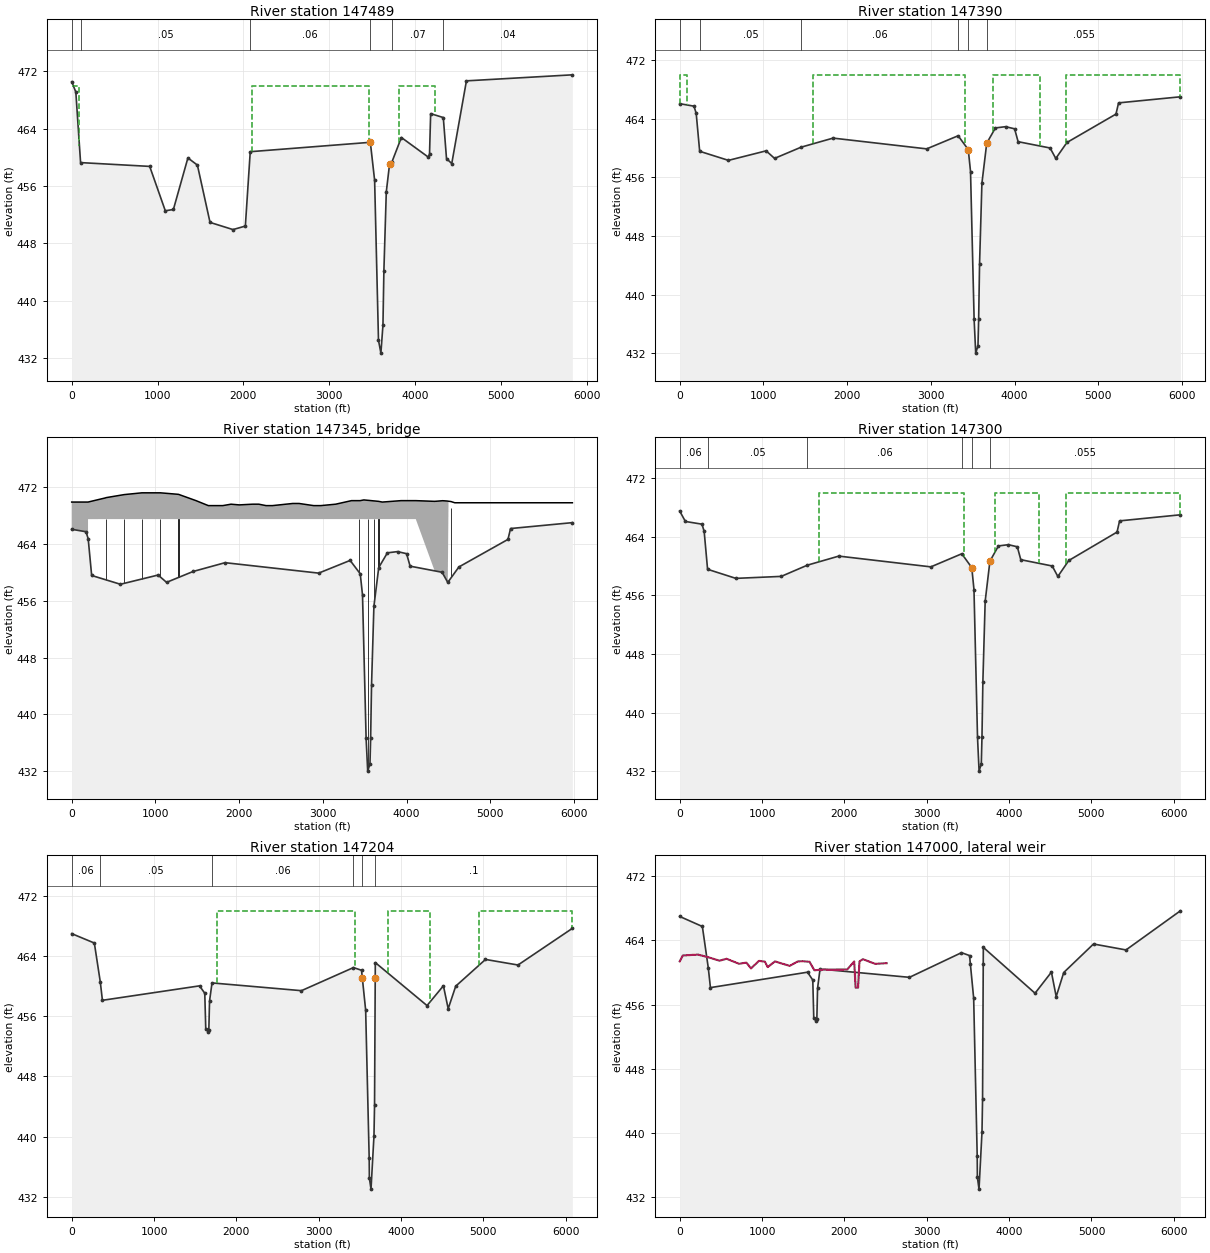
Type RM Length L Ch R = 1 ,147489  ,51.91,51.3,58.69
BEGIN DESCRIPTION:
147489
Cross-section EF173.  100 feet upstream of SH 121.  Effective flow limit set at sta 6020 in LOB, at sta 10530 in ROB.  Ineffective flow from sta 7440 - 9280, sta 9835 - 10160 due to bridge openings.  Approx. 50 feet  downstream of left bank of McWhorter Creek.
Channel data from NDM Elm Fork channel survey.
END DESCRIPTION:
XS GIS Cut Line= 5
2443295.874932637067384.866217062443153.914586637067497.54643789
2439916.294421467066992.282028482439334.128591057066901.42886373
2437570.533364977066622.53375223
#Sta/Elev= 30
       0  470.55    48.1  469.11   103.4  459.27  908.65  458.74 1090.49  452.55
 1184.65  452.73 1353.71  459.92 1464.45  458.92 1611.59  450.93 1879.13  449.93
 2023.05  450.42 2080.05  460.79 3479.05   462.1 3529.05   456.8 3574.05   434.5
 3602.05   432.7 3626.05   436.6 3637.05   444.2 3665.05   455.2 3703.99  459.14
 3729.36  459.32 3840.71  462.77 4153.77  460.04 4168.67  460.45 4181.84   466.1
 4329.15  465.55 4366.43  459.84 4427.54  459.13 4598.64  470.67 5832.77  471.51
#Mann= 6 ,-1,0
       0     .06       0   103.4     .05       0 2080.05     .06       0
 3479.05     .05       0 3729.36     .07       0 4329.15     .04       0
#XS Ineff= 4 ,-1
       0      90     470    2100 3458.05     470 3815.05 4230.05     470
 4611.77 5832.77     470
Permanent Ineff=
       F       F       F       F
Bank Sta=3479.05,3703.99
XS Rating Curve= 0 ,0
Exp/Cntr=0.5,0.3

Type RM Length L Ch R = 1 ,147390  ,179.14,177.64,203.37
BEGIN DESCRIPTION:
147390
END DESCRIPTION:
XS GIS Cut Line= 5
2443271.582002227067378.614261062443180.212762397067451.13806614
2439941.11589414 7066945.56493032439341.888418057066852.03460556
2437578.343388727066573.14736806
#Sta/Elev= 30
       0  466.06   170.5  465.72     197  464.73  238.36  459.56     582  458.32
    1032  459.62    1133  458.59 1449.74  460.12    1832  461.36    2950  459.89
 3325.62  461.68 3446.67  459.79 3473.62   456.8 3516.62   436.6 3535.62     432
 3562.62     433 3570.62   436.6 3581.62   444.2 3609.62   455.2 3667.27  460.67
    3771  462.75    3892  462.92    4000  462.63    4042  460.87    4424  460.01
    4492  458.58    4625  460.76    5211  464.64 5241.97  466.17 5980.27     467
#Mann= 6 ,-1,0
       0     .06       0  238.36     .05       0 1449.74     .06       0
 3325.62    .055       0 3446.67     .05       0 3667.27    .055       0
#XS Ineff= 4 ,-1
       0      90     470    1595    3410     470 3744.97 4299.97     470
 4609.97 5980.27     470
Permanent Ineff=
       F       F       F       F
Bank Sta=3446.67,3667.27
XS Rating Curve= 0 ,0
Exp/Cntr=0.5,0.3

Type RM Length L Ch R = 3 ,147345  ,,,
BEGIN DESCRIPTION:
SH 121
END DESCRIPTION:
Node Name=SH 121
Bridge Culvert--1,0,-1,-1, 0
Deck Dist Width WeirC Skew NumUp NumDn MinLoCord MaxHiCord MaxSubmerge Is_Ogee
30,86,2.6,0, 59, 59, , , 0.95, 0, ,,,
       0     195     195   404.5   409.5   621.5   626.5   838.5   843.5  1055.5
  1060.5  1272.5  1277.5  1484.8  1484.8    1632    1805    1903    2001    2161
    2235    2321    2398    2640    2716    2890    2976    3153    3342    3395
    3395  3445.7  3445.7  3489.5  3490.5  3541.5  3544.5    3578  3611.5  3614.5
  3664.5  3665.5  3710.3  3710.3    3935    4110  4335.1  4379.5  4380.5  4429.5
  4430.5  4479.5  4480.5  4529.5  4530.5  4575.6  4575.6    5790 5980.27
   469.9   469.9   469.9  470.49  470.52  470.94  470.95   471.2   471.2   471.2
   471.2  470.99  470.98   470.1   470.1   469.4   469.4   469.6   469.5   469.6
   469.6   469.4   469.4   469.7   469.7   469.4   469.4   469.6   470.1   470.1
   470.1   470.1   470.1   470.2   470.2  470.14  470.14   470.1  470.06  470.06
     470     470   469.9   469.9   470.1   470.1     470  470.04  470.04  470.09
  470.09  470.05  470.05  469.97  469.97   469.8   469.8   469.8   469.8
                  467.49   467.5   467.5   467.5   467.5   467.5   467.5   467.5
   467.5   467.5   467.5   467.5
                   467.5   467.5   467.5   467.5   467.5   467.5   467.5   467.5
   467.5   467.5   467.5                          467.49   467.5   467.5   467.5
   467.5   467.5   467.5   467.5   467.5   467.5
       0     297     297     506     511     723     728     940     945    1157
    1162    1374    1379    1587    1587    1734    1907    2005    2103    2263
    2337    2423    2500    2742    2818    2992    3078    3255    3444    3490
    3490  3510.7  3510.7  3554.5  3555.5  3606.5  3609.5    3643  3676.5  3679.5
  3729.5  3730.5  3775.3  3775.3    4000    4175  4400.1  4444.5  4445.5  4494.5
  4495.5  4544.5  4545.5  4594.5  4595.5  4640.6  4640.6    5855 6080.27
   469.9   469.9   469.9  470.49  470.52  470.94  470.95   471.2   471.2   471.2
   471.2  470.99  470.98   470.1   470.1   469.4   469.4   469.6   469.5   469.6
   469.6   469.4   469.4   469.7   469.7   469.4   469.4   469.6   470.1   470.1
   470.1   470.1   470.1   470.2   470.2  470.14  470.14   470.1  470.06  470.06
     470     470   469.9   469.9   470.1   470.1     470  470.04  470.04  470.09
  470.09  470.05  470.05  469.97  469.97   469.8   469.8   469.8   469.8
                  467.49   467.5   467.5   467.5   467.5   467.5   467.5   467.5
   467.5   467.5   467.5   467.5
                   467.5   467.5   467.5   467.5   467.5   467.5   467.5   467.5
   467.5   467.5   467.5                          467.49   467.5   467.5   467.5
   467.5   467.5   467.5   467.5   467.5   467.5
Pier Skew, UpSta & Num, DnSta & Num=  ,407, 2 ,509, 2 , 0 , 0 , 0 ,,
       5       5
     455     468
       5       5
     455     468
Pier Skew, UpSta & Num, DnSta & Num=  ,624, 2 ,726, 2 , 0 , 0 , 0 ,,
       5       5
     455     468
       5       5
     455     468
Pier Skew, UpSta & Num, DnSta & Num=  ,841, 2 ,943, 2 , 0 , 0 , 0 ,,
       5       5
     455     468
       5       5
     455     468
Pier Skew, UpSta & Num, DnSta & Num=  ,1058, 2 ,1160, 2 , 0 , 0 , 0 ,,
       5       5
     455     468
       5       5
     455     468
Pier Skew, UpSta & Num, DnSta & Num=  ,1275, 2 ,1377, 2 , 0 , 0 , 0 ,,
       5       5
     455     468
       5       5
     455     468
Pier Skew, UpSta & Num, DnSta & Num=  ,3430, 2 ,3592, 2 , 0 , 0 , 0 ,,
       1       1
     430     469
       1       1
     430     469
Pier Skew, UpSta & Num, DnSta & Num=  ,3540, 2 ,3642, 2 , 0 , 0 , 0 ,,
       3       3
     430     469
       3       3
     430     469
Pier Skew, UpSta & Num, DnSta & Num=  ,3613, 2 ,3715, 2 , 0 , 0 , 0 ,,
       3       3
     430     469
       3       3
     430     469
Pier Skew, UpSta & Num, DnSta & Num=  ,3665, 2 ,3767, 2 , 0 , 0 , 0 ,,
       1       1
     430     469
       1       1
     430     469
Pier Skew, UpSta & Num, DnSta & Num=  ,4385.1, 2 ,4450.1, 2 , 0 , 0 , 0 ,,
       1       1
     430     469
       1       1
     430     469
Pier Skew, UpSta & Num, DnSta & Num=  ,4435.1, 2 ,4500.1, 2 , 0 , 0 , 0 ,,
       1       1
     430     469
       1       1
     430     469
Pier Skew, UpSta & Num, DnSta & Num=  ,4485.1, 2 ,4550.1, 2 , 0 , 0 , 0 ,,
       1       1
     430     469
       1       1
     430     469
Pier Skew, UpSta & Num, DnSta & Num=  ,4535.1, 2 ,4600.1, 2 , 0 , 0 , 0 ,,
       1       1
     430     469
       1       1
     430     469
BR Coef= 1 , 0 , 0 ,1.05, 0 ,,,0.8,-1,0.5,1,
WSPro=,,,, 1 ,,,, 0 ,,,, 0 ,,,,-1 ,-1 ,-1 , 0 , 0 , 0 , 0 , 0
BC Design=,, 0 ,, 0 ,,,,,,
BC HTab HWMax=470.1
BC Use User HTab Curves=0
BC User HTab FreeFlow(D)= 0

Type RM Length L Ch R = 1 ,147300  ,51.9,52.39,58.7
BEGIN DESCRIPTION:
147300
One-foot downstream of SH 121.  Duplication of following bridge cross-section (147301) without bridge piers.
Channel data from NDM Elm Fork channel survey.
END DESCRIPTION:
XS GIS Cut Line= 2
2443476.416894397067328.86272015 2437470.47385387066381.08443198
#Sta/Elev= 30
       0  467.51      69  466.09   270.5  465.72     297  464.73  338.36  459.56
     682  458.32    1233  458.59 1549.74  460.12    1932  461.36    3050  459.89
 3425.62  461.68 3546.67  459.79 3573.62   456.8 3616.62   436.6 3635.62     432
 3662.62     433 3670.62   436.6 3681.62   444.2 3709.62   455.2 3767.27  460.67
    3871  462.75    3992  462.92    4100  462.63    4142  460.87    4524  460.01
    4592  458.58    4725  460.76    5311  464.64 5341.97  466.17 6080.27     467
#Mann= 6 ,-1,0
       0     .06       0  338.36     .05       0 1549.74     .06       0
 3425.62    .055       0 3546.67     .05       0 3767.27    .055       0
#XS Ineff= 3 ,-1
    1686 3455.78     470 3825.62 4365.62     470 4695.62 6080.27     470
Permanent Ineff=
       F       F       F
Bank Sta=3546.67,3767.27
XS Rating Curve= 0 ,0
Exp/Cntr=0.5,0.3

Type RM Length L Ch R = 1 ,147204  ,456.24,455.52,1278.53
BEGIN DESCRIPTION:
147204
Cross-section EF171.  97 feet downstream of SH 121.  Effective flow limit set at sta 6250 in LOB, at sta 10700 in ROB.  Connell project in LOB. Channel data from NDM Elm Fork channel survey - cross-section EF#171 surveyed
January 1994
END DESCRIPTION:
XS GIS Cut Line= 2
2443483.948375397067279.432700892437478.267801467066331.69575123
#Sta/Elev= 30
       0  466.97     275  465.72  347.09  460.56     373  458.11    1552  460.03
    1616  459.05    1628  454.31 1658.71  453.93 1665.21  454.15 1674.02  458.02
    1704  460.42    2790  459.39 3421.72  462.46 3519.72   462.1    3530  461.01
 3569.72   456.8 3612.72   437.1 3614.72   434.5 3634.72  433.02 3670.72   440.1
 3677.72   444.2    3686  461.08    3687  463.12    4315  457.41    4514  460.04
    4572  456.99  4663.5  459.99    5025  463.54 5419.72   462.8    6080  467.67
#Mann= 6 ,-1,0
       0     .06       0  347.09     .05       0    1704     .06       0
 3421.72     .08       0 3519.72     .05       0    3686      .1       0
#XS Ineff= 3 ,-1
 1761.54 3445.08     470 3838.72 4348.72     470 4942.72    6080     470
Permanent Ineff=
       F       F       F
Bank Sta=3530,3686
XS Rating Curve= 0 ,0
Exp/Cntr=0.3,0.1

Type RM Length L Ch R = 6 ,147000  ,,,
Lateral Weir Pos= 3
Lateral Weir End=Elm Fork Split2 ,efs2            ,139902  ,
Lateral Weir Distance=35
Lateral Weir TW Multiple XS=-1
Lateral Weir WD=5
Lateral Weir Coef=2
Lateral Weir Is ZeroHeight=-1
LW OverFlow Method 2D=0
LW OverFlow Use Velocity Into 2D=0
Lateral Weir WSCriteria=-1
Lateral Weir Flap Gates= 1
Lateral Weir Hagers EQN= 0 ,,,,,
Lateral Weir SS=0.05,0.05,
Lateral Weir Type= 0
Lateral Weir Connection Pos and Dist= 0 ,0
Lateral Weir SE= 29
       0  461.38   38.26  462.11  220.32  462.22  336.84  461.92  483.82  461.46
  568.22   461.7  720.46  461.08  809.65  461.22     865   460.5  963.02  461.44
 1034.58  461.34 1067.73  460.66 1156.84  461.37 1236.19  461.12 1334.98  460.82
 1433.83  461.37 1493.24  461.39 1576.17  461.33 1635.47  460.27    1755  460.36
    2035  460.37    2119  461.37    2136   458.1    2166   458.1    2183  461.37
 2224.72  461.65    2316  461.29    2373  461.07    2513  461.15
Lateral Weir Centerline= 0
Lateral Weir HW RS Station=147204,-35
Lateral Weir HW RS Station=146750,0
Lateral Weir HW RS Station=146373,330
Lateral Weir HW RS Station=146190,505
Lateral Weir HW RS Station=145774,865
Lateral Weir HW RS Station=145405,1200
Lateral Weir HW RS Station=145143,1495
Lateral Weir HW RS Station=144901,1755
Lateral Weir HW RS Station=144646,2035
Lateral Weir HW RS Station=144474,2245
Lateral Weir HW RS Station=144215,2513
Lateral Weir TW RS User Defined=-1
Lateral Weir TW RS Station=139902  ,0
Lateral Weir TW RS Station=139477  ,330
Lateral Weir TW RS Station=139260  ,505
Lateral Weir TW RS Station=138967  ,865
Lateral Weir TW RS Station=138769  ,1200
Lateral Weir TW RS Station=138563  ,1495
Lateral Weir TW RS Station=138334  ,1755
Lateral Weir TW RS Station=138038  ,2245
Lateral Weir TW RS Station=137852  ,2466
Lateral Weir TW RS Station=137770  ,2650
LW Culv=2,7,7,55,0.015,0.5,1,8,1,442.28,442.86, 1 ,Culvert #1  , 0 ,
    2151    2151
LW Culvert Barrel=1,Barrel #1,0
LW Culv Bottom n=0.015
LW Div RC= 0 ,False,,

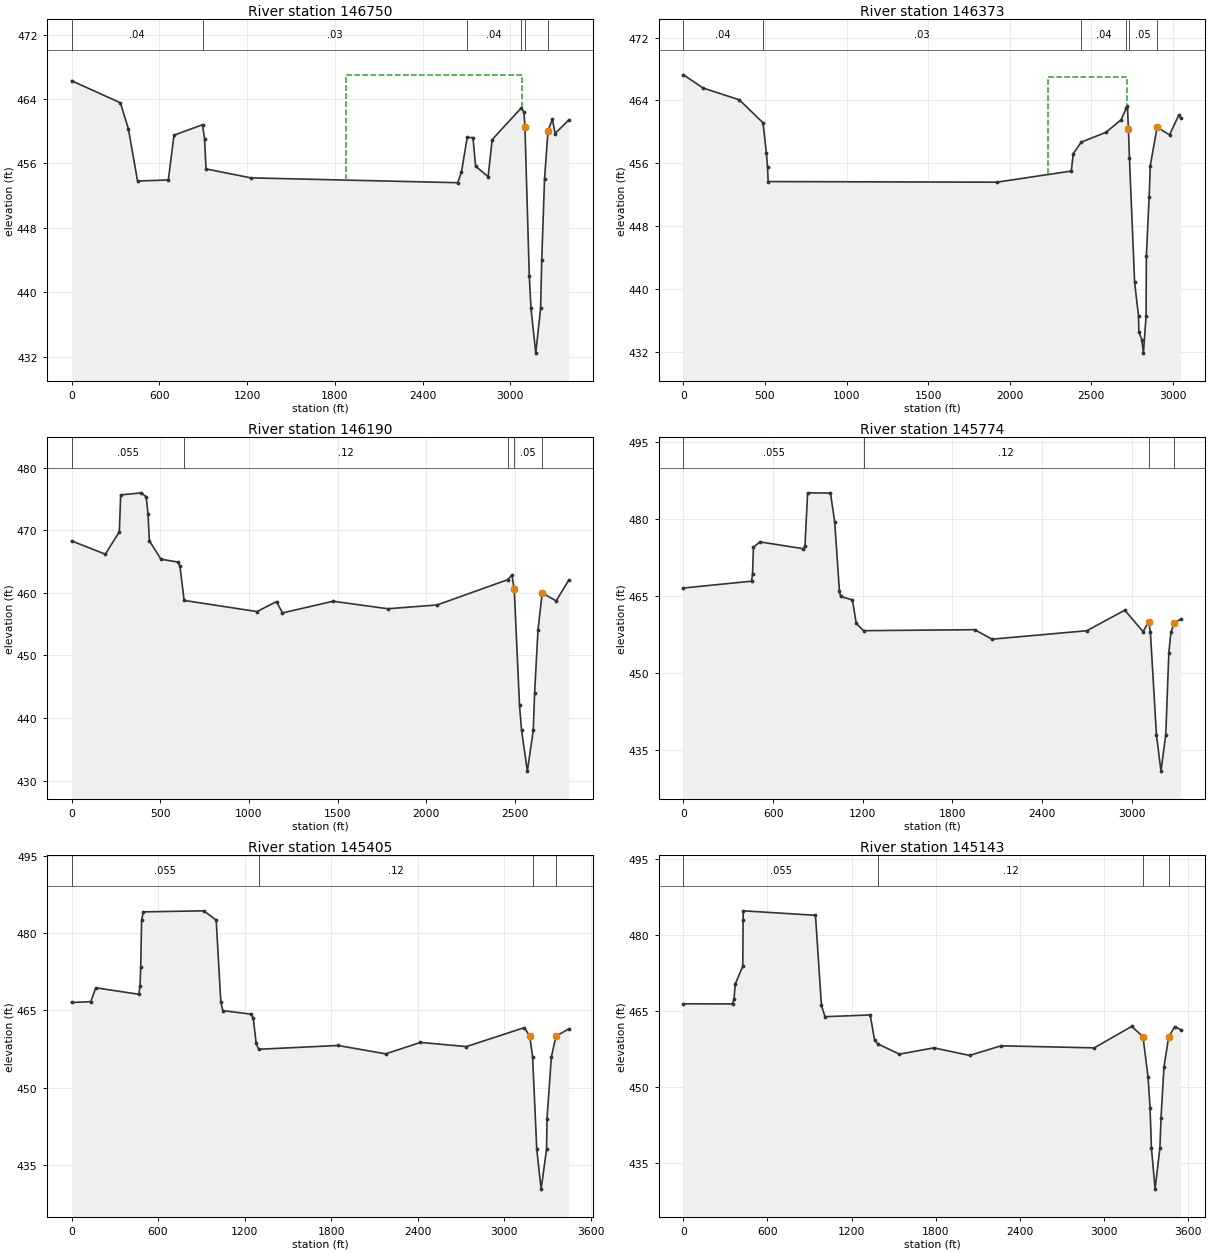
Type RM Length L Ch R = 1 ,146750  ,397.19,380.54,355
BEGIN DESCRIPTION:
IFA from SH121 main and east relief bridges
END DESCRIPTION:
XS GIS Cut Line= 3
2443253.018719147066338.980185482440181.485492147066313.01370198
2439858.112451237066266.04102689
#Sta/Elev= 30
       0  466.27   333.9  463.53  388.55   460.3  451.52  453.81  661.81  453.94
  700.36   459.5  895.46   460.8  909.48  459.04  919.56  455.31 1226.22   454.2
 2639.99   453.6 2665.62  454.91 2704.88  459.22 2744.38   459.2 2762.59  455.64
    2848  454.35  2875.7  458.96 3071.64  462.83 3092.61  462.42 3099.56  460.57
 3129.38     442 3141.07     438 3173.64  432.43 3206.76  438.01 3214.55     444
 3233.41     454 3257.28     460 3286.91  461.51 3306.19  459.71 3398.41  461.38
#Mann= 6 ,-1,0
       0     .04       0  895.46     .03       0 2704.88     .04       0
 3071.64     .08       0 3099.56     .05       0 3257.28      .1       0
#XS Ineff= 1 ,-1
    1878 3077.93     467
Permanent Ineff=
       F
Bank Sta=3099.56,3257.28
XS Rating Curve= 0 ,0
Exp/Cntr=0.3,0.1

Type RM Length L Ch R = 1 ,146373  ,205.05,185.76,158.46
BEGIN DESCRIPTION:
146373
Cross Section Truncated due to Ineffective Flow Areas
- End Lewisville CLOMR.
Proposed Park Improvements - 13863.99-14110 (not shown)
END DESCRIPTION:
XS GIS Cut Line= 4
2442867.940092977065813.895277652440153.114813977065923.01087306
2440153.125312647065923.010216892439821.828731137065937.63453148
#Sta/Elev= 30
       0  467.26  121.14  465.57  342.37  464.08  487.97  461.15  508.87  457.26
  515.69  455.46  519.58  453.66 1920.87  453.58 2378.55     455 2390.81  457.23
 2440.19  458.69 2590.88  459.93 2683.66  461.52 2717.02  463.07 2723.02   463.3
 2729.02   460.3 2735.02   456.7 2767.02   440.8 2791.02   436.5 2793.02   434.5
 2811.02   433.5 2821.02   431.8 2837.02   436.5 2839.02   444.2 2856.02   451.7
 2863.02   455.7 2905.02   460.6 2981.02   459.6 3039.02   462.2 3048.64  461.76
#Mann= 6 ,-1,0
       0     .04       0  487.97     .03       0 2440.19     .04       0
 2717.02     .09       0 2735.02     .05       0 2905.02     .12       0
#XS Ineff= 1 ,-1
    2238 2723.02     467
Permanent Ineff=
       F
Bank Sta=2729.02,2905.02
XS Rating Curve= 0 ,0
Exp/Cntr=0.3,0.1

Type RM Length L Ch R = 1 ,146190  ,406.61,415.79,411.6
XS GIS Cut Line= 4
2442481.910353217065022.028423062440124.054176557065717.22453922
2439887.171776317065787.792967652439792.415404147065764.70049414
#Sta/Elev= 30
       0  468.31  190.74  466.18  269.62  469.78  277.22  475.66  393.64  475.99
  420.93  475.33  431.48  472.59  438.75  468.34  504.04  465.38  597.84  464.93
   611.6  464.25  634.82  458.79 1045.55  457.01 1155.92   458.6 1189.49  456.79
 1474.58  458.66 1783.65  457.46 2060.45  458.06 2458.21  462.09 2482.87  462.84
 2496.13  460.57 2525.95     442 2537.64     438 2570.21   431.5 2603.33  438.01
 2611.12     444 2629.98     454 2653.85     460 2732.62  458.72 2802.91  462.01
#Mann= 5 ,-1,0
       0    .055       0  634.82     .12       0 2458.21     .04       0
 2496.13     .05       0 2653.85     .12       0
Bank Sta=2496.13,2653.85
XS Rating Curve= 0 ,0
Exp/Cntr=0.3,0.1

Type RM Length L Ch R = 1 ,145774  ,392.27,371.27,353.04
XS GIS Cut Line= 5
2442865.660569977064829.019622732439902.684540557065370.42011473
2439969.530207387065358.205900312439902.684540557065370.42011473
2439665.802140317065440.98854314
#Sta/Elev= 30
       0  466.57  455.96   467.9  462.35  469.32  468.71  474.54  511.65  475.55
  801.47  474.23  813.24  474.67   831.1  485.11   984.2  485.06 1012.42  479.43
 1043.95  466.01  1051.8  464.93 1131.06  464.24 1156.73  459.66 1205.34  458.26
 1949.77  458.45  2064.3   456.6 2700.39  458.25 2953.82  462.25  3076.3  458.07
 3113.46  460.01 3113.74     460 3125.22     458 3165.64     438 3196.03   430.9
 3228.11     438 3248.81     454  3262.9     458 3284.11  459.71 3327.15   460.5
#Mann= 4 ,-1,0
       0    .055       0 1205.34     .12       0 3113.46     .05       0
 3284.11     .12       0
Bank Sta=3113.74,3284.11
XS Rating Curve= 0 ,0
Exp/Cntr=0.3,0.1

Type RM Length L Ch R = 1 ,145405  ,245.53,258.84,276.49
XS GIS Cut Line= 3
2442868.334449147064813.930742142439738.155013967065012.21545056
2439464.193619647065159.21909356
#Sta/Elev= 30
       0  466.54  133.96   466.7   168.1  469.39  466.58  468.14   475.3  469.83
  479.86  473.46  486.06  482.49  497.81  484.14  917.69  484.34 1003.27  482.53
 1035.48   466.6 1049.27  464.96 1244.38  464.28 1260.07  463.53 1280.41  458.61
 1297.68  457.46 1848.38  458.19 2178.35  456.57 2419.79  458.79 2738.54  457.98
 3140.34  461.66  3177.9     460 3197.42     456 3226.35     438 3256.45   430.3
 3294.06     438 3297.37     444 3327.76     456 3359.72     460 3447.36   461.4
#Mann= 4 ,-1,0
       0    .055       0 1297.68     .12       0 3197.42     .05       0
 3359.72     .05       0
Bank Sta=3177.9,3359.72
XS Rating Curve= 0 ,0
Exp/Cntr=0.3,0.1

Type RM Length L Ch R = 1 ,145143  ,237.27,241.1,249.13
XS GIS Cut Line= 3
2442871.737001397064794.731305482439671.335265737064791.70998606
2439337.236196387064891.93977247
#Sta/Elev= 30
       0   466.5  350.26  466.48  360.96  467.44  369.82   470.4  423.71  473.93
  425.79   483.1  427.32  484.86   942.6  483.98  985.22   466.2 1010.59  463.95
 1333.44   464.3 1364.92  459.28 1388.81  458.56 1542.14  456.56    1788   457.8
    2043   456.3    2267   458.2    2933   457.8  3200.4  462.04 3281.01     460
 3317.16     452 3331.32     446 3341.28     438  3367.4   429.9 3401.67     438
  3409.8     444 3430.64     454 3464.55     460 3508.82  462.01 3549.21  461.37
#Mann= 4 ,-1,0
       0    .055       0 1388.81     .12       0 3281.01     .05       0
 3464.55     .11       0
Bank Sta=3281.01,3464.55
XS Rating Curve= 0 ,0
Exp/Cntr=0.3,0.1

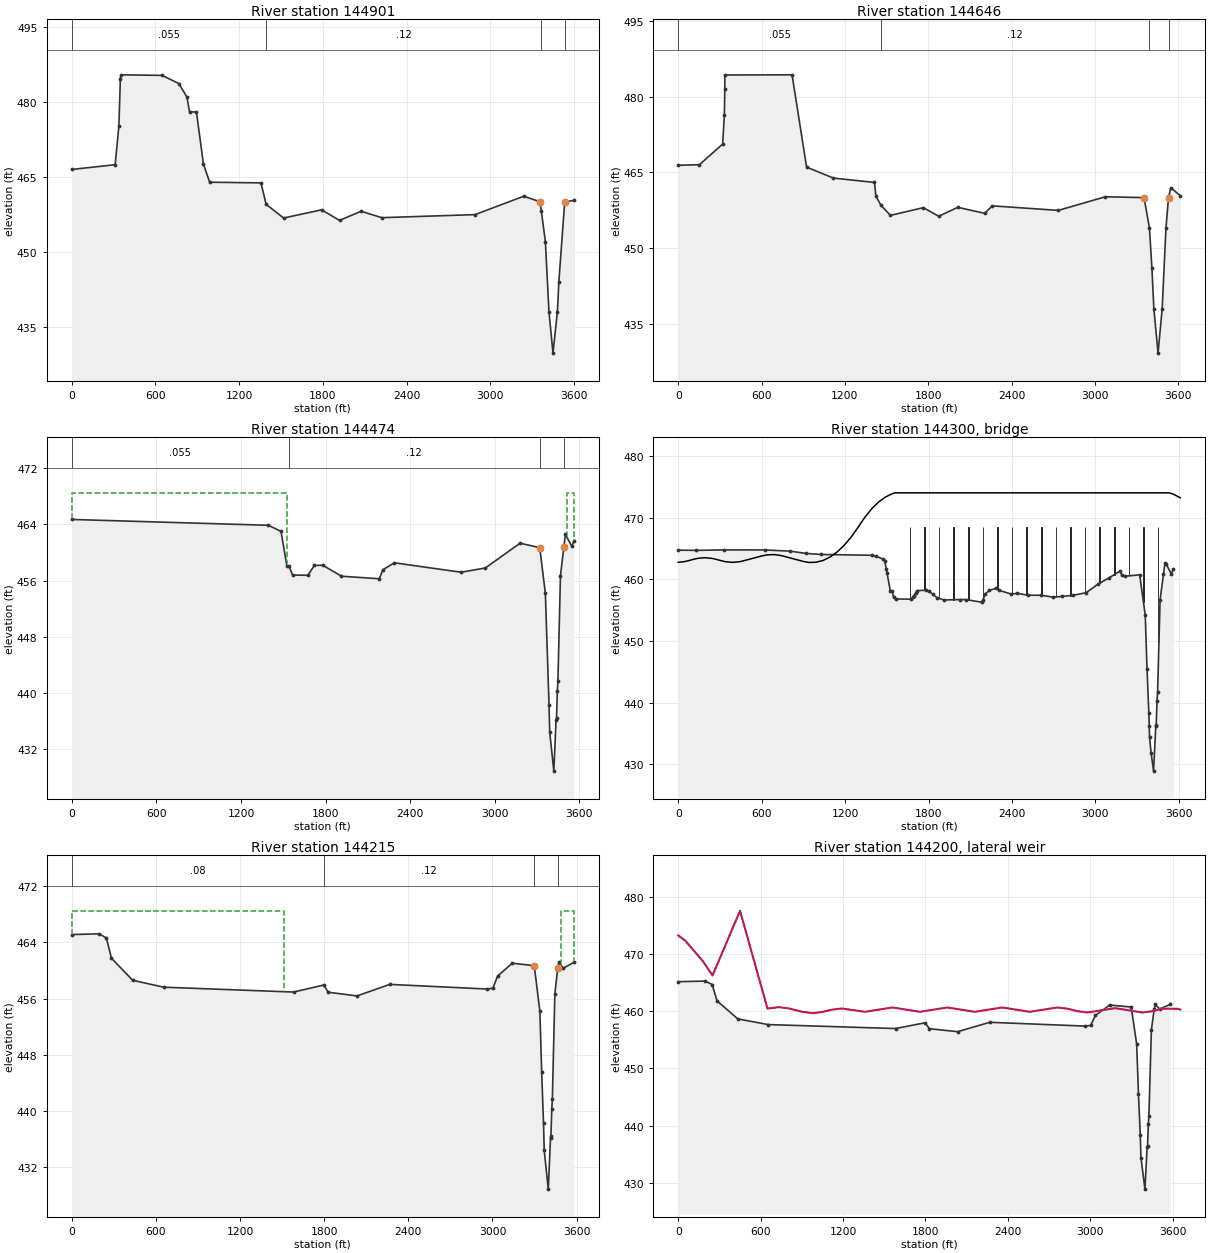
Type RM Length L Ch R = 1 ,144901  ,164.07,215.29,252.43
XS GIS Cut Line= 4
 2442875.5949333 7064772.01219082440563.907299477064737.32000297
2439652.154529817064570.562462482439298.78154889 7064636.2647589
#Sta/Elev= 30
       0  466.46  310.92  467.41  337.84  475.21  348.14  484.54  351.71   485.4
   647.3  485.29  766.73  483.66  825.43  480.96   843.9  477.98  893.39  477.97
  943.82  467.52  988.16  463.91 1356.01  463.77 1392.72  459.49 1517.79  456.74
 1790.57  458.38  1919.1  456.27 2073.74  458.09 2221.88  456.81 2889.45  457.42
 3238.82   461.1  3355.1     460 3364.83  458.24 3394.31     452 3419.84     438
 3448.82   429.7 3480.45     438 3490.92     444 3532.79     460 3598.25  460.26
#Mann= 4 ,-1,0
       0    .055       0 1392.72     .12       0 3364.83     .05       0
 3532.79     .05       0
Bank Sta=3355.1,3532.79
XS Rating Curve= 0 ,0
Exp/Cntr=0.3,0.1

Type RM Length L Ch R = 1 ,144646  ,193.35,199.16,204.24
XS GIS Cut Line= 5
 2442879.54964987064748.724507732440569.975200717064682.33651714
2439683.218115977064443.052874982439593.174988977064418.75535139
2439308.218865987064355.02910089
#Sta/Elev= 30
       0  466.41  152.49  466.52  319.82   470.6  332.21  476.45  335.17  481.49
  335.81  484.29  819.39  484.32  923.91  466.04 1117.21  463.87 1412.68  463.01
 1422.88  460.27 1459.86  458.47 1527.28  456.48 1764.37  458.01 1875.24  456.31
 2012.35  458.08 2205.02  456.89 2261.81  458.37 2735.88  457.47 3074.63  460.17
 3353.24     460 3391.99     454 3409.89     446 3423.77     438    3454   429.2
 3483.71     438 3511.01     454 3529.36     460 3546.19  461.95 3614.26  460.37
#Mann= 4 ,-1,0
       0    .055       0 1459.86     .12       0 3391.99     .05       0
 3529.36     .05       0
Bank Sta=3353.24,3529.36
XS Rating Curve= 0 ,0
Exp/Cntr=0.3,0.1

Type RM Length L Ch R = 1 ,144474  ,247.02,255.22,261.23
BEGIN DESCRIPTION:
144474
END DESCRIPTION:
XS GIS Cut Line= 6
2442873.923020637064651.483560472441359.022179057064635.47178148
2440612.865206817064501.495015312439728.731804487064256.22910164
2439558.584178887064208.842713482439372.584550897064156.05148047
#Sta/Elev= 30
       0  464.71 1394.84  463.88 1483.89  463.01 1525.36  458.11 1538.32  458.12
 1565.98   456.8  1674.5  456.76 1720.13  458.16 1779.45   458.2 1912.82  456.63
 2181.44  456.27 2205.66  457.54 2287.88  458.54    2761   457.2    2933   457.8
 3179.08  461.33 3318.63   460.7 3358.63   454.2 3384.63   438.3 3389.63   434.4
 3418.63  428.89 3434.63   436.2 3437.63   436.4 3443.63   440.3 3447.63   441.7
 3465.63   456.7    3490  460.81 3500.63   462.6 3545.63   460.9  3560.6  461.58
#Mann= 4 ,-1,0
       0    .055       0 1538.32     .12       0 3318.63     .05       0
    3490    .055       0
#XS Ineff= 2 , 0
            1525   468.5    3510           468.5
Permanent Ineff=
       F       F
Bank Sta=3318.63,3490
XS Rating Curve= 0 ,0
Exp/Cntr=0.3,0.1

Type RM Length L Ch R = 3 ,144300  ,,,
Bridge Culvert--1,0,-1,-1, 0
Deck Dist Width WeirC Skew NumUp NumDn MinLoCord MaxHiCord MaxSubmerge Is_Ogee
160,83,2.6,0, 51, 51, , , 0.98, 0, 0,0,,
       0      41      66      91     116     141     191     241     266     291
     316     341     391     441     466     491     541     591     601     641
     691     741     751     791     841     891     901     941     991    1041
    1091    1141    1191    1241    1291    1301    1306    1341    1391    1441
    1491    1541    1556    1561    1563    1563    3191    3531    3531    3561
    3611
  462.74  462.83  462.96  463.11  463.26  463.38  463.48  463.38  463.26  463.11
  462.96  462.83  462.73  462.83  462.96  463.11  463.41  463.71  463.77  463.95
  463.99  463.83  463.77  463.53  463.23  462.93  462.87  462.71  462.75  463.03
  463.58  464.38  465.44  466.75  468.33  468.67  468.84     470   471.4  472.51
  473.33  473.87  473.97     474     474     474     474     474     474  473.78
  473.19
                                           468.5   468.5   468.5
       0      37      62      87     112     137     187     237     262     287
     312     337     387     437     462     487     537     587     597     637
     687     737     747     787     837     887     897     937     987    1037
    1087    1137    1187    1237    1287    1297    1302    1337    1387    1437
    1487    1537    1552    1557    1559    1559    3182    3527    3527    3557
    3607
  462.75  462.83  462.96  463.11  463.26  463.38  463.48  463.38  463.26  463.11
  462.96  462.83  462.73  462.83  462.96  463.11  463.41  463.71  463.77  463.95
  463.99  463.83  463.77  463.53  463.23  462.93  462.87  462.71  462.75  463.03
  463.58  464.38  465.44  466.75  468.33  468.67  468.84     470   471.4  472.51
  473.33  473.87  473.97     474     474     474     474     474     474  473.78
  473.19
                                           468.5   468.5   468.5
Pier Skew, UpSta & Num, DnSta & Num=  ,1666, 2 ,1662, 2 , 0 , 0 , 0 ,,
       4       4
     450   468.5
       4       4
     450   468.5
Pier Skew, UpSta & Num, DnSta & Num=  ,1771, 2 ,1767, 2 , 0 , 0 , 0 ,,
       4       4
     450   468.5
       4       4
     450   468.5
Pier Skew, UpSta & Num, DnSta & Num=  ,1876, 2 ,1872, 2 , 0 , 0 , 0 ,,
       4       4
     450   468.5
       4       4
     450   468.5
Pier Skew, UpSta & Num, DnSta & Num=  ,1981, 2 ,1977, 2 , 0 , 0 , 0 ,,
       4       4
     450   468.5
       4       4
     450   468.5
Pier Skew, UpSta & Num, DnSta & Num=  ,2086, 2 ,2082, 2 , 0 , 0 , 0 ,,
       4       4
     450   468.5
       4       4
     450   468.5
Pier Skew, UpSta & Num, DnSta & Num=  ,2191, 2 ,2187, 2 , 0 , 0 , 0 ,,
       4       4
     450   468.5
       4       4
     450   468.5
Pier Skew, UpSta & Num, DnSta & Num=  ,2296, 2 ,2292, 2 , 0 , 0 , 0 ,,
       4       4
     450   468.5
       4       4
     450   468.5
Pier Skew, UpSta & Num, DnSta & Num=  ,2401, 2 ,2397, 2 , 0 , 0 , 0 ,,
       4       4
     450   468.5
       4       4
     450   468.5
Pier Skew, UpSta & Num, DnSta & Num=  ,2506, 2 ,2502, 2 , 0 , 0 , 0 ,,
       4       4
     450   468.5
       4       4
     450   468.5
Pier Skew, UpSta & Num, DnSta & Num=  ,2611, 2 ,2607, 2 , 0 , 0 , 0 ,,
       4       4
     450   468.5
       4       4
     450   468.5
Pier Skew, UpSta & Num, DnSta & Num=  ,2716, 2 ,2712, 2 , 0 , 0 , 0 ,,
       4       4
     450   468.5
       4       4
     450   468.5
Pier Skew, UpSta & Num, DnSta & Num=  ,2821, 2 ,2817, 2 , 0 , 0 , 0 ,,
       4       4
     450   468.5
       4       4
     450   468.5
Pier Skew, UpSta & Num, DnSta & Num=  ,2926, 2 ,2922, 2 , 0 , 0 , 0 ,,
       4       4
     450   468.5
       4       4
     450   468.5
Pier Skew, UpSta & Num, DnSta & Num=  ,3031, 2 ,3027, 2 , 0 , 0 , 0 ,,
       4       4
     450   468.5
       4       4
     450   468.5
Pier Skew, UpSta & Num, DnSta & Num=  ,3136, 2 ,3132, 2 , 0 , 0 , 0 ,,
       4       4
     450   468.5
       4       4
     450   468.5
Pier Skew, UpSta & Num, DnSta & Num=  ,3241, 2 ,3237, 2 , 0 , 0 , 0 ,,
       4       4
     450   468.5
       4       4
     450   468.5
Pier Skew, UpSta & Num, DnSta & Num=  ,3346, 2 ,3342, 2 , 0 , 0 , 0 ,,
       4       4
     450   468.5
       4       4
     450   468.5
Pier Skew, UpSta & Num, DnSta & Num=  ,3451, 2 ,3447, 2 , 0 , 0 , 0 ,,
       4       4
     450   468.5
       4       4
     450   468.5
Abutment Skew #Up #Dn= , 2 , 2
    1563    1623
   468.5   453.5
    1559    1619
   468.5   453.5
Abutment Skew #Up #Dn= , 2 , 2
    3479    3531
   455.5   468.5
    3475    3527
   455.5   468.5
BR Coef=-1 , 0 , 0 ,, 0 ,,,0.8,0,,0,
WSPro=,,,, 1 ,,,, 0 ,,,, 0 ,,,,-1 ,-1 ,-1 , 0 , 0 , 0 , 0 , 0
BR U #Sta/Elev= 66
       0  464.71  129.84  464.67  327.73  464.75  625.24  464.74  802.56  464.55
  922.16  464.17 1028.99  464.01 1394.84  463.88  1425.8   463.7 1475.79  463.23
 1483.89  463.01 1497.11  461.67 1501.96     461 1525.36  458.11 1538.32  458.12
 1548.41  457.12 1565.98   456.8  1674.5  456.76 1689.53   457.1 1692.97  457.26
  1708.3  457.79 1720.13  458.16 1779.45   458.2 1802.97  458.09 1829.07  457.57
 1863.87  456.97 1912.82  456.63 2029.32   456.7  2070.8  456.69 2181.44  456.27
 2191.97  456.64 2205.66  457.54 2236.63  458.18 2287.88  458.54    2307   458.2
    2394   457.6    2439   457.7    2515   457.4    2607   457.4    2694   457.1
    2761   457.2    2840   457.4    2933   457.8    3019   459.2    3097   460.2
 3179.08  461.33 3190.63  460.62 3215.63   460.5 3318.63   460.7 3358.63   454.2
 3371.63   445.5 3384.63   438.3 3387.63   436.2 3389.63   434.4 3400.63   431.9
 3418.63  428.89 3434.63   436.2 3437.63   436.4 3443.63   440.3 3447.63   441.7
 3465.63   456.7    3490 460.808 3500.63   462.6 3507.63   462.5 3545.63   460.9
  3560.6  461.58
BR U #Mann= 4
       0     .08  1708.3      .1 3318.63     .05    3490    .055
BR D #Sta/Elev= 104
       0  465.12   30.35  465.76   73.88  465.49  129.45  465.45  177.77  465.37
  195.69  465.23  246.96  464.63  271.62  462.64  282.82  461.76  301.73  461.39
  314.33  461.15  343.21  460.97  381.89  459.75  414.09  459.03  434.07  458.62
  537.06  458.29  624.21  458.12  655.69  457.63  816.66  457.64  941.48  457.56
 1025.87  457.53 1166.68  457.59  1404.2  457.29 1428.94  457.22 1462.33  457.11
 1511.04     457 1582.11  456.94  1624.8  457.32 1735.91  457.79 1796.65  457.94
 1810.58  457.78 1815.14  457.14 1829.21  456.91 1862.63  456.79  1900.4  456.63
 1900.68  456.62 1906.19  456.59 1939.87  456.54 2005.96  456.58 2034.26  456.39
  2049.1  456.57 2107.36  456.56 2131.11  456.69 2222.87  457.31 2268.36  458.03
 2323.29  458.05 2333.89  458.03 2389.48   458.1 2449.53  457.61 2456.06  457.54
 2477.99  457.55 2478.23  457.55 2478.36  457.55 2478.67  457.55 2534.84  457.75
 2597.28  457.75 2642.93  457.74 2728.44  457.87 2752.49  457.56 2800.47  457.28
 2870.07  457.35 2961.64  457.37 3003.29  457.48 3013.26  458.03 3029.11  458.94
 3037.19  459.22 3072.23  459.84 3092.15  460.12 3121.24  460.54 3141.43  461.04
 3181.94  460.91 3182.35  460.91 3197.48  460.86 3211.75  460.83 3270.35  460.51
 3298.35   460.7 3338.35   454.2 3351.35   445.5 3364.35   438.3 3367.35   436.2
 3369.35   434.4 3380.35   431.9 3398.35  428.89 3414.35   436.2 3417.35   436.4
 3423.35   440.3 3427.35   441.7 3445.35   456.7 3457.77  459.28 3459.88   459.5
 3463.03  460.11 3466.23  460.41 3474.58  461.15 3484.76  460.78 3499.65   460.4
 3504.92  460.33 3517.14  460.46 3518.48  460.44 3521.54   460.5 3537.01  460.61
 3542.34   460.7 3554.78  460.76 3571.13  460.62 3580.68  461.15
BR D #Mann= 4
       0     .08 1796.65      .1 3298.35     .05 3466.23    .055
BC Design=,, 0 ,, 0 ,,,,,,
BC Use User HTab Curves=0
BC User HTab FreeFlow(D)= 0

Type RM Length L Ch R = 1 ,144215  ,55.07,66.26,73.83
BEGIN DESCRIPTION:
144314-lowered top of bank
Added cross-section
END DESCRIPTION:
XS GIS Cut Line= 6
2442892.676920137064614.43901515 2442351.88928787064437.77401415
2441137.221113477064423.540118722439797.230683227064022.59144557
2439782.736617717064018.254511982439420.335439647063893.71998414
#Sta/Elev= 30
       0  465.12  195.69  465.23  246.96  464.63  282.82  461.76  434.07  458.62
  655.69  457.63 1582.11  456.94 1796.65  457.94 1829.21  456.91 2034.26  456.39
 2268.36  458.03 2961.64  457.37 3003.29  457.48 3037.19  459.22 3141.43  461.04
 3298.35   460.7 3338.35   454.2 3351.35   445.5 3364.35   438.3 3369.35   434.4
 3398.35  428.89 3414.35   436.2 3417.35   436.4 3423.35   440.3 3427.35   441.7
 3445.35   456.7 3466.23  460.41 3474.58  461.15 3504.92  460.33 3580.68  461.15
#Mann= 4 ,-1,0
       0     .08       0 1796.65     .12       0 3298.35     .05       0
 3466.23    .055       0
#XS Ineff= 2 , 0
            1514   468.5    3490           468.5
Permanent Ineff=
       F       F
Bank Sta=3298.35,3466.23
XS Rating Curve= 0 ,0
Exp/Cntr=0.3,0.1

Type RM Length L Ch R = 6 ,144200  ,,,
BEGIN DESCRIPTION:
Corporate Drive Embankment- Test
END DESCRIPTION:
Lateral Weir Pos= 3
Lateral Weir End=Elm Fork Split2 ,efs2            ,137852  ,
Lateral Weir Distance=0
Lateral Weir TW Multiple XS=-1
Lateral Weir WD=75
Lateral Weir Coef=2
LW OverFlow Method 2D=0
LW OverFlow Use Velocity Into 2D=0
Lateral Weir WSCriteria=-1
Lateral Weir Flap Gates= 0
Lateral Weir Hagers EQN= 0 ,,,,,
Lateral Weir SS=0.05,0.05,
Lateral Weir Type= 0
Lateral Weir Connection Pos and Dist= 0 ,47
Lateral Weir SE= 30
       0   473.2      50  472.32     175  468.84     250  466.22     450   477.5
     650  460.42     730  460.68     805  460.46     905  459.86     980  459.62
    1055  459.86    1115  460.22    1190  460.44    1360  459.86    1560  460.62
    1760  459.86    1960  460.62    2160  459.86    2360  460.62    2560  459.86
    2760  460.62    2835   460.4    2905  459.98    2980  459.74    3180   460.5
    3380  459.74    3455  459.98    3525   460.4    3635  460.38    3656  460.26
Lateral Weir Centerline= 0
Lateral Weir HW RS User Defined=-1
Lateral Weir HW RS Station=144215  ,0
Lateral Weir HW RS Station=144148. ,509
Lateral Weir HW RS Station=143756  ,1087
Lateral Weir HW RS Station=143265  ,1361
Lateral Weir HW RS Station=142900  ,1717
Lateral Weir HW RS Station=142702. ,1873
Lateral Weir HW RS Station=142389  ,2045
Lateral Weir HW RS Station=141891  ,2328
Lateral Weir HW RS Station=141518  ,2852
Lateral Weir HW RS Station=141084  ,3656
Lateral Weir TW RS User Defined=-1
Lateral Weir TW RS Station=137852  ,-47
Lateral Weir TW RS Station=137770  ,136
Lateral Weir TW RS Station=137601  ,364
Lateral Weir TW RS Station=137395  ,670
Lateral Weir TW RS Station=137068  ,1087
Lateral Weir TW RS Station=136811  ,1361
Lateral Weir TW RS Station=136440  ,1717
Lateral Weir TW RS Station=136289  ,1873
Lateral Weir TW RS Station=135812  ,2328
Lateral Weir TW RS Station=135252  ,2852
Lateral Weir TW RS Station=134940  ,3163
Lateral Weir TW RS Station=134668  ,3656
LW Div RC= 0 ,False,,