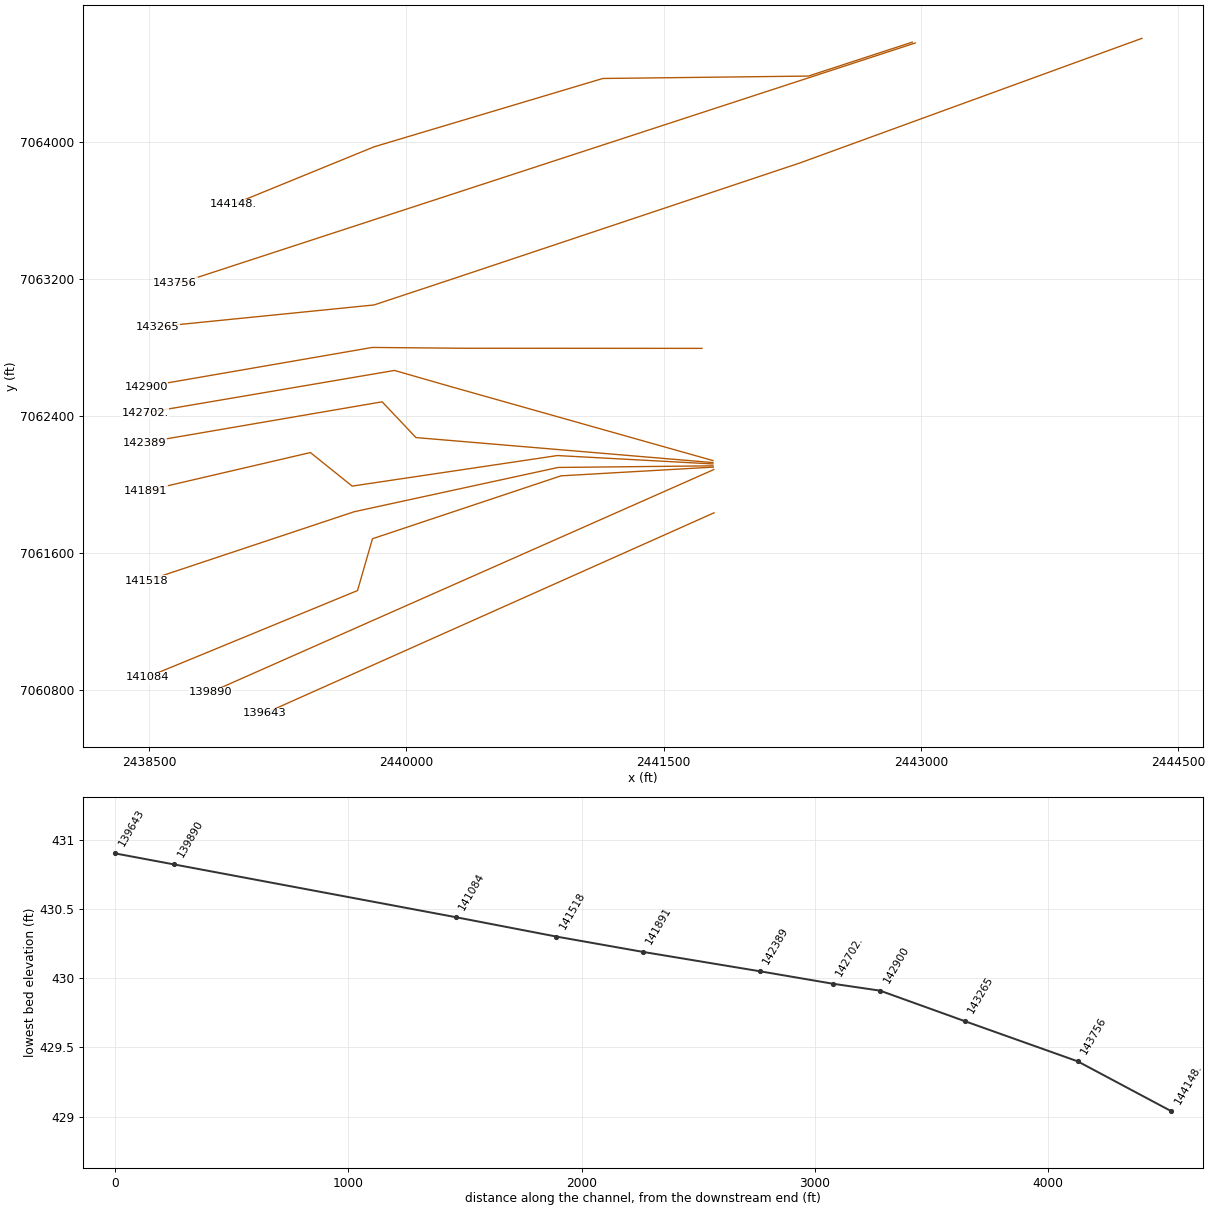
HEC-RAS study CDC_Consolidated_Model.prj: Upper Trinity CDC Consolidated Model

--- CDC_Consolidated_Model.g13 (geometry) --- (continued)

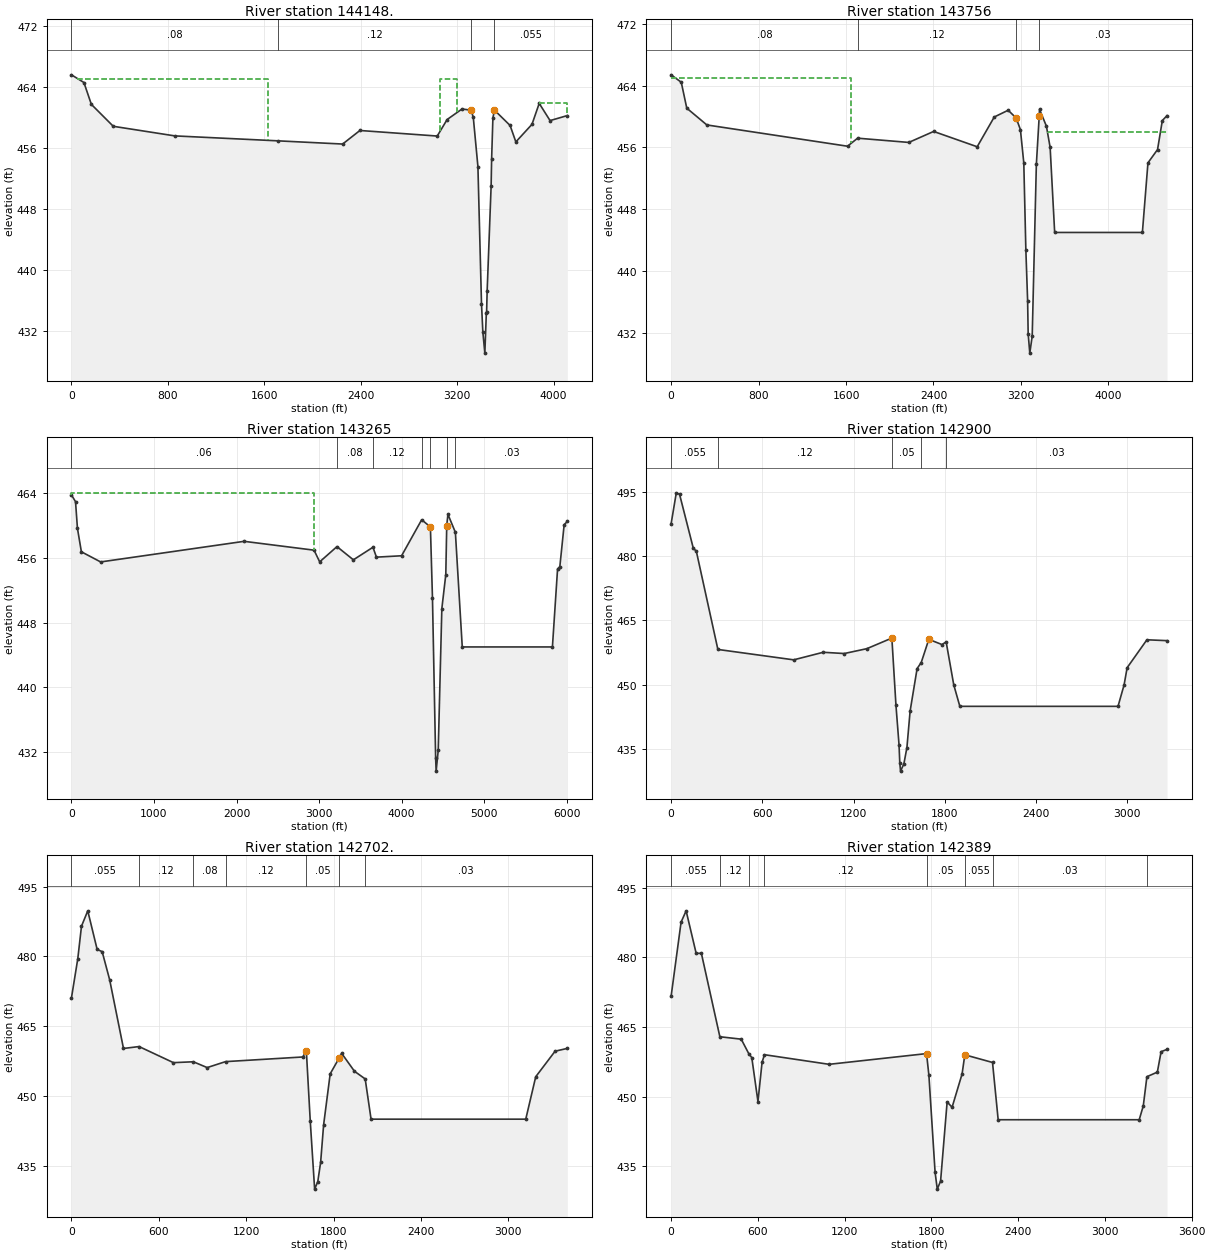
Type RM Length L Ch R = 1 ,144148. ,410.4,401.61,382.07
BEGIN DESCRIPTION:
144148 - changedn= .115 to .12 and .033 to .03.ROB modified with field surveys 2/2 from sta 3532
Added XS for Lewisville Atheltic Complex CLOMR.
END DESCRIPTION:
XS GIS Cut Line= 6
2442950.106923397064580.600172062442344.258397557064382.68094848
2441145.588222737064368.634388642439812.592857237063970.22836131
2439812.592857237063970.228033232438991.611887637063634.69688015
#Sta/Elev= 30
       0  465.59   103.4  464.58  165.05  461.71  346.99  458.83  857.33  457.57
 1713.32  456.92 2249.68   456.5 2393.13  458.28 3034.67  457.55 3116.82  459.72
 3239.88   461.1  3315.8  460.95 3333.81  459.99 3372.15  453.54 3401.85  435.53
 3412.93  431.83 3429.65  429.04 3441.93  434.28 3444.24  434.44 3448.84  437.22
 3481.79  451.02 3485.78   454.5 3496.49  459.93  3509.5  460.95 3639.14  458.94
 3686.85  456.78 3820.84  459.09 3880.67  461.84 3970.66  459.58 4114.27  460.24
#Mann= 4 ,-1,0
       0     .08       0 1713.32     .12       0  3315.8     .05       0
  3509.5    .055       0
#XS Ineff= 3 ,-1
      50    1630     465    3059    3202     465 3880.67 4114.27  461.85
Permanent Ineff=
       F       F       F
Bank Sta=3315.8,3509.5
XS Rating Curve= 0 ,0
Exp/Cntr=0.3,0.1

Type RM Length L Ch R = 1 ,143756  ,483.08,484.38,452.53
BEGIN DESCRIPTION:
143756- pool elev 445
Proposed Park Improvements - 13187.64-14694.95
END DESCRIPTION:
XS GIS Cut Line= 5
2442967.555051227064575.779971732442203.023115727064326.02194107
2440036.451661477063618.245141392438700.961878397063181.96648639
 2438652.36322237063177.97305606
#Sta/Elev= 30
       0  465.38   92.65  464.42  143.02  461.07  326.84   458.9 1613.84  456.15
 1706.24  457.19 2174.26  456.64 2401.76  458.06 2800.12  456.08 2956.51  459.93
 3083.54   460.8 3156.54   459.8 3195.54   458.3 3226.54     454 3245.54   442.7
 3261.54   436.2 3266.54   431.9 3281.54   429.4 3303.54   431.6 3341.54   453.8
 3367.54     460  3370.4  460.92 3433.59  458.74 3467.54     456 3509.05     445
 4311.59     445 4362.54     454 4450.31  455.72 4494.12  459.47 4537.25  460.11
#Mann= 4 ,-1,0
       0     .08       0 1706.24     .12       0 3156.54     .05       0
 3367.54     .03       0
#XS Ineff= 2 , 0
            1650     465    3445             458
Permanent Ineff=
       F       T
Bank Sta=3156.54,3367.54
XS Rating Curve= 0 ,0
Exp/Cntr=0.3,0.1

Type RM Length L Ch R = 1 ,143265  ,394.85,363.29,360.57
BEGIN DESCRIPTION:
nvalues from CDC were interpolated, changed based on image
END DESCRIPTION:
XS GIS Cut Line= 5
2444288.765991467064602.811741812442298.064920387063877.10485989
2440283.132270477063203.965130062439811.656835477063047.71248981
2438549.622286057062921.01195581
#Sta/Elev= 30
       0  463.74   49.23  462.91   72.45  459.62  120.15  456.73   353.6  455.48
 2091.76  458.02 2939.15  456.93 3007.38  455.49 3216.94  457.37 3415.59  455.74
 3652.86  457.29 3695.02  456.07 3999.74  456.24 4243.25  460.68  4348.9  459.79
  4373.9  451.03 4412.18  431.37 4418.27  429.69 4443.64  432.24 4487.47  449.73
 4535.38  453.92  4546.8  459.97 4561.31  461.35 4651.49  459.13  4734.9     445
 5827.24     445 5889.57  454.61 5917.06   454.9 5969.54  460.08 6008.32  460.47
#Mann= 7 ,-1,0
       0     .06       0 3216.94     .08       0 3652.86     .12       0
 4243.25      .1       0  4348.9     .05       0  4546.8     .08       0
 4651.49     .03       0
#XS Ineff= 2 , 0
            2940     464    4635             454
Permanent Ineff=
       F       T
Bank Sta=4348.9,4546.8
XS Rating Curve= 0 ,0
Exp/Cntr=0.3,0.1

Type RM Length L Ch R = 1 ,142900  ,223.14,202.73,220.73
BEGIN DESCRIPTION:
142900
Proposed Park Improvements
END DESCRIPTION:
XS GIS Cut Line= 4
2441723.820005897062794.578153572440313.501960387062795.30026498
2439801.955083227062799.989888152438482.719532717062571.69670956
#Sta/Elev= 30
       0  487.55   33.87  494.73   55.48  494.37  145.97  481.78  165.36  481.17
  307.36  458.25  805.73  455.83  999.87  457.59 1138.26   457.3 1286.79  458.43
 1451.32   460.9 1478.32   445.2 1498.32   436.1 1503.32   431.9 1508.32  429.91
 1530.32   431.6 1550.32   435.4 1571.32   443.9 1617.32   453.8 1644.32   455.2
 1694.32   460.6 1780.32   459.4 1808.32     460 1858.32     450 1898.32     445
 2938.32     445 2978.32     450 2998.32     454 3128.32   460.5 3260.73   460.3
#Mann= 5 ,-1,0
       0    .055       0  307.36     .12       0 1451.32     .05       0
 1644.32      .1       0 1808.32     .03       0
#XS Ineff= 2 , 0
                            1875             447
Permanent Ineff=
       F       T
Bank Sta=1451.32,1694.32
XS Rating Curve= 0 ,0
Exp/Cntr=0.3,0.1

Type RM Length L Ch R = 1 ,142702. ,346,313.16,243.63
BEGIN DESCRIPTION:
142702- nvalues from CDC were interpolated, changed based on image
Added XS for Lewisville Atheltic Complex CLOMR.
END DESCRIPTION:
XS GIS Cut Line= 4
2441788.056097887062140.064370722440256.699580557062572.29841439
2439931.224509727062665.840222062438477.144740727062418.04741056
#Sta/Elev= 30
       0  471.08   43.52  479.51   68.81  486.48  111.94  489.79  176.39  481.49
  210.74  481.02  262.38  474.95  357.19   460.2  464.31  460.61  700.15  457.15
  836.81  457.34  931.72  456.09 1057.85  457.37 1588.17  458.37 1612.75  459.67
 1639.68  444.52 1669.61  429.96 1691.18  431.57 1710.78   435.7 1731.37   443.8
 1776.46  454.75  1839.4  458.23 1855.14  459.15 1943.02   455.3 2016.72  453.65
 2057.06     445 3119.19     445 3187.68  454.12 3320.53  459.61 3404.88  460.22
#Mann= 7 ,-1,0
       0    .055       0  464.31     .12       0  836.81     .08       0
 1057.85     .12       0 1612.75     .05       0  1839.4     .09       0
 2016.72     .03       0
Bank Sta=1612.75,1839.4
XS Rating Curve= 0 ,0
Exp/Cntr=0.3,0.1

Type RM Length L Ch R = 1 ,142389  ,478.69,502.3,356.1
XS GIS Cut Line= 4
2441787.438973147062128.391821892440056.373209557062274.29933847
2439859.210218067062482.889472482438473.964957067062245.04513189
#Sta/Elev= 30
       0  471.64   68.78  487.57  103.61  490.01  173.03  480.85  209.06  480.86
  336.96  462.88  484.69  462.36  536.53  459.26   557.8  458.38  600.44  448.92
  629.01  457.41  645.53  459.01 1092.47  456.94 1766.43  459.25 1782.76  454.54
 1825.49  433.68 1840.56  430.05 1863.51  431.78 1908.73  448.83 1943.12  447.69
 2012.33  454.88 2031.07  458.99 2222.67  457.34 2261.77     445  3237.2     445
  3265.4  447.99 3290.42  454.27 3362.66  455.26 3388.63  459.66 3429.74  460.16
#Mann= 8 ,-1,0
       0    .055       0  336.96     .12       0  536.53     .07       0
  645.53     .12       0 1766.43     .05       0 2031.07    .055       0
 2222.67     .03       0 3290.42    .045       0
Bank Sta=1766.43,2031.07
XS Rating Curve= 0 ,0
Exp/Cntr=0.3,0.1

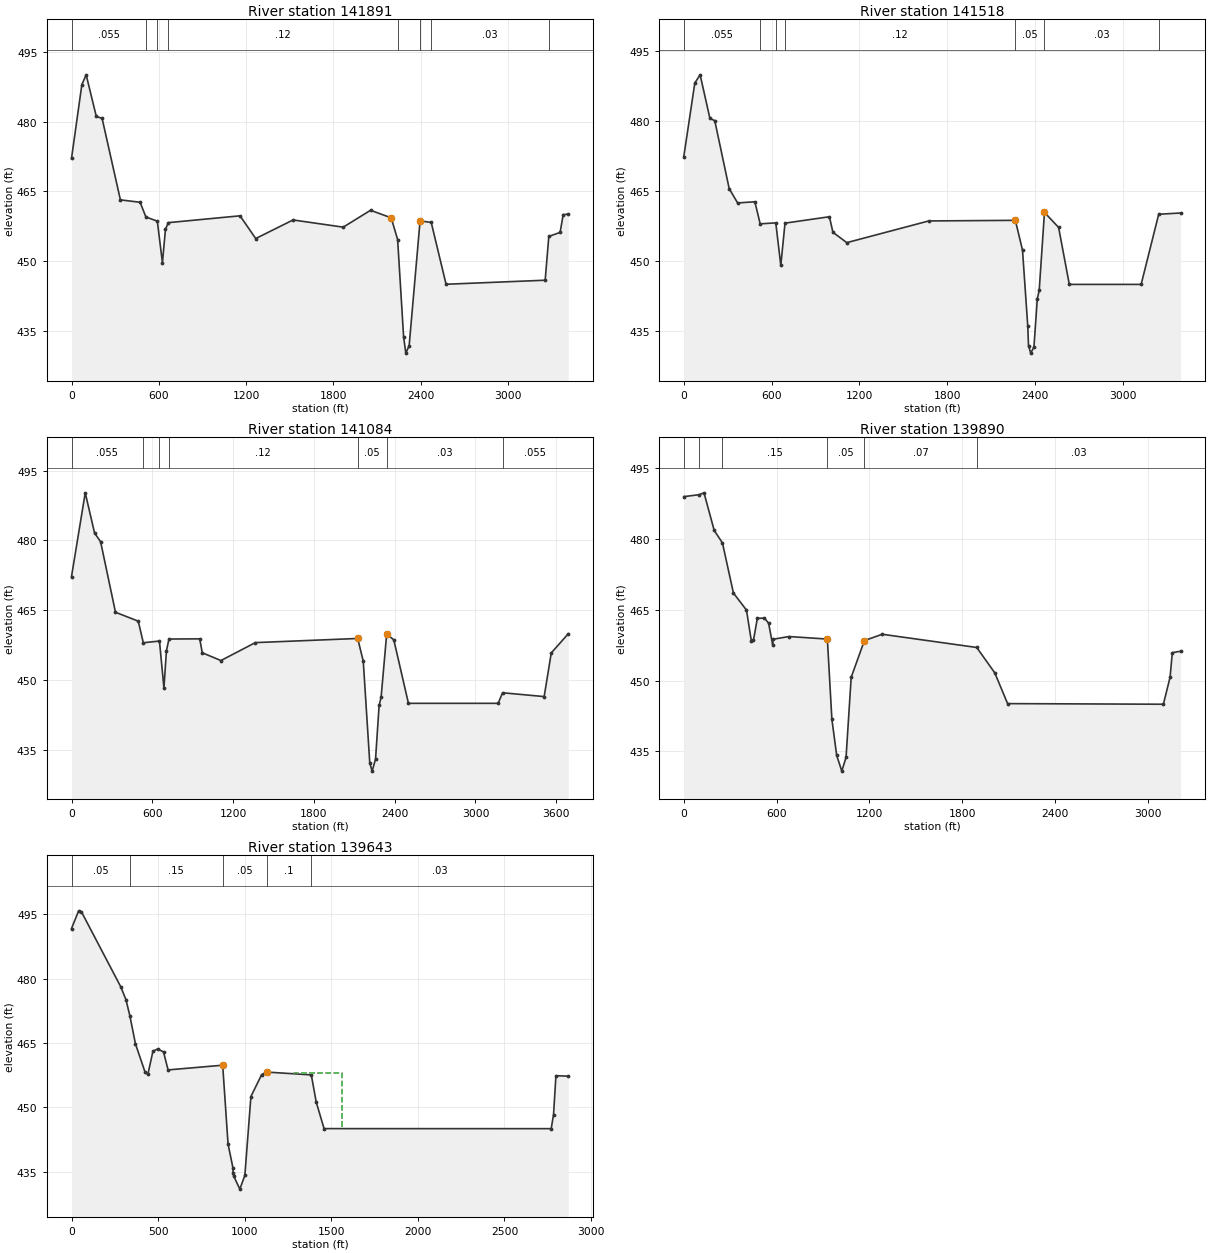
Type RM Length L Ch R = 1 ,141891  ,211.7,369.28,456.69
BEGIN DESCRIPTION:
141891- CDC nvalue seems interpolated, changed based on image
Added XS for Lewisville Atheltic Complex CLOMR.
END DESCRIPTION:
XS GIS Cut Line= 5
2441786.955706397062120.573924142440880.734421727062169.45637231
2439684.471722387061991.272673562439440.918403717062186.91565497
2438480.731347727061963.32062973
#Sta/Elev= 30
       0  472.06   71.27  487.94  100.83  490.04  170.52  481.08  210.22  480.69
   336.1  463.15  471.44  462.63   511.5  459.47  590.03  458.57  625.15  449.63
  645.86   456.8  665.71  458.25 1158.72  459.72 1266.44  454.83 1523.13  458.83
 1868.08  457.28    2056  460.91 2197.83  459.29 2242.09  454.62 2283.29  433.68
 2298.36  430.19 2321.31  431.78 2396.41  458.62 2473.07   458.3 2575.19     445
 3256.49  445.87 3281.49  455.29 3359.22  456.15 3380.29  459.97 3415.28  460.09
#Mann= 8 ,-1,0
       0    .055       0   511.5     .12       0  590.03     .07       0
  665.71     .12       0 2242.09     .05       0 2396.41    .055       0
 2473.07     .03       0 3281.49     .06       0
Bank Sta=2197.83,2396.41
XS Rating Curve= 0 ,0
Exp/Cntr=0.3,0.1

Type RM Length L Ch R = 1 ,141518  ,246.52,431.69,493.6
BEGIN DESCRIPTION:
141518
Proposed Park Improvements
END DESCRIPTION:
XS GIS Cut Line= 4
2441787.953735897062109.484707472440885.074964237062100.01195739
2439696.058641467061841.726384732438484.872415567061438.31708656
#Sta/Elev= 30
       0  472.35   75.18  488.07  111.52  489.82  178.32  480.52   211.7  480.01
  310.27  465.48  367.86  462.42  485.75  462.67  522.08  457.95  628.81  458.16
  663.06  449.07  691.91   458.1  995.55  459.47 1019.34  456.15 1114.33  453.93
 1674.39  458.57 2266.68   458.7 2315.68   452.3 2351.68     436 2356.68   431.9
 2371.68   430.3 2393.68   431.6 2416.68   441.9 2429.68   443.7 2465.68   460.4
  2562.4  457.18 2635.63     445 3126.68     445 3246.68     460 3396.28  460.27
#Mann= 7 ,-1,0
       0    .055       0  522.08     .12       0  628.81     .07       0
  691.91     .12       0 2266.68     .05       0 2465.68     .03       0
 3246.68     .06       0
Bank Sta=2266.68,2465.68
XS Rating Curve= 0 ,0
Exp/Cntr=0.3,0.1

Type RM Length L Ch R = 1 ,141084  ,735.17,1206.23,331.19
BEGIN DESCRIPTION:
141084 moved top of bank and channel n 2/11 ey  nvalues from CDC were interpolated, changed based on image
Added XS for Lewisville Atheltic Complex CLOMR.
Swale normal pool elevation 453.5
END DESCRIPTION:
XS GIS Cut Line= 5
2441789.911409147062102.063462482440902.268827477062051.16133331
2439802.91472697 7061684.33365492439715.718379057061382.08983681
2438489.299900137060877.03605689
#Sta/Elev= 30
       0  472.23  102.03  490.21  171.12   481.6  216.27  479.69  326.59  464.56
  495.57  462.65  533.32  458.01   653.2  458.38  686.37  448.29  704.91  456.28
  723.72  458.81   952.2  458.85  970.98  455.86 1109.67  454.19 1365.03  458.04
 2125.25  458.93 2166.65  454.04 2214.94  432.18 2232.61  430.44 2257.86  433.04
 2284.25  444.54 2299.17  446.33 2340.49  459.89 2393.39  458.64 2502.04     445
 3168.04     445 3201.17  447.27 3509.89  446.45 3562.76  455.83 3688.95  459.94
#Mann= 7 ,-1,0
       0    .055       0  533.32     .12       0   653.2     .07       0
  723.72     .12       0 2125.25     .05       0 2340.49     .03       0
 3201.17    .055       0
Bank Sta=2125.25,2340.49
XS Rating Curve= 0 ,0
Exp/Cntr=0.3,0.1

Type RM Length L Ch R = 1 ,139890  ,248.08,254.42,372.2
BEGIN DESCRIPTION:
139890- nvalues from CDC were interpolated, changed based on image
Added XS for Lewisville Atheltic Complex CLOMR.
Swale normal pool elevation 453.5
END DESCRIPTION:
XS GIS Cut Line= 2
2441793.06888314 7062087.77740182438856.738141647060787.81313823
#Sta/Elev= 30
       0     489   99.79  489.42  130.54  489.81  196.46  481.84  249.62   479.2
  320.73  468.57  405.05  464.96  436.74  458.37  449.95  458.51   475.4   463.2
  521.21  463.27  548.06  462.17  574.14  457.66  576.94  458.77  679.58  459.35
  927.94  458.81  957.17  441.81  988.28  434.15 1021.28  430.82 1048.79  433.74
 1081.99  450.71 1167.37  458.49 1282.55  459.83  1893.5  457.03 2009.83  451.67
 2093.09  445.13    3100     445  3143.4  450.72 3157.79  455.93 3211.22  456.23
#Mann= 6 ,-1,0
       0     .05       0   99.79     .09       0  249.62     .15       0
  927.94     .05       0 1167.37     .07       0  1893.5     .03       0
Bank Sta=927.94,1167.37
XS Rating Curve= 0 ,0
Exp/Cntr=0.3,0.1

Type RM Length L Ch R = 1 ,139643  ,732.06,1144.33,1021.86
BEGIN DESCRIPTION:
139643-  corrected left side of pond  and left landfill 2/11ey. IFA to block area without convayance ey2/11
---------------------------------------------------------------------
CDC LEW110305-1 Lewisville Athletic Complex
Cross-section 139643 - 146373
Project located in ROB.
---------------------------------------------------------------------
END DESCRIPTION:
XS GIS Cut Line= 2
2441794.045587237061835.381909222439174.835274477060665.72775248
#Sta/Elev= 30
       0  491.67   41.17   495.8   57.12  495.59   284.5  478.08  314.48  475.08
  336.95  471.33  369.14   464.8  425.21  458.13  441.13  457.68  470.28  463.06
  497.09  463.58  531.33  462.91  557.59   458.7     873   459.8     904   441.4
     932   435.9     933   434.6     937   433.9     972   430.9    1001   434.1
    1036   452.5    1098   457.6    1126   458.2 1384.67  457.54 1413.27  451.17
 1458.39  445.01  2769.9     445 2783.52  448.29  2797.3  457.35 2868.51  457.24
#Mann= 5 ,-1,0
       0     .05       0  336.95     .15       0     873     .05       0
    1126      .1       0 1384.67     .03       0
#XS Ineff= 1 ,-1
    1286    1560     458
Permanent Ineff=
       T
Bank Sta=873,1126
XS Rating Curve= 0 ,0
Exp/Cntr=0.3,0.1