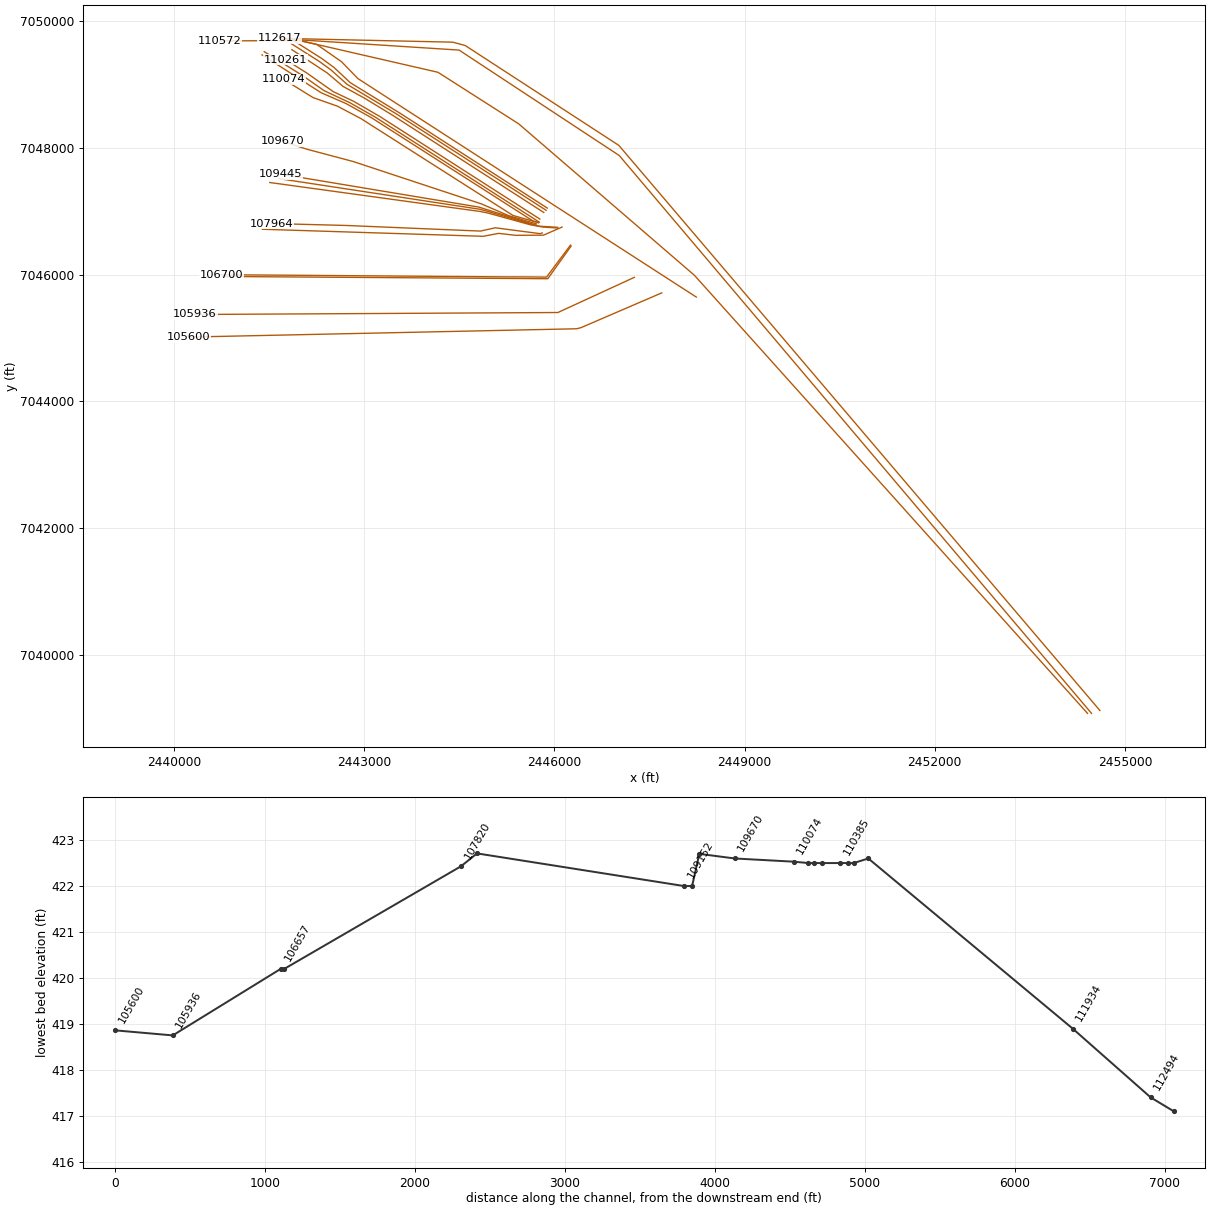
HEC-RAS study CDC_Consolidated_Model.prj: Upper Trinity CDC Consolidated Model

--- CDC_Consolidated_Model.g13 (geometry) --- (continued)

Type RM Length L Ch R = 3 ,112622  ,,,
BEGIN DESCRIPTION:
Union Pacific Railroad
END DESCRIPTION:
Node Name=UP Railroad
Bridge Culvert--1,0,-1,-1, 0
Deck Dist Width WeirC Skew NumUp NumDn MinLoCord MaxHiCord MaxSubmerge Is_Ogee
1,8,2.6,0, 22, 22, , , 0.95, 0, ,,,
    7520  7545.2  7548.8  7572.2  7575.8  7599.2  7602.8    7629    7629    7826
    7952    8030    8030  8060.3  8065.7  8093.3  8098.7  8126.3  8131.7    8158
    8164    8336
     452  452.05  452.05   452.1   452.1  452.15  452.15   452.2   452.2   452.9
   454.3   454.4   454.4  454.49  454.51  454.59  454.61  454.69  454.71  454.79
  454.81   455.2
   449.2  449.25  449.25   449.3   449.3  449.35  449.35   449.4   452.2   452.9
   454.3   454.4   451.6  451.69  451.71  451.79  451.81  451.89  451.91  451.99
  451.81   452.2
    7520  7545.2  7548.8  7572.2  7575.8  7599.2  7602.8    7629    7629    7826
    7952    8030    8030  8060.3  8065.7  8093.3  8098.7  8126.3  8131.7    8158
    8164    8336
     452  452.05  452.05   452.1   452.1  452.15  452.15   452.2   452.2   452.9
   454.3   454.4   454.4  454.49  454.51  454.59  454.61  454.69  454.71  454.79
  454.81   455.2
   449.2  449.25  449.25   449.3   449.3  449.35  449.35   449.4   452.2   452.9
   454.3   454.4   451.6  451.69  451.71  451.79  451.81  451.89  451.91  451.99
  451.81   452.2
Pier Skew, UpSta & Num, DnSta & Num=  ,7547, 2 ,7547, 2 , 0 , 0 , 0 ,,
     3.6     3.6
     430     450
     3.6     3.6
     430     450
Pier Skew, UpSta & Num, DnSta & Num=  ,7574, 2 ,7574, 2 , 0 , 0 , 0 ,,
     3.6     3.6
     430     450
     3.6     3.6
     430     450
Pier Skew, UpSta & Num, DnSta & Num=  ,7601, 2 ,7601, 2 , 0 , 0 , 0 ,,
     3.6     3.6
     430     450
     3.6     3.6
     430     450
Pier Skew, UpSta & Num, DnSta & Num=  ,8063, 2 ,8063, 2 , 0 , 0 , 0 ,,
     5.4     5.4
     430     454
     5.4     5.4
     430     454
Pier Skew, UpSta & Num, DnSta & Num=  ,8096, 2 ,8096, 2 , 0 , 0 , 0 ,,
     5.4     5.4
     430     454
     5.4     5.4
     430     454
Pier Skew, UpSta & Num, DnSta & Num=  ,8129, 2 ,8129, 2 , 0 , 0 , 0 ,,
     5.4     5.4
     430     454
     5.4     5.4
     430     454
Pier Skew, UpSta & Num, DnSta & Num=  ,8161, 2 ,8161, 2 , 0 , 0 , 0 ,,
       6       6
     430     454
       6       6
     430     454
BR Coef= 1 , 0 , 0 ,1.05, 0 ,,,0.8,-1,0.5,1,
WSPro=,,,, 1 ,,,, 0 ,,,, 0 ,,,,-1 ,-1 ,-1 , 0 , 0 , 0 , 0 , 0
BC Design=,, 0 ,, 0 ,,,,,,
BC HTab HWMax=455.3
BC Use User HTab Curves=0
BC User HTab FreeFlow(D)= 0

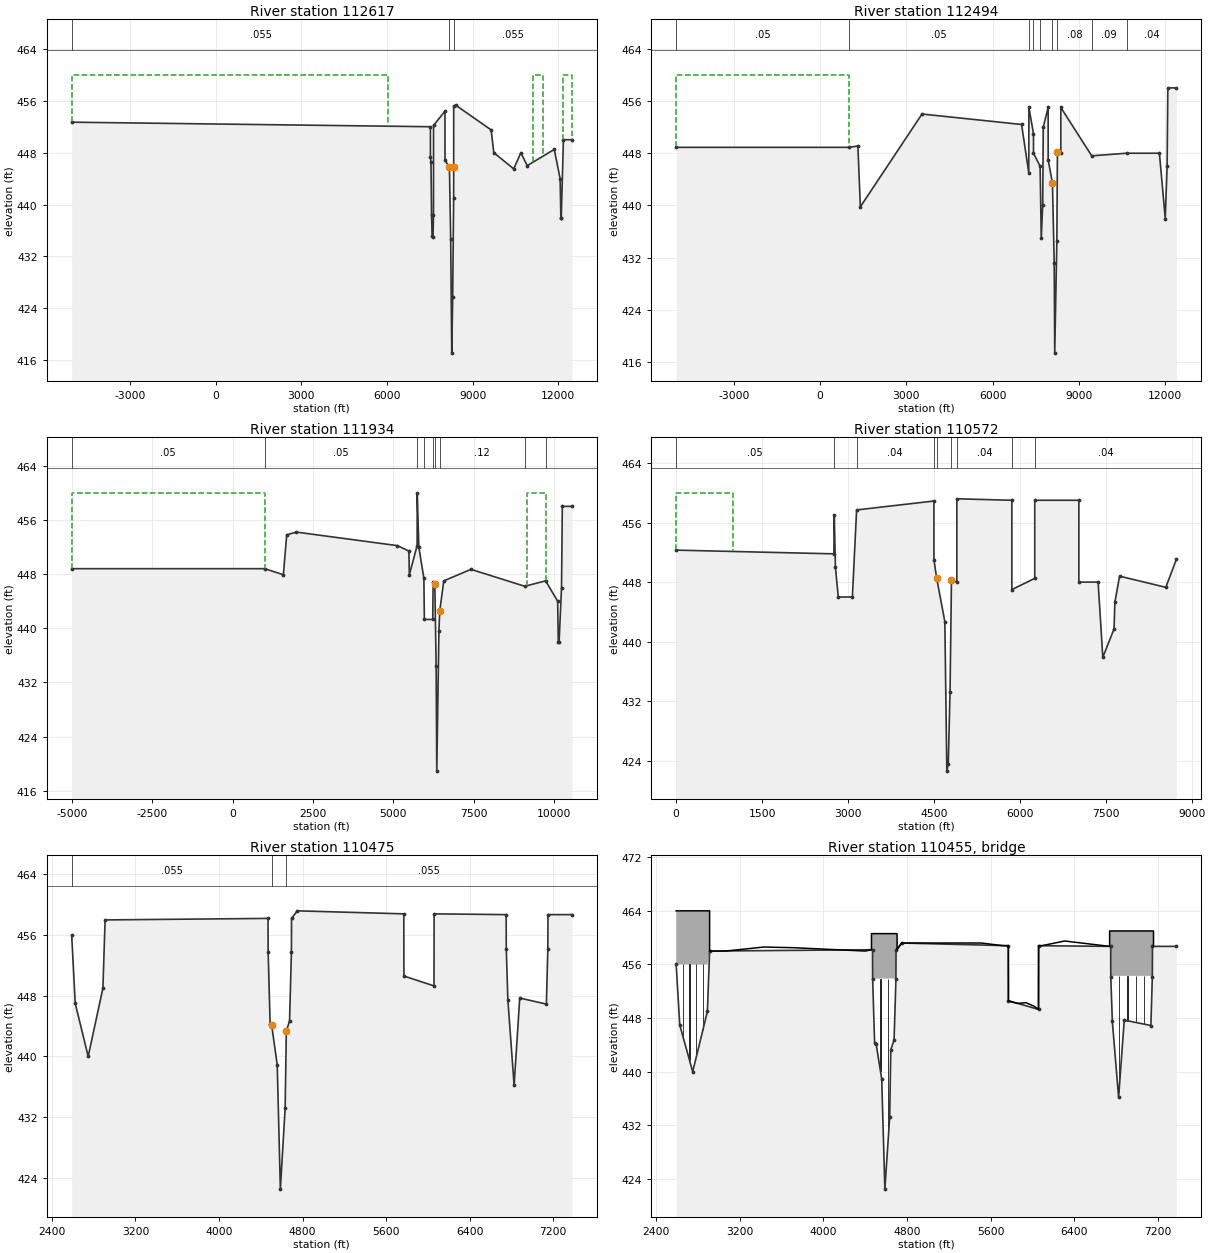
Type RM Length L Ch R = 1 ,112617  ,162,153,124
BEGIN DESCRIPTION:
This cross section corresponds to cross section 112617 of the non-georeferenced CDC model which was the source of this model.
END DESCRIPTION:
XS GIS Cut Line= 6
2454605.014264917039124.507053422447018.87863243 7048036.0893788
2447013.258564927048040.778673892444593.936960017049613.46155213
2444398.688990927049666.366301972441667.776814547049726.94189283
#Sta/Elev= 30
   -5050   452.7    7520     452    7521   447.3    7540   446.5    7560   438.4
    7579   435.1    7612     435    7628   438.4    7629   452.2    8030   454.4
    8031   446.8    8186   445.8    8230   434.7    8268   417.1    8300   425.7
    8334     441    8335   445.8    8336   455.2    8414   455.3    9650   451.5
    9740     448   10440   445.5   10690     448   10910     446   11860   448.5
   12065     444   12090     438   12105     438   12180     450   12480     450
#Mann= 3 ,0,0
   -5050    .055       0    8186     .05       0    8335    .055       0
#XS Ineff= 3 ,-1
   -5050    6050     460   11100   11480     460   12180   12480     460
Permanent Ineff=
       F       F       F
Bank Sta=8186,8335
XS Rating Curve= 0 ,0
Exp/Cntr=0.5,0.3

Type RM Length L Ch R = 1 ,112494  ,512,521,326
BEGIN DESCRIPTION:
This cross section corresponds to cross section 112494 of the non-georeferenced CDC model which was the source of this model.
END DESCRIPTION:
XS GIS Cut Line= 6
  2454473.107568 7039078.9619397  2450596.258944  7043658.268082
 2447023.7788851 7047878.0562303 2444497.0109728 7049541.6582181
 2441966.4149841 7049704.1467382  2441667.031509 7049723.3700271
#Sta/Elev= 30
   -5000   448.9    1000   448.9    1316   449.1    1402   439.8    3545     454
    7006   452.4    7256     445    7260     455    7420     451    7420     448
    7650     446    7690     435    7740     440    7760     452    7930     455
    7930     447    8079   443.4    8140   431.2    8158   417.4    8232   434.5
    8252   448.2    8370     448    8370     455    9444   447.6   10658     448
   11797     448   12000     438   12065     446   12090     458   12390     458
#Mann= 9 ,-1,0
   -5000     .05       0    1000     .05       0    7260     .05       0
    7420     .03       0    7650     .06       0    8079     .05       0
    8252     .08       0    9444     .09       0   10658     .04       0
#XS Ineff= 3 ,-1
   -5000    1000     460    1000    8079   443.4    8252   12090   448.2
Permanent Ineff=
       F       F       F
Bank Sta=8079,8252
XS Rating Curve= 0 ,0
Exp/Cntr=0.3,0.1

Type RM Length L Ch R = 1 ,111934  ,800,1362,500
BEGIN DESCRIPTION:
This cross section corresponds to cross section 111934 of the non-georeferenced CDC model which was the source of this model.
END DESCRIPTION:
XS GIS Cut Line= 6
  2454410.107568 7039078.9619397 2448208.9070922 7045989.4530521
  2445438.210862 7048377.4951921 2444163.3745009 7049191.5850993
  2441975.089179  7049694.151679  2441675.089179  7049694.151679
#Sta/Elev= 30
   -5000   448.8    1000   448.8    1579   447.9    1684   453.8    1985   454.2
    5127   452.2    5481   451.4    5495   447.9    5737   452.2    5740     460
    5790     452    5947   447.4    5962   441.3    6222   441.3    6235   446.9
    6288   446.5    6328   434.4    6348   418.9    6415   439.6    6439   442.5
    6565     447    7410   448.7    9083   446.2    9730     447   10105     444
   10125     438   10150     438   10225     446   10250     458   10550     458
#Mann= 9 ,-1,0
   -5000     .05       0    1000     .05       0    5740     .05       0
    5947     .03       0    6235     .06       0    6288     .05       0
    6439     .12       0    9083    .055       0    9730     .04       0
#XS Ineff= 5 ,-1
   -5000    1000     460    5740    6288   446.5    6439    9150   442.5
    9150    9730     460    9730   10250   442.5
Permanent Ineff=
       F       F       F       F       F
Bank Sta=6288,6439
XS Rating Curve= 0 ,0
Exp/Cntr=0.3,0.1

Type RM Length L Ch R = 1 ,110572  ,98,98,98
BEGIN DESCRIPTION:
This cross section corresponds to cross section 110572 of the non-georeferenced CDC model which was the source of this model.
END DESCRIPTION:
XS GIS Cut Line= 6
2448239.216124777045645.43833622 2442902.2979548   7049091.26509
  2442643.503853 7049357.4450038 2442253.2192005 7049629.6347481
 2441975.9927208 7049693.0739257 2440726.5552591 7049685.8642945
#Sta/Elev= 30
       0   452.3    2753   451.8    2760     457    2780     450    2830     446
    3076     446    3150   457.7    4500   458.9    4500     451    4546   448.6
    4690   442.7    4725   422.6    4750   423.6    4781   433.2    4806   448.3
    4900     448    4900   459.2    5860     459    5860     447    6260   448.5
    6260     459    7030     459    7030     448    7366     448    7448   437.9
    7644   441.7    7659   445.3    7741   448.8    8548   447.3    8734   451.1
#Mann= 9 ,-1,0
       0     .05       0    2760     .05       0    3150     .04       0
    4500      .1       0    4546     .05       0    4806     .12       0
    4900     .04       0    5860     .12       0    6260     .04       0
#XS Ineff= 3 ,-1
       0    1000     460    1000    4546   448.6    4806    8734   448.3
Permanent Ineff=
       F       F       F
Bank Sta=4546,4806
XS Rating Curve= 0 ,0
Exp/Cntr=0.3,0.1

Type RM Length L Ch R = 1 ,110475  ,40,40,40
BEGIN DESCRIPTION:
This cross section corresponds to cross section 110475 of the non-georeferenced CDC model which was the source of this model.
END DESCRIPTION:
XS GIS Cut Line= 6
2445889.135157027047048.917468642443576.38125235 7048539.1297113
2442780.950100427049027.153669632442524.952580937049266.50358464
2442331.572390267049408.48361564 2441896.70743697049684.46347108
#Sta/Elev= 30
    2590     456    2624     447    2748     440    2889     449    2910     458
    4470   458.2    4471   453.8    4490   444.3    4505   444.1    4558   438.9
    4588   422.5    4634   433.2    4645   443.3    4676   444.7    4694   453.8
    4695   458.2    4750   459.2    5770   458.8    5771   450.6    6059   449.3
    6060   458.8    6750   458.7    6751   454.2    6766   447.5    6826   436.2
    6880   447.7    7135   446.9    7149   454.2    7150   458.7    7380   458.7
#Mann= 3 ,0,0
    2590    .055       0    4505     .05       0    4645    .055       0
#XS Ineff= 2 , 0
            4505   444.1    4645           443.3
Permanent Ineff=
       F       F
Bank Sta=4505,4645
XS Rating Curve= 0 ,0
Exp/Cntr=0.5,0.3

Type RM Length L Ch R = 3 ,110455  ,,,
BEGIN DESCRIPTION:
IH 35E Access Road North Bound
END DESCRIPTION:
Node Name=IH 35E access ro
Bridge Culvert--1,0,-1,-1, 0
Deck Dist Width WeirC Skew NumUp NumDn MinLoCord MaxHiCord MaxSubmerge Is_Ogee
2,36,2.6,0, 28, 28, , , 0.95, 0, ,,,
    2590    2910    2910    3060    3430    3720    4400    4460    4460    4705
    4705    4750    5510    5720    5770    5771    5802    5864    5938    6014
    6059    6060    6090    6310    6740    6740    7160    7160
     464     464     458     458   458.6   458.5     458   458.2   460.6   460.6
   458.2   459.2   459.2   458.8   458.8   450.6   450.4   450.2   450.3   449.8
   449.3   458.8   458.8   459.5   458.7     461     461   458.7
     456     456     458     458   458.6   458.5     458   458.2   453.9   453.9
   458.2   459.2   459.2   458.8   458.8   450.6   450.4   450.2   450.3   449.8
   449.3   458.8   458.8   459.5   458.7   454.3   454.3   458.7
    2590    2910    2910    3060    3430    3720    4400    4460    4460    4705
    4705    4750    5510    5720    5770    5771    5802    5864    5938    6014
    6059    6060    6090    6310    6740    6740    7160    7160
     464     464     458     458   458.6   458.5     458   458.2   460.6   460.6
   458.2   459.2   459.2   458.8   458.8   450.6   450.4   450.2   450.3   449.8
   449.3   458.8   458.8   459.5   458.7     461     461   458.7
     456     456     458     458   458.6   458.5     458   458.2   453.9   453.9
   458.2   459.2   459.2   458.8   458.8   450.6   450.4   450.2   450.3   449.8
   449.3   458.8   458.8   459.5   458.7   454.3   454.3   458.7
Pier Skew, UpSta & Num, DnSta & Num=  ,2654, 2 ,2654, 2 , 0 , 0 , 0 ,,
       3       3
     400     460
       3       3
     400     460
Pier Skew, UpSta & Num, DnSta & Num=  ,2718, 2 ,2718, 2 , 0 , 0 , 0 ,,
       3       3
     400     460
       3       3
     400     460
Pier Skew, UpSta & Num, DnSta & Num=  ,2782, 2 ,2782, 2 , 0 , 0 , 0 ,,
       3       3
     400     460
       3       3
     400     460
Pier Skew, UpSta & Num, DnSta & Num=  ,2846, 2 ,2846, 2 , 0 , 0 , 0 ,,
       3       3
     400     460
       3       3
     400     460
Pier Skew, UpSta & Num, DnSta & Num=  ,2910, 2 ,2910, 2 , 0 , 0 , 0 ,,
       3       3
     400     460
       3       3
     400     460
Pier Skew, UpSta & Num, DnSta & Num=  ,4545, 2 ,4545, 2 , 0 , 0 , 0 ,,
     2.5     2.5
     420     459
     2.5     2.5
     420     459
Pier Skew, UpSta & Num, DnSta & Num=  ,4620, 2 ,4620, 2 , 0 , 0 , 0 ,,
     2.5     2.5
     420     459
     2.5     2.5
     420     459
Pier Skew, UpSta & Num, DnSta & Num=  ,6830, 2 ,6830, 2 , 0 , 0 , 0 ,,
     2.5     2.5
     420     459
     2.5     2.5
     420     459
Pier Skew, UpSta & Num, DnSta & Num=  ,6910, 2 ,6910, 2 , 0 , 0 , 0 ,,
     2.5     2.5
     420     459
     2.5     2.5
     420     459
Pier Skew, UpSta & Num, DnSta & Num=  ,6990, 2 ,6990, 2 , 0 , 0 , 0 ,,
     2.5     2.5
     420     459
     2.5     2.5
     420     459
Pier Skew, UpSta & Num, DnSta & Num=  ,7070, 2 ,7070, 2 , 0 , 0 , 0 ,,
     2.5     2.5
     420     459
     2.5     2.5
     420     459
BR Coef= 1 , 0 , 0 ,1.05, 0 ,,,0.8,-1,0.5,1,
WSPro=,,,, 1 ,,,, 0 ,,,, 0 ,,,,-1 ,-1 ,-1 , 0 , 0 , 0 , 0 , 0
BC Design=,, 0 ,, 0 ,,,,,,
BC HTab HWMax=459.5
BC Use User HTab Curves=0
BC User HTab FreeFlow(D)= 0

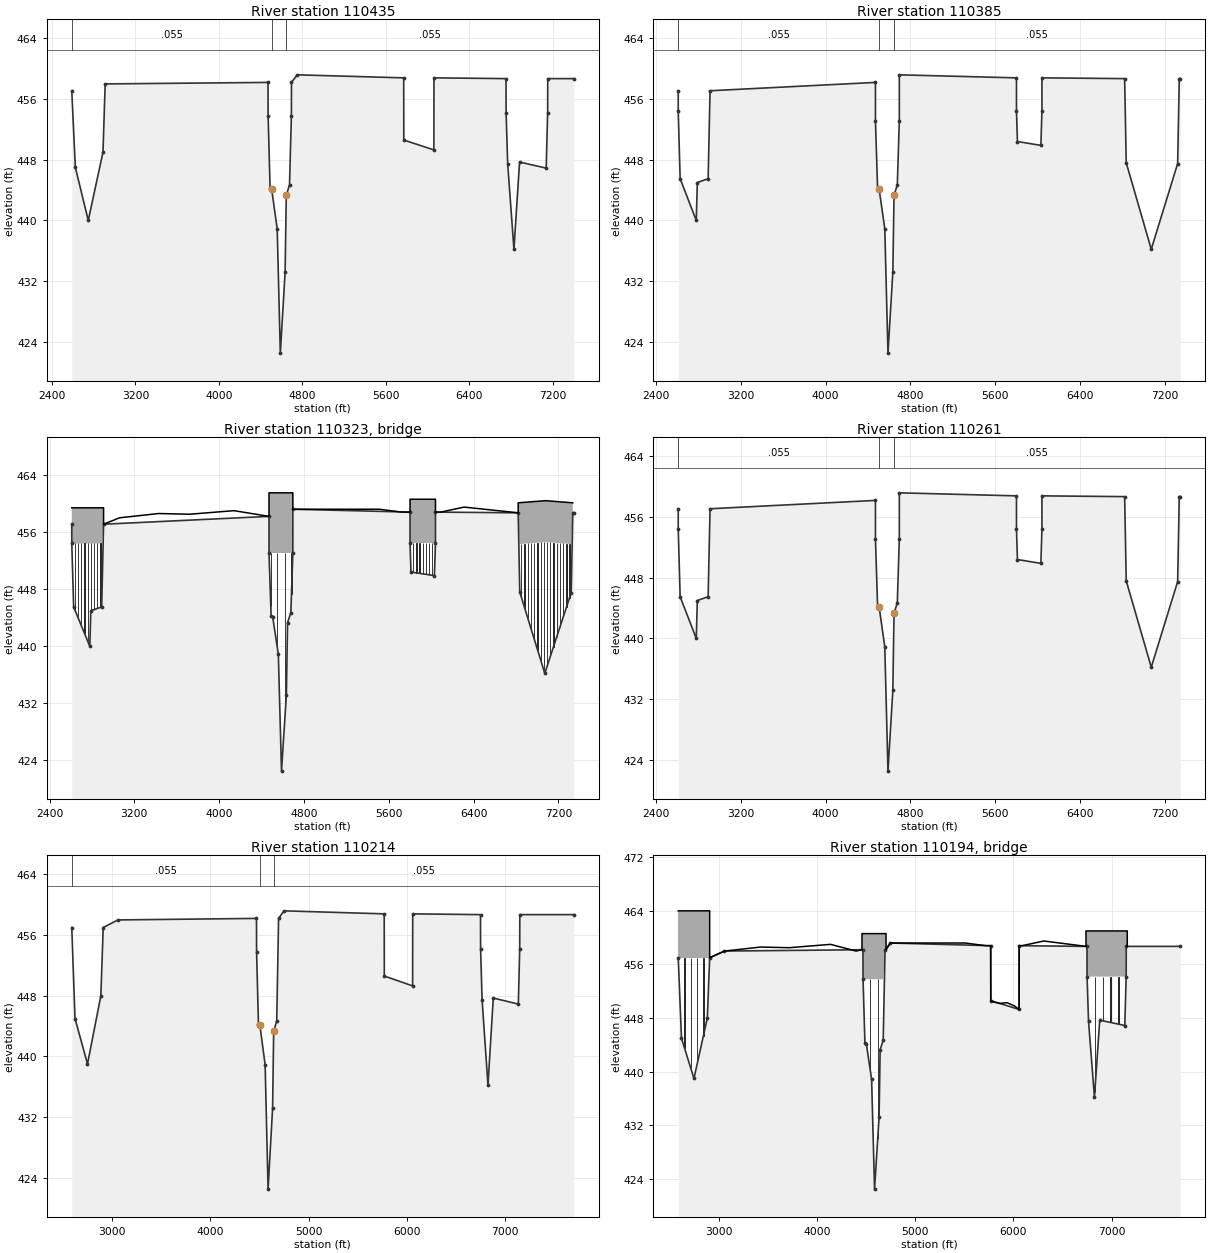
Type RM Length L Ch R = 1 ,110435  ,50,50,50
BEGIN DESCRIPTION:
This cross section corresponds to cross section 110435 of the non-georeferenced CDC model which was the source of this model.
END DESCRIPTION:
XS GIS Cut Line= 6
2445869.466233077047014.833875392443513.550341257048531.47060588
2442730.790751937049000.757725052442476.094739027049228.98397464
2442285.974056247049366.696297632441847.896182547049644.10178698
#Sta/Elev= 30
    2590   457.1    2624     447    2748     440    2889     449    2910     458
    4470   458.2    4471   453.8    4490   444.3    4505   444.1    4558   438.9
    4588   422.5    4634   433.2    4645   443.3    4676   444.7    4694   453.8
    4695   458.2    4750   459.2    5770   458.8    5771   450.6    6059   449.3
    6060   458.8    6750   458.7    6751   454.2    6766   447.5    6826   436.2
    6880   447.7    7135   446.9    7149   454.2    7150   458.7    7400   458.7
#Mann= 3 ,0,0
    2590    .055       0    4505     .05       0    4645    .055       0
#XS Ineff= 2 , 0
            4505   444.1    4645           443.3
Permanent Ineff=
       F       F
Bank Sta=4505,4645
XS Rating Curve= 0 ,0
Exp/Cntr=0.5,0.3

Type RM Length L Ch R = 1 ,110385  ,124,124,124
BEGIN DESCRIPTION:
This cross section corresponds to cross section 110385 of the non-georeferenced CDC model which was the source of this model.
END DESCRIPTION:
XS GIS Cut Line= 6
2445832.607711027046980.278498312443436.633828437048520.88007589
 2443003.60385467048784.099693812442668.024801347048967.78633431
2442415.038758757049182.07429156 2441859.38173367049547.82224771
#Sta/Elev= 30
    2610   457.1    2610   454.4    2628   445.5    2780     440    2790     445
    2892   445.5    2910   457.1    4470   458.2    4470   453.1    4490   444.3
    4505   444.1    4558   438.9    4588   422.5    4634   433.2    4645   443.3
    4676   444.7    4695   453.1    4695   459.2    5800   458.8    5800   454.4
    5809   450.4    6030   449.9    6040   454.4    6040   458.8    6820   458.7
    6835   447.6    7071   436.2    7320   447.5    7335   458.7    7345   458.7
#Mann= 3 ,0,0
    2610    .055       0    4505     .05       0    4645    .055       0
#XS Ineff= 2 , 0
            4505   444.1    4645           443.3
Permanent Ineff=
       F       F
Bank Sta=4505,4645
XS Rating Curve= 0 ,0
Exp/Cntr=0.5,0.3

Type RM Length L Ch R = 3 ,110323  ,,,
BEGIN DESCRIPTION:
IH 35E/Stemmons Freeway
END DESCRIPTION:
Node Name=IH 635E
Bridge Culvert--1,0,-1,-1, 0
Deck Dist Width WeirC Skew NumUp NumDn MinLoCord MaxHiCord MaxSubmerge Is_Ogee
1,122,2.6,0, 25, 25, , , 0.95, 0, ,,,
    2610    2910    2910    3060    3430    3720    4140    4470    4470    4695
    4695    5510    5720  5783.5  5788.5    5800    5800    6040    6040    6090
    6310    6820    6820    7078    7335
   459.4   459.4   457.1     458   458.6   458.5     459   458.2   461.5   461.5
   459.2   459.2   458.8   458.8   458.8   458.8   460.6   460.6   458.8   458.8
   459.5   458.7   460.1   460.4   460.1
   454.4   454.4   457.1     458   458.6   458.5     459   458.2   453.1   453.1
   459.2   459.2   458.8   458.8   458.8   458.8   454.4   454.4   458.8   458.8
   459.5   458.7   454.3   454.6   454.3
    2610    2910    2910    3060    3430    3720    4140    4470    4470    4695
    4695    5510    5720  5783.5  5788.5    5800    5800    6040    6040    6090
    6310    6820    6820    7078    7335
   459.4   459.4   457.1     458   458.6   458.5     459   458.2   461.5   461.5
   459.2   459.2   458.8   458.8   458.8   458.8   460.6   460.6   458.8   458.8
   459.5   458.7   460.1   460.4   460.1
   454.4   454.4   457.1     458   458.6   458.5     459   458.2   453.1   453.1
   459.2   459.2   458.8   458.8   458.8   458.8   454.4   454.4   458.8   458.8
   459.5   458.7   454.3   454.6   454.3
Pier Skew, UpSta & Num, DnSta & Num=  ,2640, 2 ,2640, 2 , 0 , 0 , 0 ,,
     2.5     2.5
     400     457
     2.5     2.5
     400     457
Pier Skew, UpSta & Num, DnSta & Num=  ,2670, 2 ,2670, 2 , 0 , 0 , 0 ,,
     2.5     2.5
     420     458
     2.5     2.5
     420     458
Pier Skew, UpSta & Num, DnSta & Num=  ,2700, 2 ,2700, 2 , 0 , 0 , 0 ,,
     2.5     2.5
     400     457
     2.5     2.5
     400     457
Pier Skew, UpSta & Num, DnSta & Num=  ,2730, 2 ,2730, 2 , 0 , 0 , 0 ,,
     2.5     2.5
     400     457
     2.5     2.5
     400     457
Pier Skew, UpSta & Num, DnSta & Num=  ,2760, 2 ,2760, 2 , 0 , 0 , 0 ,,
     2.5     2.5
     400     457
     2.5     2.5
     400     457
Pier Skew, UpSta & Num, DnSta & Num=  ,2790, 2 ,2790, 2 , 0 , 0 , 0 ,,
     2.5     2.5
     400     457
     2.5     2.5
     400     457
Pier Skew, UpSta & Num, DnSta & Num=  ,2820, 2 ,2820, 2 , 0 , 0 , 0 ,,
     2.5     2.5
     400     457
     2.5     2.5
     400     457
Pier Skew, UpSta & Num, DnSta & Num=  ,2850, 2 ,2850, 2 , 0 , 0 , 0 ,,
     2.5     2.5
     400     457
     2.5     2.5
     400     457
Pier Skew, UpSta & Num, DnSta & Num=  ,2880, 2 ,2880, 2 , 0 , 0 , 0 ,,
     2.5     2.5
     400     457
     2.5     2.5
     400     457
Pier Skew, UpSta & Num, DnSta & Num=  ,4487, 2 ,4487, 2 , 0 , 0 , 0 ,,
     2.5     2.5
     428     458
     2.5     2.5
     428     458
Pier Skew, UpSta & Num, DnSta & Num=  ,4547, 2 ,4547, 2 , 0 , 0 , 0 ,,
     2.5     2.5
     428     458
     2.5     2.5
     428     458
Pier Skew, UpSta & Num, DnSta & Num=  ,4622, 2 ,4622, 2 , 0 , 0 , 0 ,,
     2.5     2.5
     428     458
     2.5     2.5
     428     458
Pier Skew, UpSta & Num, DnSta & Num=  ,4682, 2 ,4682, 2 , 0 , 0 , 0 ,,
     2.5     2.5
     428     458
     2.5     2.5
     428     458
Pier Skew, UpSta & Num, DnSta & Num=  ,5830, 2 ,5830, 2 , 0 , 0 , 0 ,,
     2.5     2.5
     400     460
     2.5     2.5
     400     460
Pier Skew, UpSta & Num, DnSta & Num=  ,5860, 2 ,5860, 2 , 0 , 0 , 0 ,,
     2.5     2.5
     400     460
     2.5     2.5
     400     460
Pier Skew, UpSta & Num, DnSta & Num=  ,5890, 2 ,5890, 2 , 0 , 0 , 0 ,,
     2.5     2.5
     400     460
     2.5     2.5
     400     460
Pier Skew, UpSta & Num, DnSta & Num=  ,5920, 2 ,5920, 2 , 0 , 0 , 0 ,,
     2.5     2.5
     400     460
     2.5     2.5
     400     460
Pier Skew, UpSta & Num, DnSta & Num=  ,5950, 2 ,5950, 2 , 0 , 0 , 0 ,,
     2.5     2.5
     400     460
     2.5     2.5
     400     460
Pier Skew, UpSta & Num, DnSta & Num=  ,5980, 2 ,5980, 2 , 0 , 0 , 0 ,,
     2.5     2.5
     400     460
     2.5     2.5
     400     460
Pier Skew, UpSta & Num, DnSta & Num=  ,6010, 2 ,6010, 2 , 0 , 0 , 0 ,,
     2.5     2.5
     400     460
     2.5     2.5
     400     460
Pier Skew, UpSta & Num, DnSta & Num=  ,6850, 2 ,6850, 2 , 0 , 0 , 0 ,,
     2.5     2.5
     400     460
     2.5     2.5
     400     460
Pier Skew, UpSta & Num, DnSta & Num=  ,6880, 2 ,6880, 2 , 0 , 0 , 0 ,,
     2.5     2.5
     400     460
     2.5     2.5
     400     460
Pier Skew, UpSta & Num, DnSta & Num=  ,6911, 2 ,6911, 2 , 0 , 0 , 0 ,,
     2.5     2.5
     400     460
     2.5     2.5
     400     460
Pier Skew, UpSta & Num, DnSta & Num=  ,6941, 2 ,6941, 2 , 0 , 0 , 0 ,,
     2.5     2.5
     400     460
     2.5     2.5
     400     460
Pier Skew, UpSta & Num, DnSta & Num=  ,6971, 2 ,6971, 2 , 0 , 0 , 0 ,,
     2.5     2.5
     400     460
     2.5     2.5
     400     460
Pier Skew, UpSta & Num, DnSta & Num=  ,7002, 2 ,7002, 2 , 0 , 0 , 0 ,,
     2.5     2.5
     400     460
     2.5     2.5
     400     460
Pier Skew, UpSta & Num, DnSta & Num=  ,7032, 2 ,7032, 2 , 0 , 0 , 0 ,,
     2.5     2.5
     400     460
     2.5     2.5
     400     460
Pier Skew, UpSta & Num, DnSta & Num=  ,7062, 2 ,7062, 2 , 0 , 0 , 0 ,,
     2.5     2.5
     400     460
     2.5     2.5
     400     460
Pier Skew, UpSta & Num, DnSta & Num=  ,7093, 2 ,7093, 2 , 0 , 0 , 0 ,,
     2.5     2.5
     400     460
     2.5     2.5
     400     460
Pier Skew, UpSta & Num, DnSta & Num=  ,7123, 2 ,7123, 2 , 0 , 0 , 0 ,,
     2.5     2.5
     400     460
     2.5     2.5
     400     460
Pier Skew, UpSta & Num, DnSta & Num=  ,7153, 2 ,7153, 2 , 0 , 0 , 0 ,,
     2.5     2.5
     400     460
     2.5     2.5
     400     460
Pier Skew, UpSta & Num, DnSta & Num=  ,7184, 2 ,7184, 2 , 0 , 0 , 0 ,,
     2.5     2.5
     400     460
     2.5     2.5
     400     460
Pier Skew, UpSta & Num, DnSta & Num=  ,7214, 2 ,7214, 2 , 0 , 0 , 0 ,,
     2.5     2.5
     400     460
     2.5     2.5
     400     460
Pier Skew, UpSta & Num, DnSta & Num=  ,7244, 2 ,7244, 2 , 0 , 0 , 0 ,,
     2.5     2.5
     400     460
     2.5     2.5
     400     460
Pier Skew, UpSta & Num, DnSta & Num=  ,7275, 2 ,7275, 2 , 0 , 0 , 0 ,,
     2.5     2.5
     400     460
     2.5     2.5
     400     460
Pier Skew, UpSta & Num, DnSta & Num=  ,7305, 2 ,7305, 2 , 0 , 0 , 0 ,,
     2.5     2.5
     400     460
     2.5     2.5
     400     460
BR Coef= 1 , 0 , 0 ,1.05, 0 ,,,0.8,-1,0.5,1,
WSPro=,,,, 1 ,,,, 0 ,,,, 0 ,,,,-1 ,-1 ,-1 , 0 , 0 , 0 , 0 , 0
BC Design=,, 0 ,, 0 ,,,,,,
BC HTab HWMax=459.5
BC Use User HTab Curves=0
BC User HTab FreeFlow(D)= 0

Type RM Length L Ch R = 1 ,110261  ,47,47,47
BEGIN DESCRIPTION:
This cross section corresponds to cross section 110261 of the non-georeferenced CDC model which was the source of this model.
END DESCRIPTION:
XS GIS Cut Line= 6
2445770.994973337046876.246882222443242.692287187048496.66194847
2442834.748877357048732.865872382442512.141582947048886.09588088
2442087.692300597049184.879075962441762.372741257049388.64999388
#Sta/Elev= 30
    2610   457.1    2610   454.4    2628   445.5    2780     440    2790     445
    2892   445.5    2910   457.1    4470   458.2    4470   453.1    4490   444.3
    4505   444.1    4558   438.9    4588   422.5    4634   433.2    4645   443.3
    4676   444.7    4695   453.1    4695   459.2    5800   458.8    5800   454.4
    5809   450.4    6030   449.9    6040   454.4    6040   458.8    6820   458.7
    6835   447.6    7071   436.2    7320   447.5    7335   458.7    7345   458.7
#Mann= 3 ,0,0
    2610    .055       0    4505     .05       0    4645    .055       0
#XS Ineff= 2 , 0
            4505   444.1    4645           443.3
Permanent Ineff=
       F       F
Bank Sta=4505,4645
XS Rating Curve= 0 ,0
Exp/Cntr=0.5,0.3

Type RM Length L Ch R = 1 ,110214  ,40,40,40
BEGIN DESCRIPTION:
This cross section corresponds to cross section 110214 of the non-georeferenced CDC model which was the source of this model.
END DESCRIPTION:
XS GIS Cut Line= 6
2445762.770580357046827.490746132443169.604178767048487.20986763
2442769.662065277048713.997471792442370.318375777048900.07616788
2442034.175019177049135.741707062441423.469173657049516.99107139
#Sta/Elev= 30
    2590     457    2623     445    2750     439    2886     448    2910     457
    3060     458    4470   458.2    4471   453.8    4490   444.3    4505   444.1
    4558   438.9    4588   422.5    4634   433.2    4645   443.3    4676   444.7
    4695   458.2    4750   459.2    5770   458.8    5771   450.6    6059   449.3
    6060   458.8    6750   458.7    6751   454.2    6766   447.5    6826   436.2
    6880   447.7    7135   446.9    7149   454.2    7150   458.7    7700   458.7
#Mann= 3 ,0,0
    2590    .055       0    4505     .05       0    4645    .055       0
#XS Ineff= 2 , 0
            4505   444.1    4645           443.3
Permanent Ineff=
       F       F
Bank Sta=4505,4645
XS Rating Curve= 0 ,0
Exp/Cntr=0.5,0.3

Type RM Length L Ch R = 3 ,110194  ,,,
BEGIN DESCRIPTION:
IH 35E Access Road South Bound
END DESCRIPTION:
Node Name=IH 35E access ro
Bridge Culvert--1,0,-1,-1, 0
Deck Dist Width WeirC Skew NumUp NumDn MinLoCord MaxHiCord MaxSubmerge Is_Ogee
1.5,37,2.6,0, 29, 29, , , 0.95, 0, ,,,
    2590    2910    2910    3060    3430    3720    4140    4400    4460    4460
    4705    4705    4750    5510    5720    5770    5771    5802    5864    5938
    6014    6059    6060    6090    6310    6740    6740    7160    7160
     464     464     457     458   458.6   458.5     459     458   458.2   460.6
   460.6   458.2   459.2   459.2   458.8   458.8   450.6   450.4   450.2   450.3
   449.8   449.3   458.8   458.8   459.5   458.7     461     461   458.7
     457     457     457     458   458.6   458.5     459     458   458.2   453.8
   453.8   458.2   459.2   459.2   458.8   458.8   450.6   450.4   450.2   450.3
   449.8   449.3   458.8   458.8   459.5   458.7   454.2   454.2   458.7
    2590    2910    2910    3060    3430    3720    4140    4400    4460    4460
    4705    4705    4750    5510    5720    5770    5771    5802    5864    5938
    6014    6059    6060    6090    6310    6740    6740    7160    7160
     464     464     457     458   458.6   458.5     459     458   458.2   460.6
   460.6   458.2   459.2   459.2   458.8   458.8   450.6   450.4   450.2   450.3
   449.8   449.3   458.8   458.8   459.5   458.7     461     461   458.7
     457     457     457     458   458.6   458.5     459     458   458.2   453.8
   453.8   458.2   459.2   459.2   458.8   458.8   450.6   450.4   450.2   450.3
   449.8   449.3   458.8   458.8   459.5   458.7   454.2   454.2   458.7
Pier Skew, UpSta & Num, DnSta & Num=  ,2654, 2 ,2654, 2 , 0 , 0 , 0 ,,
       3       3
     420     458
       3       3
     420     458
Pier Skew, UpSta & Num, DnSta & Num=  ,2718, 2 ,2718, 2 , 0 , 0 , 0 ,,
       3       3
     420     458
       3       3
     420     458
Pier Skew, UpSta & Num, DnSta & Num=  ,2782, 2 ,2782, 2 , 0 , 0 , 0 ,,
       3       3
     420     458
       3       3
     420     458
Pier Skew, UpSta & Num, DnSta & Num=  ,2846, 2 ,2846, 2 , 0 , 0 , 0 ,,
       3       3
     420     458
       3       3
     420     458
Pier Skew, UpSta & Num, DnSta & Num=  ,4545, 2 ,4545, 2 , 0 , 0 , 0 ,,
     2.5     2.5
     420     459
     2.5     2.5
     420     459
Pier Skew, UpSta & Num, DnSta & Num=  ,4620, 2 ,4620, 2 , 0 , 0 , 0 ,,
     2.5     2.5
     428     459
     2.5     2.5
     428     459
Pier Skew, UpSta & Num, DnSta & Num=  ,6830, 2 ,6830, 2 , 0 , 0 , 0 ,,
     2.5     2.5
     428     459
     2.5     2.5
     428     459
Pier Skew, UpSta & Num, DnSta & Num=  ,6910, 2 ,6910, 2 , 0 , 0 , 0 ,,
     2.5     2.5
     428     459
     2.5     2.5
     428     459
Pier Skew, UpSta & Num, DnSta & Num=  ,6990, 2 ,6990, 2 , 0 , 0 , 0 ,,
     2.5     2.5
     428     459
     2.5     2.5
     428     459
Pier Skew, UpSta & Num, DnSta & Num=  ,7070, 2 ,7070, 2 , 0 , 0 , 0 ,,
     2.5     2.5
     428     459
     2.5     2.5
     428     459
BR Coef= 1 , 0 , 0 ,1.05, 0 ,,,0.8,-1,0.5,1,
WSPro=,,,, 1 ,,,, 0 ,,,, 0 ,,,,-1 ,-1 ,-1 , 0 , 0 , 0 , 0 , 0
BC Design=,, 0 ,, 0 ,,,,,,
BC HTab HWMax=459.5
BC Use User HTab Curves=0
BC User HTab FreeFlow(D)= 0

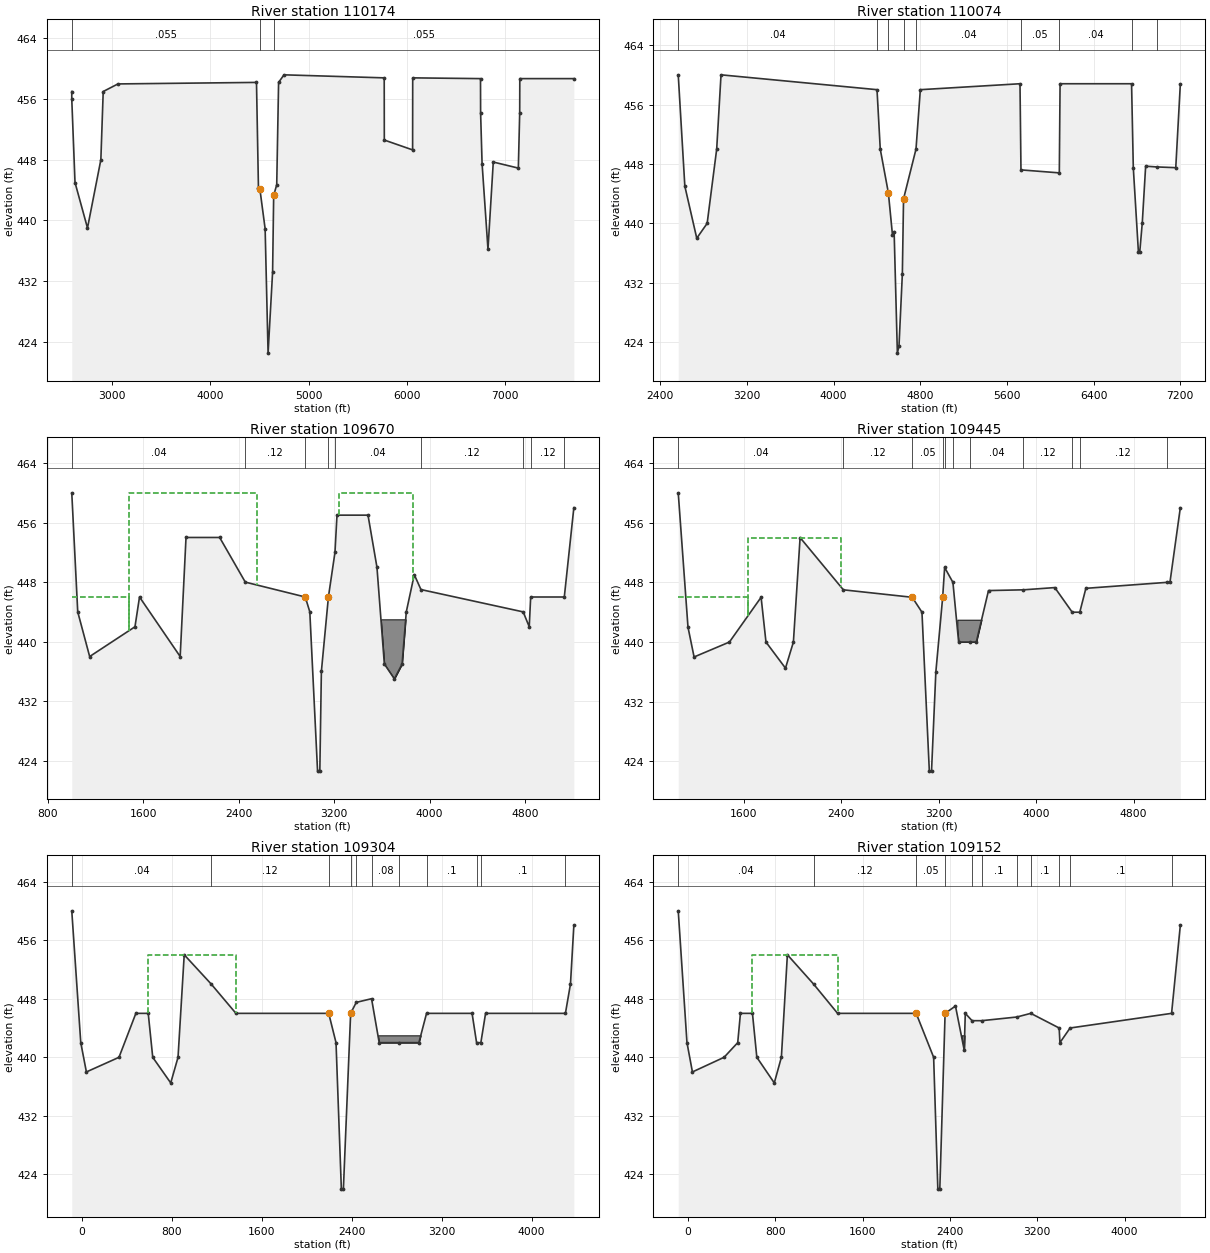
Type RM Length L Ch R = 1 ,110174  ,99,99,99
BEGIN DESCRIPTION:
This cross section corresponds to cross section 110174 of the non-georeferenced CDC model which was the source of this model.
END DESCRIPTION:
XS GIS Cut Line= 6
2445750.485499927046821.746006972445660.48272717 7046847.1055363
 2443106.16631357048479.944134132442715.727789917048697.22847646
2442320.171166337048869.14775205 2441389.32746057049466.92690246
#Sta/Elev= 30
    2590     457    2590     456    2623     445    2750     439    2886     448
    2910     457    3060     458    4470   458.2    4490   444.3    4505   444.1
    4558   438.9    4588   422.5    4634   433.2    4645   443.3    4676   444.7
    4695   458.2    4750   459.2    5770   458.8    5771   450.6    6059   449.3
    6060   458.8    6750   458.7    6751   454.2    6766   447.5    6826   436.2
    6880   447.7    7135   446.9    7149   454.2    7150   458.7    7700   458.7
#Mann= 3 ,0,0
    2590    .055       0    4505     .05       0    4645    .055       0
#XS Ineff= 2 , 0
            4505   444.1    4645           443.3
Permanent Ineff=
       F       F
Bank Sta=4505,4645
XS Rating Curve= 0 ,0
Exp/Cntr=0.5,0.3

Type RM Length L Ch R = 1 ,110074  ,350,393,827
BEGIN DESCRIPTION:
This cross section corresponds to cross section 110074 of the non-georeferenced CDC model which was the source of this model.
END DESCRIPTION:
XS GIS Cut Line= 6
2445751.427427177046817.661041382445345.934143667046933.79597972
2442947.968139087048461.571139382442577.363893427048657.23905513
2442194.711115427048791.875924962441731.779298517049077.63585213
#Sta/Elev= 30
    2565     460    2626     445    2736     438    2832     440    2920     450
    2960     460    4400     458    4430     450    4505   444.1    4543   438.4
    4558   438.9    4588  422.53    4603   423.5    4634   433.2    4645   443.3
    4760     450    4800     458    5720   458.8    5729   447.2    6083   446.8
    6090   458.8    6750   458.8    6766   447.5    6813   436.2    6826   436.2
    6849   440.1    6880   447.7    6981   447.6    7158   447.5    7200   458.7
#Mann= 9 ,-1,0
    2565     .04       0    4400      .1       0    4505     .05       0
    4645      .1       0    4760     .04       0    5729     .05       0
    6083     .04       0    6750     .09       0    6981     .03       0
#XS Ineff= 2 , 0
            4505   444.1    4645           443.3
Permanent Ineff=
       F       F
Bank Sta=4505,4645
XS Rating Curve= 0 ,0
Exp/Cntr=0.3,0.1

Type RM Length L Ch R = 1 ,109670  ,168,236,420
BEGIN DESCRIPTION:
This cross section corresponds to cross section 109670 of the non-georeferenced CDC model which was the source of this model.
NEW SECTION ADDED BY OEI
END DESCRIPTION:
XS GIS Cut Line= 6
2445715.926185857046800.19913405 2445277.68559257046930.58732472
2444848.563091167047115.495747552442828.366344187047783.47210188
2442094.442943257047978.625911062441716.040484857048101.30053447
#Sta/Elev= 30
    1000     460    1050     444    1150     438    1530     442    1568     446
    1909     438    1958     454    2240     454    2455     448    2958     446
    2996     444    3061   422.6    3080   422.6    3093     436    3152     446
    3207     452    3224     457    3484     457    3559     450    3621     437
    3705     435    3770     437    3805     444    3872     449    3928     447
    4785     444    4836     442    4848     446    5130     446    5210     458
#Mann= 9 ,-1,0
    1000     .04       0    2455     .12       0    2958     .05       0
    3152     .12       0    3207     .04       0    3928     .12       0
    4785     .06       0    4848     .12       0    5130     .03       0
#XS Ineff= 6 ,-1
    1000    1480     446    1480    2550     460    2550    2958     446
    3152    3240     446    3240    3860     460    3860    5210     446
Permanent Ineff=
       F       F       F       F       F       F
#Block Obstruct= 1 ,-1
    3559    3872     443
Bank Sta=2958,3152
XS Rating Curve= 0 ,0
Exp/Cntr=0.3,0.1

Type RM Length L Ch R = 1 ,109445  ,2,48,85
BEGIN DESCRIPTION:
This cross section corresponds to cross section 109445 of the non-georeferenced CDC model which was the source of this model.
END DESCRIPTION:
XS GIS Cut Line= 3
2445708.647000917046780.327782722444809.831869427047064.88495639
2441675.622914767047585.87604038
#Sta/Elev= 30
    1064     460    1144     442    1194     438    1484     440    1744     446
    1784     440    1944   436.5    2009     440    2064     454    2419     447
    2984     446    3064     444  3124.5   422.7  3142.5   422.7    3178     436
    3234     446    3250     450    3318     448    3365     440    3460     440
    3510     440    3610   446.9    3897     447    4154   447.3    4297     444
    4359     444    4409   447.2    5074     448    5099     448    5184     458
#Mann= 11 ,-1,0
    1064     .04       0    2419     .12       0    2984     .05       0
    3234      .1       0    3250     .05       0    3318     .06       0
    3460     .04       0    3897     .12       0    4297     .06       0
    4359     .12       0    5074     .03       0
#XS Ineff= 4 ,-1
    1064    1634     446    1634    2400     454    2400    2984     446
    3234    5184     446
Permanent Ineff=
       F       F       F       F
#Block Obstruct= 2 ,-1
    3354    3620     443    3760    3880     445
Bank Sta=2984,3234
XS Rating Curve= 0 ,0
Exp/Cntr=0.3,0.1

Type RM Length L Ch R = 1 ,109304  ,2,54,71
BEGIN DESCRIPTION:
This cross section corresponds to cross section 109304 of the non-georeferenced CDC model which was the source of this model.
NEW SECTION ADDED BY OEI,  Excavated Pond, no swale in hole #9 landing area.
END DESCRIPTION:
XS GIS Cut Line= 6
2446051.742115267046745.836709962445756.887061927046764.43575414
2445598.416578357046804.442563882444939.988433247047000.39591213
2444822.626135177047031.196375462441661.358835677047513.08255079
#Sta/Elev= 30
     -90     460     -10     442      40     438     330     440     480     446
     590     446     630     440     790   436.5     855     440     910     454
    1150     450    1370     446    2195     446    2260     442  2307.5     422
  2325.5     422    2390     446    2440   447.5    2576     448    2644     442
    2823     442    2997     442    3065     446    3470     446    3510     442
    3548     442    3590     446    4300     446    4345     450    4375     458
#Mann= 11 ,-1,0
     -90     .04       0    1150     .12       0    2195     .05       0
    2390     .12       0    2440     .05       0    2576     .08       0
    2823     .04       0    3065      .1       0    3510     .06       0
    3548      .1       0    4300     .03       0
#XS Ineff= 4 ,-1
     -90     590     446     590    1370     454    1370    2195     446
    2390    4375     446
Permanent Ineff=
       F       F       F       F
#Block Obstruct= 1 ,-1
    2620    3029     443
Bank Sta=2195,2390
XS Rating Curve= 0 ,0
Exp/Cntr=0.3,0.1

Type RM Length L Ch R = 1 ,109152  ,163,1380,221
BEGIN DESCRIPTION:
This cross section corresponds to cross section 109152 of the non-georeferenced CDC model which was the source of this model.
NEW SECTION ADDED BY OEI.
END DESCRIPTION:
XS GIS Cut Line= 6
2446048.402883087046735.230431962445808.778034277046751.33440238
2445618.218376017046786.543977632444954.597984087046970.67779572
2444836.601500937046994.919873222441511.208217357047452.72374763
#Sta/Elev= 30
     -90     460     -10     442      40     438     330     440     455     442
     480     446     590     446     630     440     790   436.5     855     440
     910     454    1150     450    1370     446    2090     446    2250     440
  2288.5     422  2306.5     422    2355     446    2450     447    2530     441
    2540     446    2602     445    2690     445    3012   445.5    3140     446
    3400     444    3407     442    3500     444    4430     446    4510     458
#Mann= 11 ,-1,0
     -90     .04       0    1150     .12       0    2090     .05       0
    2355     .12       0    2602     .05       0    2690      .1       0
    3012     .05       0    3140      .1       0    3400     .06       0
    3500      .1       0    4430     .03       0
#XS Ineff= 4 ,-1
     -90     590     446     590    1370     454    1370    2090     446
    2355    4510     446
Permanent Ineff=
       F       F       F       F
#Block Obstruct= 1 ,-1
    2492    2540     443
Bank Sta=2090,2355
XS Rating Curve= 0 ,0
Exp/Cntr=0.3,0.1

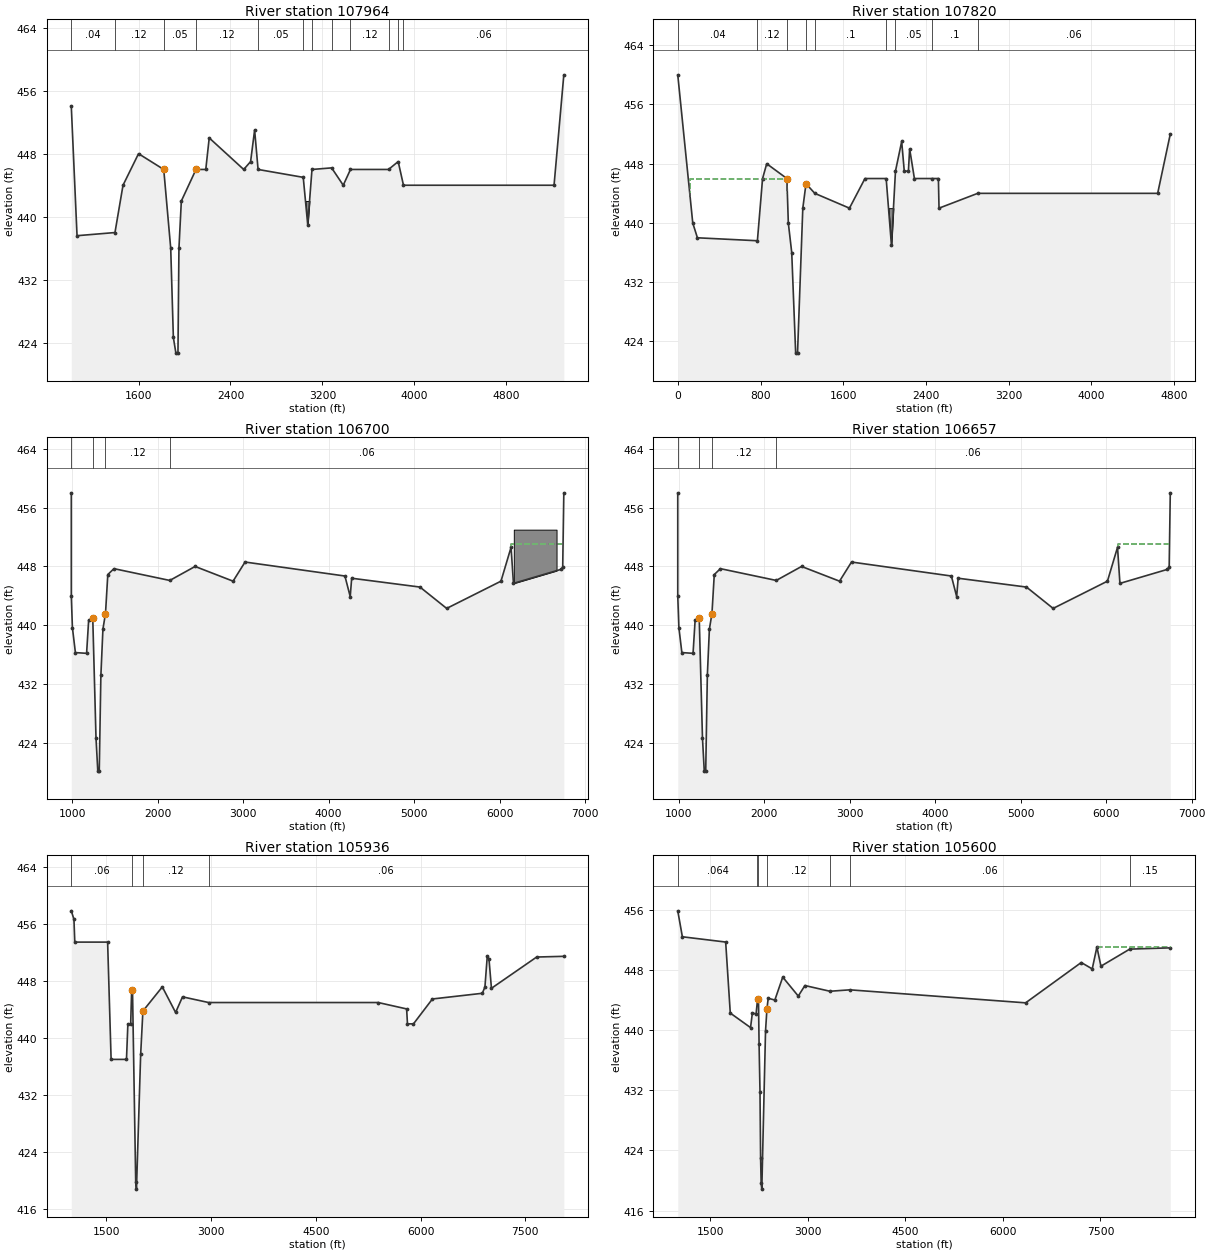
Type RM Length L Ch R = 1 ,107964  ,37,107,201
BEGIN DESCRIPTION:
This cross section corresponds to cross section 107964 of the non-georeferenced CDC model which was the source of this model.
FIS SECTION RECODED BY OEI, Added dense shrubs b/w fairways, mounds b/s 6 & 8
END DESCRIPTION:
XS GIS Cut Line= 6
2445808.357103357046657.124288962445775.275148517046645.97208031
2445068.484895417046738.446960972444833.605115837046686.63210396
2442716.03290743 7046775.21001082441539.11334527 7046806.0485318
#Sta/Elev= 30
    1015     454    1065   437.6    1395     438    1465     444    1600     448
  1819.3     446    1880     436    1903   424.7    1925  422.71    1943  422.71
  1951.5     436  1972.4     442    2100     446    2185     446    2215     450
    2515     446    2575     447    2610     451    2640     446    3033     445
    3072     439    3109     446    3280   446.2    3381     444    3444     446
    3775     446    3859     447    3905     444    5215     444    5300     458
#Mann= 12 ,-1,0
    1015     .04       0    1395     .12       0  1819.3     .05       0
    2100     .12       0    2640     .05       0    3033     .09       0
    3109     .12       0    3280     .05       0    3444     .12       0
    3775     .05       0    3859      .1       0    3905     .06       0
#XS Ineff= 2 , 0
          1819.3     446    2100             446
Permanent Ineff=
       F       F
#Block Obstruct= 1 ,-1
    3033    3109     442
Bank Sta=1819.3,2100
XS Rating Curve= 0 ,0
Exp/Cntr=0.3,0.1

Type RM Length L Ch R = 1 ,107820  ,759,1177,557
BEGIN DESCRIPTION:
This cross section corresponds to cross section 107820 of the non-georeferenced CDC model which was the source of this model.
NEW SECTION ADDED BY OEI
---------------------------------------------------------------------
CDC LEW050102-01 Vista Ridge Golf Center
Cross-section 107820 - 109670
Located in ROB.
--------------------------------------------------------------------
END DESCRIPTION:
XS GIS Cut Line= 6
2446120.972947937046749.88591446 2445827.42858757046622.02593397
2445390.500983697046619.73591229 2445120.92442317046650.20566763
2444876.301224687046604.346507392441393.439424017046715.47030088
#Sta/Elev= 30
       0     460     145     440     190     438     770   437.6     820     446
     860     448    1055     446    1069     440    1102     436    1140  422.43
    1158  422.43    1209     442    1240   445.3    1325     444    1660     442
    1810     446    2015     446    2066     437    2105     447    2165     451
    2190     447    2230     447    2242     450    2288     446    2460     446
    2520     446    2526     442    2900     444    4640     444    4762     452
#Mann= 9 ,-1,0
       0     .04       0     770     .12       0    1055     .05       0
    1240     .05       0    1325      .1       0    2015     .09       0
    2105     .05       0    2460      .1       0    2900     .06       0
#XS Ineff= 2 ,-1
     120    1060     446    1240    4762   445.3
Permanent Ineff=
       F       F
#Block Obstruct= 1 ,-1
    2015    2105     442
Bank Sta=1055,1240
XS Rating Curve= 0 ,0
Exp/Cntr=0.3,0.1

Type RM Length L Ch R = 1 ,106700  ,24,24,24
BEGIN DESCRIPTION:
This cross section corresponds to cross section 106700 of the non-georeferenced CDC model which was the source of this model.
Water tank section DS Copied section.
END DESCRIPTION:
XS GIS Cut Line= 5
2446254.662969267046465.101050972445876.386822917045960.52594464
2445562.02557501 7045963.65257882445240.248987597045964.12501881
2440747.161517087045998.48026505
#Sta/Elev= 30
     990     458     990     444    1003   439.7    1038   436.3    1169   436.2
    1193   440.7    1241     441    1279   424.7    1300   420.2    1317   420.2
    1336   433.2    1360   439.5    1390   441.6    1417   446.9    1489   447.7
    2142   446.1    2438     448    2882     446    3022   448.6    4190   446.7
    4252   443.9    4269   446.4    5068   445.2    5380   442.3    6015     446
    6133   450.6    6161   445.7    6716   447.6    6737   447.9    6750     458
#Mann= 4 ,-1,0
     990     .06       0    1241     .05       0    1390     .12       0
    2142     .06       0
#XS Ineff= 3 ,-1
     990    1241     441    1390    1500   441.6    6133    6750     451
Permanent Ineff=
       F       F       F
#Block Obstruct= 1 ,-1
    6165    6665     453
Bank Sta=1241,1390
XS Rating Curve= 0 ,0
Exp/Cntr=0.3,0.1

Type RM Length L Ch R = 1 ,106657  ,850,721,560
BEGIN DESCRIPTION:
This cross section corresponds to cross section 106657 of the non-georeferenced CDC model which was the source of this model.
Water tank section DS
---------------------------------------------------------------------
CDC LEW052401-1 Water Storage Tank
Cross-section 106657 - 107964
Project located in far ROB west of Gun Club road.
---------------------------------------------------------------------
END DESCRIPTION:
XS GIS Cut Line= 3
2446264.197070937046450.406198472445896.118082677045935.09522122
2440769.508913347045970.63287979
#Sta/Elev= 30
     990     458     990     444    1003   439.7    1038   436.3    1169   436.2
    1193   440.7    1241     441    1279   424.7    1300   420.2    1317   420.2
    1336   433.2    1360   439.5    1390   441.6    1417   446.9    1489   447.7
    2142   446.1    2438     448    2882     446    3022   448.6    4190   446.7
    4252   443.9    4269   446.4    5068   445.2    5380   442.3    6015     446
    6133   450.6    6161   445.7    6716   447.6    6737   447.9    6750     458
#Mann= 4 ,-1,0
     990     .06       0    1241     .05       0    1390     .12       0
    2142     .06       0
#XS Ineff= 3 ,-1
     990    1241     441    1390    1500   441.6    6133    6750     451
Permanent Ineff=
       F       F       F
Bank Sta=1241,1390
XS Rating Curve= 0 ,0
Exp/Cntr=0.3,0.1

Type RM Length L Ch R = 1 ,105936  ,434,384,385
BEGIN DESCRIPTION:
This cross section corresponds to cross section 105936 of the non-georeferenced CDC model which was the source of this model.
END DESCRIPTION:
XS GIS Cut Line= 3
2447261.761020667045957.092224462446056.025899357045402.07004055
2440333.456307777045370.96642822
#Sta/Elev= 30
    1000   457.9    1038   456.7    1050   453.5    1520   453.5    1570     437
    1790     437    1810     442    1850     442    1864   446.7    1876   446.8
    1922   419.8    1933  418.75    1993   437.7    2025   443.8    2303   447.2
    2493   443.6    2592   445.8    2966     445    5393     445    5800   444.1
    5812     442    5898     442    6169   445.5    6884   446.3    6921   447.2
    6954   451.5    6979   451.1    7014     447    7661   451.4    8050   451.5
#Mann= 4 ,-1,0
    1000     .06       0    1876     .05       0    2025     .12       0
    2966     .06       0
#XS Ineff= 3 ,-1
    1000    1876   446.8    2025    6954   443.8    6954    8050   451.5
Permanent Ineff=
       F       F       F
Bank Sta=1876,2025
XS Rating Curve= 0 ,0
Exp/Cntr=0.3,0.1

Type RM Length L Ch R = 1 ,105600  ,436,385,385
BEGIN DESCRIPTION:
This cross section corresponds to cross section 105600 of the non-georeferenced CDC model which was the source of this model.
Interpolated cross-section.
END DESCRIPTION:
XS GIS Cut Line= 4
2447693.509501017045711.683266462446421.248922177045163.56658055
2446349.58863243 7045145.66602582440235.841673587045014.70926672
#Sta/Elev= 30
    1000  455.85 1070.85   452.4 1736.83   451.7 1807.68  442.26 2119.41  440.33
 2147.74   442.3 2204.43  442.12 2226.05     444 2241.27  444.18 2250.61   438.1
  2264.6  431.82 2273.93  423.04 2282.69  419.61 2292.59  418.86 2349.85  439.89
 2371.49   442.8 2390.77  444.23    2493  443.99 2614.51  447.04  2853.3  444.52
 2955.22  445.92 3340.26  445.16 3646.38  445.35 6349.51  443.62 7205.06  448.98
  7373.9  448.13 7445.97  451.04 7507.74  448.49 7950.43  450.76 8574.32  450.93
#Mann= 7 ,-1,0
    1000    .064       0 2226.05    .072       0 2241.27     .05       0
 2371.49     .12       0 3340.26    .066       0 3646.38     .06       0
 7950.43     .15       0
#XS Ineff= 3 ,-1
    1000 2241.27  444.18 2371.49 7445.97   442.8 7445.97 8574.32  451.04
Permanent Ineff=
       F       F       F
#Block Obstruct= 2 , 0
                            7950             458
Bank Sta=2241.27,2371.49
XS Rating Curve= 0 ,0
Exp/Cntr=0.3,0.1