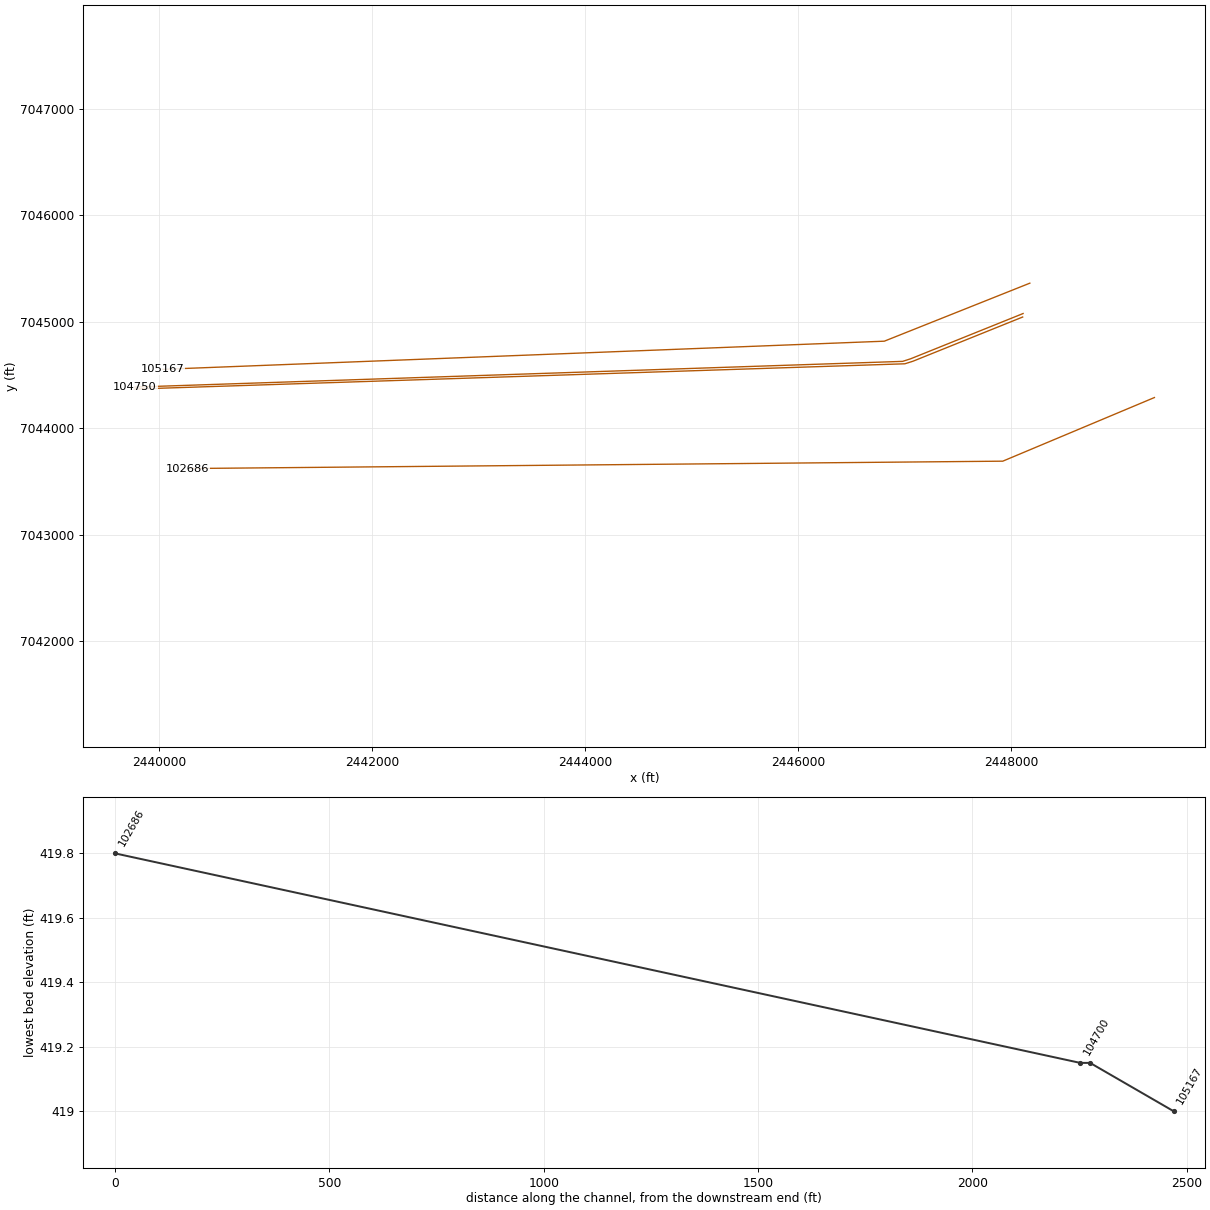
HEC-RAS study CDC_Consolidated_Model.prj: Upper Trinity CDC Consolidated Model

--- CDC_Consolidated_Model.g13 (geometry) --- (continued)

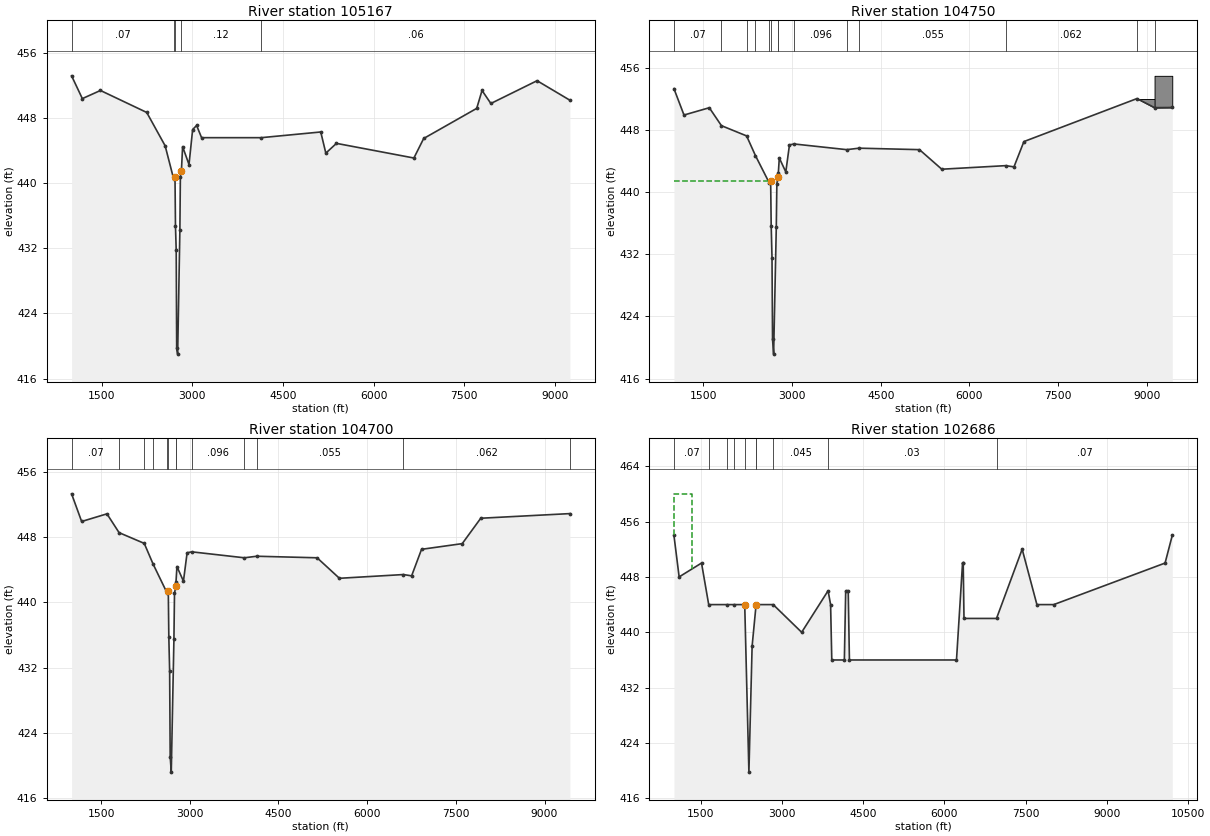
Type RM Length L Ch R = 1 ,105167  ,132,195,97
BEGIN DESCRIPTION:
This cross section corresponds to cross section 105167 of the non-georeferenced CDC model which was the source of this model.
END DESCRIPTION:
XS GIS Cut Line= 3
2448176.333010447045363.731206462446809.859037347044818.43997422
2440036.274159347044554.02285214
#Sta/Elev= 30
    1000   453.2    1178   450.4    1478   451.4    2244   448.7    2549   444.6
    2691   440.5    2712   440.8    2720   434.7    2732   431.8    2740   419.7
    2756     419    2793   434.3    2801   440.8    2818   441.5    2838   444.5
    2944   442.3    3004   446.6    3070   447.1    3152   445.6    4140   445.6
    5125   446.3    5209   443.7    5385   444.9    6667   443.1    6829   445.5
    7707   449.2    7795   451.4    7941   449.8    8706   452.6    9250   450.2
#Mann= 5 ,-1,0
    1000     .07       0    2691      .1       0    2712     .05       0
    2818     .12       0    4140     .06       0
#Block Obstruct= 2 , 0
                            8650             458
Bank Sta=2712,2818
XS Rating Curve= 0 ,0
Exp/Cntr=0.3,0.1

Type RM Length L Ch R = 1 ,104750  ,23,23,23
BEGIN DESCRIPTION:
This cross section corresponds to cross section 104750 of the non-georeferenced CDC model which was the source of this model.
Copy of cross-section 104700.
---------------------------------------------------------------------
CDC COP070199-01 Windsor Estates
Cross-section 104750 - 105600
Located in ROB west of Denton Creek.
---------------------------------------------------------------------
END DESCRIPTION:
XS GIS Cut Line= 4
2448113.084121177045078.379086882447057.470746857044653.08531804
2446982.141501167044628.758923132439775.045022997044387.18558738
#Sta/Elev= 30
 1001.58  453.35 1171.64  449.95 1599.66  450.89 1804.88  448.58 2230.58  447.26
 2380.82  444.71 2617.17  441.16 2637.23   441.4 2646.37   435.7 2660.08  431.59
 2669.21  421.07 2687.48  419.15 2732.44  435.47 2742.16  441.12 2762.81  441.97
 2767.32   442.5 2783.54  444.41 2893.42  442.62 2955.61  446.11  3036.4  446.22
 3923.04  445.49 4133.14  445.68 5154.15  445.49 5531.46  442.97 6614.39  443.43
 6752.52  443.27 6920.44  446.53 8832.78  452.07    9130   450.9 9429.95  450.92
#Mann= 14 ,-1,0
 1001.58     .07       0 1804.88    .076       0 2230.58    .089       0
 2380.82    .096       0 2617.17    .091       0 2637.23     .05       0
 2762.81    .106       0 2767.32    .116       0  3036.4    .096       0
 3923.04    .062       0 4133.14    .055       0 6614.39    .062       0
 8832.78    .025       0    9130     .15       0
#XS Ineff= 2 , 0
        2637.235441.4023 2762.81          441.97
Permanent Ineff=
       F       F
#Block Obstruct= 2 ,-1
    8830    9130     452    9130  9429.5     455
Bank Sta=2637.23,2762.81
XS Rating Curve= 0 ,0
Exp/Cntr=0.3,0.1

Type RM Length L Ch R = 1 ,104700  ,1362,2252,998
BEGIN DESCRIPTION:
This cross section corresponds to cross section 104700 of the non-georeferenced CDC model which was the source of this model.
Interpolated cross-section.
END DESCRIPTION:
XS GIS Cut Line= 4
2448109.035572837045045.457892882447078.592751837044629.84028579
2447002.81534433 7044606.01553032439768.890507767044368.21974605
#Sta/Elev= 30
 1001.58  453.35 1171.64  449.95 1599.66  450.89 1804.88  448.58 2230.58  447.26
 2380.82  444.71 2617.17  441.16 2637.23   441.4 2646.37   435.7 2660.08  431.59
 2669.21  421.07 2687.48  419.15 2732.44  435.47 2742.16  441.12 2762.81  441.97
 2767.32   442.5 2783.54  444.41 2893.42  442.62 2955.61  446.11  3036.4  446.22
 3923.04  445.49 4133.14  445.68 5154.15  445.49 5531.46  442.97 6614.39  443.43
 6752.52  443.27 6920.44  446.53 7608.72  447.23 7921.76  450.35 9429.95  450.92
#Mann= 13 ,-1,0
 1001.58     .07       0 1804.88    .076       0 2230.58    .089       0
 2380.82    .096       0 2617.17    .091       0 2637.23     .05       0
 2762.81    .106       0 2767.32    .116       0  3036.4    .096       0
 3923.04    .062       0 4133.14    .055       0 6614.39    .062       0
 9429.95    .062       0
Bank Sta=2637.23,2762.81
XS Rating Curve= 0 ,0
Exp/Cntr=0.3,0.1

Type RM Length L Ch R = 1 ,102686  ,907,1268,605
BEGIN DESCRIPTION:
This cross section corresponds to cross section 102686 of the non-georeferenced CDC model which was the source of this model.
pond 1650-1990, forest 2110-2260,2530-2840
----------------------------------------------------------
XS 102709 to 97192 retored  to  to 1991 topo  to remove CAR 062309-01
END DESCRIPTION:
XS GIS Cut Line= 3
 2449346.20501457044288.79208338 2447922.35189117043690.69715096
2440269.43379802 7043621.4781293
#Sta/Elev= 30
  1008.4     454  1104.3     448  1517.4     450    1650     444    1990     444
    2110     444  2314.8     444    2392   419.8  2451.2     438  2524.8     444
    2530     444    2840     444  3365.7     440  3853.3     446  3899.7     444
  3921.7     436  4153.8     436  4178.4     446  4224.8     446  4247.2     436
  6223.3     436  6335.2     450  6347.4     450  6361.7     442  6962.2     442
  7435.4     452  7707.4     444  8018.6     444   10073     450   10206     454
#Mann= 10 ,-1,0
  1008.4     .07       0    1650     .04       0    1990     .07       0
    2110      .1       0  2314.8     .05       0  2524.8    .045       0
    2530      .1       0    2840    .045       0  3853.3     .03       0
  6962.2     .07       0
#XS Ineff= 2 , 0
            1350     460
Permanent Ineff=
       F       F
Bank Sta=2314.8,2524.8
XS Rating Curve= 0 ,0
Exp/Cntr=0.3,0.1