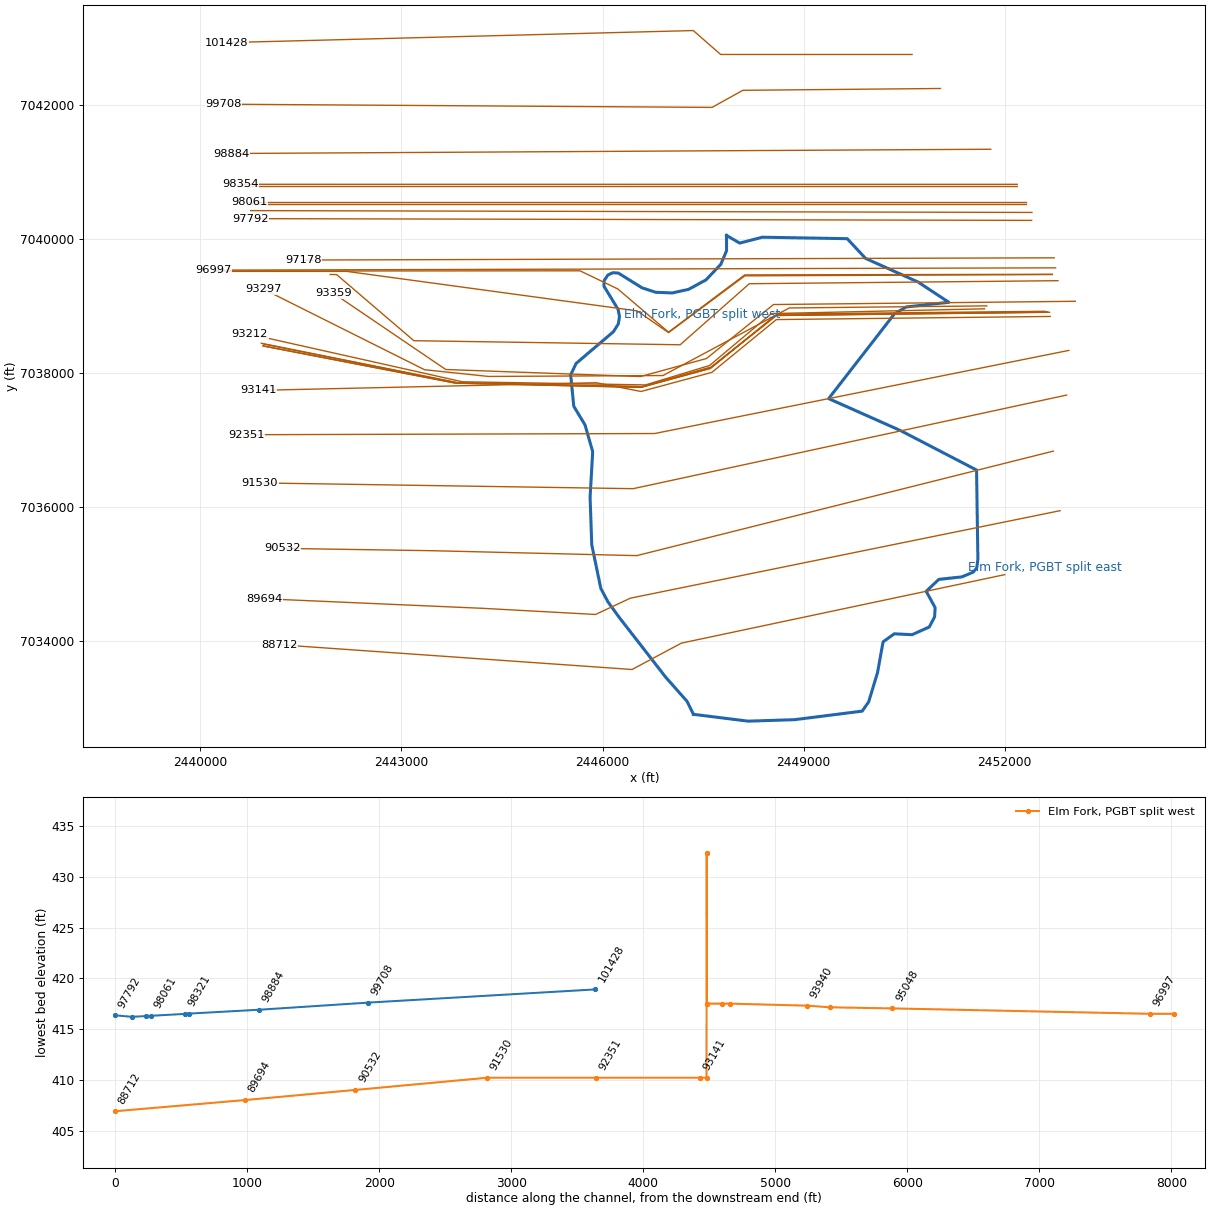
HEC-RAS study CDC_Consolidated_Model.prj: Upper Trinity CDC Consolidated Model

--- CDC_Consolidated_Model.g13 (geometry) --- (continued)

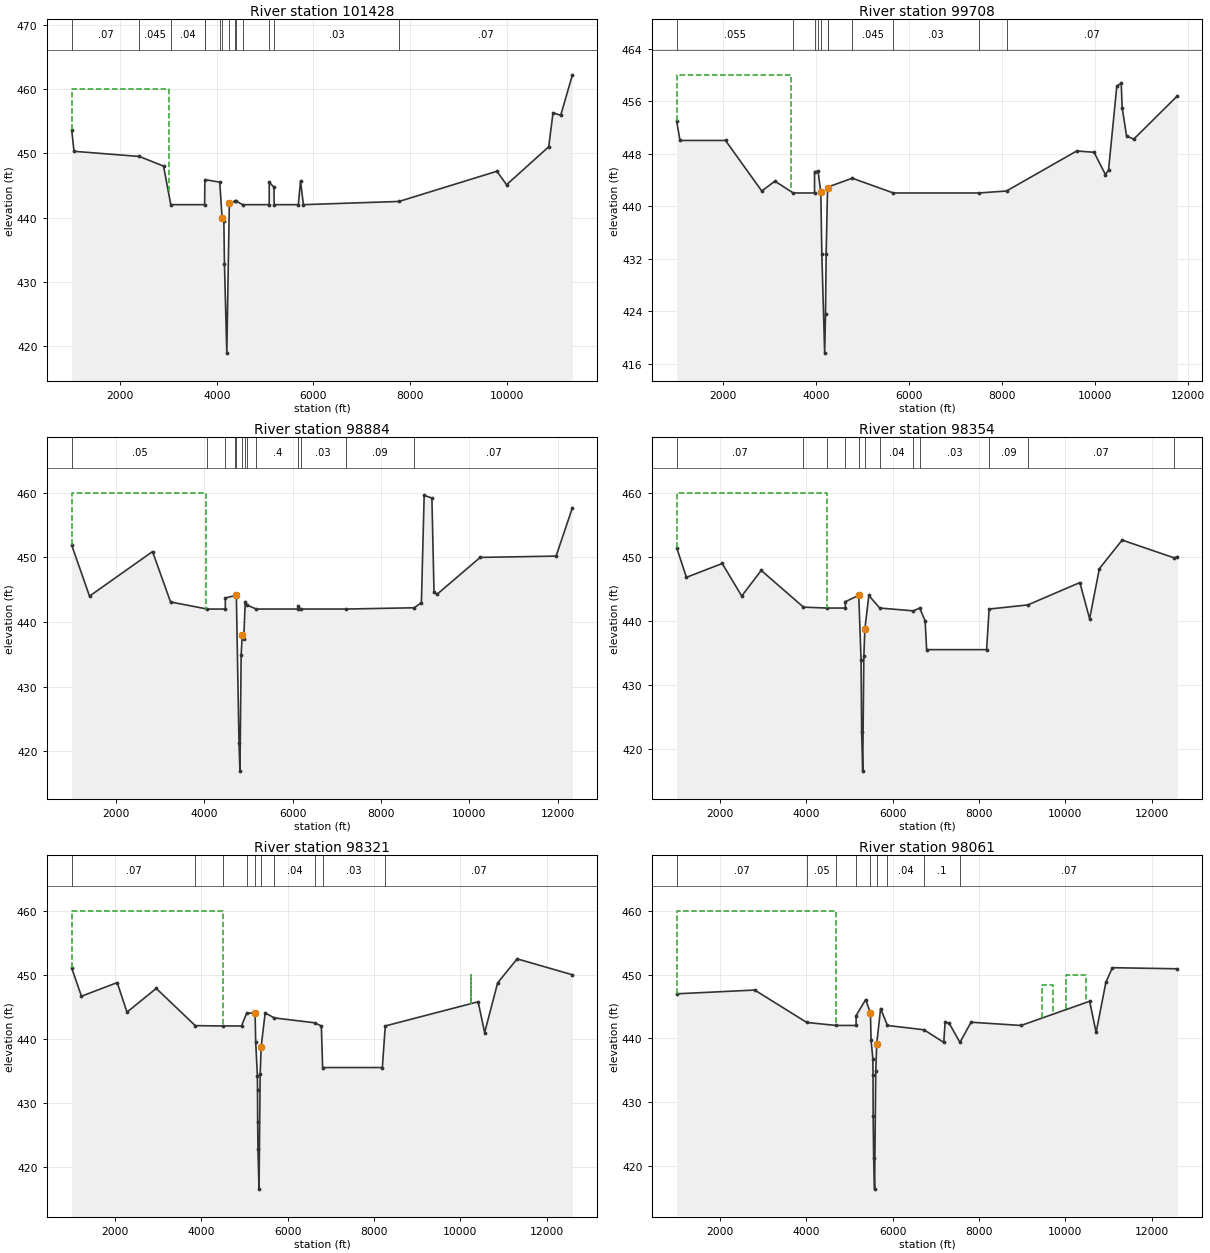
Type RM Length L Ch R = 1 ,101428  ,930,1720,870
BEGIN DESCRIPTION:
This cross section corresponds to cross section 101428 of the non-georeferenced CDC model which was the source of this model.
END DESCRIPTION:
XS GIS Cut Line= 4
2450618.600107497042750.521209812447762.271830687042750.52120981
2447354.618118447043107.218002962440395.945027927042927.45786379
#Sta/Elev= 30
    1000   453.6    1048   450.3    2400   449.5    2900     448    3050     442
    3750     442    3755   445.9    4063   445.5    4111     440    4148   439.4
    4160   432.8    4209   418.9    4261   442.2    4387   442.6    4390   442.6
    4537     442    5086     442    5086   445.5    5184   444.7    5189     442
    5689     442    5734   445.7    5793     442    7772   442.5    9797   447.2
    9996   445.1   10868     451   10958   456.3   11116   455.9   11359   462.2
#Mann= 14 ,-1,0
    1000     .07       0    2400    .045       0    3050     .04       0
    3750      .1       0    3755      .1       0    4063      .1       0
    4111     .05       0    4261      .1       0    4387    .045       0
    4390      .1       0    4537     .04       0    5086    .045       0
    5189     .03       0    7772     .07       0
#XS Ineff= 2 , 0
            3008     460
Permanent Ineff=
       F       F
Bank Sta=4111,4261
XS Rating Curve= 0 ,0
Exp/Cntr=0.3,0.1

Type RM Length L Ch R = 1 ,99708   ,899,823,899
BEGIN DESCRIPTION:
This cross section corresponds to cross section 99708 of the non-georeferenced CDC model which was the source of this model.
END DESCRIPTION:
XS GIS Cut Line= 4
2451043.622879517042242.79223838 2448093.4909845 7042215.4750358
2447634.88002509 7041960.69208082440342.924792777042008.16147405
#Sta/Elev= 30
    1000   452.9    1072     450    2050     450    2829   442.3    3113   443.8
    3505     442    3964     442    3964  445.23    4040   445.3    4099   442.1
    4121   432.7    4182   417.6    4200   423.5    4214   432.7    4244   442.8
    4250   442.9    4775  444.25    5659     442    7500     442    8092   442.3
    9602   448.4    9975   448.2   10219   444.8   10286   445.5   10464   458.3
   10559   458.7   10579     455   10673   450.7   10828   450.2   11767   456.8
#Mann= 11 ,-1,0
    1000    .055       0    3505     .04       0    3964      .1       0
    4040    .055       0    4099     .05       0    4244    .045       0
    4250      .1       0    4775    .045       0    5659     .03       0
    7500     .09       0    8092     .07       0
#XS Ineff= 2 , 0
            3453     460
Permanent Ineff=
       F       F
Bank Sta=4099,4244
XS Rating Curve= 0 ,0
Exp/Cntr=0.3,0.1

Type RM Length L Ch R = 1 ,98884   ,519,530,505
BEGIN DESCRIPTION:
98884
END DESCRIPTION:
XS GIS Cut Line= 2
  2451793.584962 7041336.0811253 2440455.7631498 7041272.5235096
#Sta/Elev= 30
    1000   451.9    1403     444    2830   450.9    3238   443.1    4070     442
    4478     442    4478  443.71    4700   444.1    4728   444.1    4788   421.3
    4810   416.9    4837   434.9    4861     438    4895   437.3    4929   443.1
    4960  442.65    5179     442    6130     442    6130   442.4    6184     442
    7200     442    8757   442.2    8918     443    8981   459.6    9156   459.2
    9204   444.6    9275   444.3   10250     450   11968   450.2   12338   457.7
#Mann= 13 ,-1,0
    1000     .05       0    4070     .04       0    4478      .1       0
    4700     .05       0    4728    .045       0    4861      .1       0
    4929    .045       0    4960      .1       0    5179      .4       0
    6130    .045       0    6184     .03       0    7200     .09       0
    8757     .07       0
#XS Ineff= 2 , 0
            4030     460
Permanent Ineff=
       F       F
Bank Sta=4728,4861
XS Rating Curve= 0 ,0
Exp/Cntr=0.3,0.1

Type RM Length L Ch R = 1 ,98354   ,30,33,30
BEGIN DESCRIPTION:
added
END DESCRIPTION:
XS GIS Cut Line= 2
  2452189.336564 7040812.5738667 2440597.7567036 7040813.0078945
#Sta/Elev= 30
    1000  451.42 1225.94   446.8  2054.4  448.96 2506.28  443.88 2958.16  447.88
 3937.24  442.14 4473.44     442 4905.67     442 4905.67  442.99 5217.91  443.99
 5270.71   433.9 5284.34  422.62 5308.69  416.52 5335.11  434.44  5358.6  438.71
 5451.01  443.96 5703.33     442 6483.15  441.56 6628.29     442 6754.83     440
 6789.88   435.5 8178.63   435.5 8236.96  441.84 9133.91  442.4910338.93  445.98
10564.87  440.3210790.82  448.1611318.01  452.6212523.04  449.8412598.35  450.03
#Mann= 12 ,-1,0
    1000     .07       0 3937.24     .05       0 4473.44     .04       0
 4905.67      .1       0 5217.91     .05       0  5358.6      .1       0
 5703.33     .04       0 6483.15    .045       0 6628.29     .03       0
 8236.96     .09       0 9133.91     .07       012523.04     .07       0
#XS Ineff= 2 , 0
         4473.44     460
Permanent Ineff=
       F       F
Bank Sta=5217.91,5358.6
XS Rating Curve= 0 ,0
Exp/Cntr=0.3,0.1

Type RM Length L Ch R = 1 ,98321   ,230,260,230
BEGIN DESCRIPTION:
added
END DESCRIPTION:
XS GIS Cut Line= 2
  2452189.335329 7040779.5738667 2440597.7554679 7040780.0078945
#Sta/Elev= 30
    1000  451.05 1225.98  446.65 2054.57  448.78 2280.56  444.16  2958.5  447.87
 3862.42  442.05 4498.56     442 4933.92     442 5054.38  444.03 5248.41  443.98
 5262.39  439.53 5301.53  434.22 5305.26  431.96 5308.06  427.04 5315.24   422.7
 5339.75  416.49 5366.13  434.42 5389.58  438.76 5481.73  444.04 5693.02  443.26
 6624.88   442.5 6783.21     442 6813.58   435.5 8196.83   435.5 8264.47     442
10415.85  445.78 10566.5  440.9610867.81  448.7411319.77  452.4912600.32     450
#Mann= 10 ,-1,0
    1000     .07       0 3862.42     .05       0 4498.56     .04       0
 5054.38      .1       0 5248.41     .05       0 5389.58      .1       0
 5693.02     .04       0 6624.88    .045       0 6813.58     .03       0
 8264.47     .07       0
#XS Ineff= 2 ,-1
    1000 4498.56     460 10257.4 10259.4     450
Permanent Ineff=
       F       T
Bank Sta=5248.41,5389.58
XS Rating Curve= 0 ,0
Exp/Cntr=0.3,0.1

Type RM Length L Ch R = 1 ,98061   ,30,32,30
BEGIN DESCRIPTION:
added
END DESCRIPTION:
XS GIS Cut Line= 2
  2452319.978925 7040547.3828945 2440726.2289258 7040547.3828945
#Sta/Elev= 30
    1000  446.97 2807.72  447.56 4012.86  442.47 4696.47     442 5156.46     442
 5156.46  443.54 5377.98  446.07 5488.74  443.93 5503.38  439.64 5544.37  436.79
 5548.28  434.25  5551.2  427.79 5562.92  421.11 5584.39   416.3 5611.55  434.83
 5633.68  439.11  5723.8  444.66 5882.45     442 6730.25  441.32  7186.9  439.34
 7218.28  442.49 7307.39  442.41 7561.47  439.34 7818.71  442.51 8978.99     442
10565.83   445.810716.48   440.910942.44  448.7811093.08  451.0712599.51   450.9
#Mann= 9 ,-1,0
    1000     .07       0 4012.86     .05       0 4696.47     .04       0
 5156.46      .1       0 5488.74     .05       0 5633.68      .1       0
 5882.45     .04       0 6730.25      .1       0 7561.47     .07       0
#XS Ineff= 3 ,-1
    1000 4696.47     460    9471    9724   448.3 10027.410489.38     450
Permanent Ineff=
       F       T       T
Bank Sta=5488.74,5633.68
XS Rating Curve= 0 ,0
Exp/Cntr=0.3,0.1

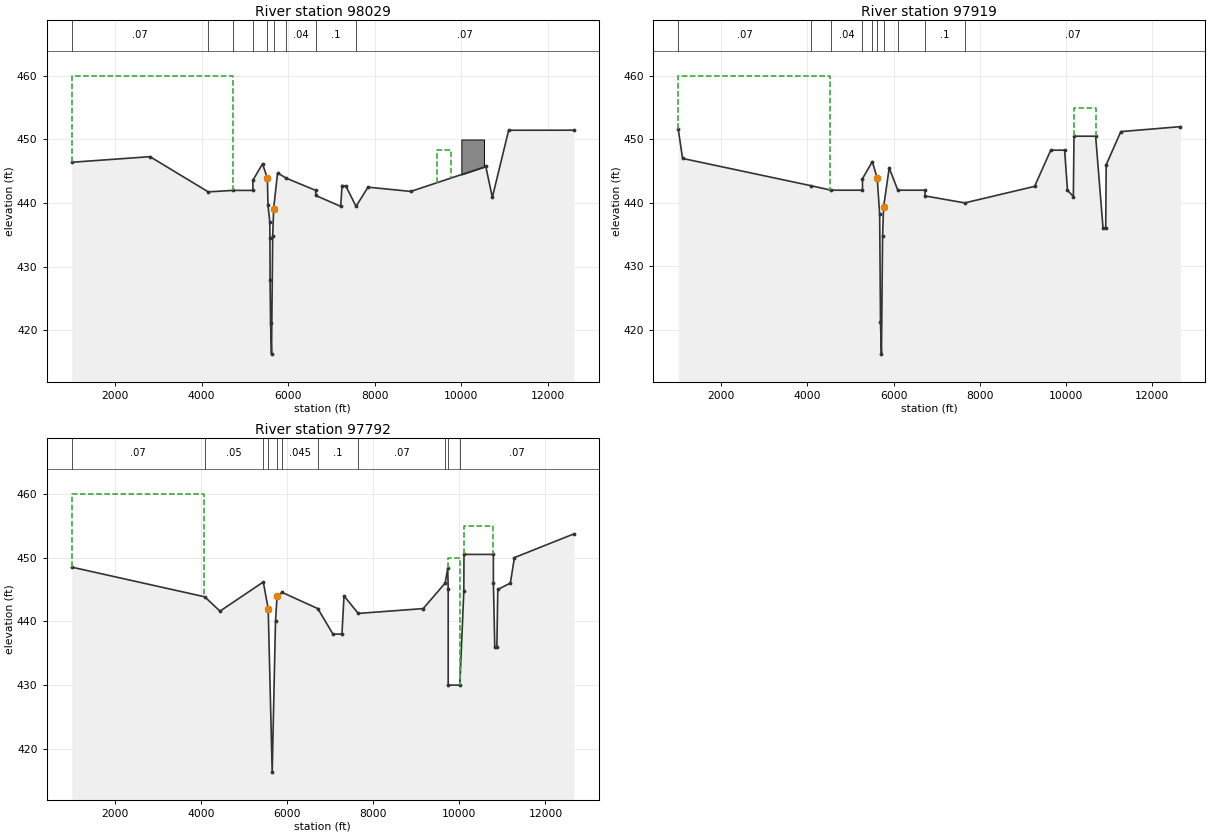
Type RM Length L Ch R = 1 ,98029   ,111,110,105
BEGIN DESCRIPTION:
added
END DESCRIPTION:
XS GIS Cut Line= 2
  2452319.978925 7040515.3828945 2440726.2289258 7040515.3828945
#Sta/Elev= 30
    1000  446.42 2807.57   447.3 4153.04  441.77 4720.83     442 5183.85     442
 5183.85   443.6 5406.83  446.17 5518.32  443.92 5533.04  439.65 5574.26  437.11
 5578.19  434.53 5581.13  427.88 5592.91  421.13  5614.5  416.28 5641.62  434.82
 5663.73  439.15 5753.59  444.74 5959.62  443.91 6636.07     442 6636.07   441.2
 7212.61  439.49 7243.91  442.77 7332.76  442.68 7567.02  439.49 7842.66  442.51
 8832.82  441.8410565.08  445.7610715.71   440.911092.29  451.45 12598.6  451.46
#Mann= 9 ,-1,0
    1000     .07       0 4153.04     .05       0 4720.83     .04       0
 5183.85      .1       0 5518.32     .05       0 5663.73      .1       0
 5959.62     .04       0 6636.07      .1       0 7567.02     .07       0
#XS Ineff= 2 ,-1
    1000 4720.83     460    9440    9759   448.3
Permanent Ineff=
       F       T
#Block Obstruct= 1 ,-1
   10000   10522     450
Bank Sta=5518.32,5663.73
XS Rating Curve= 0 ,0
Exp/Cntr=0.3,0.1

Type RM Length L Ch R = 1 ,97919   ,117,127,117
BEGIN DESCRIPTION:
97919
Cross-section EF122.  Effective flow limit set at sta 4517 in LOB, at sta 10300 in ROB.  Denton Creek removed from conveyance in ROB.
Channel data from NDM Elm Fork channel survey - cross-section EF#122 surveyed December 1993.
END DESCRIPTION:
XS GIS Cut Line= 2
  2452408.071922 7040392.9809774 2440749.1037704  7040420.187944
#Sta/Elev= 30
    1000   451.6    1101     447    4087   442.7    4547     442    5278     442
    5278  443.81    5506   446.5    5620   443.9    5677   438.2    5696   421.2
    5718   416.2    5745   434.8    5767   439.3    5898   445.5    6099     442
    6730     442    6730   441.1    7652     440    9274   442.6 9649.71   448.3
 9971.06   448.310037.94     442   10174     441   10189   450.5 10691.5   450.5
10863.59     43610925.35     43610936.24     44611276.13  451.2212657.48     452
#Mann= 10 ,-1,0
    1000     .07       0    4087     .05       0    4547     .04       0
    5278      .1       0    5506      .1       0    5620     .05       0
    5767      .1       0    6099     .04       0    6730      .1       0
    7652     .07       0
#XS Ineff= 2 ,-1
    1000    4517     460   10189 10691.5     455
Permanent Ineff=
       F       F
Bank Sta=5620,5767
XS Rating Curve= 0 ,0
Exp/Cntr=0.3,0.1

Type RM Length L Ch R = 1 ,97792   ,0,0,0
XS GIS Cut Line= 2
  2452402.986738 7040274.4987799 2440744.1325716 7040300.5404466
#Sta/Elev= 30
    1000   448.5    4087  443.85 4441.55   441.6    5447  446.17    5561     442
    5654  416.35 5731.01     440    5767     444 5887.97  444.53    6713     442
 7065.58     438 7273.81     438 7321.58     444    7652  441.24 9160.29     442
    9670     446    9730   448.3 9741.17     445 9741.17     430   10011     430
10103.67  444.6910107.49   450.5   10790   450.510790.66     446 10822.2     436
10871.24     43610892.32     44511184.31     44611278.98     45012658.57  453.71
#Mann= 11 ,-1,0
    1000     .07       0    4087     .05       0    5447      .1       0
    5561     .05       0    5767      .1       0 5887.97    .045       0
    6713      .1       0    7652     .07       0    9670     .07       0
 9741.17    .035       0   10011     .07       0
#XS Ineff= 3 ,-1
    1000    4060     460    9730   10011     450   10108   10790     455
Permanent Ineff=
       F       T       F
Bank Sta=5561,5767
XS Rating Curve= 0 ,0
Exp/Cntr=0.3,0.1

River Reach=Elm Fork        ,PGBT split west
Reach XY= 30
      2447850.52      7040050.17      2447851.28      7039823.18
       2447765.5      7039618.88      2447543.86      7039386.42
      2447283.34      7039244.82      2447041.73      7039191.65
      2446794.53      7039201.31      2446590.32      7039267.69
      2446235.77      7039488.35      2446154.21      7039493.36
      2446079.96      7039459.22       2446023.8      7039374.59
      2446021.19      7039292.91      2446232.21      7038946.89
       2446253.3       7038838.4      2446235.52      7038729.33
      2446162.43      7038612.58      2445606.85      7038140.69
       2445524.8      7037970.04       2445570.8       7037501.1
      2445738.38      7037223.01      2445853.15       7036823.6
       2445814.6      7036141.12      2445839.38      7035433.75
       2445974.7      7034782.32      2446080.86      7034582.01
      2446241.32      7034359.76      2446941.68      7033458.66
      2447261.03       7033097.4      2447356.93      7032903.31

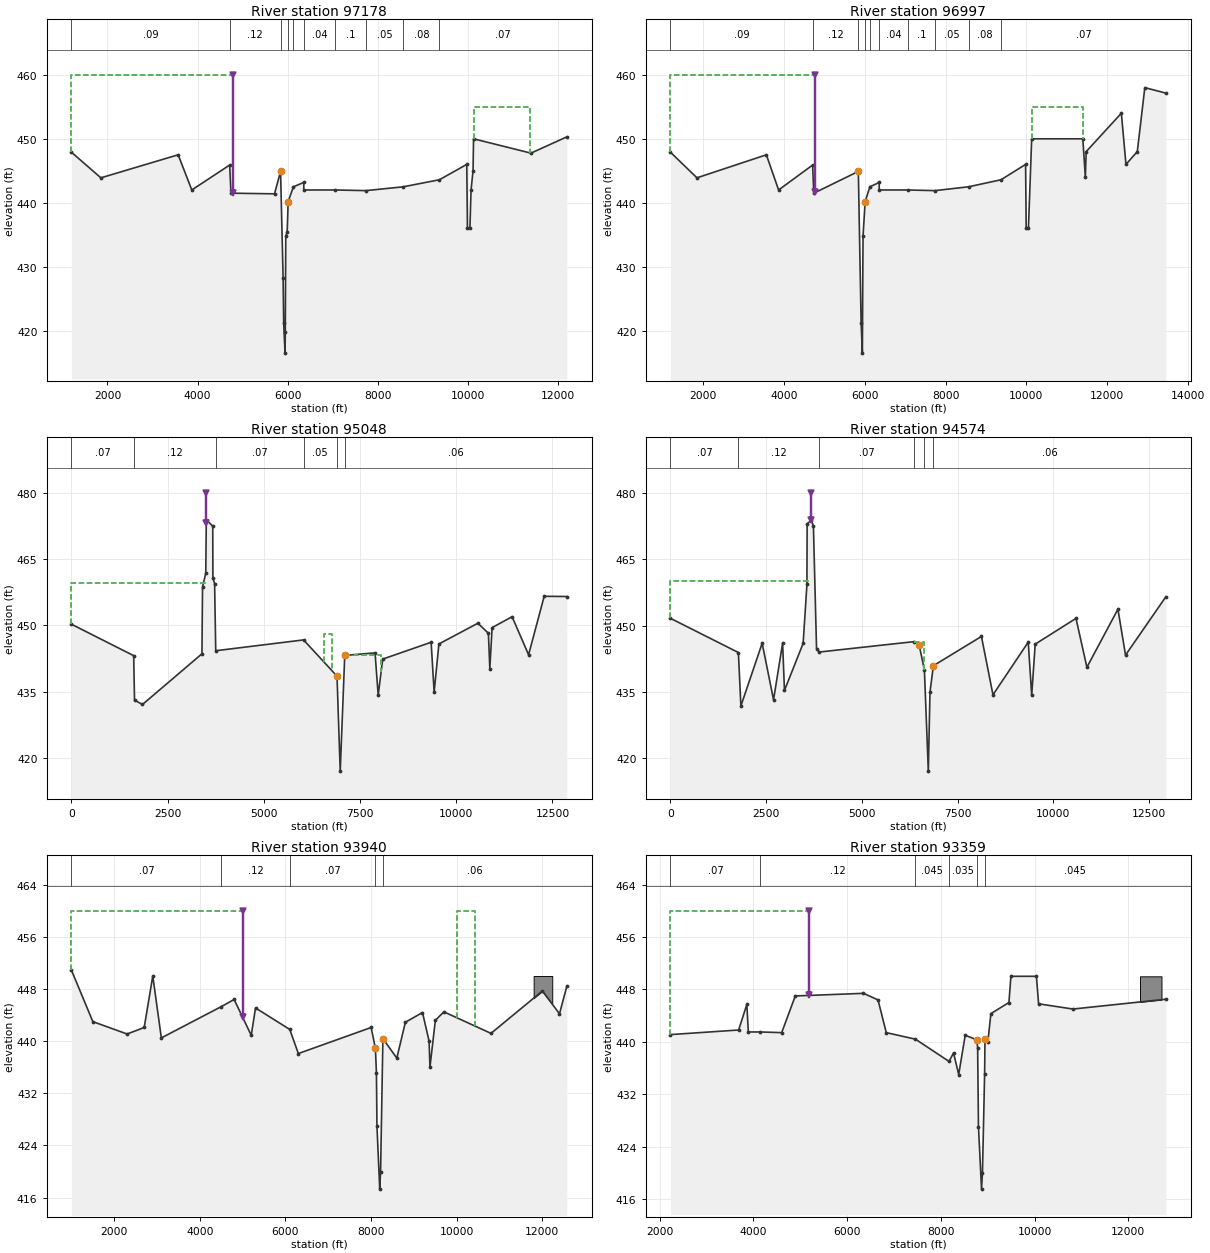
Type RM Length L Ch R = 1 ,97178   ,150,181,150
BEGIN DESCRIPTION:
97178
END DESCRIPTION:
XS GIS Cut Line= 2
  2452739.651967 7039715.7661245 2441539.7009425 7039682.6648127
#Sta/Elev= 30
    1200   447.9    1854   443.9    3570   447.5    3873     442    4714   445.9
    4743   441.5    5710   441.4    5844   444.9    5901   428.2    5913   421.2
    5944   416.5    5949   419.8    5960   434.8    5991   435.4    6013   440.2
    6130   442.5    6360  443.18    6360     442    7060     442    7740   441.9
    8571   442.5    9372   443.6 9979.15     446 9993.89     43610049.34     436
10074.03     44210118.38     44510129.84     45011404.61  447.76   12200   450.3
#Mann= 10 ,-1,0
    1200     .09       0    4714     .12       0    5844     .05       0
    6013    .045       0    6130      .1       0    6360     .04       0
    7060      .1       0    7740     .05       0    8571     .08       0
    9372     .07       0
Levee=-1,4780,460,0,,,,
#XS Ineff= 2 ,-1
    1200    4780     46010129.84   11394     455
Permanent Ineff=
       F       F
Bank Sta=5844,6013
XS Rating Curve= 0 ,0
Exp/Cntr=0.3,0.1

Type RM Length L Ch R = 1 ,96997   ,1410,1949,100
BEGIN DESCRIPTION:
97178
Cross-section EF121.  Effective flow limit set at sta 4780 in LOB, at sta 9950 in ROB.  Denton Creek removed from conveyance in ROB.
Channel data from NDM Elm Fork channel survey.
END DESCRIPTION:
XS GIS Cut Line= 2
  2452761.367025 7039566.1204765 2440197.6951501 7039532.1614198
#Sta/Elev= 30
    1200   447.9    1854   443.9    3570   447.5    3873     442    4714   445.9
    4743   441.5    5844   444.9    5913   421.2    5944   416.5    5960   434.8
    6013   440.2    6130   442.5    6360  443.18    6360     442    7060     442
    7740   441.9    8571   442.5    9372   443.6 9979.15     446 9993.89     436
10049.34     43610129.84     450   11394     45011456.62     44411477.32     448
12346.57     45412460.83     44612740.92     44812926.99     45813446.46  457.14
#Mann= 10 ,-1,0
    1200     .09       0    4714     .12       0    5844     .05       0
    6013    .045       0    6130      .1       0    6360     .04       0
    7060      .1       0    7740     .05       0    8571     .08       0
    9372     .07       0
Levee=-1,4780,460,0,,,,
#XS Ineff= 2 ,-1
    1200    4780     46010129.84   11394     455
Permanent Ineff=
       F       F
Bank Sta=5844,6013
XS Rating Curve= 0 ,0
Exp/Cntr=0.3,0.1

Type RM Length L Ch R = 1 ,95048   ,170,474,440
XS GIS Cut Line= 6
  2452712.304684 7039470.0572163 2448121.5037444 7039460.9007607
 2446985.0470978 7038606.5394672 2446226.5929182  7039252.102073
 2445663.5196863 7039522.0493112 2440196.0544085 7039517.8623899
#Sta/Elev= 30
       0  450.27  1617.6  443.16  1639.6  433.09  1846.4  432.11  3391.7  443.58
  3406.7  458.72  3491.1  461.82  3504.7  473.89  3672.4  472.46  3676.7   460.7
  3720.7  459.47  3749.7  444.27  6032.2  446.72  6901.4  438.52  6984.9  417.03
  7102.4  443.22  7890.1  443.78  7971.5  434.22  8089.5  442.38  9347.5  446.19
  9425.5  434.91  9549.5   445.8 10562.5   450.5 10835.5  448.22 10872.5  440.24
   10932   449.5 11451.1  451.97 11879.7  443.36 12285.5  456.5912872.34  456.54
#Mann= 6 ,-1,0
       0     .07       0  1617.6     .12       0  3749.7     .07       0
  6032.2     .05       0  6901.4     .05       0  7102.4     .06       0
Levee=-1,3504,480,0,,,,
#XS Ineff= 3 ,-1
       0    3504 459.634  6573.9  6772.9     448  7102.4  8047.4  443.22
Permanent Ineff=
       F       T       F
Bank Sta=6901.4,7102.4
XS Rating Curve= 0 ,0
Exp/Cntr=0.3,0.1

Type RM Length L Ch R = 1 ,94574   ,62,172,133
BEGIN DESCRIPTION:
---------------------------------------------------------------------
CDC CAR051319-01 Southwest Wholesale Nursery
Project located at cross-section 93359, 94574, and 95048 located in LOB.
---------------------------------------------------------------------
END DESCRIPTION:
XS GIS Cut Line= 6
  2452713.163634 7039466.2073167 2448123.6021857 7039446.7912325
 2446985.3961818 7038599.4854465  2446515.072059 7038924.2281307
 2442183.7665311 7039513.3787417  2440194.546002 7039513.7555372
#Sta/Elev= 30
       0  451.65  1773.1  443.93  1838.1  431.85  2394.2  446.03  2691.1  433.25
  2928.1  446.05  2976.1  435.36    3464  445.99  3563.1   459.3  3568.1  472.97
  3671.1  473.81  3732.1  472.55  3814.1  444.81  3884.1  444.04  6350.4  446.38
  6492.8  445.66  6630.8     440    6733  417.14  6776.4  434.96  6865.1  440.95
  8120.1  447.56  8421.7  434.38  9342.9  446.28  9432.9  434.23    9524  445.82
 10589.4  451.64 10874.6   440.6 11684.7  453.72 11883.7  443.3512935.94  456.52
#Mann= 6 ,-1,0
       0     .07       0  1773.1     .12       0  3884.1     .07       0
  6350.4     .05       0  6630.8     .05       0  6865.1     .06       0
Levee=-1,3671,480,0,,,,
#XS Ineff= 3 ,-1
       0    3671     460  6350.4  6630.8  446.38  6865.1  7810.1  440.95
Permanent Ineff=
       F       T       F
Bank Sta=6492.8,6865.1
XS Rating Curve= 0 ,0
Exp/Cntr=0.3,0.1

Type RM Length L Ch R = 1 ,93940   ,650,581,460
BEGIN DESCRIPTION:
---------------------------------------------------------------------
CDC CAR062309-1 WTP Pre-Sedimentation Basins
Cross-section 93940 - 105167
------------------------------------------------------------
Bridge blocked ROB as part of the project for SPF only.
No other impacts to 100-year or SPF conveyance models.
--------------------------------------------
CDC COP050812-01 River Oaks Assisted Living and Memory Care.  Cross-section 93359 - 93940. In ROB.
--------------------------------------------
END DESCRIPTION:
XS GIS Cut Line= 6
  2452796.764067 7039374.5410043 2448190.2778735 7039329.1939821
 2447158.7989653 7038418.3231004 2443184.5720057 7038479.0480446
 2442031.7429465 7039465.8249424 2441936.7191864 7039466.5562402
#Sta/Elev= 30
    1000   450.9    1500     443    2300   441.1    2700   442.1    2900     450
    3100   440.5    4500   445.3    4800   446.4    5200   440.9    5300   445.1
    6100   441.8    6300   438.1    8000   442.1    8100   438.9    8124   435.1
    8136     427    8201   417.3    8221     420    8275   440.4    8600   437.4
    8800   442.9    9200   444.4    9354     440    9374     436    9500   443.2
    9700   444.5   10800   441.2   12000   447.7   12400   444.2   12570   448.4
#Mann= 5 ,-1,0
    1000     .07       0    4500     .12       0    6100     .07       0
    8100     .05       0    8275     .06       0
Levee=-1,5000,460,0,,,,
#XS Ineff= 2 ,-1
    1000    5000     460   10000   10426     460
Permanent Ineff=
       F       F
#Block Obstruct= 1 ,-1
   11796   12231     450
Bank Sta=8100,8275
XS Rating Curve= 0 ,0
Exp/Cntr=0.3,0.1

Type RM Length L Ch R = 1 ,93359   ,62,62,62
BEGIN DESCRIPTION:
93359
Cross-section EF120.  62 feet u/s Sandy Lake Road.  Effective flow limit set at sta 8000 in LOB, at sta 9150 in ROB.  Channel data from NDM Elm Fork survey c/s EF#120 surveyed January 1994.
--------------------------------------------------
CDC COP050812-01 River Oaks Assisted Living and Memory Care.  Cross-section 93359 - 93940. Located in ROB.
--------------------------------------------
CDC COP 092717-01 Holmes Builders Blackberry Farm Addition. Cross-section 93359 - 98354.  In ROB.
END DESCRIPTION:
XS GIS Cut Line= 6
  2453055.818995 7039066.9760026 2448551.3670463 7039018.6499838
 2447550.3090091 7038212.5351262 2446565.0570426 7037943.8299549
 2443660.8308957 7038049.0098627 2441985.5265035 7039186.2165778
#Sta/Elev= 30
    2230   441.1    3684   441.8    3859   445.7    3891   441.5    4146   441.5
    4603   441.4    4893     447    6347   447.4    6658   446.4    6834   441.4
    7457   440.4    8174     437    8270   438.3    8380     435    8519     441
    8766   440.3    8784   439.1    8802     427    8867   417.5    8887     420
    8933   435.1    8941   440.4    9002     440    9067   444.3    9452     446
    9494     450   10038     450   10085   445.8   10817     445   12800   446.5
#Mann= 6 ,-1,0
    2230     .07       0    4146     .12       0    7457    .045       0
    8174    .035       0    8766     .05       0    8941    .045       0
Levee=-1,5190,460,0,,,,
#XS Ineff= 2 , 0
            5190     460
Permanent Ineff=
       F       F
#Block Obstruct= 1 ,-1
   12248   12707     450
Bank Sta=8766,8941
XS Rating Curve= 0 ,0
Exp/Cntr=0.3,0.1

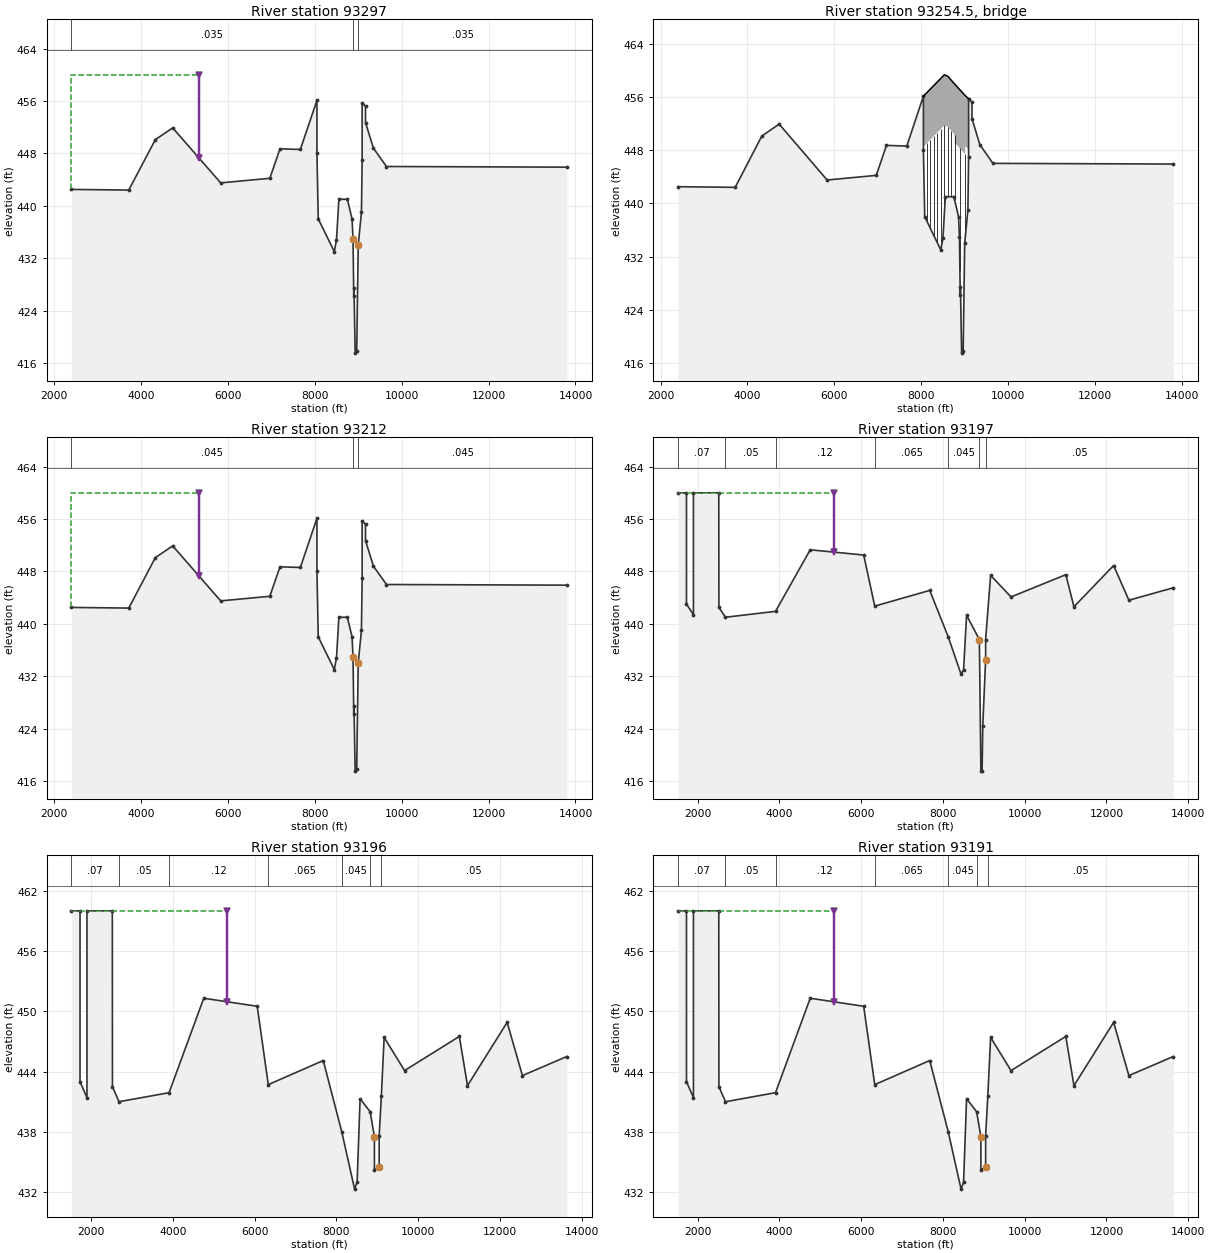
Type RM Length L Ch R = 1 ,93297   ,113,113,113
BEGIN DESCRIPTION:
This cross section corresponds to cross section 93297 of the non-georeferenced CDC model which was the source of this model.
Upstream bounding cross-section for Sandy Lake Road bridge
END DESCRIPTION:
XS GIS Cut Line= 6
2451734.592626187038998.613031222448786.985660497038967.59209588
2446901.668565017037959.034729792444298.008746097037945.72931021
2443344.115968857038045.839674292440940.74752348 7039248.2781476
#Sta/Elev= 30
    2400   442.5    3719   442.4    4331   450.1    4730   451.9    5835   443.5
    6965   444.2    7200   448.7    7668   448.6    8050   456.1    8050     448
    8080     438    8450     433    8500   434.8    8555     441    8750     441
    8858     438    8880     435    8897   426.3    8902   427.4    8930   417.5
    8965   417.8    9000     434    9074     439    9090     447    9090   455.7
    9168   455.2    9168   452.7    9350   448.8    9650     446   13800   445.9
#Mann= 3 ,0,0
    2400    .035       0    8880     .03       0    9000    .035       0
Levee=-1,5329,460,0,,,,
#XS Ineff= 2 , 0
            5329     460
Permanent Ineff=
       F       F
Bank Sta=8880,9000
XS Rating Curve= 0 ,0
Exp/Cntr=0.3,0.1

Type RM Length L Ch R = 3 ,93254.5 ,,,
BEGIN DESCRIPTION:
Sandy Lake Road
Note:  Bridge and roadway modeled from plans dated Dec. 1996 and stamped Dec. 1997.
END DESCRIPTION:
Node Name=Sandy Lake Road
Bridge Culvert--1,0,-1,-1, 0
Deck Dist Width WeirC Skew NumUp NumDn MinLoCord MaxHiCord MaxSubmerge Is_Ogee
1,83,2.6,0, 8, 8, , , 0.95, 0, ,,,
    8050    8530    8610    8770    8770    9010    9010    9090
   456.1   459.3   459.1   457.9   457.9   456.2   456.2   455.7
   448.5   451.7   451.5   450.3   449.1   447.4   448.6   448.1
    8050    8530    8610    8770    8770    9010    9010    9090
   456.1   459.3   459.1   457.9   457.9   456.2   456.2   455.7
   448.5   451.7   451.5   450.3   449.1   447.4   448.6   448.1
Pier Skew, UpSta & Num, DnSta & Num=  ,8130, 2 ,8130, 2 , 0 , 0 , 0 ,,
     2.5     2.5
     425     452
     2.5     2.5
     425     452
Pier Skew, UpSta & Num, DnSta & Num=  ,8210, 2 ,8210, 2 , 0 , 0 , 0 ,,
     2.5     2.5
     425     452
     2.5     2.5
     425     452
Pier Skew, UpSta & Num, DnSta & Num=  ,8290, 2 ,8290, 2 , 0 , 0 , 0 ,,
     2.5     2.5
     425     452
     2.5     2.5
     425     452
Pier Skew, UpSta & Num, DnSta & Num=  ,8370, 2 ,8370, 2 , 0 , 0 , 0 ,,
     2.5     2.5
     425     452
     2.5     2.5
     425     452
Pier Skew, UpSta & Num, DnSta & Num=  ,8450, 2 ,8450, 2 , 0 , 0 , 0 ,,
     2.5     2.5
     425     452
     2.5     2.5
     425     452
Pier Skew, UpSta & Num, DnSta & Num=  ,8530, 2 ,8530, 2 , 0 , 0 , 0 ,,
     2.5     2.5
     425     453
     2.5     2.5
     425     453
Pier Skew, UpSta & Num, DnSta & Num=  ,8610, 2 ,8610, 2 , 0 , 0 , 0 ,,
     2.5     2.5
     425     453
     2.5     2.5
     425     453
Pier Skew, UpSta & Num, DnSta & Num=  ,8690, 2 ,8690, 2 , 0 , 0 , 0 ,,
     2.5     2.5
     425     452
     2.5     2.5
     425     452
Pier Skew, UpSta & Num, DnSta & Num=  ,8770, 2 ,8770, 2 , 0 , 0 , 0 ,,
       3       3
     425     452
       3       3
     425     452
Pier Skew, UpSta & Num, DnSta & Num=  ,8890, 2 ,8890, 2 , 0 , 0 , 0 ,,
       3       3
     425     452
       3       3
     425     452
Pier Skew, UpSta & Num, DnSta & Num=  ,9010, 2 ,9010, 2 , 0 , 0 , 0 ,,
       3       3
     425     452
       3       3
     425     452
BR Coef= 1 , 0 , 0 ,1.05, 0 ,,,0.8,-1,0.5,1,
WSPro=,,,, 1 ,,,, 0 ,,,, 0 ,,,,-1 ,-1 ,-1 , 0 , 0 , 0 , 0 , 0
BC Design=,, 0 ,, 0 ,,,,,,
BC HTab HWMax=456.1
BC Use User HTab Curves=0
BC User HTab FreeFlow(D)= 0

Type RM Length L Ch R = 1 ,93212   ,2,3,4
BEGIN DESCRIPTION:
This cross section corresponds to cross section 93212 of the non-georeferenced CDC model which was the source of this model.
Downstream bounding cross-section for Sandy Lake Road bridge
END DESCRIPTION:
XS GIS Cut Line= 6
2451700.19735375 7038954.69809282448520.069527697038883.64377296
2447597.799390587038109.242434642446642.141196947037819.29157096
2443907.252637837037866.266214552440736.861069247038575.79107872
#Sta/Elev= 30
    2400   442.5    3719   442.4    4331   450.1    4730   451.9    5835   443.5
    6965   444.2    7200   448.7    7668   448.6    8050   456.1    8050     448
    8080     438    8450     433    8500   434.8    8555     441    8750     441
    8858     438    8880     435    8897   426.3    8902   427.4    8930   417.5
    8965   417.8    9000     434    9074     439    9090     447    9090   455.7
    9168   455.2    9168   452.7    9350   448.8    9650     446   13800   445.9
#Mann= 3 ,0,0
    2400    .045       0    8880     .05       0    9000    .045       0
Levee=-1,5329,460,0,,,,
#XS Ineff= 2 , 0
            5329     460
Permanent Ineff=
       F       F
Bank Sta=8880,9000
XS Rating Curve= 0 ,0
Exp/Cntr=0.3,0.1

Type RM Length L Ch R = 1 ,93197   ,1,1,1
BEGIN DESCRIPTION:
This cross section corresponds to cross section 93197 of the non-georeferenced CDC model which was the source of this model.
END DESCRIPTION:
XS GIS Cut Line= 6
2452600.490828757038917.960305382448624.117547937038876.03912938
2447622.075260677038085.549240542446594.051726167037793.92941697
2443835.875484027037852.248854132440907.53596965  7038441.053893
#Sta/Elev= 30
    1520     460    1730     460    1730     443    1900   441.4    1900     460
    2520     460    2523   442.5    2684     441    3908   441.9    4756   451.3
    6064   450.5    6334   442.7    7679   445.1    8132     438    8445   432.3
    8507     433    8580   441.3    8893   437.6    8930   417.5    8960   417.5
    8976   424.4    9046   434.5    9046   437.6    9168   447.4    9667   444.1
   11007   447.5   11206   442.6   12176   448.9   12550   443.6   13635   445.5
#Mann= 7 ,-1,0
    1520     .07       0    2684     .05       0    3908     .12       0
    6334    .065       0    8132    .045       0    8893     .05       0
    9046     .05       0
Levee=-1,5329,460,0,,,,
#XS Ineff= 2 , 0
            5329     460
Permanent Ineff=
       F       F
Bank Sta=8893,9046
XS Rating Curve= 0 ,0
Exp/Cntr=0.3,0.1

Type RM Length L Ch R = 1 ,93196   ,1,1,1
BEGIN DESCRIPTION:
This cross section corresponds to cross section 93196 of the non-georeferenced CDC model which was the source of this model.
END DESCRIPTION:
XS GIS Cut Line= 6
2452641.390353267038908.900284132448592.968660097038861.20648189
2447619.803611677038082.320244392446590.514987837037792.19451229
2443830.769195027037851.319065972440941.944247077038428.13162729
#Sta/Elev= 30
    1520     460    1730     460    1730     443    1900   441.4    1900     460
    2520     460    2523   442.5    2684     441    3908   441.9    4756   451.3
    6064   450.5    6334   442.7    7679   445.1    8132     438    8445   432.3
    8507     433    8580   441.3    8826     440    8930   437.5    8930   434.2
    9046   434.5    9046   437.6    9100   441.6    9168   447.4    9667   444.1
   11007   447.5   11206   442.6   12176   448.9   12550   443.6   13635   445.5
#Mann= 7 ,-1,0
    1520     .07       0    2684     .05       0    3908     .12       0
    6334    .065       0    8132    .045       0    8826     .02       0
    9100     .05       0
Levee=-1,5329,460,0,,,,
#XS Ineff= 2 , 0
            5329     460
Permanent Ineff=
       F       F
Bank Sta=8930,9046
XS Rating Curve= 0 ,0
Exp/Cntr=0.3,0.1

Type RM Length L Ch R = 1 ,93191   ,1,1,1
BEGIN DESCRIPTION:
This cross section corresponds to cross section 93191 of the non-georeferenced CDC model which was the source of this model.
END DESCRIPTION:
XS GIS Cut Line= 6
2452633.708610097038904.114532552448582.513956587038855.67696539
2447608.631061857038066.236943222446572.952030847037783.50916222
2443805.37685734 7037846.64322232440933.827626397038401.55917062
#Sta/Elev= 30
    1520     460    1730     460    1730     443    1900   441.4    1900     460
    2520     460    2523   442.5    2684     441    3908   441.9    4756   451.3
    6064   450.5    6334   442.7    7679   445.1    8132     438    8445   432.3
    8507     433    8580   441.3    8826     440    8930   437.5    8930   434.2
    9046   434.5    9046   437.6    9100   441.6    9168   447.4    9667   444.1
   11007   447.5   11206   442.6   12176   448.9   12550   443.6   13635   445.5
#Mann= 7 ,-1,0
    1520     .07       0    2684     .05       0    3908     .12       0
    6334    .065       0    8132    .045       0    8826     .02       0
    9100     .05       0
Levee=-1,5329,460,0,,,,
#XS Ineff= 2 , 0
            5329     460
Permanent Ineff=
       F       F
Bank Sta=8930,9046
XS Rating Curve= 0 ,0
Exp/Cntr=0.3,0.1

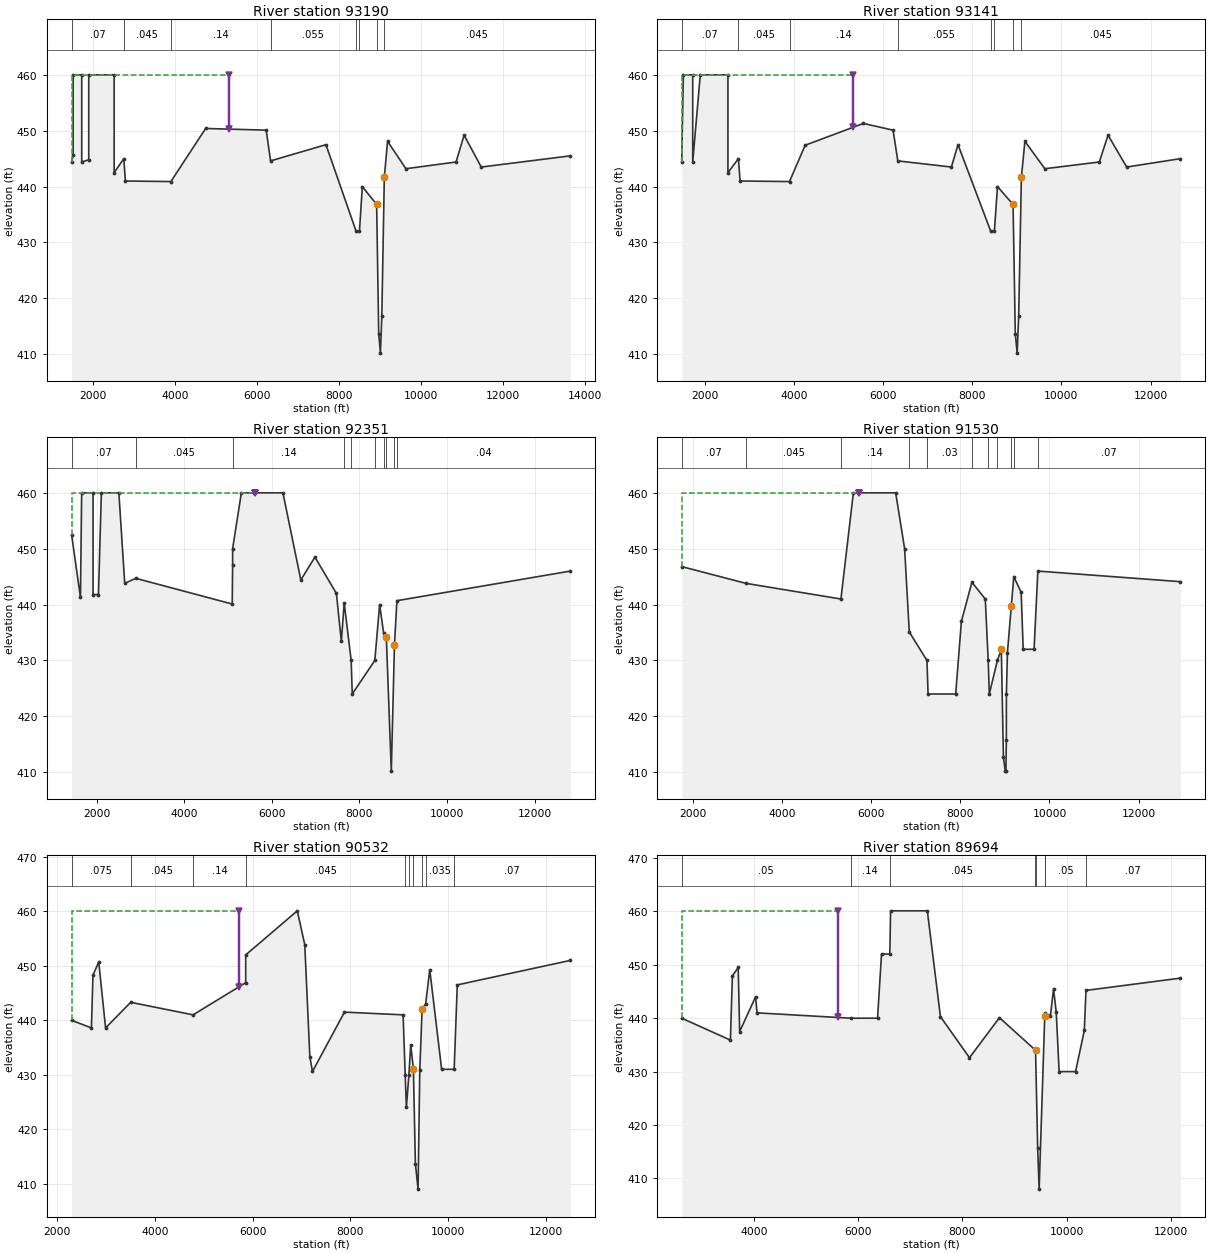
Type RM Length L Ch R = 1 ,93190   ,50,50,50
BEGIN DESCRIPTION:
This cross section corresponds to cross section 93190 of the non-georeferenced CDC model which was the source of this model.
END DESCRIPTION:
XS GIS Cut Line= 6
   2452670.74636   7038903.30167     2448582.553     7038854.674
      2447608.67     7038065.234     2446572.991     7037782.506
     2443805.416     7037845.6412440933.865646337038400.55714905
#Sta/Elev= 30
    1483   444.4    1520   445.6    1520     460    1730     460    1730   444.4
    1900   444.8    1900     460    2520     460    2520   442.5    2755     445
    2793     441    3901   440.9    4749   450.4    6224   450.1    6330   444.6
    7680   447.5    8415     432    8496     432    8566     440    8915   436.8
    8965   413.7    9007   410.2    9041   416.8    9102   441.7    9181   448.1
    9628   443.2   10849   444.4   11046   449.2   11463   443.5   13635   445.5
#Mann= 8 ,-1,0
    1483     .07       0    2755    .045       0    3901     .14       0
    6330    .055       0    8415    .035       0    8496     .12       0
    8915     .05       0    9102    .045       0
Levee=-1,5329,460,0,,,,
#XS Ineff= 2 , 0
            5329     460
Permanent Ineff=
       F       F
Bank Sta=8915,9102
XS Rating Curve= 0 ,0
Exp/Cntr=0.3,0.1

Type RM Length L Ch R = 1 ,93141   ,760,790,740
BEGIN DESCRIPTION:
93141
END DESCRIPTION:
XS GIS Cut Line= 6
 2452682.0648126 7038840.95028882448594.03788367 7038794.2240043
2447632.440069357038006.71606489  2446574.4408737037721.01223996
2445907.796865087037851.96014079 2440858.56340847037737.79077835
#Sta/Elev= 30
    1483   444.4    1520     460    1730     460    1730   444.4    1900     460
    2520     460    2520   442.5    2755     445    2793     441    3901   440.9
    4252   447.4    5558   451.3    6224   450.1    6330   444.6    7532   443.5
    7680   447.5    8415     432    8496     432    8566     440    8915   436.8
    8965   413.7    9007   410.2    9041   416.8    9102   441.7    9181   448.1
    9628   443.2   10849   444.4   11046   449.2   11463   443.5   12670     445
#Mann= 8 ,-1,0
    1483     .07       0    2755    .045       0    3901     .14       0
    6330    .055       0    8415    .035       0    8496     .12       0
    8915     .05       0    9102    .045       0
Levee=-1,5329,460,0,,,,
#XS Ineff= 2 , 0
            5329     460
Permanent Ineff=
       F       F
Bank Sta=8915,9102
XS Rating Curve= 0 ,0
Exp/Cntr=0.3,0.1

Type RM Length L Ch R = 1 ,92351   ,820,821,820
BEGIN DESCRIPTION:
92351
END DESCRIPTION:
XS GIS Cut Line= 4
2452958.679744937038334.056289462446778.237053337037093.70312713
2441681.935894257037078.872448132440681.94012853 7037075.9623736
#Sta/Elev= 30
    1420   452.5    1622   441.3    1650     460    1910     460    1910   441.8
    2034   441.8    2100     460    2500     460    2634   443.8    2887   444.7
    5091   440.1    5100     447    5100     450    5300     460    6250     460
    6659   444.4    6981   448.5    7472     442    7585   433.4    7650   440.3
    7810     430    7834     424    8350     430    8460     440    8550     435
    8613   434.2    8727   410.2    8799   432.8    8855   440.7   12820     446
#Mann= 10 ,-1,0
    1420     .07       0    2887    .045       0    5100     .14       0
    7650     .05       0    7810     .03       0    8350     .05       0
    8550     .14       0    8613     .05       0    8799     .14       0
    8855     .04       0
Levee=-1,5608,460,0,,,,
#XS Ineff= 2 , 0
            5608     460
Permanent Ineff=
       F       F
Bank Sta=8613,8799
XS Rating Curve= 0 ,0
Exp/Cntr=0.3,0.1

Type RM Length L Ch R = 1 ,91530   ,1000,998,1000
BEGIN DESCRIPTION:
91530
END DESCRIPTION:
XS GIS Cut Line= 4
2452926.00067642 7037667.63373782446457.170110177036270.74315888
2441883.650057767036341.302400962440883.769044657036356.72834108
#Sta/Elev= 30
    1748   446.8    3190   443.8    5321     441    5600     460    6550     460
    6750     450    6855   435.1    7252     430    7276     424    7896     424
    8024     437    8260     444    8560     441    8626     430    8650     424
    8832     430    8920     432    8967   412.7    9009   410.2    9023   410.2
    9033   415.8    9034     424    9057   431.4    9145   439.8    9200     445
    9365   442.2    9411     432    9655     432    9740     446   12940   444.1
#Mann= 11 ,-1,0
    1748     .07       0    3190    .045       0    5321     .14       0
    6855    .035       0    7252     .03       0    8260    .045       0
    8626     .03       0    8832     .05       0    9145     .14       0
    9200    .035       0    9740     .07       0
Levee=-1,5730,460,0,,,,
#XS Ineff= 2 , 0
            5730     460
Permanent Ineff=
       F       F
Bank Sta=8920,9145
XS Rating Curve= 0 ,0
Exp/Cntr=0.3,0.1

Type RM Length L Ch R = 1 ,90532   ,650,838,950
BEGIN DESCRIPTION:
90532
END DESCRIPTION:
XS GIS Cut Line= 5
2452726.779946277036831.144925222446511.170002167035271.50893688
2443460.91166702 7035345.00649332442720.441363197035356.46742839
2441220.621005267035379.68151771
#Sta/Elev= 30
    2300     440    2705   438.6    2737   448.3    2855   450.7    2995   438.6
    3508   443.3    4784     441    5860   446.9    5860     452    6915   460.1
    7068   453.9    7172   433.3    7226   430.6    7880   441.5    9079     441
    9122     430    9146     424    9198     430    9235   435.5    9290     431
    9330   413.7    9385     409    9420   430.8    9468   442.1    9540     443
    9624   449.3    9867     431   10123     431   10187   446.5   12500     451
#Mann= 10 ,-1,0
    2300    .075       0    3508    .045       0    4784     .14       0
    5860    .045       0    9122     .03       0    9198    .045       0
    9290     .05       0    9468     .14       0    9540    .035       0
   10123     .07       0
Levee=-1,5720,460,0,,,,
#XS Ineff= 2 , 0
            5720     460
Permanent Ineff=
       F       F
Bank Sta=9290,9468
XS Rating Curve= 0 ,0
Exp/Cntr=0.3,0.1

Type RM Length L Ch R = 1 ,89694   ,800,982,1000
BEGIN DESCRIPTION:
89694
END DESCRIPTION:
XS GIS Cut Line= 6
2452828.585188847035942.362582042446415.268947247034636.62405179
2445895.703057267034393.601243882444214.567311917034485.10959105
2443457.398878757034518.245679632440959.789463927034627.54897753
#Sta/Elev= 30
    2620     440    3554   435.9    3591   447.9    3703   449.5    3731   437.5
    4036     444    4064     441    5860     440    6374     440    6450     452
    6609     452    6624   460.1    7328   460.1    7579   440.3    8136   432.6
    8710   440.1    9390   434.1    9402   434.1    9443   415.7    9471     408
    9579   440.5    9592   440.9    9688   440.5    9747   445.5    9799   441.1
    9854     430   10169     430   10337   437.7   10369   445.2   12180   447.5
#Mann= 8 ,-1,0
    2620     .05       0    5860     .14       0    6609    .045       0
    9390     .14       0    9402     .05       0    9579     .14       0
    9592     .05       0   10369     .07       0
Levee=-1,5621,460,0,,,,
#XS Ineff= 2 , 0
            5621     460
Permanent Ineff=
       F       F
Bank Sta=9402,9579
XS Rating Curve= 0 ,0
Exp/Cntr=0.3,0.1

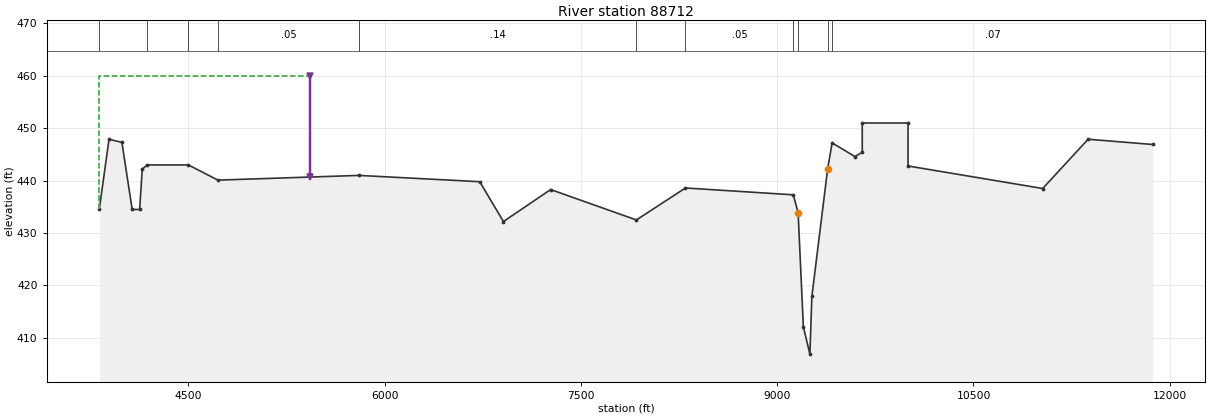
Type RM Length L Ch R = 1 ,88712   ,1150,1067,950
BEGIN DESCRIPTION:
88712
OEI Updated Ground Data and manning's n values  for proposed conditions on West Tracts
Includes CDC Elm Fork Water Treatment Improvements project (CAR 041718-01) from section 93141 to 88712.
END DESCRIPTION:
XS GIS Cut Line= 5
2452003.022207417034988.043296472447177.857973257033966.21692805
2446440.408988837033572.352230222444164.230142277033732.23708105
2441171.60391302 7033942.4470999
#Sta/Elev= 30
    3820   434.6    3894   447.9  3992.5   447.3    4071   434.5    4128   434.5
    4148   442.2  4185.7     443 4500.86     443    4726   440.1    5804     441
    6727   439.8    6908   432.2    7269   438.3    7924   432.5    8299   438.6
    9123   437.3    9160   433.9    9200   412.1    9250   406.9    9265   417.9
    9386   442.3    9420   447.2    9594   444.6    9650   445.4    9650     451
   10000     451   10000   442.8   11029   438.5   11376   447.9   11870   446.9
#Mann= 11 ,-1,0
    3820     .08       0  4185.7     .02       0 4500.86     .08       0
    4726     .05       0    5804     .14       0    7924     .07       0
    8299     .05       0    9123     .12       0    9160     .05       0
    9386     .12       0    9420     .07       0
Levee=-1,5432,460,0,,,,
#XS Ineff= 2 , 0
            5432     460
Permanent Ineff=
       F       F
Bank Sta=9160,9386
XS Rating Curve= 0 ,0
Exp/Cntr=0.3,0.1

River Reach=Elm Fork        ,PGBT split east
Reach XY= 30
      2447850.52      7040050.17      2448046.24      7039935.45
      2448387.09      7040023.41      2449651.56      7040001.42
      2449924.88      7039707.44      2450709.71      7039354.02
      2451168.18      7039051.97      2450533.58      7038983.11
      2450359.03      7038883.33      2449374.49      7037614.65
      2450454.81      7037133.85      2451581.78      7036549.12
      2451601.55      7035215.06      2451584.45      7035087.75
      2451531.25      7035025.05      2451364.04      7034954.75
      2451018.24      7034916.79      2450829.87      7034738.84
      2450963.55      7034496.21      2450955.74      7034358.19
      2450875.93      7034206.43      2450618.79      7034091.55
      2450352.95      7034104.98      2450186.47      7033984.14
      2450104.06      7033526.54      2449971.54      7033089.05
      2449875.18      7032951.03      2448864.61      7032823.42
      2448171.55      7032801.49      2447356.93      7032903.31