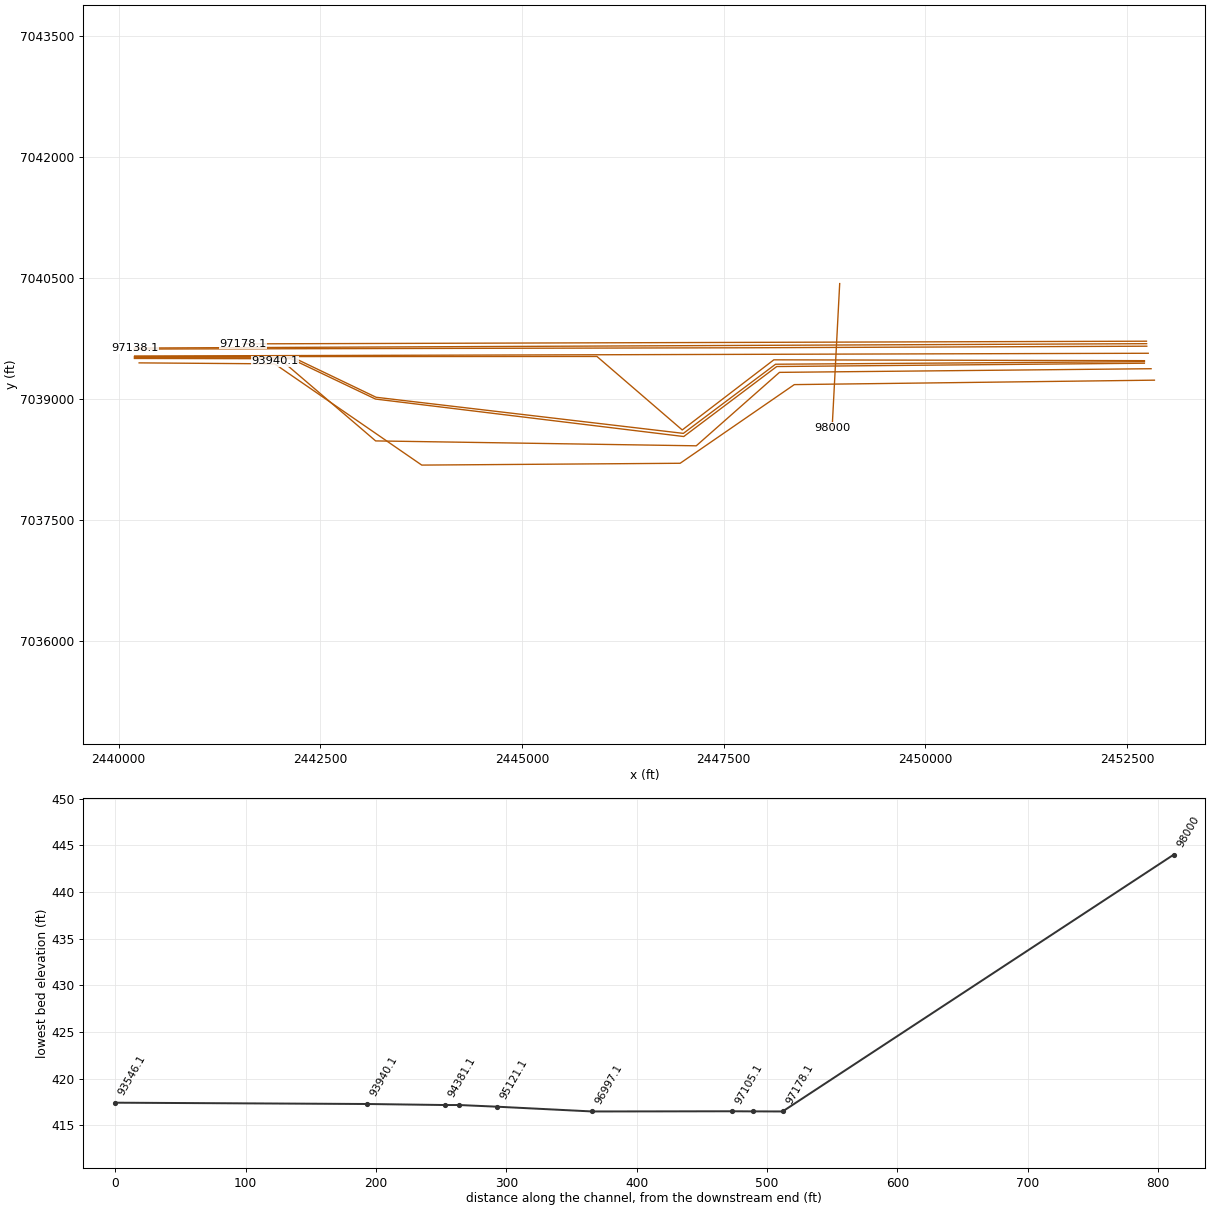
HEC-RAS study CDC_Consolidated_Model.prj: Upper Trinity CDC Consolidated Model

--- CDC_Consolidated_Model.g13 (geometry) --- (continued)

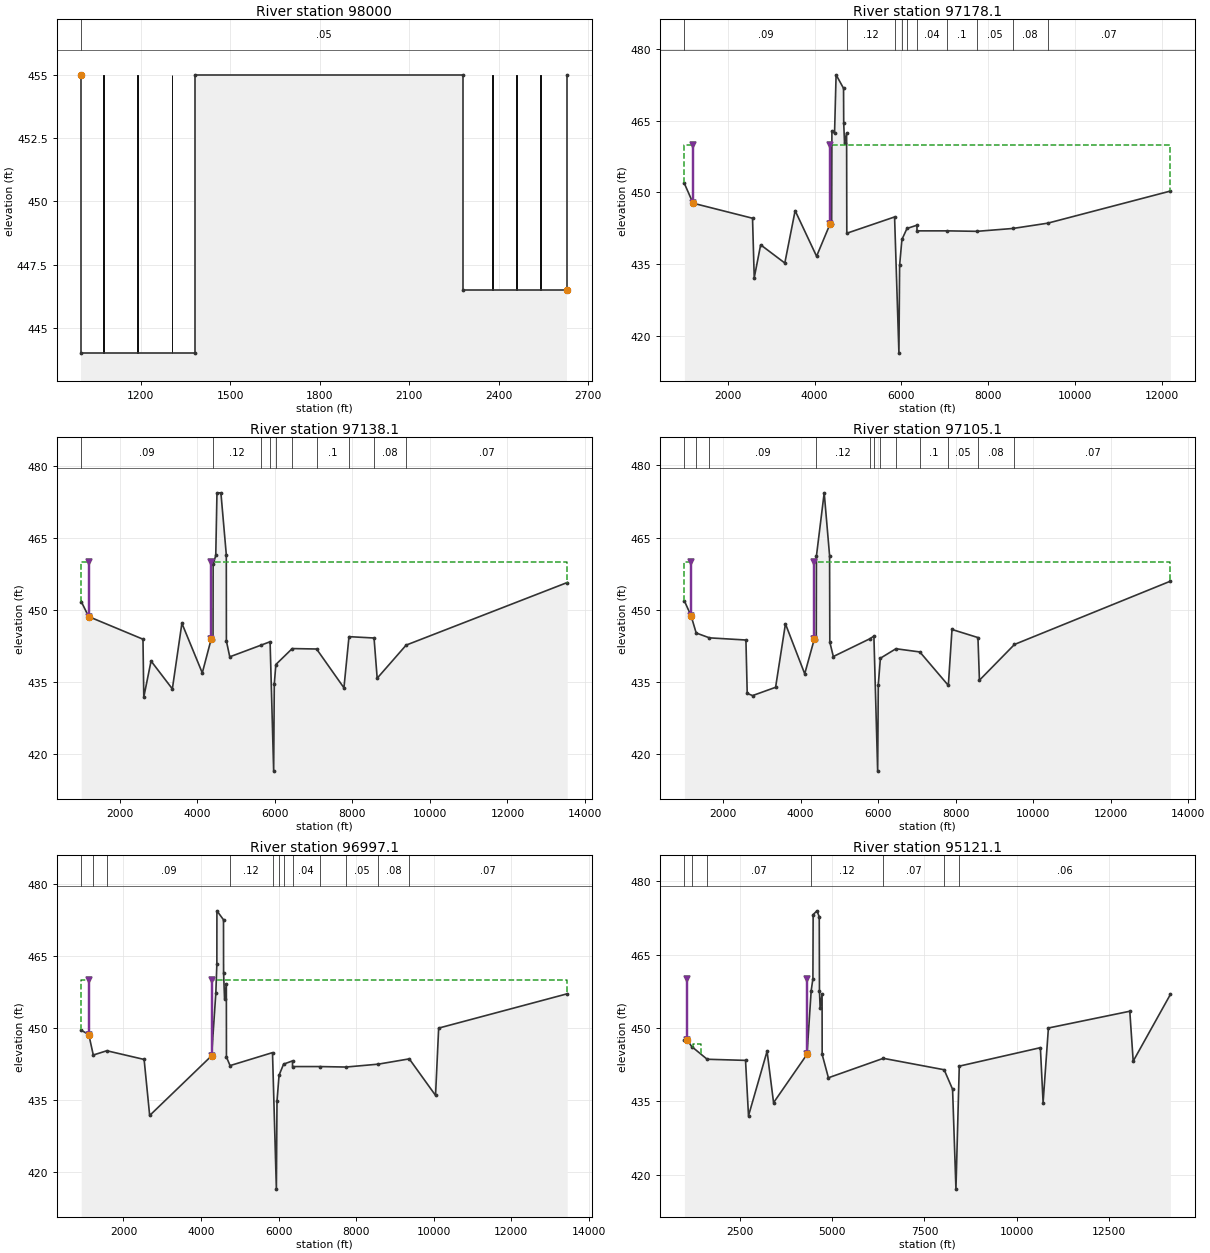
Type RM Length L Ch R = 1 ,98000   ,300,300,300
BEGIN DESCRIPTION:
98000
At PGBT West Face of DWU Crossing,
380' +/- bridge opening
END DESCRIPTION:
XS GIS Cut Line= 2
2448936.862001187040430.24205771 2448843.40123017038643.49431889
#Sta/Elev= 8
    1000     455    1000     444    1380     444    1380     455    2280     455
    2280   446.5    2630   446.5    2630     455
#Mann= 1 ,-1,0
    1000     .05       0
#Block Obstruct= 6 ,-1
    1073    1076     455    1188    1191     455    1303    1306     455
    2378    2381     455    2458    2461     455    2538    2541     455
Bank Sta=1000,2630
XS Rating Curve= 0 ,0
Exp/Cntr=0.3,0.1

Type RM Length L Ch R = 1 ,97178.1 ,42,23,51
BEGIN DESCRIPTION:
97178.1
END DESCRIPTION:
XS GIS Cut Line= 2
2452739.651967767039715.766124472441539.700942527039682.66481271
#Sta/Elev= 30
    1000  451.89    1200  447.77 2570.58  444.63 2609.74  432.22 2757.61  439.09
 3314.35  435.29 3552.33  446.21 4046.48   436.7    4360   443.5  4393.8  443.51
 4399.84  462.83 4460.64  462.36 4496.27  474.54 4667.93  471.73 4671.58  464.48
 4690.52  460.32 4738.44   462.4    4743   441.5    5844   444.9    5944   416.5
    5960   434.8    6013   440.2    6130   442.5    6360  443.18    6360     442
    7060     442    7740   441.9    8571   442.5    9372   443.6   12200   450.3
#Mann= 10 ,-1,0
    1000     .09       0 4738.44     .12       0    5844     .05       0
    6013    .045       0    6130      .1       0    6360     .04       0
    7060      .1       0    7740     .05       0    8571     .08       0
    9372     .07       0
Levee=-1,1200,460,-1,4360,460,,
#XS Ineff= 2 , 0
            1200     460    4360             460
Permanent Ineff=
       T       T
Bank Sta=1200,4360
XS Rating Curve= 0 ,0
Exp/Cntr=0.3,0.1

Type RM Length L Ch R = 1 ,97138.1 ,34,16,22
BEGIN DESCRIPTION:
New cross section. The bottom of the channel has been interpolated between the original xs from plan 1
END DESCRIPTION:
XS GIS Cut Line= 3
  2452741.439853 7039685.0389417 2440201.6321608  7039630.750773
 2440195.5608185 7039630.8589748
#Sta/Elev= 30
    1000  451.83    1192  448.69 2594.03  443.98    2615  431.93 2802.51  439.44
 3352.16  433.63 3598.27   447.3 4124.63  436.96    4354  443.99 4401.32  443.86
 4404.61  459.54 4472.32  461.42 4503.48  474.44  4605.1  474.46 4744.53  461.56
  4746.7   443.6 4833.62  440.31 5631.02  442.71 5874.45  443.45 5966.82  416.51
 5982.84  434.61 6023.18  438.71 6446.02  442.03 7074.19  441.94 7780.46  433.86
 7910.97  444.51 8557.43  444.23  8638.4  435.85 9385.77  442.7513543.55  455.78
#Mann= 10 ,-1,0
    1000     .09       0 4404.61     .12       0 5631.02     .05       0
 5874.45    .045       0 6023.18      .1       0 6446.02     .04       0
 7074.19      .1       0 7910.97     .05       0 8557.43     .08       0
 9385.77     .07       0
Levee=-1,1192,460,-1,4354,460,,
#XS Ineff= 2 , 0
            1192     460    4354             460
Permanent Ineff=
       F       F
Bank Sta=1192,4354
XS Rating Curve= 0 ,0
Exp/Cntr=0.3,0.1

Type RM Length L Ch R = 1 ,97105.1 ,109,107,67
BEGIN DESCRIPTION:
New cross section. The bottom of the channel has been interpolated between the original xs from plan 1
END DESCRIPTION:
XS GIS Cut Line= 3
  2452743.331491  7039653.726297 2447805.9616994 7039634.2818526
 2440197.1522537 7039618.4168451
#Sta/Elev= 30
    1000  451.88    1175  448.73 1304.47  445.21 1647.25   444.2 2588.11  443.75
 2621.45  432.66 2760.16  432.21 3353.57  433.93 3607.71  447.11 4105.04  436.73
    4353  443.96 4403.17  443.85 4407.52   461.2 4607.62  474.32 4746.44  461.29
 4752.61  443.32 4842.93  440.32 5785.47  444.01 5889.99  444.56 5987.17  416.52
 6003.19  434.45 6057.43  439.97 6459.09  441.94 7075.57  441.27 7810.71  434.32
  7904.9  445.94 8574.81  444.26 8613.02   435.4 9517.57  442.8313540.31  455.97
#Mann= 12 ,-1,0
    1000     .09       0 1304.47    .045       0 1647.25     .09       0
 4407.52     .12       0 5785.47     .05       0 5889.99    .045       0
 6057.43      .1       0 6459.09     .04       0 7075.57      .1       0
 7810.71     .05       0 8574.81     .08       0 9517.57     .07       0
Levee=-1,1175,460,-1,4353,460,,
#XS Ineff= 2 , 0
            1175     460    4353             460
Permanent Ineff=
       F       F
Bank Sta=1175,4353
XS Rating Curve= 0 ,0
Exp/Cntr=0.3,0.1

Type RM Length L Ch R = 1 ,96997.1 ,1420,73,91
XS GIS Cut Line= 2
  2452761.367025 7039566.1204765 2440197.6951501 7039532.1614198
#Sta/Elev= 30
     910  449.57 1106.21  448.63 1221.18   444.4 1570.68  445.29 2532.48  443.48
 2675.78  431.82    4273  444.24 4382.31   457.3 4408.63  463.28 4409.99   474.4
 4580.08  472.54 4582.06  461.56 4606.98  456.11 4653.55  459.24 4655.93  443.99
 4749.05   442.2    5844   444.9    5944   416.5    5960   434.8    6013   440.2
    6130   442.5    6360  443.18    6360     442    7060     442    7740   441.9
    8571   442.5    9372   443.610049.34     43610129.84     45013446.46  457.14
#Mann= 12 ,-1,0
     910     .09       0 1221.18    .045       0 1570.68     .09       0
 4749.05     .12       0    5844     .05       0    6013    .045       0
    6130      .1       0    6360     .04       0    7060      .1       0
    7740     .05       0    8571     .08       0    9372     .07       0
Levee=-1,1106.21,460,-1,4273,460,,
#XS Ineff= 2 , 0
         1106.21     460    4273             460
Permanent Ineff=
       T       T
Bank Sta=1106.21,4273
XS Rating Curve= 0 ,0
Exp/Cntr=0.3,0.1

Type RM Length L Ch R = 1 ,95121.1 ,258,29,606
XS GIS Cut Line= 5
  2452714.231375 7039474.3086176 2448120.4813753 7039484.7252843
 2446985.0647087 7038614.9336176  2445927.773042  7039526.391951
 2440194.4397086  7039524.438826
#Sta/Elev= 30
    1000  447.54    1074  447.61 1196.76  446.21 1616.92   443.6 2655.91  443.37
 2736.54  432.03 3239.38  445.24 3415.29  434.71    4321  444.61 4433.51  457.61
 4480.45  460.09 4487.02  473.21 4589.79  473.99 4652.24  472.77 4658.07  457.57
 4676.24  454.13 4728.93  457.01 4731.32  444.58 4900.26  439.81  6387.6  443.79
 8034.74  441.45 8262.81  437.46 8353.79  417.01 8444.11  442.1910640.29  445.97
 10714.1  434.7210857.74     45013061.73  453.4313153.72  443.2114161.27  456.88
#Mann= 7 ,-1,0
    1000     .07       0 1196.76    .045       0 1616.92     .07       0
 4433.51     .12       0  6387.6     .07       0 8034.74     .05       0
 8444.11     .06       0
Levee=-1,1074,460,-1,4321,460,,
#XS Ineff= 1 ,-1
    1246    1457   446.8
Permanent Ineff=
       F
Bank Sta=1074,4321
XS Rating Curve= 0 ,0
Exp/Cntr=0.3,0.1

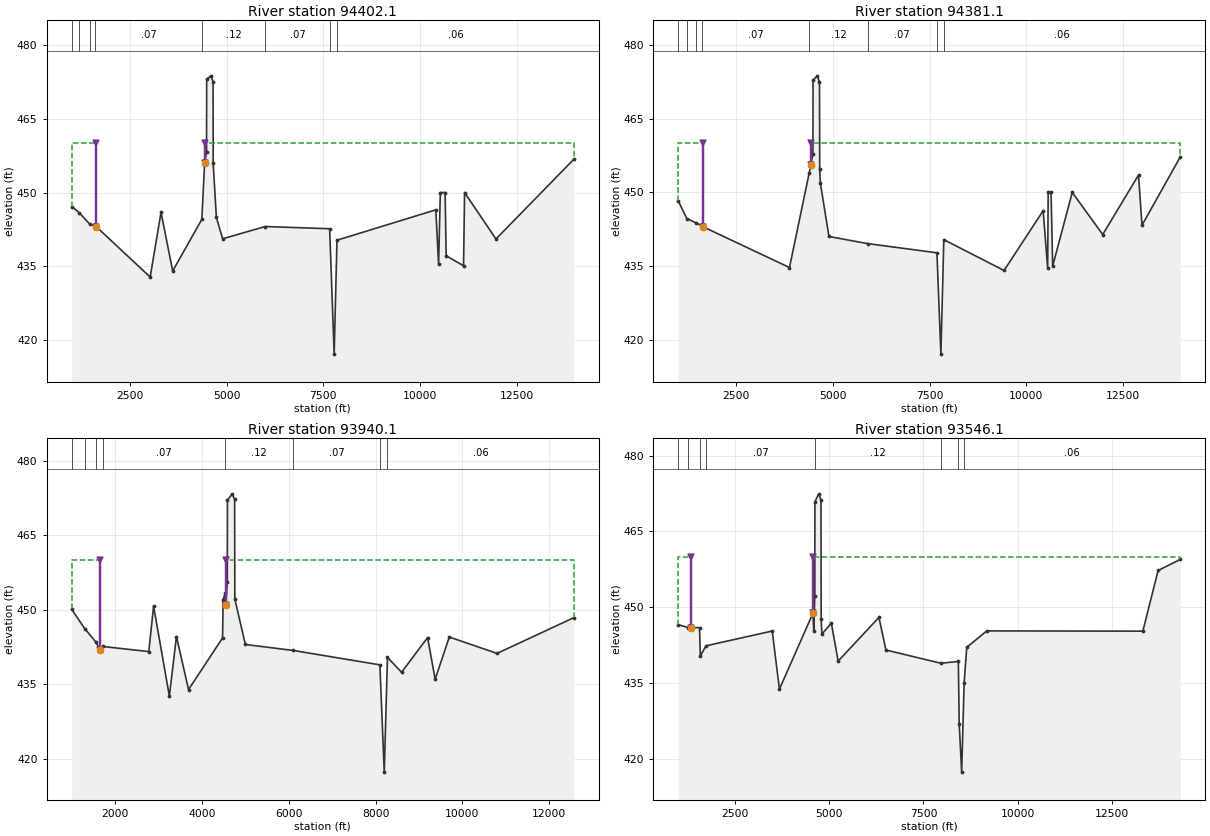
Type RM Length L Ch R = 1 ,94402.1 ,24,11,19
XS GIS Cut Line= 6
  2452714.101167 7039462.1905621 2448141.5606578 7039430.1159093
 2446999.1995466 7038572.4770204 2443190.1717688 7039020.3936871
 2442169.3384355 7039509.9770204 2440195.5537133 7039511.0186871
#Sta/Elev= 30
    1000  447.16 1197.41  445.87    1463   443.6 1609.67   443.2 1633.56  443.06
  3026.2  432.84 3306.51  445.98 3607.47  434.07 4360.36  444.54 4433.24  456.06
 4482.02  458.22 4486.36  472.96 4593.59   473.7 4651.55   472.5 4654.34  455.91
 4736.35  444.97 4898.84  440.61 5998.97   443.1 7663.18  442.65 7780.57  417.19
 7852.88  440.3210406.81  446.49 10478.7  435.3910523.68     45010646.68     450
10674.57  437.1711123.57  435.1311150.34     45011961.36  440.5713973.59  456.76
#Mann= 8 ,-1,0
    1000     .07       0 1197.41     .09       0    1463    .045       0
 1609.67     .07       0 4360.36     .12       0 5998.97     .07       0
 7663.18     .05       0 7852.88     .06       0
Levee=-1,1633.56,460,-1,4433.24,460,,
#XS Ineff= 2 , 0
         1633.56     460 4433.24             460
Permanent Ineff=
       F       F
Bank Sta=1633.56,4433.24
XS Rating Curve= 0 ,0
Exp/Cntr=0.3,0.1

Type RM Length L Ch R = 1 ,94381.1 ,313,60,494
BEGIN DESCRIPTION:
New cross section. The bottom of the channel has been interpolated between the original xs from plan 1
END DESCRIPTION:
XS GIS Cut Line= 6
  2452713.587567 7039442.7027148 2448156.2959008  7039401.470076
 2447003.9521508 7038533.4145204 2443182.7715953 7038998.2582704
 2442135.8965952 7039498.2582704  2440194.924373 7039501.7304926
#Sta/Elev= 30
    1000   448.3 1222.68  444.69 1466.12   443.8 1616.55   443.2    1648  443.01
 3876.45  434.76 4387.62     454    4429  455.55 4482.58  457.88 4485.89  472.76
 4592.65  473.66 4652.21  472.43 4657.61  454.67 4675.78  451.85  4897.1  441.06
 5894.01  439.62 7688.88  437.75  7791.5  417.19 7867.03  440.42 9424.64  434.16
10435.66  446.2910551.95  434.6310565.78     45010639.78     45010681.53  435.06
   11188     45011975.54  441.4612901.31  453.52 12990.8  443.34 13981.9  457.22
#Mann= 8 ,-1,0
    1000     .07       0 1222.68     .09       0 1466.12    .045       0
 1616.55     .07       0 4387.62     .12       0 5894.01     .07       0
 7688.88     .05       0 7867.03     .06       0
Levee=-1,1648,460,-1,4429,460,,
#XS Ineff= 2 , 0
            1648     460    4429             460
Permanent Ineff=
       F       F
Bank Sta=1648,4429
XS Rating Curve= 0 ,0
Exp/Cntr=0.3,0.1

Type RM Length L Ch R = 1 ,93940.1 ,500,193,280
BEGIN DESCRIPTION:
93940.1
END DESCRIPTION:
XS GIS Cut Line= 6
2452796.764058267039374.541085142448190.277864437039329.19406296
2447158.79895625 7038418.3231813 2443184.57199667038479.04812546
2442031.742937427039465.825023292441936.719177347039466.55632105
#Sta/Elev= 30
    1000  450.05 1298.67   446.2 1563.17   443.4    1654  441.83 1709.27   442.6
 2775.04  441.57 2885.57  450.72 3249.03   432.6 3412.43   444.6 3690.96  433.92
 4474.93  444.32 4488.12  451.99 4534.08  453.37    4550  450.93 4584.03  455.62
 4587.47  472.04    4697  473.33 4752.94   472.2  4757.9  452.15    5000     443
    6100   441.8    8100   438.9    8201   417.3    8275   440.4    8600   437.4
    9200   444.4    9374     436    9700   444.5   10800   441.2   12570   448.4
#Mann= 8 ,-1,0
    1000     .07       0 1298.67     .09       0 1563.17    .045       0
 1709.27     .07       0 4534.08     .12       0    6100     .07       0
    8100     .05       0    8275     .06       0
Levee=-1,1654,460,-1,4550,460,,
#XS Ineff= 2 , 0
            1654     460    4550             460
Permanent Ineff=
       T       T
Bank Sta=1654,4550
XS Rating Curve= 0 ,0
Exp/Cntr=0.3,0.1

Type RM Length L Ch R = 1 ,93546.1 ,150,187,180
XS GIS Cut Line= 6
  2452838.048882 7039232.5115355 2448374.2329386 7039177.3943633
  2446959.302383 7038201.6999188  2443756.177383 7038179.1304744
 2441933.2607164 7039434.6860299 2440252.8275286 7039446.8995564
#Sta/Elev= 30
    1000  446.59 1264.74     446 1338.79     446 1563.74     446 1586.14   440.4
 1735.71   442.4 3492.32  445.33 3681.65  433.82  4570.1  448.84 4593.21  445.34
 4619.87  452.26 4622.97  470.87 4724.26  472.44 4784.08   471.2 4788.68  447.65
 4807.51  444.72 5058.99  446.87 5238.94  439.38 6320.33  448.02 6505.33  441.57
 7960.75  438.96 8425.14  439.31 8447.69     427 8512.69  417.44 8578.69   435.1
 8648.37  442.11 9179.75  445.3513316.03   445.313720.15  457.2914308.77  459.48
#Mann= 8 ,-1,0
    1000     .07       0 1264.74     .09       0 1563.74    .045       0
 1735.71     .07       0 4619.87     .12       0 7960.75    .045       0
 8425.14     .05       0 8578.69     .06       0
Levee=-1,1338.79,460,-1,4570.1,460,,
#XS Ineff= 2 , 0
         1338.79     460  4570.1             460
Permanent Ineff=
       F       F
Bank Sta=1338.79,4570.1
XS Rating Curve= 0 ,0
Exp/Cntr=0.3,0.1