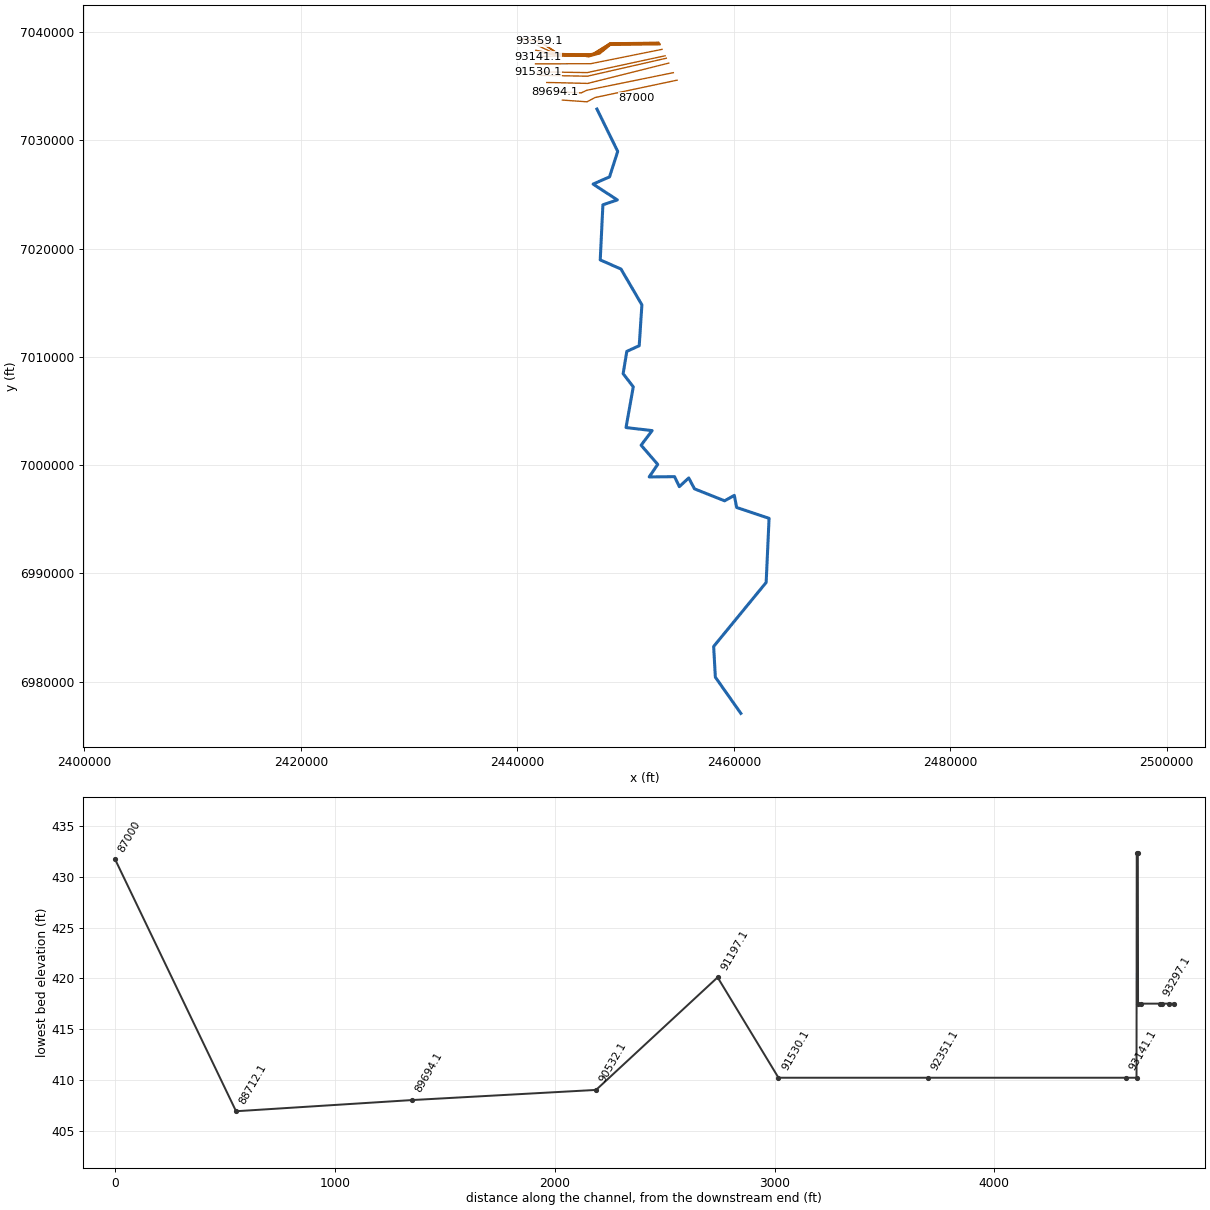
HEC-RAS study CDC_Consolidated_Model.prj: Upper Trinity CDC Consolidated Model

--- CDC_Consolidated_Model.g13 (geometry) --- (continued)

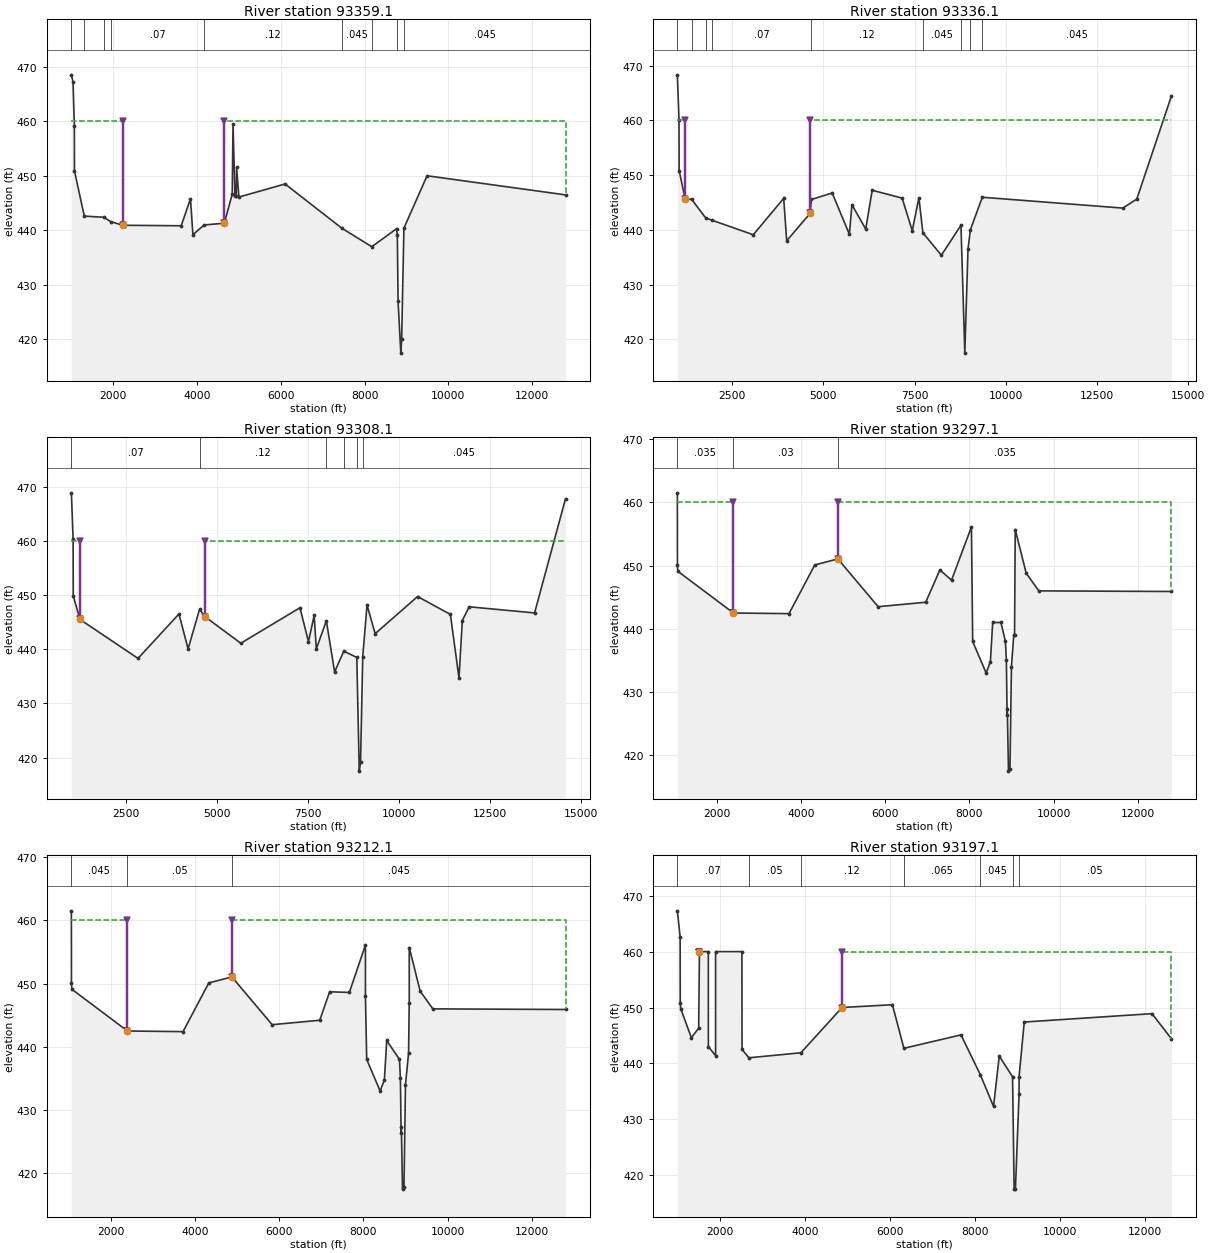
Type RM Length L Ch R = 1 ,93359.1 ,33,23,23
BEGIN DESCRIPTION:
93359.1
---------------------------------------------------------------------
CDC Cop 050812-01 River Oaks Assisted Living and Memory Care
Cross-section 93359 - 93940
Located in ROB.
---------------------------------------------------------------------
END DESCRIPTION:
XS GIS Cut Line= 6
2453055.818986337039066.976083472448551.367037277039018.65006463
2447550.309000027038212.535207052446565.057033517037943.83003581
 2443660.83088667038049.009943542441985.526494417039186.21665864
#Sta/Elev= 30
    1000   468.5 1039.07  467.17 1071.69  459.18 1073.87  450.91 1308.28  442.61
 1775.16   442.4 1938.78   441.6    2230  440.93  3622.4  440.84 3844.58  445.78
 3902.42   439.2 4170.33  440.99    4650   441.3  4841.1  446.61 4860.26   459.4
 4906.88  446.25    4938  446.29 4945.07  451.57 5001.24   446.1    6103   448.5
    7457   440.4    8174     437    8766   440.3    8784   439.1    8802     427
    8867   417.5    8887     420    8941   440.4    9494     450   12800   446.5
#Mann= 9 ,-1,0
    1000     .07       0 1308.28     .09       0 1775.16    .045       0
 1938.78     .07       0 4170.33     .12       0    7457    .045       0
    8174    .035       0    8766     .05       0    8941    .045       0
Levee=-1,2230,460,-1,4650,460,,
#XS Ineff= 2 , 0
            2230     460    4650             460
Permanent Ineff=
       T       T
Bank Sta=2230,4650
XS Rating Curve= 0 ,0
Exp/Cntr=0.3,0.1

Type RM Length L Ch R = 1 ,93336.1 ,20,28,20
XS GIS Cut Line= 6
  2453036.414768 7039051.9060668 2448555.0580697 7039001.0485002
 2446934.1813335  7037993.670028 2443826.5424447 7037996.9252363
 2442057.8792502  7039155.779403 2440239.7567821 7039436.5125483
#Sta/Elev= 30
    1000  468.33 1044.56  460.14 1049.07  450.84    1216  445.59 1391.73  445.59
 1774.59   442.2 1937.97   441.8 3080.55  439.12 3914.43  445.77 3996.18  438.02
    4638  443.02 4671.84  445.56  5242.8  446.75 5713.54  439.23 5785.38  444.59
 6162.25  440.16 6340.45  447.25 7159.94  445.81 7437.52  439.86 7619.38  445.88
 7729.59  439.48  8235.5  435.38 8772.46  440.86 8878.01   417.5 8965.03   436.5
 9031.83  440.06 9357.53  445.9713209.59  443.9913591.42  445.6414541.94   464.5
#Mann= 9 ,-1,0
    1000     .07       0 1391.73     .09       0 1774.59    .045       0
 1937.97     .07       0 4671.84     .12       0 7729.59    .045       0
 8772.46    .035       0 9031.83     .05       0 9357.53    .045       0
Levee=-1,1216,460,-1,4638,460,,
#XS Ineff= 2 , 0
            1216     460    4638             460
Permanent Ineff=
       F       F
Bank Sta=1216,4638
XS Rating Curve= 0 ,0
Exp/Cntr=0.3,0.1

Type RM Length L Ch R = 1 ,93308.1 ,9,11,19
XS GIS Cut Line= 6
  2453062.798231 7039022.5473428 2448558.4463798 7038977.3158613
 2446935.5297132 7037980.7880836 2443823.8051762 7037988.6353058
 2442052.8676762 7039137.6110002 2440226.5189349 7039423.9257427
#Sta/Elev= 30
    1000  468.92 1047.65  460.38 1051.75  449.89    1236  445.53 2829.74  438.33
 3954.34  446.54 4204.56  440.08 4520.57  447.43    4667  446.04 5652.72  441.13
 7275.89  447.68 7510.43  441.42 7666.39  446.29 7725.43  440.08 8000.69  445.27
 8227.98  435.83 8479.47  439.67 8837.23  438.51 8904.82   417.5 8940.18  419.17
 8999.92  438.62 9117.45  448.18 9341.49   442.910506.43  449.7611407.27  446.46
11643.17  434.6911734.56  445.3311923.48  447.8613718.71  446.7314567.81  467.83
#Mann= 6 ,-1,0
    1000     .07       0 4520.57     .12       0 8000.69    .045       0
 8479.47    .035       0 8837.23     .05       0 8999.92    .045       0
Levee=-1,1236,460,-1,4667,460,,
#XS Ineff= 2 , 0
            1236     460    4667             460
Permanent Ineff=
       F       F
Bank Sta=1236,4667
XS Rating Curve= 0 ,0
Exp/Cntr=0.3,0.1

Type RM Length L Ch R = 1 ,93297.1 ,85,85,85
BEGIN DESCRIPTION:
93297.1
Upstream bounding cross-section for Sandy Lake Road bridge
---------------------------------------------------------------------
CDC CAR061818-01 Sandy Lake Ardinger Tract
Project located in LOB.
Cross-sections 93297.1 - 97178.1
---------------------------------------------------------------------
END DESCRIPTION:
XS GIS Cut Line= 6
2453066.561747017039007.696674472448786.985660497038967.59209588
2447555.995668417038166.889629052446724.131518517037930.82809331
 2443517.29180367038005.28102839 2441834.59635017038799.91001655
#Sta/Elev= 30
    1068   461.5    1070   450.1    1079   449.1    2400   442.5    3719   442.4
    4331   450.1    4879  451.05    5835   443.5    6965   444.2    7300   449.3
    7578   447.7    8050   456.1    8080     438    8400     433    8500   434.8
    8555     441    8750     441    8858     438    8880     435    8897   426.3
    8902   427.4    8930   417.5    8965   417.8    9000     434    9055     439
    9074     439    9090   455.7    9350   448.8    9650     446   12800   445.9
#Mann= 3 ,0,0
    1068    .035       0    2400     .03       0    4879    .035       0
Levee=-1,2400,460,-1,4879,460,,
#XS Ineff= 2 , 0
            2400     460    4879             460
Permanent Ineff=
       T       T
Bank Sta=2400,4879
XS Rating Curve= 0 ,0
Exp/Cntr=0.3,0.1

Type RM Length L Ch R = 1 ,93212.1 ,10,15,20
BEGIN DESCRIPTION:
This cross section corresponds to cross section 93212 of the non-georeferenced CDC model which was the source of this model.
Downstream bounding cross-section for Sandy Lake Road bridge
END DESCRIPTION:
XS GIS Cut Line= 6
2453032.140556017038966.992687632448520.069527697038883.64377296
2447597.799390587038109.242434642446642.141196947037819.29157096
2443907.252637837037866.266214552441707.816747997038336.53299055
#Sta/Elev= 30
    1068   461.5    1070   450.1    1079   449.1    2400   442.5    3719   442.4
    4331   450.1    4879451.0464    5835   443.5    6965   444.2    7200   448.7
    7668   448.6    8050   456.1    8050     448    8080     438    8400     433
    8500   434.8    8555     441    8858     438    8880     435    8897   426.3
    8902   427.4    8930   417.5    8965   417.8    9000     434    9074     439
    9090     447    9090   455.7    9350   448.8    9650     446   12800   445.9
#Mann= 3 ,0,0
    1068    .045       0    2400     .05       0    4879    .045       0
Levee=-1,2400,460,-1,4879,460,,
#XS Ineff= 2 , 0
            2400     460    4879             460
Permanent Ineff=
       T       T
Bank Sta=2400,4879
XS Rating Curve= 0 ,0
Exp/Cntr=0.3,0.1

Type RM Length L Ch R = 1 ,93197.1 ,1,1,1
BEGIN DESCRIPTION:
This cross section corresponds to cross section 93197 of the non-georeferenced CDC model which was the source of this model.
END DESCRIPTION:
XS GIS Cut Line= 6
2453120.484211337038918.043310462448624.117547937038876.03912938
2447622.075260677038085.549240542446594.051726167037793.92941697
2443835.875484027037852.24885413 2441886.55884467038237.30353022
#Sta/Elev= 30
    1000   467.3    1066   462.6    1068   450.8    1079   449.8    1330   444.6
    1502   446.3    1520     460    1730     460    1730     443    1900   441.4
    1900     460    2520     460    2523   442.5    2684     441    3908   441.9
    4879450.0003    6064   450.5    6334   442.7    7679   445.1    8132     438
    8445   432.3    8580   441.3    8893   437.6    8930   417.5    8960   417.5
    9046   434.5    9046   437.6    9168   447.4   12176   448.9   12635   444.4
#Mann= 7 ,-1,0
    1000     .07       0    2684     .05       0    3908     .12       0
    6334    .065       0    8132    .045       0    8893     .05       0
    9046     .05       0
Levee=-1,1520,460,-1,4879,460,,
#XS Ineff= 2 , 0
            1520     460    4879             460
Permanent Ineff=
       T       T
Bank Sta=1520,4879
XS Rating Curve= 0 ,0
Exp/Cntr=0.3,0.1

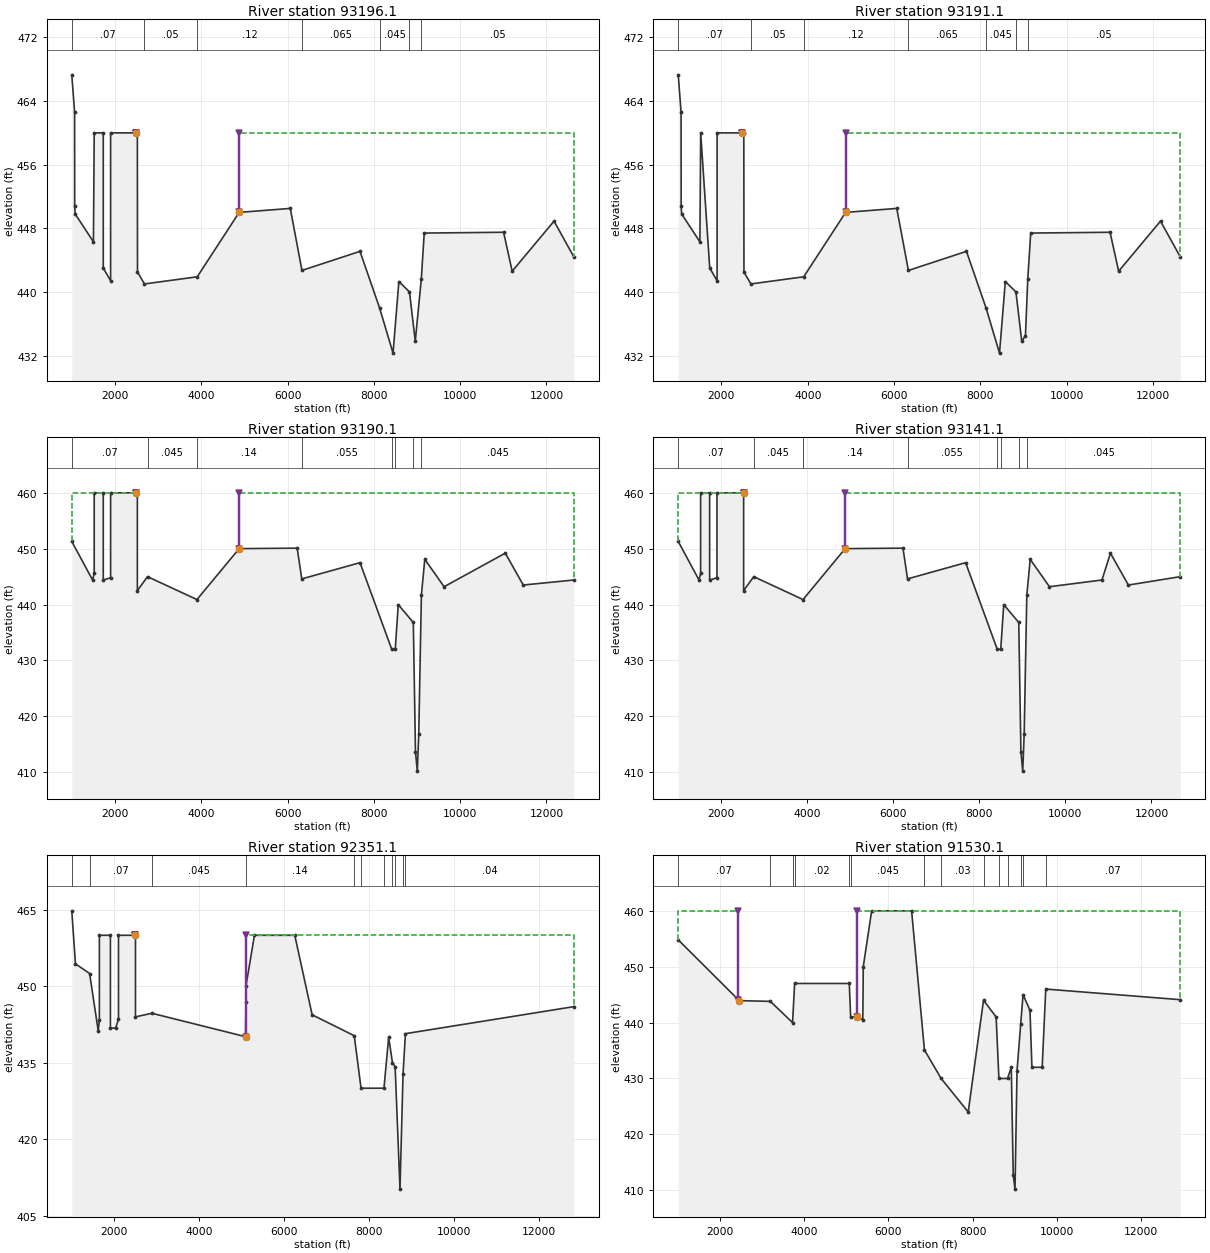
Type RM Length L Ch R = 1 ,93196.1 ,5,5,5
BEGIN DESCRIPTION:
This cross section corresponds to cross section 93196 of the non-georeferenced CDC model which was the source of this model.
END DESCRIPTION:
XS GIS Cut Line= 6
2453161.383407747038911.607299722448592.968660097038861.20648189
2447619.803611677038082.320244392446590.514987837037792.19451229
2443830.769195027037851.319065972441921.452803677038226.72940439
#Sta/Elev= 30
    1000   467.3    1066   462.6    1068   450.8    1079   449.8    1502   446.3
    1520     460    1730     460    1730     443    1900   441.4    1900     460
    2480     460    2520     460    2523   442.5    2684     441    3908   441.9
    4879450.0003    6064   450.5    6334   442.7    7679   445.1    8132     438
    8445   432.3    8580   441.3    8826     440    8960   433.8    9100   441.6
    9168   447.4   11007   447.5   11206   442.6   12176   448.9   12635   444.4
#Mann= 7 ,-1,0
    1000     .07       0    2684     .05       0    3908     .12       0
    6334    .065       0    8132    .045       0    8826     .02       0
    9100     .05       0
Levee=-1,2480,460,-1,4879,460,,
#XS Ineff= 2 , 0
            2480     460    4879             460
Permanent Ineff=
       T       T
Bank Sta=2480,4879
XS Rating Curve= 0 ,0
Exp/Cntr=0.3,0.1

Type RM Length L Ch R = 1 ,93191.1 ,1,1,1
BEGIN DESCRIPTION:
This cross section corresponds to cross section 93191 of the non-georeferenced CDC model which was the source of this model.
END DESCRIPTION:
XS GIS Cut Line= 6
 2453153.70166467038906.782834312448582.513956587038855.67696539
2447608.631061857038066.236943222446572.952030847037783.50916222
2443805.37685734 7037846.64322232441915.66278902 7038211.8235943
#Sta/Elev= 30
    1000   467.3    1066   462.6    1068   450.8    1079   449.8    1502   446.3
    1520     460    1730     443    1900   441.4    1900     460    2480     460
    2520     460    2523   442.5    2684     441    3908   441.9    4879450.0003
    6064   450.5    6334   442.7    7679   445.1    8132     438    8445   432.3
    8580   441.3    8826     440    8960   433.8    9046   434.5    9100   441.6
    9168   447.4   11007   447.5   11206   442.6   12176   448.9   12635   444.4
#Mann= 7 ,-1,0
    1000     .07       0    2684     .05       0    3908     .12       0
    6334    .065       0    8132    .045       0    8826     .02       0
    9100     .05       0
Levee=-1,2480,460,-1,4879,460,,
#XS Ineff= 2 , 0
            2480     460    4879             460
Permanent Ineff=
       T       T
Bank Sta=2480,4879
XS Rating Curve= 0 ,0
Exp/Cntr=0.3,0.1

Type RM Length L Ch R = 1 ,93190.1 ,49,49,49
BEGIN DESCRIPTION:
This cross section corresponds to cross section 93190 of the non-georeferenced CDC model which was the source of this model.
END DESCRIPTION:
XS GIS Cut Line= 6
      2453153.74      7038905.78 2448582.5139566 7038855.6769654
 2447608.6310619 7038066.2369432 2446572.9520308 7037783.5091622
 2443805.3768573 7037846.6432223  2441915.662789 7038211.8232662
#Sta/Elev= 30
    1000   451.3    1483   444.4    1520   445.6    1520     460    1730     460
    1730   444.4    1900   444.8    1900     460    2480     460    2520     460
    2520   442.5    2755     445    3901   440.9    4879450.0134    6224   450.1
    6330   444.6    7680   447.5    8415     432    8496     432    8566     440
    8915   436.8    8965   413.7    9007   410.2    9041   416.8    9102   441.7
    9181   448.1    9628   443.2   11046   449.2   11463   443.5   12635   444.4
#Mann= 8 ,-1,0
    1000     .07       0    2755    .045       0    3901     .14       0
    6330    .055       0    8415    .035       0    8496     .12       0
    8915     .05       0    9102    .045       0
Levee=-1,2480,460,-1,4879,460,,
#XS Ineff= 2 , 0
            2480     460    4879             460
Permanent Ineff=
       T       T
Bank Sta=2480,4879
XS Rating Curve= 0 ,0
Exp/Cntr=0.3,0.1

Type RM Length L Ch R = 1 ,93141.1 ,760,900,740
BEGIN DESCRIPTION:
This cross section corresponds to cross section 93141 of the non-georeferenced CDC model which was the source of this model.
END DESCRIPTION:
XS GIS Cut Line= 6
2453165.058925337038843.361045142448594.03788367 7038794.2240043
2447632.440069357038006.71606489  2446574.4408737037721.01223996
2445907.796865087037851.960140792441858.408966517037755.36518963
#Sta/Elev= 30
    1000   451.3    1483   444.4    1520   445.6    1520     460    1730     460
    1730   444.4    1900   444.8    1900     460    2520     460    2520   442.5
    2755     445    3901   440.9    4879450.0134    6224   450.1    6330   444.6
    7680   447.5    8415     432    8496     432    8566     440    8915   436.8
    8965   413.7    9007   410.2    9041   416.8    9102   441.7    9181   448.1
    9628   443.2   10849   444.4   11046   449.2   11463   443.5   12670     445
#Mann= 8 ,-1,0
    1000     .07       0    2755    .045       0    3901     .14       0
    6330    .055       0    8415    .035       0    8496     .12       0
    8915     .05       0    9102    .045       0
Levee=-1,2520,460,-1,4879,460,,
#XS Ineff= 2 , 0
            2520     460    4879             460
Permanent Ineff=
       T       T
Bank Sta=2520,4879
XS Rating Curve= 0 ,0
Exp/Cntr=0.3,0.1

Type RM Length L Ch R = 1 ,92351.1 ,820,680,820
BEGIN DESCRIPTION:
This cross section corresponds to cross section 92351 of the non-georeferenced CDC model which was the source of this model.
END DESCRIPTION:
XS GIS Cut Line= 3
2453370.468947597038416.698184552446778.237053337037093.70312713
2441681.935894257037078.87244813
#Sta/Elev= 30
    1000   464.8    1087   454.4    1420   452.5    1622   441.3    1650   443.3
    1650     460    1910     460    1910   441.8    2034   441.8    2100   443.6
    2100     460    2500     460    2500     444    2887   444.7    5090440.1099
    5100     447    5100     450    5300     460    6250     460    6659   444.4
    7650   440.3    7810     430    8350     430    8460     440    8550     435
    8613   434.2    8727   410.2    8799   432.8    8855   440.7   12820     446
#Mann= 11 ,-1,0
    1000    .045       0    1420     .07       0    2887    .045       0
    5100     .14       0    7650     .05       0    7810     .03       0
    8350     .05       0    8550     .14       0    8613     .05       0
    8799     .14       0    8855     .04       0
Levee=-1,2500,460,-1,5090,460,,
#XS Ineff= 2 , 0
            2500     460    5090             460
Permanent Ineff=
       T       T
Bank Sta=2500,5090
XS Rating Curve= 0 ,0
Exp/Cntr=0.3,0.1

Type RM Length L Ch R = 1 ,91530.1 ,333.71,277,333.71
BEGIN DESCRIPTION:
CDC CAR 092120-1 Western Extrusions
91530.1
END DESCRIPTION:
XS GIS Cut Line= 3
  2453657.147836 7037825.5189207 2446457.1701102 7036270.7431589
 2441883.6500578  7036341.302401
#Sta/Elev= 30
    1000   454.8  2451.1  443.93    3190   443.8    3719     440    3768     447
    5068     447    5100     441    5240     441    5390   440.5    5400     450
    5600     460    6550     460    6855   435.1    7252     430    7896     424
    8260     444    8560     441    8626     430    8832     430    8920     432
    8967   412.7    9009   410.2    9057   431.4    9145   439.8    9200     445
    9365   442.2    9411     432    9655     432    9740     446   12940   444.1
#Mann= 14 ,-1,0
    1000     .07       0    3190    .045       0    3719     .03       0
    3768     .02       0    5068     .03       0    5100    .045       0
    6855    .035       0    7252     .03       0    8260    .045       0
    8626     .03       0    8832     .05       0    9145     .14       0
    9200    .035       0    9740     .07       0
Levee=-1,2430,460,-1,5240,460,,
#XS Ineff= 2 , 0
            2430     460    5240             460
Permanent Ineff=
       T       T
Bank Sta=2451.1,5240
XS Rating Curve= 0 ,0
Exp/Cntr=0.3,0.1

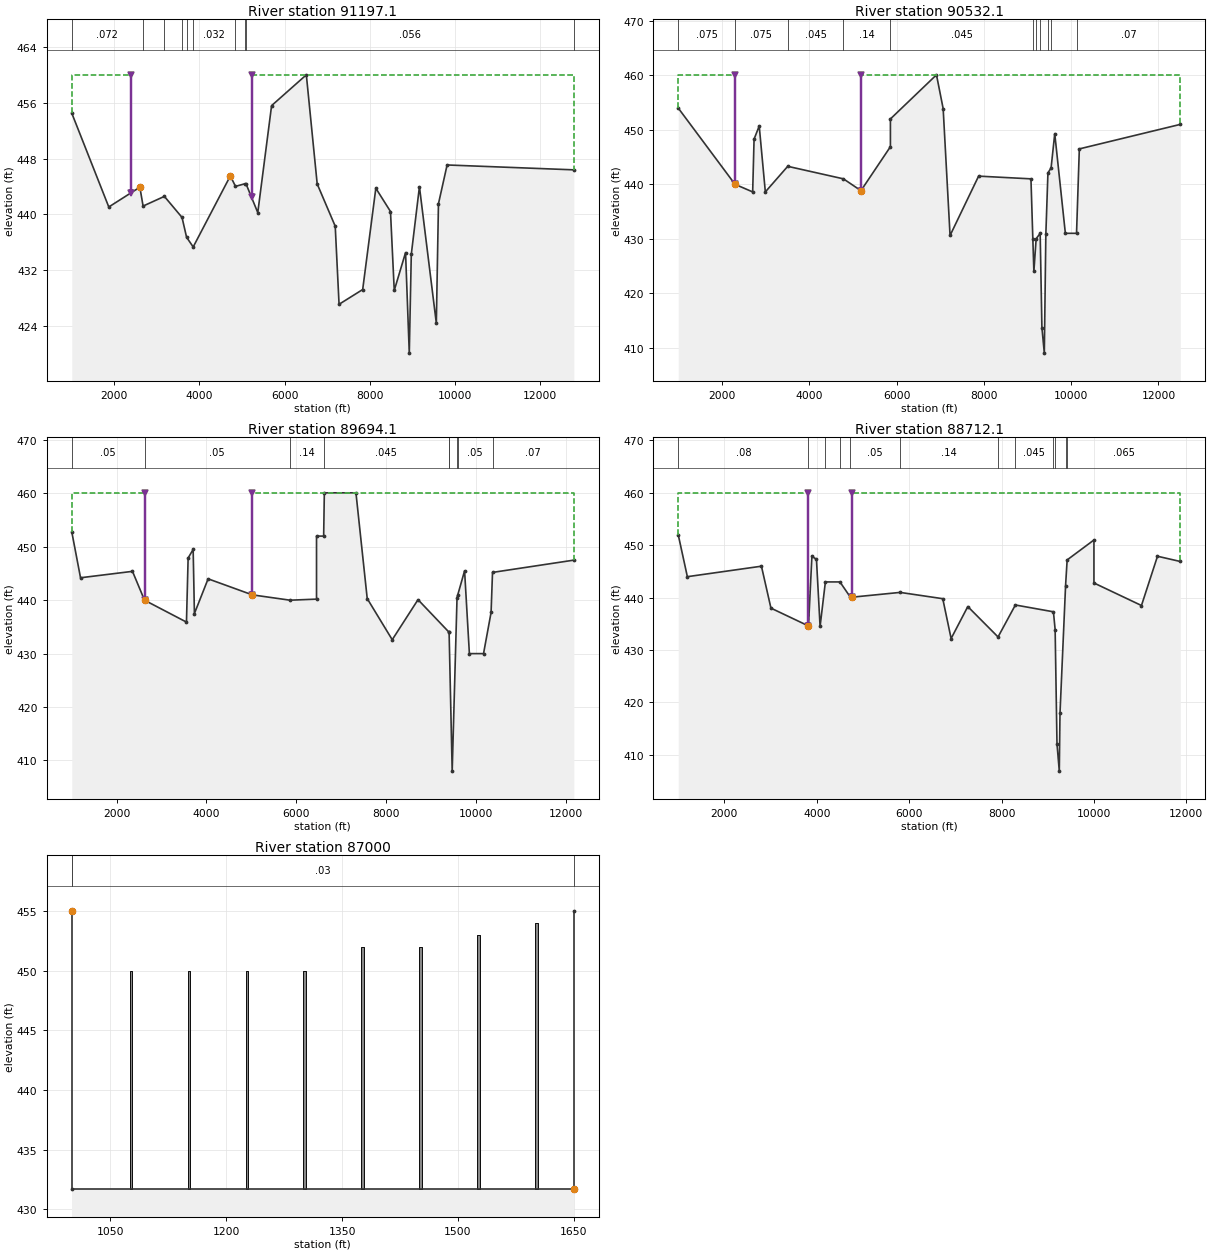
Type RM Length L Ch R = 1 ,91197.1 ,666.18,552.98,666.18
BEGIN DESCRIPTION:
CDC CAR 092120-1 Western Extrusions
Added cross-section.
END DESCRIPTION:
XS GIS Cut Line= 5
  2453767.4382327037599.300443812446520.950107547035948.81744172
2446383.479754217035938.749532792443386.861097487035993.80230705
2442032.932758397036015.02715394
#Sta/Elev= 30
    1000  454.54  1869.4  441.07  2599.6  443.91 2675.13   441.2 3175.08  442.59
 3589.81  439.57 3696.54  436.73 3851.98  435.33 4724.32  445.53 4845.78  444.03
 5059.15  444.39 5094.53  444.37 5369.14  440.26 5693.63  455.62 6509.78  460.04
 6764.46  444.38 7188.27  438.31 7278.32   427.1 7833.32  429.22 8142.08  443.76
 8486.24  440.42 8574.74  429.09 8840.23  434.52 8927.74  420.09 8974.95  434.27
 9166.27  443.98 9562.97  424.39 9613.12  441.53 9816.29   447.112793.15   446.4
#Mann= 10 ,-1,0
    1000    .072       0 2675.13    .055       0 3175.08    .049       0
 3589.81    .037       0 3696.54    .038       0 3851.98    .032       0
 4845.78    .065       0 5059.15     .05       0 5094.53    .056       0
12793.15     .07       0
Levee=-1,2386.614,460,-1,5221.645,460,,
#XS Ineff= 2 , 0
        2386.614     4605221.645             460
Permanent Ineff=
       T       T
Bank Sta=2599.6,4724.32
XS Rating Curve= 0 ,0
Exp/Cntr=0.3,0.1

Type RM Length L Ch R = 1 ,90532.1 ,650,838,950
BEGIN DESCRIPTION:
This cross section corresponds to cross section 90532 of the non-georeferenced CDC model which was the source of this model.
END DESCRIPTION:
XS GIS Cut Line= 4
2453987.691138337037147.536024722446511.170002167035271.50893688
2443460.91166702 7035345.00649332442720.441363197035356.46742839
#Sta/Elev= 30
    1000     454    2300     440    2705   438.6    2737   448.3    2855   450.7
    2995   438.6    3508   443.3    4784     441    5185438.8321    5860   446.9
    5860     452    6915   460.1    7068   453.9    7226   430.6    7880   441.5
    9079     441    9122     430    9146     424    9198     430    9290     431
    9330   413.7    9385     409    9420   430.8    9468   442.1    9540     443
    9624   449.3    9867     431   10123     431   10187   446.5   12500     451
#Mann= 11 ,-1,0
    1000    .075       0    2300    .075       0    3508    .045       0
    4784     .14       0    5860    .045       0    9122     .03       0
    9198    .045       0    9290     .05       0    9468     .14       0
    9540    .035       0   10123     .07       0
Levee=-1,2300,460,-1,5185,460,,
#XS Ineff= 2 , 0
            2300     460    5185             460
Permanent Ineff=
       T       T
Bank Sta=2300,5185
XS Rating Curve= 0 ,0
Exp/Cntr=0.3,0.1

Type RM Length L Ch R = 1 ,89694.1 ,800,800,1000
BEGIN DESCRIPTION:
This cross section corresponds to cross section 89694 of the non-georeferenced CDC model which was the source of this model.
---------------------------------------------------------------------
CDC CAR040507-1 Western Extrusions
Cross-section 89694-91530
Located in LOB within ineffective flow area.
---------------------------------------------------------------------
END DESCRIPTION:
XS GIS Cut Line= 5
2454416.018037597036265.561082632446415.268947247034636.62405179
2445895.703057267034393.601243882444214.567311917034485.10959105
2443457.398878757034518.24567963
#Sta/Elev= 30
    1000   452.8    1195   444.2    2352   445.4    2620     440    3554   435.9
    3591   447.9    3703   449.5    3731   437.5    4036     444    5020     441
    5860     440    6450   440.2    6450     452    6609     452    6624   460.1
    7328   460.1    7579   440.3    8136   432.6    8710   440.1    9390   434.1
    9402   434.1    9471     408    9579   440.5    9592   440.9    9747   445.5
    9854     430   10169     430   10337   437.7   10369   445.2   12180   447.5
#Mann= 9 ,-1,0
    1000     .05       0    2620     .05       0    5860     .14       0
    6609    .045       0    9390     .14       0    9402     .05       0
    9579     .14       0    9592     .05       0   10369     .07       0
Levee=-1,2620,460,-1,5020,460,,
#XS Ineff= 2 , 0
            2620     460    5020             460
Permanent Ineff=
       T       T
Bank Sta=2620,5020
XS Rating Curve= 0 ,0
Exp/Cntr=0.3,0.1

Type RM Length L Ch R = 1 ,88712.1 ,1150,550,950
BEGIN DESCRIPTION:
This cross section corresponds to cross section 88712 of the non-georeferenced CDC model which was the source of this model.
OEI Updated Ground Data and manning's n values  for proposed conditions on West Tracts
END DESCRIPTION:
XS GIS Cut Line= 4
2454761.838868267035572.279004632447177.857973257033966.21692805
2446440.408988837033572.352230222444164.230142277033732.23708105
#Sta/Elev= 30
    1000     452 1197.54     444 2801.35     446 3006.98     438    3820   434.6
    3894   447.9  3992.5   447.3    4071   434.5  4185.7     443 4500.86     443
    4726   440.1    4770440.0958    5804     441    6727   439.8    6908   432.2
    7269   438.3    7924   432.5    8299   438.6    9123   437.3    9160   433.9
    9200   412.1    9250   406.9    9265   417.9    9386   442.3    9420   447.2
   10000     451   10000   442.8   11029   438.5   11376   447.9   11870   446.9
#Mann= 12 ,-1,0
    1000     .08       0    3820     .08       0  4185.7     .02       0
 4500.86     .08       0    4726     .05       0    5804     .14       0
    7924     .07       0    8299    .045       0    9123     .12       0
    9160     .05       0    9386     .12       0    9420    .065       0
Levee=-1,3820,460,-1,4770,460,,
#XS Ineff= 2 , 0
            3820     460    4770             460
Permanent Ineff=
       T       T
Bank Sta=3820,4770
XS Rating Curve= 0 ,0
Exp/Cntr=0.3,0.1

Type RM Length L Ch R = 1 ,87000   ,,,
BEGIN DESCRIPTION:
This cross section corresponds to cross section 87000 of the non-georeferenced CDC model which was the source of this model.
PGBT, West Face of Bridge Structure Approximated
END DESCRIPTION:
XS GIS Cut Line= 2
2450736.60840169 7034400.27806782451049.781003687033963.45840338
#Sta/Elev= 4
    1000     455    1000   431.7    1650   431.7    1650     455
#Mann= 3 ,0,0
    1000    .055       0    1000     .03       0    1650    .055       0
#Block Obstruct= 8 ,-1
    1075    1078     450    1150    1153     450    1225    1228     450
    1300    1303     450    1375    1378     452    1450    1453     452
    1525    1528     453    1600    1603     454
#XS Lid=3
    1000  452.62  448.27    1180  454.09  448.61    1650  457.92   453.7
Bank Sta=1000,1650
XS Rating Curve= 0 ,0
Exp/Cntr=0.3,0.1

River Reach=Elm Fork        ,ef3 ds
Reach XY= 30
      2447356.93      7032903.31      2449276.42      7028990.09
      2448521.48      7026637.83      2447000.53      7025969.64
       2449243.1      7024505.45      2447907.61      7024057.09
      2447661.34       7018966.6      2449579.68      7018119.64
      2451509.59      7014814.57      2451262.61      7011037.61
       2450116.3      7010513.16      2449776.69      7008454.84
      2450712.67      7007237.43      2450043.63      7003476.24
      2452456.92      7003195.07      2451436.24      7001846.74
      2452973.76      7000073.06      2452181.75      6998915.55
      2454526.25      6998940.04      2454971.66       6998016.3
      2455835.87      6998821.28      2456369.33      6997815.18
      2459151.98      6996708.01      2460049.87      6997211.53
      2460262.81      6996093.07      2463259.53      6995089.58
      2462990.63      6989165.68      2458140.49       6983253.5
      2458296.43      6980416.59       2460651.9      6977070.51