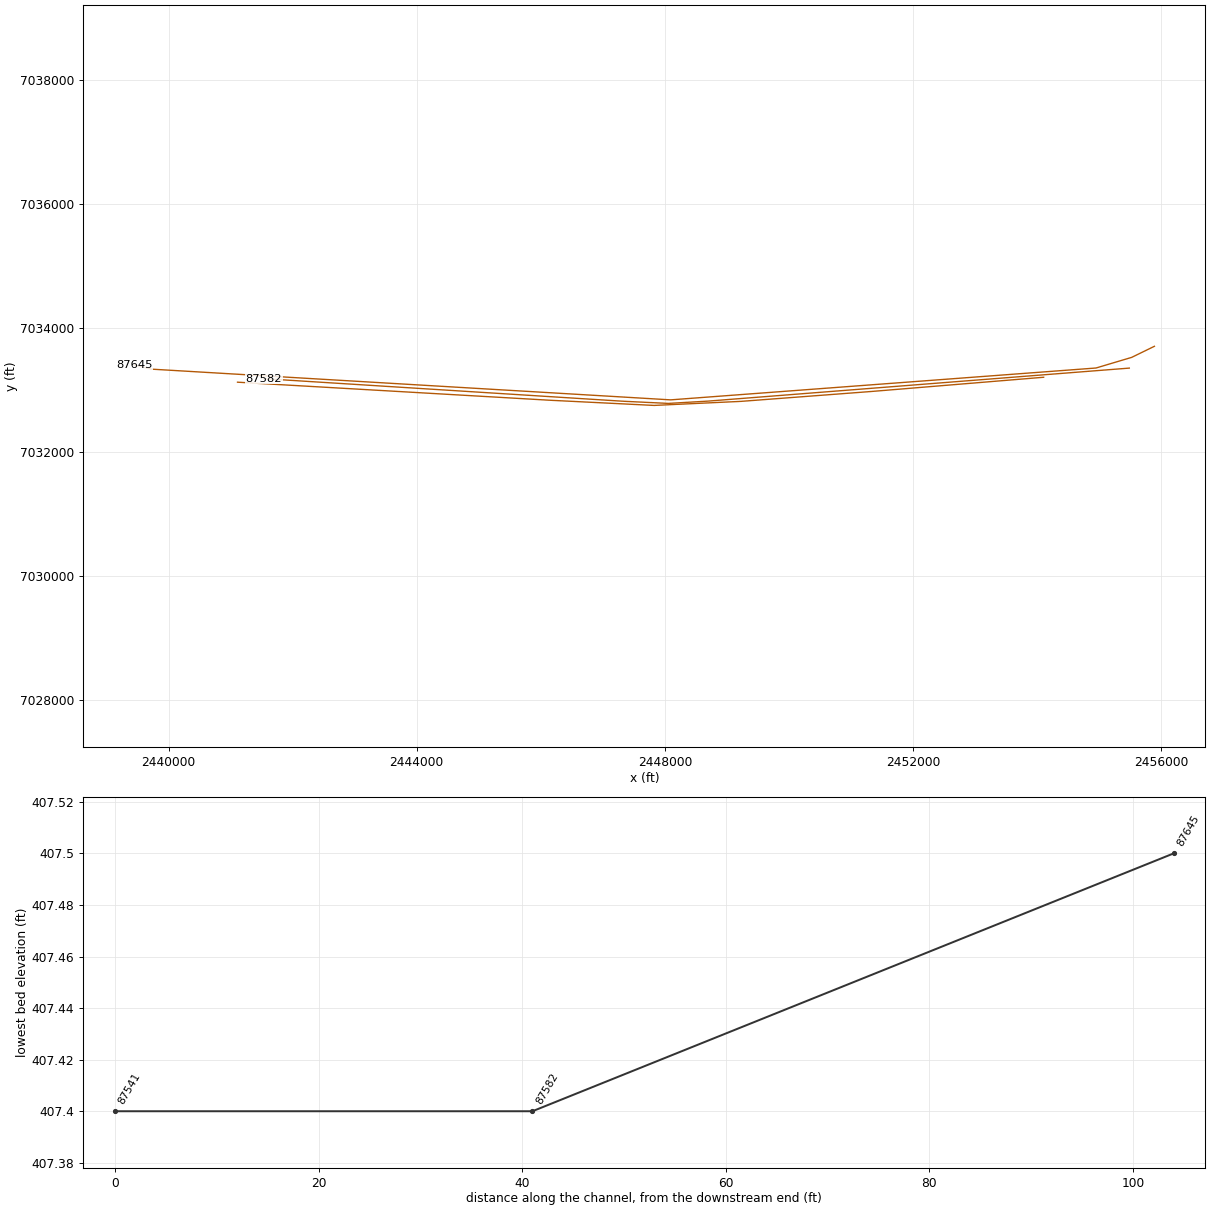
HEC-RAS study CDC_Consolidated_Model.prj: Upper Trinity CDC Consolidated Model

--- CDC_Consolidated_Model.g13 (geometry) --- (continued)

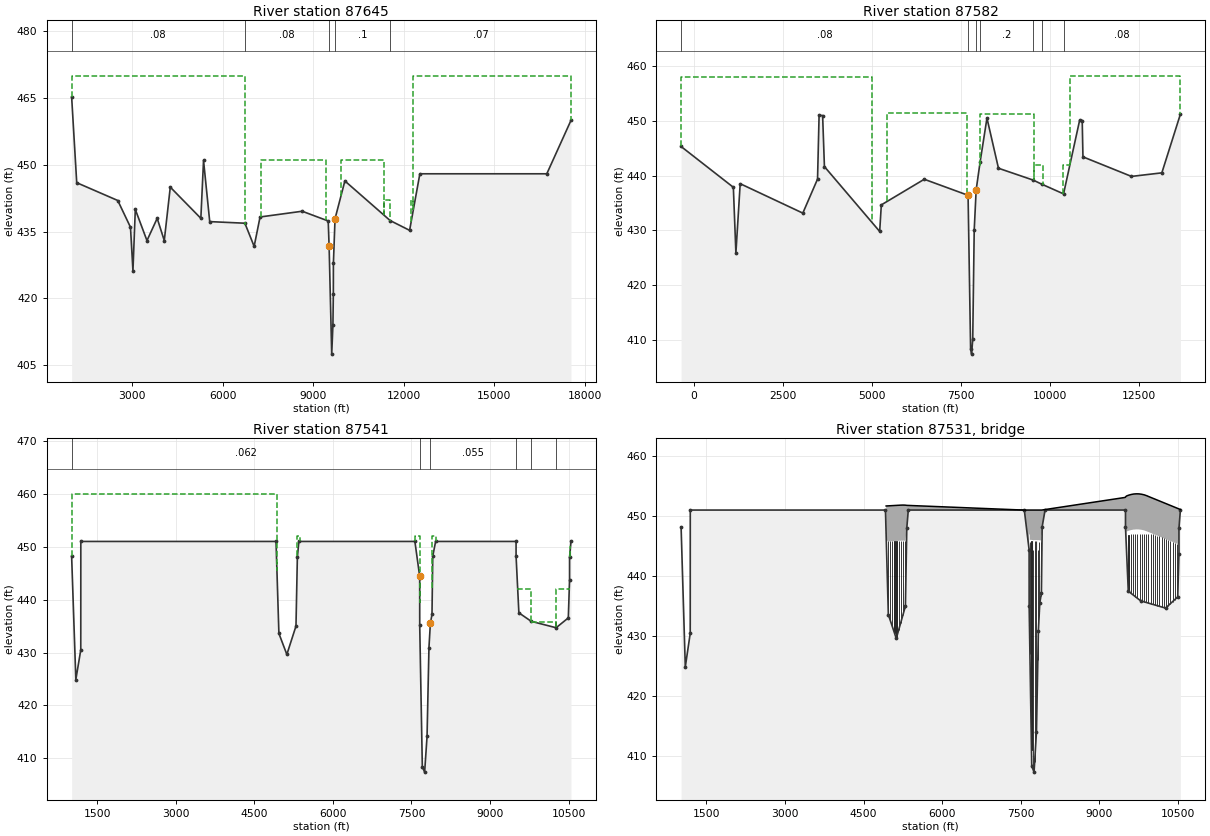
Type RM Length L Ch R = 1 ,87645   ,60.5,63,58
BEGIN DESCRIPTION:
87645
Luna Road Extension USACE Permit Number 199300443
Cross-section 87645 - 90532
Located in LOB.
---------------------------------------------------------------------
CDC CAR171221-01 Valwood Crossing
In LOB between cross-sections 87541 - 88712.
This project supercedes previous two CDC projects listed below.
CDC PROJECTS: CAR032511-1 AND CAR032511-2 PROPOSED LUNA ROAD LP and #2 LP
---------------------------------------------------------------------
END DESCRIPTION:
XS GIS Cut Line= 6
2455887.09514791 7033701.99403132455520.128034097033523.18992697
  2454945.8729497033352.136135222448091.474912437032838.97213531
2439726.696366437033333.714256052439450.78484476 7033400.9532948
#Sta/Elev= 30
    1000  465.29 1168.59     446 2528.56     442 2949.73     436 3031.52  426.22
 3109.47     440 3496.07     433  3834.8     438  4069.4     433  4268.4     445
 5281.31     438  5370.2     451 5575.21  437.26    6740   436.9    7047   431.7
    7243   438.3 8639.04  439.59    9501   437.4    9531   431.7    9617   407.5
    9657     414    9671   421.1    9673   427.9    9727   437.910053.13  446.39
11552.79   437.5   12198   435.312537.56     448 16743.4     448 17544.8     460
#Mann= 5 ,-1,0
    1000     .08       0    6740     .08       0    9531     .05       0
    9727      .1       011552.79     .07       0
#XS Ineff= 6 ,-1
    1000  6757.5     470    7280    9420     451    9920 11336.1     451
 11336.1   11560   442.2 12249.9 12319.8   442.2 12319.8 17544.8     470
Permanent Ineff=
       F       F       F       T       T       F
Bank Sta=9531,9727
XS Rating Curve= 0 ,0
Exp/Cntr=0.3,0.1

Type RM Length L Ch R = 1 ,87582   ,22,41,46
BEGIN DESCRIPTION:
New section at North ROW line
END DESCRIPTION:
XS GIS Cut Line= 6
  2455482.505018  7033350.636151 2448691.0987682 7032818.6338361
 2448056.8539766 7032781.7675167 2447360.7578611 7032814.9220418
 2447253.9467138 7032821.1584311 2441533.7738261 7033180.8155491
#Sta/Elev= 30
  -349.5   445.3  1116.9  437.85  1188.1  425.85  1308.6  438.51 3065.48  433.14
 3478.73  439.35 3522.16     451 3621.33  450.95 3671.78  441.63 5222.44  429.79
 5267.85  434.64 6472.87  439.32 7702.19  436.39    7773   408.4    7801   407.4
    7833  410.15  7874.2  430.01    7929  437.38 8039.65  442.46 8232.07  450.48
 8554.92  441.33 9527.41  439.17  9766.6  438.4310380.91  436.6510832.48   450.1
10904.37  450.0310925.14  443.4112286.15  439.84 13138.5  440.4913660.51  451.23
#Mann= 7 ,-1,0
  -349.5     .08       0 7702.19     .05       0    7929     .06       0
 8039.65      .2       0 9527.41     .08       0  9766.6     .05       0
10380.91     .08       0
#XS Ineff= 6 ,-1
  -349.5  5005.8     458  5434.5  7675.1   451.4  8023.2  9551.7   451.2
  9551.7  9794.4     442 10378.8 10555.1     442 10555.113660.51   458.2
Permanent Ineff=
       T       T       T       T       T       T
Bank Sta=7702.19,7929
XS Rating Curve= 0 ,0
Exp/Cntr=0.3,0.1

Type RM Length L Ch R = 1 ,87541   ,19,19,19
BEGIN DESCRIPTION:
Upstream of Cotton Belt Regional Rail
H&B Trail added to Staion 5060 to 5074
---------------------------------------------------------------------
CDC PROJECTS: CAR032511-1 AND CAR032511-2 PROPOSED LUNA ROAD LP and #2 LP
CROSS-SECTION 87541 - 89694
---------------------------------------------------------------------
END DESCRIPTION:
XS GIS Cut Line= 6
2454102.120371437033203.139057892451323.501912927032973.65756147
2449224.330586347032814.517131722447823.491196427032749.33812821
 2446156.59164317032832.145377292441112.34216543 7033123.6423869
#Sta/Elev= 30
  1015.6   448.2    1096   424.9    1190   430.5    1191     451    4916     451
    4971  433.61 5122.55  429.64 5296.85     435 5323.27     448    5352     451
    7566     451 7657.76  444.39 7658.21  435.12    7708   408.4    7752   407.4
 7798.15  414.14 7834.56  430.95 7861.47   435.5 7892.34  437.21 7907.13  448.23
    7962     451    9497     451    9497   448.2  9550.5  437.51 9786.69   435.9
10261.24  434.6910493.88  436.5510517.75  443.7510517.76     448   10545     451
#Mann= 6 ,-1,0
  1015.6    .062       0 7657.76     .05       0 7861.47    .055       0
    9497     .09       0 9786.69    .055       010261.24     .09       0
#XS Ineff= 10 ,-1
  1015.6 4933.65     460 4933.66 5325.35     439 5325.35    5380     452
    7560    7658     452    7899    7965     452    7965 9518.24   435.8
 9518.24    9778     442    9778   10268   435.8   1026810517.76     442
10517.76   10545     450
Permanent Ineff=
       F       F       T       T       T       F       T       F       T       T
Bank Sta=7657.76,7861.47
XS Rating Curve= 0 ,0
Exp/Cntr=0.5,0.3

Type RM Length L Ch R = 3 ,87531   ,,,
BEGIN DESCRIPTION:
Cotton Belt Regional Rail
END DESCRIPTION:
Bridge Culvert--1,0,-1,-1, 0
Deck Dist Width WeirC Skew NumUp NumDn MinLoCord MaxHiCord MaxSubmerge Is_Ogee
0.5,18,2.6,0, 71, 71, , , 0.95, 0, ,,,
    4929 4931.49  4931.5  4967.5  5007.5  5047.5  5087.5  5127.5  5167.5  5207.5
  5216.5  5241.5  5247.5    5250  5287.5  5327.5 5327.51    7550    7550    7659
 7659.01  7672.2 7672.21    7703  7731.8 7731.81  7734.2 7734.21    7763    7820
  7822.8 7822.81  7825.2  7825.2    7828  7853.5  7884.5 7884.51    7898 7898.01
    9490 9490.01    9514 9514.01    9556    9605    9640    9655    9705  9715.8
    9755    9805    9855    9892    9905    9910    9934    9976   10018   10060
   10102   10144   10186   10228   10270   10354   10438   10522   10533   10546
10546.01
  451.68  451.68  451.68 451.698 451.718 451.738 451.758 451.778 451.798 451.818
  451.82  451.83  451.83  451.83  451.82  451.78  451.78     451     451     451
     451     451     451     451     451     451     451     451     451     451
     451     451     451     451     451     451     451     451     451     451
   453.1   453.1  453.33  453.33  453.47  453.59 453.646  453.67   453.7   453.7
  453.69  453.63  453.53 453.417  453.38  453.36 453.267 453.118 452.968 452.819
 452.669 452.519  452.37  452.22 452.071 451.771 451.472  451.17  451.13  451.09
  451.09
                 445.763 445.781 445.801 445.821 445.841 445.861 445.881 445.901
 445.903 445.913 445.913 445.913 445.903 445.863                     444     444
  447.02  446.87  446.04  446.04     446   444.4   444.4     446     446     446
     446   444.4   444.4     446     446  445.98  445.95  446.93  446.88     443
                 445.628 447.413 447.553 447.673 447.729 447.753 447.783 447.783
 447.773 447.713 447.613   447.5 447.463 447.443  447.35 447.201 447.051 446.902
 446.752 446.602 446.453 446.303 446.154 445.854 445.555  445.26  445.22  445.18
    4927 4931.49  4931.5  4967.5  5007.5  5047.5  5087.5  5127.5  5167.5  5207.5
  5216.5  5241.5  5247.5    5250  5287.5  5327.5 5327.51    7550    7550    7659
 7659.01  7672.2 7672.21    7703  7731.8 7731.81  7734.2 7734.21    7763    7820
  7822.8 7822.81  7825.2  7825.2    7828  7853.5  7884.5 7884.51    7898 7898.01
    9460 9460.01    9514 9514.01    9556    9605    9640    9655    9705  9715.8
    9755    9805    9855    9892    9905    9910    9934    9976   10018   10060
   10102   10144   10186   10228   10270   10354   10438   10522   10533   10575
10575.01
  451.68  451.68  451.68 451.698 451.718 451.738 451.758 451.778 451.798 451.818
  451.82  451.83  451.83  451.83  451.82  451.78  451.78     451     451     451
     451     451     451     451     451     451     451     451     451     451
     451     451     451     451     451     451     451     451     451     451
   453.1   453.1  453.33  453.33  453.47  453.59 453.646  453.67   453.7   453.7
  453.69  453.63  453.53 453.417  453.38  453.36 453.267 453.118 452.968 452.819
 452.669 452.519  452.37  452.22 452.071 451.771 451.472  451.17  451.13     451
     451
                 445.763 445.781 445.801 445.821 445.841 445.861 445.881 445.901
 445.903 445.913 445.913 445.913 445.903 445.863                     441     441
  446.97  447.05  445.95  446.04     446   444.4   444.4     446     446     446
     446   444.4   444.4     446     446  445.93  446.02  446.98  446.92     443
                 445.628 447.413 447.553 447.673 447.729 447.753 447.783 447.783
 447.773 447.713 447.613   447.5 447.463 447.443  447.35 447.201 447.051 446.902
 446.752 446.602 446.453 446.303 446.154 445.854 445.555  445.26  445.22  445.09
Pier Skew, UpSta & Num, DnSta & Num=  ,4967.5, 6 ,4967.5, 6 , 5 , 5 , 0 ,,
       2       2   1.167   1.167       3       3
     420  437.72  437.72 442.719 442.719     447
       2       2   1.167   1.167       3       3
     420  437.72  437.72 442.719 442.719     447
Pier Skew, UpSta & Num, DnSta & Num=  ,5007.5, 6 ,5007.5, 6 , 5 , 5 , 0 ,,
       2       2   1.167   1.167       3       3
     420  433.74  433.74 442.739 442.739     447
       2       2   1.167   1.167       3       3
     420  433.74  433.74 442.739 442.739     447
Pier Skew, UpSta & Num, DnSta & Num=  ,5047.5, 6 ,5047.5, 6 , 5 , 5 , 0 ,,
       2       2   1.167   1.167       3       3
     420  432.26  432.26 442.759 442.759     447
       2       2   1.167   1.167       3       3
     420  432.26  432.26 442.759 442.759     447
Pier Skew, UpSta & Num, DnSta & Num=  ,5087.5, 6 ,5087.5, 6 , 5 , 5 , 0 ,,
       2       2   1.167   1.167       3       3
     420  431.78  431.78 442.779 442.779     447
       2       2   1.167   1.167       3       3
     420  431.78  431.78 442.779 442.779     447
Pier Skew, UpSta & Num, DnSta & Num=  ,5127.5, 6 ,5127.5, 6 , 5 , 5 , 0 ,,
       2       2   1.167   1.167       3       3
     420   431.3   431.3 442.799 442.799     447
       2       2   1.167   1.167       3       3
     420   431.3   431.3 442.799 442.799     447
Pier Skew, UpSta & Num, DnSta & Num=  ,5167.5, 6 ,5167.5, 6 , 5 , 5 , 0 ,,
       2       2   1.167   1.167       3       3
     420  432.32  432.32 442.819 442.819     447
       2       2   1.167   1.167       3       3
     420  432.32  432.32 442.819 442.819     447
Pier Skew, UpSta & Num, DnSta & Num=  ,5207.5, 6 ,5207.5, 6 , 5 , 5 , 0 ,,
       2       2   1.167   1.167       3       3
     420  432.84  432.84 442.839 442.839     447
       2       2   1.167   1.167       3       3
     420  432.84  432.84 442.839 442.839     447
Pier Skew, UpSta & Num, DnSta & Num=  ,5247.5, 6 ,5247.5, 6 , 5 , 5 , 0 ,,
       2       2   1.167   1.167       3       3
     420  434.85  434.85 442.851 442.851     447
       2       2   1.167   1.167       3       3
     420  434.85  434.85 442.851 442.851     447
Pier Skew, UpSta & Num, DnSta & Num=  ,5287.5, 6 ,5287.5, 6 , 5 , 5 , 0 ,,
       2       2   1.167   1.167       3       3
     420  435.84  435.84 442.841 442.841     447
       2       2   1.167   1.167       3       3
     420  435.84  435.84 442.841 442.841     447
Pier Skew, UpSta & Num, DnSta & Num=  ,7673.1, 4 ,7673.1, 4 , 3 , 3 , 0 ,,
     1.5     1.5       3       3
     415  443.39  443.39   445.7
     1.5     1.5       3       3
     415  443.33  443.33  445.75
Pier Skew, UpSta & Num, DnSta & Num=  ,7703, 4 ,7703, 4 , 3 , 3 , 0 ,,
     1.5     1.5     2.5     2.5
     415  443.22  443.22   445.8
     1.5     1.5     2.5     2.5
     415  443.33  443.33  445.83
Pier Skew, UpSta & Num, DnSta & Num=  ,7733, 2 ,7733, 2 , 0 , 0 , 0 ,,
       8     5.8
     420   444.4
       8     5.8
     420   444.4
Pier Skew, UpSta & Num, DnSta & Num=  ,7763, 4 ,7763, 4 , 3 , 3 , 0 ,,
     1.5     1.5     2.5     2.5
     415  443.28  443.28  445.84
     1.5     1.5     2.5     2.5
     415  443.28  443.28  445.78
Pier Skew, UpSta & Num, DnSta & Num=  ,7793, 4 ,7793, 4 , 3 , 3 , 0 ,,
     1.5     1.5     2.5     2.5
     415  443.28  443.28  445.84
     1.5     1.5     2.5     2.5
     415  443.28  443.28  445.78
Pier Skew, UpSta & Num, DnSta & Num=  ,7824, 2 ,7824, 2 , 0 , 0 , 0 ,,
       8     5.8
     420   444.4
       8     5.8
     420   444.4
Pier Skew, UpSta & Num, DnSta & Num=  ,7853.5, 4 ,7853.5, 4 , 3 , 3 , 0 ,,
     1.5     1.5     2.5     2.5
     415   443.2   443.2  445.76
     1.5     1.5     2.5     2.5
     415   443.2   443.2  445.75
Pier Skew, UpSta & Num, DnSta & Num=  ,7883.5, 4 ,7883.5, 4 , 3 , 3 , 0 ,,
     1.5     1.5       3       3
     415   443.2   443.2  445.76
     1.5     1.5       3       3
     415   443.2   443.2  445.75
Pier Skew, UpSta & Num, DnSta & Num=  ,9556, 6 ,9556, 6 , 5 , 5 , 0 ,,
       2       2   1.167   1.167       3       3
     420  440.62  440.62 444.491 444.491 446.849
       2       2   1.167   1.167       3       3
     420  440.62  440.62 444.491 444.491 446.849
Pier Skew, UpSta & Num, DnSta & Num=  ,9598, 6 ,9598, 6 , 5 , 5 , 0 ,,
       2       2   1.167   1.167       3       3
     420  438.67  438.67 444.594 444.594     447
       2       2   1.167   1.167       3       3
     420  438.67  438.67 444.594 444.594     447
Pier Skew, UpSta & Num, DnSta & Num=  ,9640, 6 ,9640, 6 , 5 , 5 , 0 ,,
       2       2   1.167   1.167       3       3
     420  437.73  437.73 444.667 444.667     447
       2       2   1.167   1.167       3       3
     420  437.73  437.73 444.667 444.667     447
Pier Skew, UpSta & Num, DnSta & Num=  ,9682, 6 ,9682, 6 , 5 , 5 , 0 ,,
       2       2   1.167   1.167       3       3
     420  438.78  438.78 444.711 444.711     447
       2       2   1.167   1.167       3       3
     420  438.78  438.78 444.711 444.711     447
Pier Skew, UpSta & Num, DnSta & Num=  ,9724, 6 ,9724, 6 , 5 , 5 , 0 ,,
       2       2   1.167   1.167       3       3
     420  438.89  438.89 444.721 444.721     447
       2       2   1.167   1.167       3       3
     420  438.89  438.89 444.721 444.721     447
Pier Skew, UpSta & Num, DnSta & Num=  ,9766, 6 ,9766, 6 , 5 , 5 , 0 ,,
       2       2   1.167   1.167       3       3
     420  438.94  438.94 444.698 444.698     447
       2       2   1.167   1.167       3       3
     420  438.94  438.94 444.698 444.698     447
Pier Skew, UpSta & Num, DnSta & Num=  ,9808, 6 ,9808, 6 , 5 , 5 , 0 ,,
       2       2   1.167   1.167       3       3
     420  436.99  436.99 444.641 444.641     447
       2       2   1.167   1.167       3       3
     420  436.99  436.99 444.641 444.641     447
Pier Skew, UpSta & Num, DnSta & Num=  ,9850, 6 ,9850, 6 , 5 , 5 , 0 ,,
       2       2   1.167   1.167       3       3
     420  437.05  437.05 444.561 444.561     447
       2       2   1.167   1.167       3       3
     420  437.05  437.05 444.561 444.561     447
Pier Skew, UpSta & Num, DnSta & Num=  ,9892, 6 ,9892, 6 , 5 , 5 , 0 ,,
       2       2   1.167   1.167       3       3
     420  436.94  436.94 444.438 444.438     447
       2       2   1.167   1.167       3       3
     420  436.94  436.94 444.438 444.438     447
Pier Skew, UpSta & Num, DnSta & Num=  ,9934, 6 ,9934, 6 , 5 , 5 , 0 ,,
       2       2   1.167   1.167       3       3
     420  436.29  436.29 444.288 444.288     447
       2       2   1.167   1.167       3       3
     420  436.29  436.29 444.288 444.288     447
Pier Skew, UpSta & Num, DnSta & Num=  ,9976, 6 ,9976, 6 , 5 , 5 , 0 ,,
       2       2   1.167   1.167       3       3
     420  436.64  436.64 444.138 444.138     447
       2       2   1.167   1.167       3       3
     420  436.64  436.64 444.138 444.138     447
Pier Skew, UpSta & Num, DnSta & Num=  ,10018, 6 ,10018, 6 , 5 , 5 , 0 ,,
       2       2   1.167   1.167       3       3
     420  436.49  436.49 443.989 443.989     447
       2       2   1.167   1.167       3       3
     420  436.49  436.49 443.989 443.989     447
Pier Skew, UpSta & Num, DnSta & Num=  ,10060, 6 ,10060, 6 , 5 , 5 , 0 ,,
       2       2   1.167   1.167       3       3
     420  436.84  436.84 443.839 443.839     447
       2       2   1.167   1.167       3       3
     420  436.84  436.84 443.839 443.839     447
Pier Skew, UpSta & Num, DnSta & Num=  ,10102, 6 ,10102, 6 , 5 , 5 , 0 ,,
       2       2   1.167   1.167       3       3
     420  436.69  436.69  443.69  443.69     447
       2       2   1.167   1.167       3       3
     420  436.69  436.69  443.69  443.69     447
Pier Skew, UpSta & Num, DnSta & Num=  ,10144, 6 ,10144, 6 , 5 , 5 , 0 ,,
       2       2   1.167   1.167       3       3
     420  436.54  436.54  443.54  443.54     447
       2       2   1.167   1.167       3       3
     420  436.54  436.54  443.54  443.54     447
Pier Skew, UpSta & Num, DnSta & Num=  ,10186, 6 ,10186, 6 , 5 , 5 , 0 ,,
       2       2   1.167   1.167       3       3
     420  436.39  436.39  443.39  443.39     447
       2       2   1.167   1.167       3       3
     420  436.39  436.39  443.39  443.39     447
Pier Skew, UpSta & Num, DnSta & Num=  ,10228, 6 ,10228, 6 , 5 , 5 , 0 ,,
       2       2   1.167   1.167       3       3
     420  436.74  436.74 443.241 443.241     447
       2       2   1.167   1.167       3       3
     420  436.74  436.74 443.241 443.241     447
Pier Skew, UpSta & Num, DnSta & Num=  ,10270, 6 ,10270, 6 , 5 , 5 , 0 ,,
       2       2   1.167   1.167       3       3
     420  437.73  437.73 443.091 443.091     447
       2       2   1.167   1.167       3       3
     420  437.73  437.73 443.091 443.091     447
Pier Skew, UpSta & Num, DnSta & Num=  ,10312, 6 ,10312, 6 , 5 , 5 , 0 ,,
       2       2   1.167   1.167       3       3
     420  438.66  438.66 442.942 442.942     447
       2       2   1.167   1.167       3       3
     420  438.66  438.66 442.942 442.942     447
Pier Skew, UpSta & Num, DnSta & Num=  ,10352, 6 ,10352, 6 , 5 , 5 , 0 ,,
       2       2   1.167   1.167       3       3
     420  438.58  438.58 442.792 442.792     447
       2       2   1.167   1.167       3       3
     420  438.58  438.58 442.792 442.792     447
Pier Skew, UpSta & Num, DnSta & Num=  ,10396, 6 ,10396, 6 , 5 , 5 , 0 ,,
       2       2   1.167   1.167       3       3
     420   437.5   437.5 442.642 442.642     447
       2       2   1.167   1.167       3       3
     420   437.5   437.5 442.642 442.642     447
Pier Skew, UpSta & Num, DnSta & Num=  ,10438, 6 ,10438, 6 , 5 , 5 , 0 ,,
       2       2   1.167   1.167       3       3
     420  437.35  437.35 442.493 442.493     447
       2       2   1.167   1.167       3       3
     420  437.35  437.35 442.493 442.493     447
Pier Skew, UpSta & Num, DnSta & Num=  ,10480, 6 ,10480, 6 , 5 , 5 , 0 ,,
       2       2   1.167   1.167       3       3
     420  438.27  438.27 442.343 442.343     447
       2       2   1.167   1.167       3       3
     420  438.27  438.27 442.343 442.343     447
Abutment Skew #Up #Dn= , 4 , 4
    4928 4935.75 4935.75 4959.75
     446     446   443.7   435.7
    4928 4935.75 4935.75 4959.75
     446     446   443.7   435.7
Abutment Skew #Up #Dn= , 4 , 4
 5293.25 5323.25 5323.25    5330
   433.8   443.8     446     446
 5293.25 5323.25 5323.25    5330
   433.8   443.8     446     446
Abutment Skew #Up #Dn= , 3 , 5
    7656  7660.5  7663.6
  444.61  444.36  431.29
    7620    7656  7660.5  7663.8  7664.8
  444.17  444.17  444.09  429.79  426.29
Abutment Skew #Up #Dn= , 4 , 5
  7894.5  7895.5  7896.5  7899.7
     433  438.03  444.42  444.53
  7894.6  7895.6  7896.5  7899.7    7964
   434.7   439.7  444.38  444.48  444.48
Abutment Skew #Up #Dn= , 4 , 5
    9513 9518.25 9518.25 9548.25
   447.8   447.8   445.9   435.9
    9460    9513 9518.25 9518.25 9548.25
   447.8   447.8   447.8   445.9   435.9
Abutment Skew #Up #Dn= , 4 , 4
10493.7510517.7510517.75   10540
  435.75  443.75   445.5   445.5
10493.7510517.7510517.75   10571
  435.75  443.75   445.5   445.5
BR Coef= 1 , 0 , 0 ,1.05, 0 ,,,0.8,-1,0.5,1,
WSPro=,,,, 1 ,,,, 0 ,,,, 0 ,,,,-1 ,-1 ,-1 , 0 , 0 , 0 , 0 , 0
BR U #Sta/Elev= 243
  1015.6   448.2    1016   445.7    1037   439.5  1054.5  437.17  1063.5  435.15
    1082   426.6    1096   424.9  1098.5   424.9  1107.5   424.9    1127   424.9
  1142.5   427.1  1151.5  427.29    1171   427.6    1190   430.5    1191   448.2
    1191     451    4930     451    4930   448.2 4930.89 440.055 4935.81 439.731
 4954.78  436.49  4963.5  436.01    4965  435.61    4971  433.61 4973.39  433.56
  4984.6  433.23 4995.45  432.93    4998  432.89 5006.56  432.83    5011  431.35
  5039.5  431.02  5075.5   430.6  5111.5   430.2 5116.93 430.097 5122.55 429.641
 5129.63 429.908 5133.65 430.107 5135.97  430.48 5139.11  430.75  5147.5  430.77
 5152.02  431.22 5168.59   431.9  5173.3 431.464 5177.27  431.17  5183.5  430.84
 5186.13 430.645 5200.58 430.934  5219.5  431.09 5221.63 431.046 5224.97 430.935
 5227.17 431.156 5231.32 431.669 5245.97 433.142 5249.52 433.148  5255.5   433.8
 5273.71  434.23  5291.5   434.8  5297.6  435.09 5318.03 435.872 5322.05 435.986
 5325.21 436.038 5327.49  443.69  5327.5  450.42    7566     451    7567     447
 7567.94 447.523  7581.6 447.539 7582.23 447.541 7586.28 447.393 7602.55 447.119
 7608.87 447.148 7611.57 447.038 7625.42 446.953 7629.12 446.892 7633.28 446.687
 7642.31 446.646 7648.27 446.917 7650.65 447.397 7651.03 445.966 7652.18 445.821
 7654.57 445.739 7654.83 446.275 7655.16 446.612 7656.25 446.567 7656.82 446.487
 7657.34 443.126 7657.76 444.387 7658.21 435.118 7660.61 433.495 7669.19 429.428
 7672.14 427.807 7676.86 423.918 7677.97 423.391 7678.29 423.105  7679.8 422.371
 7682.01 421.133 7683.96 419.975 7686.71 418.424 7687.43 418.074 7689.71  417.04
 7692.27 415.622 7693.12  415.39 7696.45 414.584 7697.37 413.884 7698.03 413.505
    7703   411.2    7708   408.4    7752   407.4    7775   409.3    7790   412.4
  7795.2 413.577 7798.15 414.135 7798.62 414.288 7799.24 414.597 7802.24 416.074
 7804.39 416.953 7811.12 420.398 7811.92 420.606 7820.09 423.483 7822.96 424.767
 7832.27 429.331  7833.3     430 7834.56  430.95 7838.43  431.53 7848.02  433.08
 7854.73  434.23 7861.47 435.503 7871.49  435.63 7872.89  435.65 7873.52  435.68
 7880.66 435.998 7883.47   436.2 7883.76 436.243 7892.34 437.207 7892.56 437.277
 7893.38 437.544 7897.84 438.951 7898.41 442.692  7898.8 443.661 7899.62 445.869
 7901.26 446.151 7902.35 446.497 7906.53 447.151 7906.93 447.798 7907.13  448.23
 7907.99 448.029 7909.82 447.959  7911.2 447.417 7915.76 447.514 7923.86   447.4
 7930.13 447.875 7940.53 447.951 7946.08 448.051 7961.94 448.136    7962     451
    9497     451    9497   448.2 9497.69  447.65 9503.88 447.355 9513.22 447.536
    9514 447.474  9514.3 447.069  9514.6 444.995 9515.59 444.505  9522.8 441.907
 9537.45 439.049 9548.52 437.755  9550.5 437.513 9573.09 436.797 9580.57  436.67
 9584.03 436.591 9605.49 436.244 9615.63 436.362 9619.53 436.371 9637.76 436.591
 9646.12 436.673  9679.1 436.761 9686.73 436.827    9694  436.24    9730  436.11
    9766  435.97 9786.69   435.9    9802  435.84    9838  435.71    9874  435.57
    9910  435.44 9916.03 435.543 9924.82 435.239 9930.34 435.134    9946  435.01
 9952.16 435.019 9964.54 435.031 9972.74  434.89 9979.36 434.998 9987.96 434.936
 9993.33 434.934 9999.57 434.88510004.46 434.96710009.59 434.998   10011 434.823
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BR U #Mann= 7
  1015.6    .072    7566    .055 7657.76     .04 7861.47    .055    9497    .075
 9786.69    .07510261.24    .075
BR U Banks=,7861.47
BR D #Sta/Elev= 230
  1015.6   448.2    1016   445.7    1037   439.5  1054.5  437.17  1063.5  435.15
    1082   426.6    1096   424.9  1098.5   424.9  1107.5   424.9    1127   424.9
  1142.5   427.1  1151.5  427.29    1171   427.6    1190   430.5    1191   448.2
    1191     451    4928     451 4928.01   448.2 4928.87 447.315 4932.69 443.922
 4933.41   442.9 4933.69 441.928 4941.46   440.5 4943.02     440 4948.81     438
 4954.78  436.49  4955.5  435.86  4966.5  435.64  4967.5  435.62  4970.2  435.57
  4977.1  433.27 4979.37  433.24 4989.54  433.01 4999.67  432.81 5001.67  432.77
 5006.85  432.69    5011  431.29  5039.5  430.98  5075.5  430.59  5111.5  430.23
 5114.87 430.172  5124.9 429.538 5127.86 429.411 5128.48 429.484  5138.6 430.481
  5147.5  430.82 5154.51  431.01 5168.85 431.222 5186.18  431.24 5196.77 431.057
 5200.51 431.027 5216.28 432.214 5235.22 433.206  5241.2  433.51  5255.5  433.81
  5291.5  434.79 5302.73  435.21 5303.03  435.31 5311.03   437.7 5312.33   438.1
 5316.05   438.6 5323.42 441.365 5324.81 442.276 5326.85  443.66 5327.49  443.69
  5327.5  450.42    7566     451    7567     447 7567.96 442.503 7574.74 442.437
 7581.58 442.264 7596.12 442.165 7604.14 441.848  7606.9 442.031 7625.67 441.741
 7627.83 441.692 7644.12 438.821 7645.81 438.698 7646.54 438.145  7649.7 436.093
 7665.58 427.395 7669.53 426.421 7673.46 425.623 7675.42 424.953 7678.06 424.327
 7682.06 423.445 7690.31 421.169 7693.72 420.063 7695.73 419.491  7698.8 418.547
 7703.82 417.164 7710.74 414.784 7711.99 414.323 7712.87 414.065 7713.72 413.732
    7720   411.2    7726   408.4    7758   407.4    7787   409.3    7798   412.4
 7801.02 413.766 7801.95 414.426 7803.22 414.936 7810.84 419.308  7814.4 419.852
 7820.02 420.851 7821.12  421.46 7827.31 424.705 7829.31  425.79 7829.84 426.197
  7833.9     430 7835.95  432.04 7839.86  432.73 7846.01  434.13 7857.61  436.33
  7876.9  436.17 7886.24 436.806  7897.3 437.103 7904.52 438.428 7910.18 438.966
 7927.49 439.174 7935.01 440.183 7939.65 440.213 7942.19 440.376 7958.75 440.387
 7961.96 440.328    7962     451    9463     451 9463.62 440.342 9476.81 440.065
 9479.04 440.099 9490.07  440.33 9504.79 440.548 9511.66 440.512 9528.17 439.927
 9532.35 439.494  9543.7 438.895  9547.1 438.435  9551.5   436.7 9557.94 437.668
 9572.01 437.294 9579.77 437.293 9582.01 437.227 9585.78 437.074 9592.73 436.929
 9594.94 436.934 9609.67 436.894 9615.95 436.912 9623.22 436.888 9631.08 437.023
 9634.22 437.041  9642.3 437.185 9662.65 437.341 9672.07 437.609 9682.26   437.2
 9692.05  436.91    9694  436.24    9730   436.1    9766  435.97    9802  435.85
    9838  435.72    9874  435.59    9910  435.47 9914.16 435.121  9916.9 435.032
 9919.06 435.019 9936.71 434.718 9939.43 434.714    9946   434.9 9952.42 434.996
 9962.38 434.996 9971.66 435.385 9982.56 435.195 9986.53 435.41410001.97 435.268
10012.93 435.304   10018  435.2610022.75 435.464   10054  435.1510065.48 435.612
10074.05 434.817 10082.7 434.817 10089.2 435.56410096.52 435.55910101.33 435.584
10105.51 435.534 10119.3 435.57910124.05  435.6210128.43 435.397 10136.6 435.413
10141.13  435.46   10162  435.08   10198  434.84   10234  435.38   10270  435.29
 10274.5  435.45   10306  435.58   10342  435.7110343.75 437.28610349.97 437.347
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BR D #Mann= 7
  1015.6    .071    7566    .055  7649.7     .04 7857.61    .055    9463     .07
    9802    .075   10270     .07
BC Design=,, 0 ,, 0 ,,,,,,
BC Use User HTab Curves=0
BC User HTab FreeFlow(D)= 0