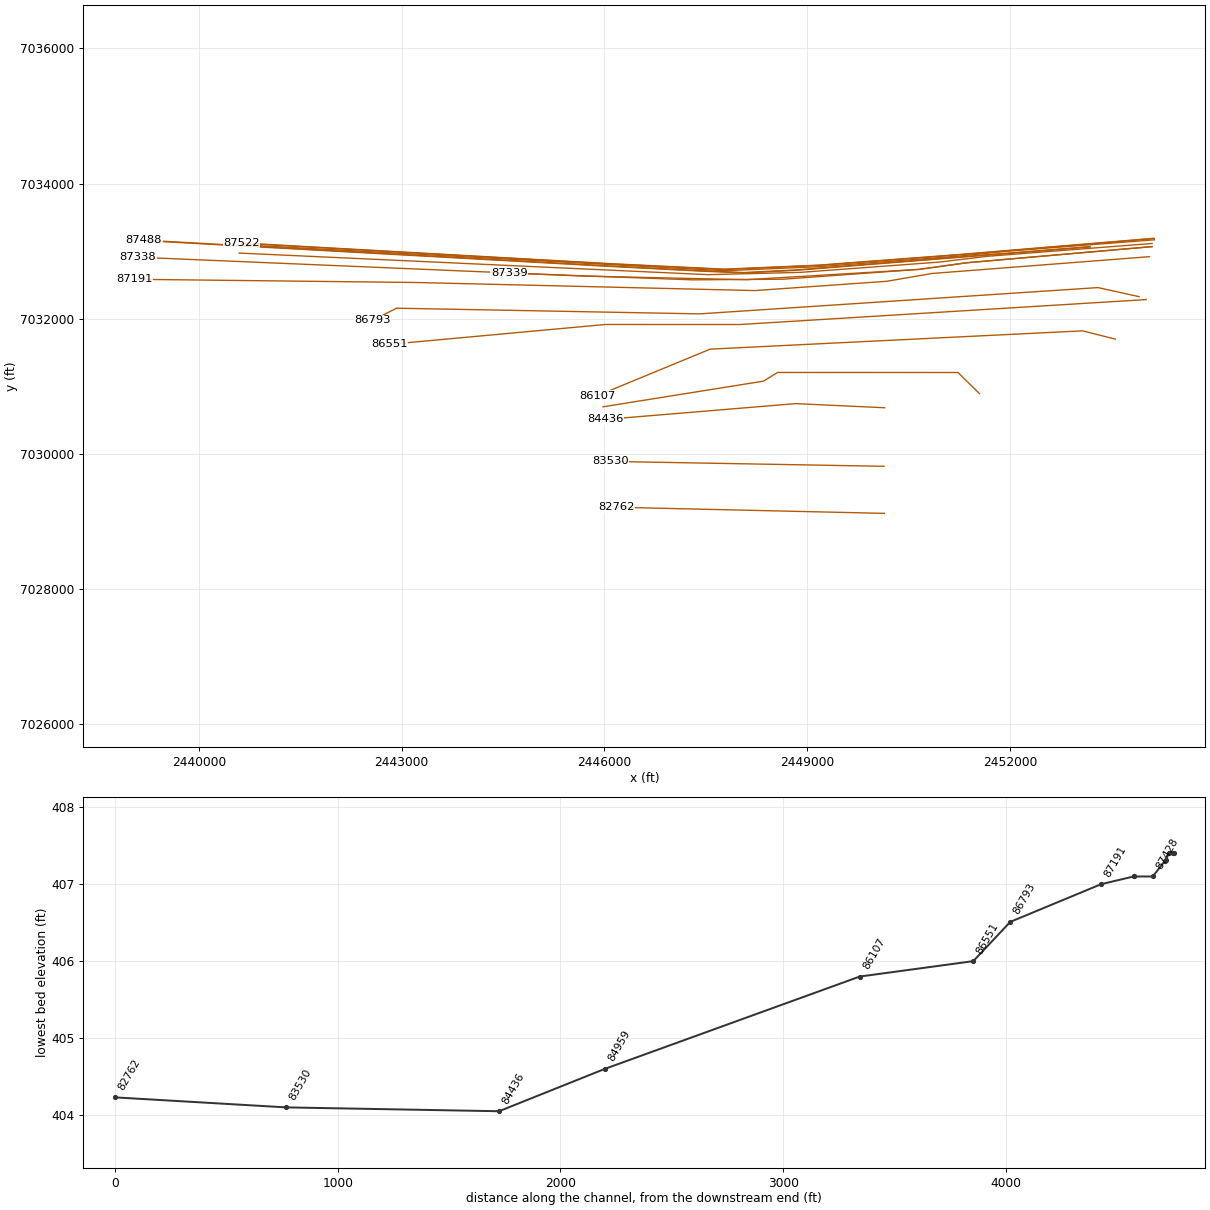
HEC-RAS study CDC_Consolidated_Model.prj: Upper Trinity CDC Consolidated Model

--- CDC_Consolidated_Model.g13 (geometry) --- (continued)

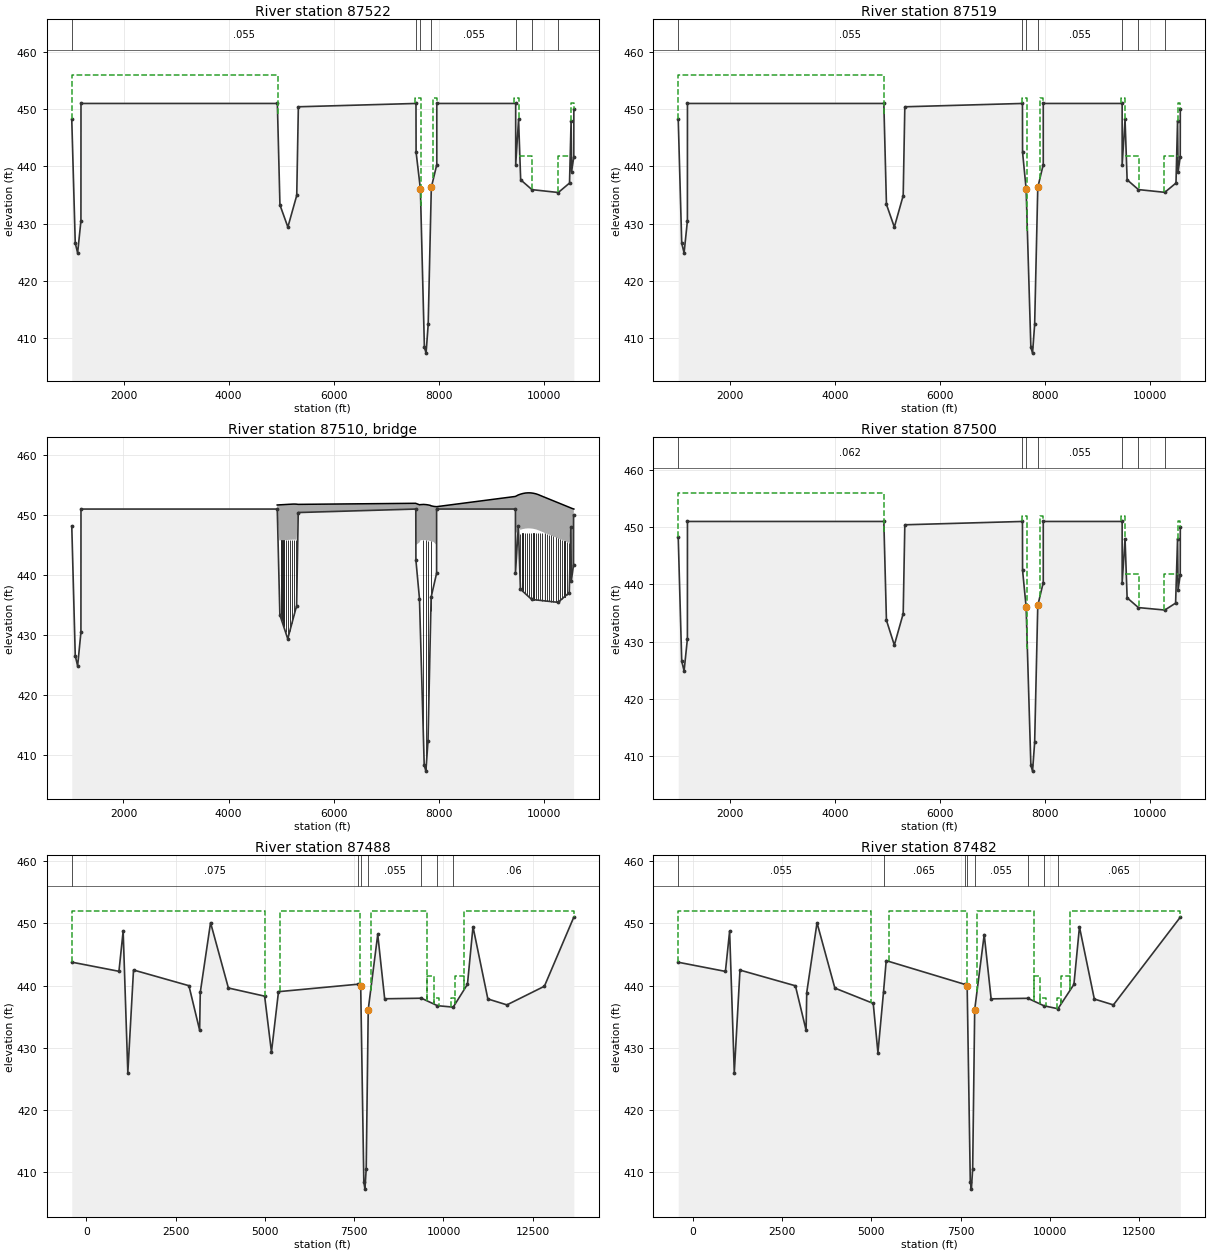
Type RM Length L Ch R = 1 ,87522   ,3,3,3
BEGIN DESCRIPTION:
Downstream of Cotton Belt Regional Rail
H&B Trail added to Staion 5060 to 5074
---------------------------------------------------------------------
CDC CAR102120-01 Cotton Belt Regional Rail
---------------------------------------------------------------------
END DESCRIPTION:
XS GIS Cut Line= 6
2454120.089167517033189.222747132451256.687085937032950.51850013
2449170.19257125 7032792.92695182447774.69765884 7032732.9585678
2446114.146846097032813.27960138 2440630.59999147033120.73640699
#Sta/Elev= 30
  1015.6   448.2    1082   426.6    1127   424.9    1190   430.5    1191     451
    4928     451  4977.1  433.28 5127.86  429.41 5296.67  434.94  5327.5  450.42
    7566     451 7567.96   442.5  7649.7  436.09    7726   408.4    7758   407.4
    7798   412.4 7857.61  436.33 7961.96  440.33    7962     451    9463     451
 9463.62  440.34 9518.24   448.2 9557.94  437.67 9772.45  435.95 10274.5  435.45
10487.76   437.110517.76     44810527.34  439.0910568.62  441.68   10570     450
#Mann= 7 ,-1,0
  1015.6    .055       0    7566    .055       0  7649.7     .05       0
 7857.61    .055       0    9463     .06       0 9772.45    .055       0
 10274.5     .06       0
#XS Ineff= 9 ,-1
  1015.6 4933.66     456 4933.66    7550     439    7550    7658     452
    7899    7965     452    7965    9440   435.8    9440 9518.24     452
 9518.24    9778   441.9   1026810517.76   441.910517.76   10570     451
Permanent Ineff=
       F       F       F       F       F       T       T       T       T
Bank Sta=7649.7,7857.61
XS Rating Curve= 0 ,0
Exp/Cntr=0.5,0.3

Type RM Length L Ch R = 1 ,87519   ,19,19,22
BEGIN DESCRIPTION:
H&B Trail added to Staion 5060 to 5074
END DESCRIPTION:
XS GIS Cut Line= 6
  2454132.526349 7033186.3697901 2451253.6809513 7032946.3307402
 2449167.5349776 7032788.7966183 2447772.1138286 7032729.0936998
 2446111.7577053 7032809.2905406 2440627.0446559 7033116.3156248
#Sta/Elev= 30
  1015.6   448.2    1082   426.6    1127   424.9    1190   430.5    1191     451
    4928     451  4977.9  433.37 5127.86  429.41 5296.59  434.91  5327.5  450.42
    7566     451 7567.96   442.5  7635.7  436.09    7726   408.4    7758   407.4
    7798   412.4 7857.61  436.33 7961.96  440.33    7962     451    9463     451
 9463.62  440.34 9518.24   448.2 9557.94  437.67 9772.45  435.96 10274.5  435.48
10487.76   437.110517.76     44810527.34  439.0910568.62  441.68   10570     450
#Mann= 7 ,-1,0
  1015.6    .055       0    7566    .055       0  7635.7     .05       0
 7857.61    .055       0    9463     .06       0 9772.45    .055       0
 10274.5     .06       0
#XS Ineff= 9 ,-1
  1015.6 4933.66     456 4933.66    7550     439    7550 7659.66     452
 7897.34    7965     452    7965    9440   435.8    9440 9518.24     452
 9518.24    9778   441.9   1026810517.76   441.910517.76   10570     451
Permanent Ineff=
       F       F       F       F       F       T       T       T       T
Bank Sta=7635.7,7857.61
XS Rating Curve= 0 ,0
Exp/Cntr=0.5,0.3

Type RM Length L Ch R = 3 ,87510   ,,,
BEGIN DESCRIPTION:
Cotton Belt Regional Rail
END DESCRIPTION:
Bridge Culvert--1,0,-1,-1, 0
Deck Dist Width WeirC Skew NumUp NumDn MinLoCord MaxHiCord MaxSubmerge Is_Ogee
2.5,14,2.6,0, 63, 63, , , 0.95, 0, ,,,
    4927 4931.49  4931.5  4967.5  5007.5  5047.5  5087.5  5127.5  5167.5  5207.5
  5216.5  5241.5  5247.5    5250  5287.5  5327.5 5327.51    7562 7562.01    7637
    7656    7662    7705    7712    7754    7762    7803    7812    7847    7852
    7901    7909    7963 7963.01    9462 9462.01    9514    9556    9605    9640
    9655    9705  9715.8    9755    9805    9855    9905    9910    9934    9976
   10018   10060   10102   10144   10186   10228   10270   10354   10438   10522
   10533   1057510575.01
  451.68  451.68  451.68 451.698 451.718 451.738 451.758 451.778 451.798 451.818
  451.82  451.83  451.83  451.83  451.82  451.78  451.78  451.96  451.96  451.71
  451.74  451.74 451.766  451.77 451.745  451.74 451.683  451.67   451.6 451.548
  451.46  451.44   451.4   451.4   453.1   453.1 453.336  453.47  453.59 453.646
  453.67   453.7   453.7  453.69  453.63  453.53  453.38  453.36 453.267 453.118
 452.968 452.819 452.669 452.519  452.37  452.22 452.071 451.771 451.472 451.173
  451.13     451     451
                 445.763 445.781 445.801 445.821 445.841 445.861 445.881 445.901
 445.903 445.913 445.913 445.913 445.903 445.863                 444.957 445.457
 445.823 445.823 445.849 445.853 445.828 445.823 445.766 445.753 445.683 445.631
 445.543 445.492 444.992                 446.795 447.419 447.553 447.673 447.729
 447.753 447.783 447.783 447.773 447.713 447.613 447.463 447.443  447.35 447.201
 447.051 446.902 446.752 446.602 446.453 446.303 446.154 445.854 445.555 445.261
  445.22
    4927 4931.49  4931.5  4967.5  5007.5  5047.5  5087.5  5127.5  5167.5  5207.5
  5216.5  5241.5  5247.5    5250  5287.5  5327.5  5327.5    7562 7562.01    7637
    7656    7662    7705    7712    7754    7762    7803    7812    7847    7852
    7901    7907    7963 7963.01    9462 9462.01    9514    9556    9605    9640
    9655    9705  9715.8    9755    9805    9855    9905    9910    9934    9976
   10018   10060   10102   10144   10186   10228   10270   10354   10438   10522
   10533   1057510575.01
  451.68  451.68  451.68 451.698 451.718 451.738 451.758 451.778 451.798 451.818
  451.82  451.83  451.83  451.83  451.82  451.78  451.78  451.96  451.96  451.71
  451.74  451.74 451.766  451.77 451.745  451.74 451.683  451.67   451.6 451.548
  451.46  451.44   451.4   451.4   453.1   453.1 453.336  453.47  453.59 453.646
  453.67   453.7   453.7  453.69  453.63  453.53  453.38  453.36 453.267 453.118
 452.968 452.819 452.669 452.519  452.37  452.22 452.071 451.771 451.472 451.173
  451.13     451     451
                 445.763 445.781 445.801 445.821 445.841 445.861 445.881 445.901
 445.903 445.913 445.913 445.913 445.903 445.863                 444.957 445.457
 445.823 445.823 445.849 445.853 445.828 445.823 445.766 445.753 445.683 445.631
 445.543 445.492 444.992                 446.795 447.419 447.553 447.673 447.729
 447.753 447.783 447.783 447.773 447.713 447.613 447.463 447.443  447.35 447.201
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Pier Skew, UpSta & Num, DnSta & Num=  ,4967.5, 6 ,4967.5, 6 , 5 , 5 , 0 ,,
       2       2   1.167   1.167       3       3
     420 437.719 437.719 442.719 442.719     447
       2       2   1.167   1.167       3       3
     420 437.719 437.719 442.719 442.719     447
Pier Skew, UpSta & Num, DnSta & Num=  ,5007.5, 6 ,5007.5, 6 , 5 , 5 , 0 ,,
       2       2   1.167   1.167       3       3
     420 433.739 433.739 442.739 442.739     447
       2       2   1.167   1.167       3       3
     420 433.739 433.739 442.739 442.739     447
Pier Skew, UpSta & Num, DnSta & Num=  ,5047.5, 6 ,5047.5, 6 , 5 , 5 , 0 ,,
       2       2   1.167   1.167       3       3
     420  431.97  431.97 442.759 442.759     447
       2       2   1.167   1.167       3       3
     420  431.97  431.97 442.759 442.759     447
Pier Skew, UpSta & Num, DnSta & Num=  ,5087.5, 6 ,5087.5, 6 , 5 , 5 , 0 ,,
       2       2   1.167   1.167       3       3
     420  431.58  431.58 442.779 442.779     447
       2       2   1.167   1.167       3       3
     420  431.58  431.58 442.779 442.779     447
Pier Skew, UpSta & Num, DnSta & Num=  ,5127.5, 6 ,5127.5, 6 , 5 , 5 , 0 ,,
       2       2   1.167   1.167       3       3
     420  430.75  430.75 442.799 442.799     447
       2       2   1.167   1.167       3       3
     420  430.75  430.75 442.799 442.799     447
Pier Skew, UpSta & Num, DnSta & Num=  ,5167.5, 6 ,5167.5, 6 , 5 , 5 , 0 ,,
       2       2   1.167   1.167       3       3
     420  432.36  432.36 442.819 442.819     447
       2       2   1.167   1.167       3       3
     420  432.36  432.36 442.819 442.819     447
Pier Skew, UpSta & Num, DnSta & Num=  ,5207.5, 6 ,5207.5, 6 , 5 , 5 , 0 ,,
       2       2   1.167   1.167       3       3
     420  432.88  432.88 442.839 442.839     447
       2       2   1.167   1.167       3       3
     420  432.88  432.88 442.839 442.839     447
Pier Skew, UpSta & Num, DnSta & Num=  ,5247.5, 6 ,5247.5, 6 , 5 , 5 , 0 ,,
       2       2   1.167   1.167       3       3
     420 434.851 434.851 442.851 442.851     447
       2       2   1.167   1.167       3       3
     420 434.851 434.851 442.851 442.851     447
Pier Skew, UpSta & Num, DnSta & Num=  ,5287.5, 6 ,5287.5, 6 , 5 , 5 , 0 ,,
       2       2   1.167   1.167       3       3
     420 435.841 435.841 442.841 442.841     447
       2       2   1.167   1.167       3       3
     420 435.841 435.841 442.841 442.841     447
Pier Skew, UpSta & Num, DnSta & Num=  ,7705, 4 ,7705, 4 , 3 , 3 , 0 ,,
       4       4     4.5     4.5
     420 442.787 442.787     450
       4       4     4.5     4.5
     420 442.787 442.787     450
Pier Skew, UpSta & Num, DnSta & Num=  ,7754, 4 ,7754, 4 , 3 , 3 , 0 ,,
       4       4     4.5     4.5
     420 442.766 442.766     450
       4       4     4.5     4.5
     420 442.766 442.766     450
Pier Skew, UpSta & Num, DnSta & Num=  ,7803, 4 ,7803, 4 , 3 , 3 , 0 ,,
       4       4     4.5     4.5
     420 442.704 442.704     450
       4       4     4.5     4.5
     420 442.704 442.704     450
Pier Skew, UpSta & Num, DnSta & Num=  ,7852, 4 ,7852, 4 , 3 , 3 , 0 ,,
       4       4     4.5     4.5
     420 442.569 442.569     450
       4       4     4.5     4.5
     420 442.569 442.569     450
Pier Skew, UpSta & Num, DnSta & Num=  ,9556, 6 ,9556, 6 , 5 , 5 , 0 ,,
       2       2   1.167   1.167       3       3
     420  440.62  440.62 444.491 444.491 446.849
       2       2   1.167   1.167       3       3
     420  440.62  440.62 444.491 444.491 446.849
Pier Skew, UpSta & Num, DnSta & Num=  ,9598, 6 ,9598, 6 , 5 , 5 , 0 ,,
       2       2   1.167   1.167       3       3
     420  438.67  438.67 444.594 444.594     447
       2       2   1.167   1.167       3       3
     420  438.67  438.67 444.594 444.594     447
Pier Skew, UpSta & Num, DnSta & Num=  ,9640, 6 ,9640, 6 , 5 , 5 , 0 ,,
       2       2   1.167   1.167       3       3
     420  437.73  437.73 444.667 444.667     447
       2       2   1.167   1.167       3       3
     420  437.73  437.73 444.667 444.667     447
Pier Skew, UpSta & Num, DnSta & Num=  ,9682, 6 ,9682, 6 , 5 , 5 , 0 ,,
       2       2   1.167   1.167       3       3
     420  438.78  438.78 444.711 444.711     447
       2       2   1.167   1.167       3       3
     420  438.78  438.78 444.711 444.711     447
Pier Skew, UpSta & Num, DnSta & Num=  ,9724, 6 ,9724, 6 , 5 , 5 , 0 ,,
       2       2   1.167   1.167       3       3
     420  438.89  438.89 444.721 444.721     447
       2       2   1.167   1.167       3       3
     420  438.89  438.89 444.721 444.721     447
Pier Skew, UpSta & Num, DnSta & Num=  ,9766, 6 ,9766, 6 , 5 , 5 , 0 ,,
       2       2   1.167   1.167       3       3
     420  438.94  438.94 444.698 444.698     447
       2       2   1.167   1.167       3       3
     420  438.94  438.94 444.698 444.698     447
Pier Skew, UpSta & Num, DnSta & Num=  ,9808, 6 ,9808, 6 , 5 , 5 , 0 ,,
       2       2   1.167   1.167       3       3
     420  436.99  436.99 444.641 444.641     447
       2       2   1.167   1.167       3       3
     420  436.99  436.99 444.641 444.641     447
Pier Skew, UpSta & Num, DnSta & Num=  ,9850, 6 ,9850, 6 , 5 , 5 , 0 ,,
       2       2   1.167   1.167       3       3
     420  437.05  437.05 444.561 444.561     447
       2       2   1.167   1.167       3       3
     420  437.05  437.05 444.561 444.561     447
Pier Skew, UpSta & Num, DnSta & Num=  ,9892, 6 ,9892, 6 , 5 , 5 , 0 ,,
       2       2   1.167   1.167       3       3
     420   437.1   437.1 444.441 444.441     447
       2       2   1.167   1.167       3       3
     420   437.1   437.1 444.441 444.441     447
Pier Skew, UpSta & Num, DnSta & Num=  ,9934, 6 ,9934, 6 , 5 , 5 , 0 ,,
       2       2   1.167   1.167       3       3
     420  436.29  436.29 444.288 444.288     447
       2       2   1.167   1.167       3       3
     420  436.29  436.29 444.288 444.288     447
Pier Skew, UpSta & Num, DnSta & Num=  ,9976, 6 ,9976, 6 , 5 , 5 , 0 ,,
       2       2   1.167   1.167       3       3
     420  436.64  436.64 444.138 444.138     447
       2       2   1.167   1.167       3       3
     420  436.64  436.64 444.138 444.138     447
Pier Skew, UpSta & Num, DnSta & Num=  ,10018, 6 ,10018, 6 , 5 , 5 , 0 ,,
       2       2   1.167   1.167       3       3
     420  436.49  436.49 443.989 443.989     447
       2       2   1.167   1.167       3       3
     420  436.49  436.49 443.989 443.989     447
Pier Skew, UpSta & Num, DnSta & Num=  ,10060, 6 ,10060, 6 , 5 , 5 , 0 ,,
       2       2   1.167   1.167       3       3
     420  436.84  436.84 443.839 443.839     447
       2       2   1.167   1.167       3       3
     420  436.84  436.84 443.839 443.839     447
Pier Skew, UpSta & Num, DnSta & Num=  ,10102, 6 ,10102, 6 , 5 , 5 , 0 ,,
       2       2   1.167   1.167       3       3
     420  436.09  436.09  443.69  443.69     447
       2       2   1.167   1.167       3       3
     420  436.09  436.09  443.69  443.69     447
Pier Skew, UpSta & Num, DnSta & Num=  ,10144, 6 ,10144, 6 , 5 , 5 , 0 ,,
       2       2   1.167   1.167       3       3
     420  436.04  436.04  443.54  443.54     447
       2       2   1.167   1.167       3       3
     420  436.04  436.04  443.54  443.54     447
Pier Skew, UpSta & Num, DnSta & Num=  ,10186, 6 ,10186, 6 , 5 , 5 , 0 ,,
       2       2   1.167   1.167       3       3
     420  436.89  436.89  443.39  443.39     447
       2       2   1.167   1.167       3       3
     420  436.89  436.89  443.39  443.39     447
Pier Skew, UpSta & Num, DnSta & Num=  ,10228, 6 ,10228, 6 , 5 , 5 , 0 ,,
       2       2   1.167   1.167       3       3
     420  436.81  436.81 443.241 443.241     447
       2       2   1.167   1.167       3       3
     420  436.81  436.81 443.241 443.241     447
Pier Skew, UpSta & Num, DnSta & Num=  ,10270, 6 ,10270, 6 , 5 , 5 , 0 ,,
       2       2   1.167   1.167       3       3
     420  437.73  437.73 443.091 443.091     447
       2       2   1.167   1.167       3       3
     420  437.73  437.73 443.091 443.091     447
Pier Skew, UpSta & Num, DnSta & Num=  ,10312, 6 ,10312, 6 , 5 , 5 , 0 ,,
       2       2   1.167   1.167       3       3
     420  438.66  438.66 442.942 442.942     447
       2       2   1.167   1.167       3       3
     420  438.66  438.66 442.942 442.942     447
Pier Skew, UpSta & Num, DnSta & Num=  ,10352, 6 ,10352, 6 , 5 , 5 , 0 ,,
       2       2   1.167   1.167       3       3
     420  438.58  438.58 442.792 442.792     447
       2       2   1.167   1.167       3       3
     420  438.58  438.58 442.792 442.792     447
Pier Skew, UpSta & Num, DnSta & Num=  ,10396, 6 ,10396, 6 , 5 , 5 , 0 ,,
       2       2   1.167   1.167       3       3
     420   437.5   437.5 442.642 442.642     447
       2       2   1.167   1.167       3       3
     420   437.5   437.5 442.642 442.642     447
Pier Skew, UpSta & Num, DnSta & Num=  ,10438, 6 ,10438, 6 , 5 , 5 , 0 ,,
       2       2   1.167   1.167       3       3
     420  437.35  437.35 442.493 442.493     447
       2       2   1.167   1.167       3       3
     420  437.35  437.35 442.493 442.493     447
Pier Skew, UpSta & Num, DnSta & Num=  ,10480, 6 ,10480, 6 , 5 , 5 , 0 ,,
       2       2   1.167   1.167       3       3
     420  438.27  438.27 442.343 442.343     447
       2       2   1.167   1.167       3       3
     420  438.27  438.27 442.343 442.343     447
Abutment Skew #Up #Dn= , 4 , 4
    4928 4935.75 4935.75 4959.75
     446     446   443.7   435.7
    4928 4935.75 4935.75 4959.75
     446     446   443.7   435.7
Abutment Skew #Up #Dn= , 5 , 4
 5293.25 5323.25 5323.25    5330 5330.01
   433.8   443.8     446     446  450.42
 5293.25 5323.25 5323.25    5330
   433.8   443.8     446     446
Abutment Skew #Up #Dn= , 4 , 4
    7566    76127659.6667659.666
   446.3   446.3   446.3  428.34
    7566    76127659.6667659.666
   446.3   446.3   446.3  428.34
Abutment Skew #Up #Dn= , 4 , 4
 7874.837897.3337897.333    7963
  435.19  438.95  446.17  446.17
 7874.837897.3337897.333    7963
  435.19  438.95  446.17  446.17
Abutment Skew #Up #Dn= , 4 , 4
    9462 9518.25 9518.25 9548.25
   447.8   447.8   445.9   435.9
    9462 9518.25 9518.25 9548.25
   447.8   447.8   445.9   435.9
Abutment Skew #Up #Dn= , 4 , 4
10499.7510517.7510517.75   10571
  437.75  443.75   445.5   445.5
10499.7510517.7510517.75   10571
  437.75  443.75   445.5   445.5
BR Coef= 1 , 0 , 0 ,1.05, 0 ,,,0.8,-1,0.5,1,
WSPro=,,,, 1 ,,,, 0 ,,,, 0 ,,,,-1 ,-1 ,-1 , 0 , 0 , 0 , 0 , 0
BR U #Sta/Elev= 221
  1015.6   448.2    1016   445.7    1037   439.5  1054.5  437.17  1063.5  435.15
    1082   426.6    1096   424.9  1098.5   424.9  1107.5   424.9    1127   424.9
  1142.5   427.1  1151.5  427.29    1171   427.6    1190   430.5    1191   448.2
    1191     451    4928     451 4928.01   448.2 4928.87 447.315 4933.69     442
 4941.46     440 4943.02   439.5  4952.5   436.9  4955.5  436.84  4967.5   436.6
  4968.3  436.57  4977.9  433.37 4980.03  433.32  4990.1  433.04 5000.15  432.86
  5002.3  432.82  5006.5   432.8    5011   431.3  5039.5  430.96  5075.5  430.58
  5111.5  430.22 5114.87 430.172  5124.9 429.538 5127.86 429.411 5128.48 429.484
  5138.6 430.481  5147.5  430.82 5154.51  431.01 5168.85 431.222  5183.5  430.93
 5186.18  431.24 5196.77 431.057 5200.51 431.027 5216.28 432.214 5235.22 433.206
  5241.2  433.52  5255.5  433.82  5291.5  434.78 5303.69   435.1  5305.1  435.57
 5312.83   438.1 5316.05     439 5323.42     441 5325.31     442 5327.49  443.69
  5327.5  450.42    7566     451    7567     447 7567.96 442.503 7574.74 442.437
 7581.58 442.264 7596.12 442.165 7604.14 441.848  7606.9 442.031 7615.67 441.741
 7617.83 441.692 7626.12 438.821  7635.7 436.093 7665.58 427.395 7669.53 426.421
 7673.46 425.623 7675.42 424.953 7678.06 424.327 7682.06 423.445 7690.31 421.169
 7693.72 420.063 7695.73 419.491  7698.8 418.547 7703.82 417.164 7710.74 414.784
 7711.99 414.323 7712.87 414.065 7713.72 413.732    7720   411.2    7726   408.4
    7758   407.4    7787   409.3    7798   412.4 7801.02 413.766 7801.95 414.426
 7803.22 414.936 7810.84 419.308  7814.4 419.852 7820.02 420.851 7821.12  421.46
 7827.31 424.705 7829.31  425.79 7829.84 426.197  7833.4   429.6 7835.95  432.04
 7839.86  432.73 7846.01  434.13 7857.61  436.33  7876.9 436.175 7886.24 436.806
  7897.3 437.103 7904.52 438.428 7910.18 438.966 7927.49 439.174 7935.01 440.183
 7939.65 440.213 7942.19 440.376 7958.75 440.387 7961.96 440.328    7962     451
    9463     451 9463.62 440.342 9476.81 440.065 9479.04 440.099 9490.07  440.33
 9504.79 440.548 9511.66 440.512 9528.17 439.927 9532.35 439.494  9543.7 438.895
  9547.1 438.435 9549.55 438.174 9557.94 437.668 9572.01 437.294 9579.77 437.293
 9582.01 437.227 9585.78 437.074 9592.73 436.929 9594.94 436.934 9609.67 436.894
 9615.95 436.912 9623.22 436.888 9631.08 437.023 9634.22 437.041  9642.3 437.185
 9662.65 437.341 9672.07 437.609 9682.26   437.2 9692.05  436.91    9694  436.23
    9730   436.1    9766  435.98    9802  435.85    9838  435.73    9874  435.61
    9910  435.48 9914.16 435.121  9916.9 435.032 9919.06 435.019 9936.71 434.718
 9939.43 434.714 9952.42 434.996 9962.38 434.996 9971.66 435.385    9982  435.68
 9986.53 435.41410001.97 435.26810012.93 435.304   10018  435.2410022.75  435.46
   10054  435.1510065.48  435.6110074.05 434.817 10082.7 434.817 10089.2  435.56
10096.52  435.5610101.33  435.5810105.51  435.53 10119.3  435.5810124.05  435.62
10128.43   435.4 10136.6  435.4110141.13  435.46   10162  435.08   10198  435.55
   10234  435.99   10270  435.46 10274.5  435.48   10306   435.6   10342  435.72
10349.97 437.34710353.78 437.19810359.38 437.11210363.63 436.98410372.68 436.497
10383.86 436.388 10394.9 435.98410408.99 435.633 10412.8 435.50910423.46 435.314
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BR U #Mann= 7
  1015.6    .065  7635.7    .047 7857.61     .05 7961.96    .055    9463     .07
    9766     .06   10270    .065
BR U Banks=7635.7,7857.61
BR D #Sta/Elev= 212
  1015.6   448.2    1016   445.7    1037   439.5  1054.5  437.17  1063.5  435.15
    1082   426.6    1096   424.9  1098.5   424.9  1107.5   424.9    1127   424.9
  1142.5   427.1  1151.5  427.29    1171   427.6    1190   430.5    1191   448.2
    1191     451    4928     451 4928.01   448.2 4928.87 447.315 4933.69     442
 4941.46 439.939 4943.02 439.238  4953.5  436.81  4955.5  436.77  4967.5  436.53
 4969.42   436.5  4977.7  433.74 4979.84  433.69 4989.85  433.43 4999.94  433.18
  5002.1  433.13 5005.45  433.05    5011 431.205  5039.5  430.92  5075.5  430.56
  5111.5  430.29 5114.87 430.172  5124.9 429.538 5127.86 429.411 5128.48 429.484
  5138.6 430.481  5147.5  430.85 5154.51  431.01 5168.85 431.222  5183.5  431.14
 5186.18  431.24 5196.77 431.057 5200.51 431.027 5216.28 432.214 5235.22 433.206
  5241.2  433.53  5255.5  433.83  5291.5  434.76 5303.39   435.1 5304.68  435.53
 5312.83   438.1 5316.05     439 5323.42     441 5325.31     442 5327.49  443.69
  5327.5  450.42    7566     451    7567     447 7567.96 442.503 7574.74 442.437
 7581.58 442.264 7596.12 442.165 7604.14 441.848  7606.9 442.031 7615.67 441.741
 7617.83 441.692 7628.12 438.145  7635.7 436.093 7665.58 427.395 7669.53 426.421
 7673.46 425.623 7675.42 424.953 7678.06 424.327 7682.06 423.445 7690.31 421.169
 7693.72 420.063 7695.73 419.491  7698.8 418.547 7703.82 417.164 7710.74 414.784
 7711.99 414.323 7712.87 414.065 7713.72 413.732    7720   411.2    7726   408.4
    7758   407.4    7787   409.3    7798   412.4 7801.02 413.766 7801.95 414.426
 7803.22 414.936 7810.84 419.308  7814.4 419.852 7820.02 420.851 7821.12  421.46
 7827.31 424.705 7829.31  425.79 7829.84 426.197  7833.4   429.6 7835.95  432.04
 7839.86  432.73 7846.01 434.125 7857.61 436.332  7876.9 436.175 7886.24 436.806
  7897.3 437.103 7904.52 438.428 7910.18 438.966 7927.49 439.174 7935.01 440.183
 7939.65 440.213 7942.19 440.376 7958.75 440.387 7961.96 440.328    7962     451
    9463     451 9463.62 440.342 9476.81 440.065 9479.04 440.099 9490.07  440.33
 9504.79 440.548 9511.66 440.512 9528.17 439.927 9532.35 439.494  9543.7 438.895
  9547.1 438.435 9549.55 438.174 9557.94 437.668 9572.01 437.294 9579.77 437.293
 9582.01 437.227 9585.78 437.074 9592.73 436.929 9594.94 436.934 9609.67 436.894
 9615.95 436.912 9623.22 436.888 9631.08 437.023 9634.22 437.041  9642.3 437.185
 9662.65 437.341 9672.07 437.609 9682.26   437.2 9692.05  436.91    9694  436.22
    9730   436.1    9766  435.98    9802  435.86    9838  435.74    9874  435.62
    9910  435.51 9914.16 435.121  9916.9 435.032 9919.06 435.019 9936.71 434.718
 9939.43 434.714 9952.42 434.996 9962.38 434.996 9971.66 435.385 9982.56 435.195
 9986.53 435.41410001.97 435.26810012.93 435.304   10054  435.0310071.55  435.05
10074.05 434.817 10082.7 434.81710084.72  435.05   10090  435.06   10126  435.03
   10162  435.15   10198  435.27   10234  435.39   10270  435.51   10306  435.63
   10342  435.7510349.97 437.34710353.78 437.19810359.38 437.11210363.63 436.984
10372.68 436.49710383.86 436.388 10394.9 435.98410408.99 435.633 10412.8 435.509
10423.46 435.31410433.91 435.397 10444.1 435.48310453.61  435.8110463.72 436.052
10480.42 436.73610487.76 437.10410491.02 437.58810493.38 437.81110503.13 438.422
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BR D #Mann= 7
  1015.6    .065  7635.7    .047 7857.61     .05 7961.96    .055    9463    .075
    9766     .06   10270    .065
BR D Banks=7635.7,7857.61
BC Design=,, 0 ,, 0 ,,,,,,
BC Use User HTab Curves=0
BC User HTab FreeFlow(D)= 0

Type RM Length L Ch R = 1 ,87500   ,39,12,12
BEGIN DESCRIPTION:
Downstream of Cotton Belt Regional Rail
---------------------------------------------------------------------
CDC CAR102120-01 Cotton Belt Regional Rail
---------------------------------------------------------------------
CDC CAR 080723-1 Veloweb Hike and Bike Trail
Cross-section 87500 - 87541
H&B Trail added to Staion 5060 to 5074
---------------------------------------------------------------------
END DESCRIPTION:
XS GIS Cut Line= 6
  2454133.990425 7033167.4262825 2451992.0963282 7033001.8869271
 2451255.3521402  7032927.402843 2449168.7393853 7032769.8334724
 2447772.0046775 7032710.0768215 2440625.9330823 7033094.2972044
#Sta/Elev= 30
  1015.6   448.2    1082   426.6    1127   424.9    1190   430.5    1191     451
    4928     451  4977.7  433.74 5127.86  429.41 5296.56   434.9  5327.5  450.42
    7566     451 7567.96   442.5  7635.7  436.09    7726   408.4    7758   407.4
    7798   412.4 7857.61  436.33 7961.96  440.33    7962     451    9463     451
 9463.62  440.34 9518.24     448 9557.94  437.67 9772.45  435.96 10274.5  435.53
10480.42  436.7410517.76     44810527.34  439.0910568.62  441.68   10570     450
#Mann= 7 ,-1,0
  1015.6    .062       0    7566    .055       0  7635.7     .05       0
 7857.61    .055       0    9463     .06       0 9772.45     .06       0
 10274.5     .06       0
#XS Ineff= 9 ,-1
  1015.6 4933.66     456 4933.66    7550     439    7550 7659.66     452
 7897.34    7965     452    7965    9440   435.8    9440 9518.25     452
 9518.25    9778   441.9   1026810517.76   441.910517.76   10570     451
Permanent Ineff=
       F       F       F       F       F       T       T       T       T
Bank Sta=7635.7,7857.61
XS Rating Curve= 0 ,0
Exp/Cntr=0.5,0.3

Type RM Length L Ch R = 1 ,87488   ,44,6,6
BEGIN DESCRIPTION:
Cross-section added between proposed location of downstream face of NB Cotton Belt and South R/W line.
END DESCRIPTION:
XS GIS Cut Line= 6
  2453181.881655 7033067.1439925 2448824.0185169 7032721.4770364
 2448060.1296277 7032683.2825919 2447442.7956431 7032709.7347765
 2446110.1277495 7032778.3332504 2439188.0954804 7033162.1382055
#Sta/Elev= 30
    -405  443.76  915.83  442.29 1033.38  448.75 1164.13  426.01 1323.15   442.5
 2874.36  439.98 3173.99  432.84 3191.91  438.89 3479.86   450.1 3978.98  439.61
  4993.6   438.3 5184.62  429.32 5381.33  439.02 7609.67  440.22 7682.52  439.94
    7770  408.52    7801  407.32    7837  410.62 7893.54  436.15  8159.7  448.21
 8353.57  437.88  9381.4  437.97 9831.14  436.7710272.08  436.5410670.89   440.2
10826.01  449.4411242.05  437.8511775.75   436.912824.51  439.8913648.95     451
#Mann= 7 ,-1,0
    -405    .075       0 7609.67    .055       0 7682.52     .05       0
 7893.54    .055       0  9381.4     .06       0 9831.14    .055       0
10272.08     .06       0
#XS Ineff= 8 ,-1
    -405  4997.3     452  5436.7    7676     452  7957.7  9545.4     452
  9545.4    9730   441.5    9730    9874     438   10211   10320     438
   10320 10575.5   441.5 10575.513648.95     452
Permanent Ineff=
       T       T       T       T       T       T       T       T
Bank Sta=7682.52,7893.54
XS Rating Curve= 0 ,0
Exp/Cntr=0.5,0.3

Type RM Length L Ch R = 1 ,87482   ,36.5,54,28
XS GIS Cut Line= 6
  2453182.353762 7033061.1625951 2448824.4128056 7032715.4892555
 2448060.1510573 7032677.2761681 2447442.5024909 7032703.7418322
 2446109.8080633 7032772.3417558 2439187.7646977 7033156.1473306
#Sta/Elev= 30
    -405  443.74  915.83  442.27 1033.38  448.73 1164.13  425.99 1323.15  442.48
 2874.36  439.96 3173.99  432.82 3191.91  438.87 3479.86  450.08 3978.98  439.59
 5053.47  437.13 5184.62  429.22  5341.5     439  5416.5     444 7609.67   440.2
 7682.52  439.92    7770   408.5    7801   407.3    7837   410.6 7893.54  436.13
  8159.7  448.19 8353.57  437.86  9381.4  437.95 9831.14  436.7510223.96  436.27
10670.89  440.1810826.01  449.4211242.05  437.8311775.75  436.8913648.95  450.98
#Mann= 8 ,-1,0
    -405    .055       0  5341.5    .065       0 7609.67    .055       0
 7682.52     .05       0 7893.54    .055       0  9381.4    .065       0
 9831.14    .055       010223.96    .065       0
#XS Ineff= 8 ,-1
    -405  4997.3     452  5491.7    7676     452  7957.7    9540     452
    9540    9730   441.5    9730    9880     438   10205   10320     438
   10320   10572   441.5   1057213648.95     452
Permanent Ineff=
       T       T       T       T       T       T       T       T
Bank Sta=7682.52,7893.54
XS Rating Curve= 0 ,0
Exp/Cntr=0.5,0.3

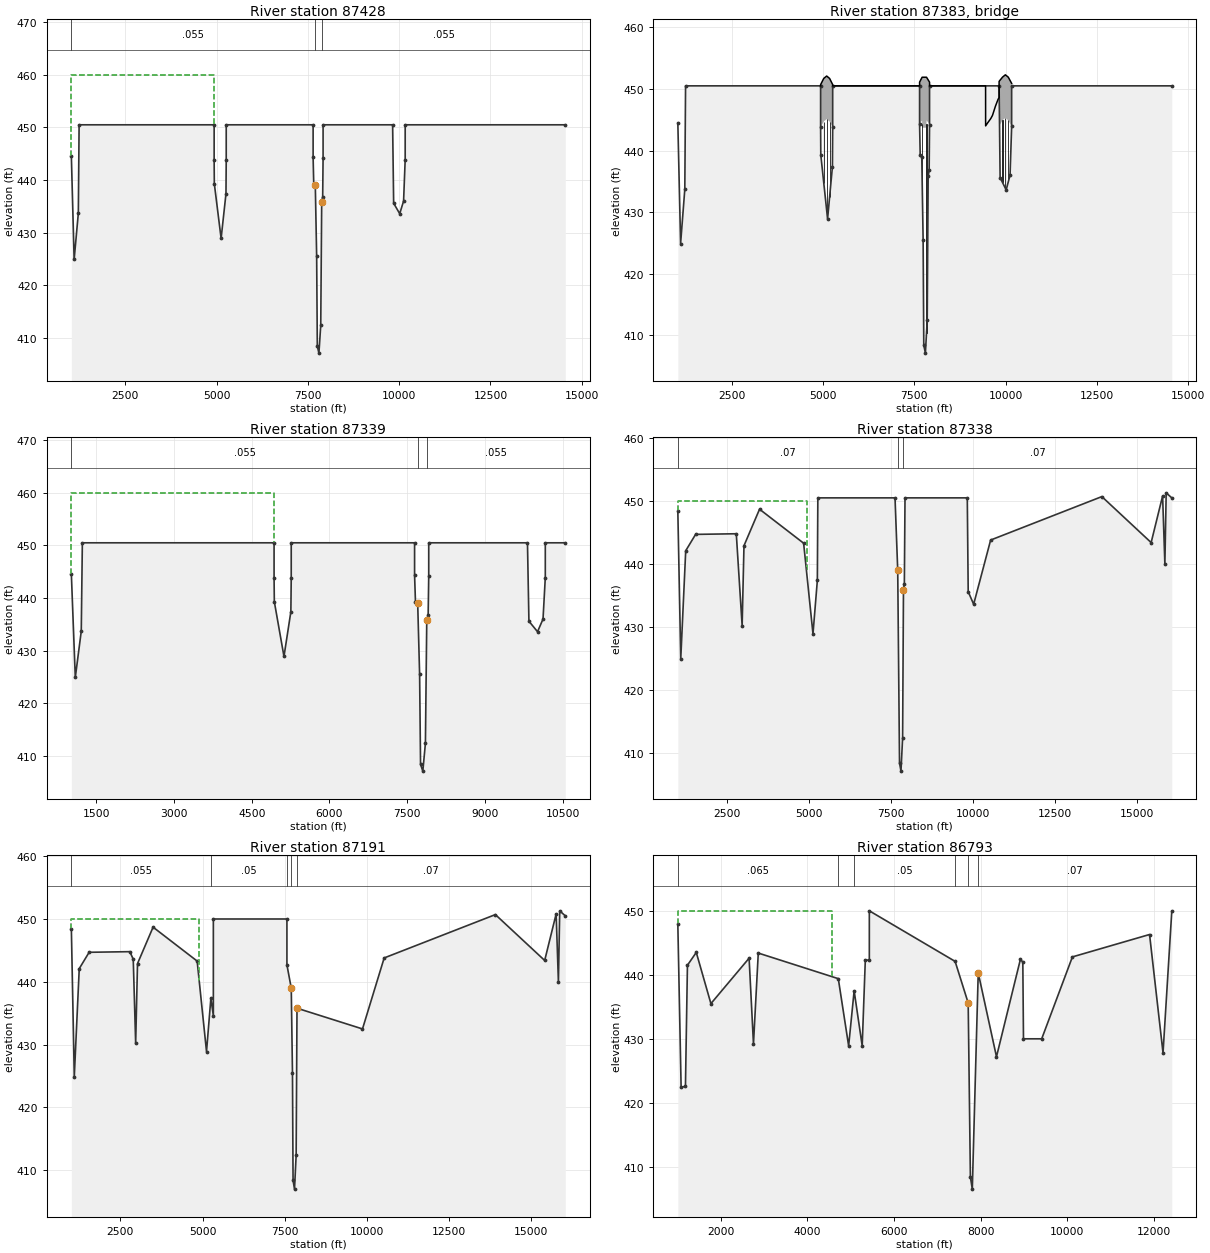
Type RM Length L Ch R = 1 ,87428   ,85,85,85
BEGIN DESCRIPTION:
This cross section corresponds to cross section 87428 of the non-georeferenced CDC model which was the source of this model.
END DESCRIPTION:
XS GIS Cut Line= 6
  2454099.7762167033113.246849212451670.286324357032924.21146613
2450948.477072427032837.734276882448898.740358267032685.89796638
2447533.458640017032651.919687882440595.786211237032971.39049108
#Sta/Elev= 30
    1020   444.5    1096   424.9    1211   433.7    1232   450.5    4931   450.5
    4931  443.78    4936   439.3    5122   428.9    5255   437.4    5262  443.78
    5262   450.5    7642   450.5    7642  444.29    7659   439.3    7702     439
    7739   425.5    7757   408.4    7801   407.1    7851   412.4    7877   435.8
    7904   436.8    7915  444.18    7915   450.5    9820   450.5    9848   435.6
   10014   433.6   10120     436   10164   443.9   10164   450.5   14550   450.5
#Mann= 3 ,0,0
    1020    .055       0    7702     .05       0    7877    .055       0
#XS Ineff= 2 , 0
            4931     460
Permanent Ineff=
       F       F
Bank Sta=7702,7877
XS Rating Curve= 0 ,0
Exp/Cntr=0.5,0.3

Type RM Length L Ch R = 3 ,87383   ,,,
BEGIN DESCRIPTION:
Belt Line Road
END DESCRIPTION:
Node Name=Belt Line Road
Bridge Culvert--1,0,-1,-1, 0
Deck Dist Width WeirC Skew NumUp NumDn MinLoCord MaxHiCord MaxSubmerge Is_Ogee
0.5,84,2.6,0, 38, 38, , , 0.95, 0, ,,,
    4931    4931  5015.8  5018.3  5095.8  5098.3  5175.8  5178.3    5262    5262
    5369    7520    7642    7642  7710.8  7713.3  7830.8  7833.3    7915    7915
    8024    9450    9451    9508    9593    9639    9720    9791    9820    9820
    9830  9910.8  9913.3  9990.8  9993.3 10070.8 10073.3   10164
   450.5   450.7  451.69  451.71  452.09  452.09  451.71  451.69   450.7   450.5
   450.5   450.5   450.5   451.1  451.89   451.9   451.9  451.89   451.1   450.5
   450.5   450.5     444   444.5   445.2   445.7   447.2   448.3   448.6   451.2
   451.3  451.89  451.91  452.29  452.29  451.91  451.89   450.9
   450.5  443.78  444.69  444.71  445.09  445.09  444.71  444.69  443.78   450.5
   450.5   450.5   450.5  444.29  444.89   443.7   443.7  444.89  444.29   450.5
   450.5   450.5     444   444.5   445.2   445.7   447.2   448.3   448.6   443.9
     444  444.89  444.91  445.29  445.29  444.91  444.89   443.9
    4931    4931  5015.8  5018.3  5095.8  5098.3  5175.8  5178.3    5262    5262
    5369    7520    7642    7642  7710.8  7713.3  7830.8  7833.3    7915    7915
    8024    9450    9451    9508    9593    9639    9720    9791    9820    9820
    9830  9910.8  9913.3  9990.8  9993.3 10070.8 10073.3   10164
   450.5   450.7  451.69  451.71  452.09  452.09  451.71  451.69   450.7   450.5
   450.5   450.5   450.5   451.1  451.89   451.9   451.9  451.89   451.1   450.5
   450.5   450.5     444   444.5   445.2   445.7   447.2   448.3   448.6   451.2
   451.3  451.89  451.91  452.29  452.29  451.91  451.89   450.9
   450.5  443.78  444.69  444.71  445.09  445.09  444.71  444.69  443.78   450.5
   450.5   450.5   450.5  444.29  444.89   443.7   443.7  444.89  444.29   450.5
   450.5   450.5     444   444.5   445.2   445.7   447.2   448.3   448.6   443.9
     444  444.89  444.91  445.29  445.29  444.91  444.89   443.9
Pier Skew, UpSta & Num, DnSta & Num=  ,5017.05, 2 ,5017.05, 2 , 0 , 0 , 0 ,,
     2.5     2.5
     430     450
     2.5     2.5
     430     450
Pier Skew, UpSta & Num, DnSta & Num=  ,5097.05, 2 ,5097.05, 2 , 0 , 0 , 0 ,,
     2.5     2.5
     430     450
     2.5     2.5
     430     450
Pier Skew, UpSta & Num, DnSta & Num=  ,5177.05, 2 ,5177.05, 2 , 0 , 0 , 0 ,,
     2.5     2.5
     430     450
     2.5     2.5
     430     450
Pier Skew, UpSta & Num, DnSta & Num=  ,7712.05, 2 ,7712.05, 2 , 0 , 0 , 0 ,,
     2.5     2.5
     410     450
     2.5     2.5
     410     450
Pier Skew, UpSta & Num, DnSta & Num=  ,7832.05, 2 ,7832.05, 2 , 0 , 0 , 0 ,,
     2.5     2.5
     410     450
     2.5     2.5
     410     450
Pier Skew, UpSta & Num, DnSta & Num=  ,9912.05, 2 ,9912.05, 2 , 0 , 0 , 0 ,,
     2.5     2.5
     410     450
     2.5     2.5
     410     450
Pier Skew, UpSta & Num, DnSta & Num=  ,9992.05, 2 ,9992.05, 2 , 0 , 0 , 0 ,,
     2.5     2.5
     410     450
     2.5     2.5
     410     450
Pier Skew, UpSta & Num, DnSta & Num=  ,10072.05, 2 ,10072.05, 2 , 0 , 0 , 0 ,,
     2.5     2.5
     410     450
     2.5     2.5
     410     450
BR Coef= 1 , 0 , 0 ,1.05, 0 ,,,0.8,-1,0.5,1,
WSPro=,,,, 1 ,,,, 0 ,,,, 0 ,,,,-1 ,-1 ,-1 , 0 , 0 , 0 , 0 , 0
BC Design=,, 0 ,, 0 ,,,,,,
BC HTab HWMax=450.5
BC Use User HTab Curves=0
BC User HTab FreeFlow(D)= 0

Type RM Length L Ch R = 1 ,87339   ,1,1,1
BEGIN DESCRIPTION:
This cross section corresponds to cross section 87339 of the non-georeferenced CDC model which was the source of this model.
END DESCRIPTION:
XS GIS Cut Line= 6
2454096.437968087033066.68066938 2451360.00446467032828.53350788
2450655.638419247032730.874910552448644.077809847032584.72428422
2447305.792756777032575.173778382444591.557699687032674.81465521
#Sta/Elev= 30
    1020   444.5    1096   424.9    1211   433.7    1232   450.5    4931   450.5
    4931  443.78    4936   439.3    5122   428.9    5255   437.4    5262  443.78
    5262   450.5    7642   450.5    7642  444.29    7659   439.3    7702     439
    7739   425.5    7757   408.4    7801   407.1    7851   412.4    7877   435.8
    7904   436.8    7915  444.18    7915   450.5    9820   450.5    9848   435.6
   10014   433.6   10120     436   10164   443.9   10164   450.5   10550   450.5
#Mann= 3 ,0,0
    1020    .055       0    7702     .05       0    7877    .055       0
#XS Ineff= 2 , 0
            4931     460
Permanent Ineff=
       F       F
Bank Sta=7702,7877
XS Rating Curve= 0 ,0
Exp/Cntr=0.5,0.3

Type RM Length L Ch R = 1 ,87338   ,99,146,258
BEGIN DESCRIPTION:
This cross section corresponds to cross section 87338 of the non-georeferenced CDC model which was the source of this model.
END DESCRIPTION:
XS GIS Cut Line= 6
  2454105.186966 7033067.3151826 2451356.5897733 7032827.4649405
 2450652.3930189 7032729.6787187 2448100.9394604 7032577.6547446
 2445703.8589528 7032630.5614629 2439097.1060902 7032909.7754714
#Sta/Elev= 30
    1007   448.4    1096   424.9    1247   442.1    1548   444.7    2787   444.8
    2965   430.2    3021   442.9    3495   448.7    4837   443.3    5122   428.9
    5255   437.4    5270   450.5    7620   450.5    7702     439    7757   408.4
    7801   407.1    7851   412.4    7877   435.8    7904   436.8    7924   450.5
    9820   450.5    9848   435.6   10014   433.6   10531   443.8   13917   450.7
   15418   443.4   15767   450.8   15836     440   15876   451.3   16046   450.5
#Mann= 3 ,0,0
    1007     .07       0    7702    .055       0    7877     .07       0
#XS Ineff= 2 , 0
            4925     450
Permanent Ineff=
       F       F
Bank Sta=7702,7877
XS Rating Curve= 0 ,0
Exp/Cntr=0.3,0.1

Type RM Length L Ch R = 1 ,87191   ,308,408,390
BEGIN DESCRIPTION:
This cross section corresponds to cross section 87191 of the non-georeferenced CDC model which was the source of this model.
---------------------------------------------------------------------
UPSTREAM END OF CDC COP082301-1 DEVELOPMENT AT 1550 E. BELT LINE ROAD.
CROSS-SECTION 86107 - 87191
---------------------------------------------------------------------
END DESCRIPTION:
XS GIS Cut Line= 6
   2454060.74775 7032917.9004551 2450850.1058781 7032670.0259509
 2450173.5688453 7032553.5389791 2448224.0310777 7032416.5881376
 2443228.3750586 7032535.8631615 2439047.8611099 7032583.4418065
#Sta/Elev= 30
    1007   448.4    1096   424.9    1247   442.1    1548   444.7    2787   444.8
    2891   443.6    2965   430.2    3021   442.9    3495   448.7    4837   443.3
    5122   428.9    5255   437.4    5330   434.6    5330     450    7570     450
    7570   442.7    7702     439    7739   425.5    7757   408.4    7801     407
    7851   412.4    7877   435.8    9871   432.5   10531   443.8   13917   450.7
   15418   443.4   15767   450.8   15836     440   15876   451.3   16046   450.5
#Mann= 5 ,-1,0
    1007    .055       0    5255     .05       0    7570      .1       0
    7702    .055       0    7877     .07       0
#XS Ineff= 2 , 0
            4900     450
Permanent Ineff=
       F       F
Bank Sta=7702,7877
XS Rating Curve= 0 ,0
Exp/Cntr=0.3,0.1

Type RM Length L Ch R = 1 ,86793   ,140,166,166
BEGIN DESCRIPTION:
This cross section corresponds to cross section 86793 of the non-georeferenced CDC model which was the source of this model.
XS 86799 to 87207 retored to 1991 topo to remove project COP 082310-01
END DESCRIPTION:
XS GIS Cut Line= 5
  2453906.375684 7032326.3898271 2453299.8099682 7032460.7291254
 2447409.0589544 7032071.9759659 2442924.8950225 7032155.9000106
 2442570.1162045 7031975.0332464
#Sta/Elev= 30
    1007   447.9    1083   422.4    1183   422.6    1229   441.5    1433   443.5
    1771   435.5    2653   442.6    2754   429.2    2865   443.4    4713   439.4
    4952   428.9    5079   437.5    5265   428.9    5337   442.3    5430   442.3
    5430     450    7411   442.1    7713   435.6    7764   408.4    7808  406.51
    7945   440.3  8366.6   427.2  8918.4   442.4  8974.8     442    8990     430
    9411     430   10120   442.8   11902   446.3   12213   427.8   12415   449.9
#Mann= 6 ,-1,0
    1007    .065       0    4713    .055       0    5079     .05       0
    7411      .1       0    7713    .055       0    7945     .07       0
#XS Ineff= 2 , 0
            4560     450
Permanent Ineff=
       F       F
Bank Sta=7713,7945
XS Rating Curve= 0 ,0
Exp/Cntr=0.3,0.1

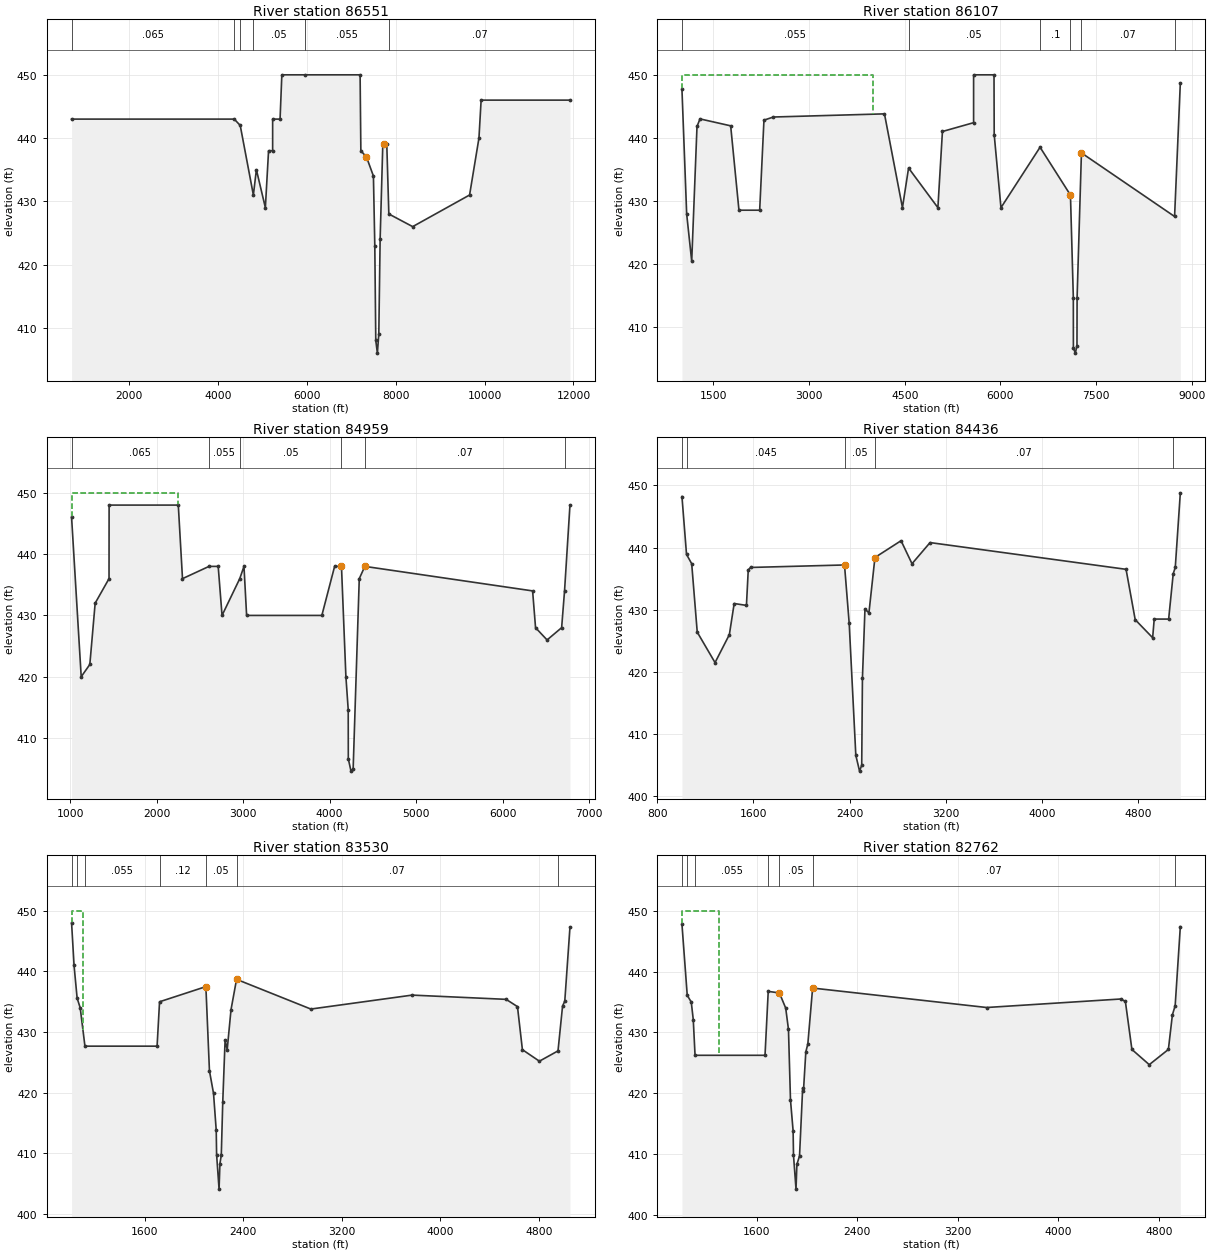
Type RM Length L Ch R = 1 ,86551   ,431,510,1114
BEGIN DESCRIPTION:
This cross section corresponds to cross section 86551 of the non-georeferenced CDC model which was the source of this model.
END DESCRIPTION:
XS GIS Cut Line= 6
2454012.779178877032283.428838422453713.343142387032265.04242904
2452715.223020747032203.754397792448004.311044757031914.48809189
2446014.163122187031915.053707552442816.607098677031620.84253979
#Sta/Elev= 30
     700     443    4362     443    4497     442    4793     431    4861     435
    5063     429    5135     438    5227     438    5227     443    5394     443
    5434     450    5960     450    7196     450    7213     438    7340     437
    7496     434    7527     423    7549     408    7585     406    7617     409
    7647     424    7707     439    7737     439    7797     439    7843     428
    8380     426    9661     431    9872     440    9921     446   11921     446
#Mann= 6 ,-1,0
     700    .065       0    4362    .065       0    4497    .055       0
    4793     .05       0    5960    .055       0    7843     .07       0
Bank Sta=7340,7737
XS Rating Curve= 0 ,0
Exp/Cntr=0.3,0.1

Type RM Length L Ch R = 1 ,86107   ,479,1145,299
BEGIN DESCRIPTION:
This cross section corresponds to cross section 86107 of the non-georeferenced CDC model which was the source of this model.
---------------------------------------------------------------------
DOWNSTREAM END OF CDC COP082301-1 DEVELOPMENT AT 1550 E. BELT LINE ROAD.
CROSS-SECTION 86107 - 87191
---------------------------------------------------------------------
END DESCRIPTION:
XS GIS Cut Line= 4
2453555.21398494 7031698.60040032453070.766134927031820.77404046
2447563.644931357031550.248990972445897.360862347030862.53908031
#Sta/Elev= 30
    1006   447.7    1080   427.9    1159   420.4    1242   441.8    1289     443
    1770   441.9    1900   428.5    2225   428.5    2292   442.8    2440   443.3
    4182   443.8    4464   428.9    4560   435.2    5020   428.9    5091     441
    5580   442.4    5580     450    5900     450    5903   440.5    6009   428.9
    6622   438.5    7099   430.9    7144   414.6    7145   406.6    7176   405.8
    7201     407    7203   414.6    7271   437.6    8732   427.5    8822   448.7
#Mann= 6 ,-1,0
    1006    .055       0    4560     .05       0    6622      .1       0
    7099     .05       0    7271     .07       0    8732     .03       0
#XS Ineff= 2 , 0
            4000     450
Permanent Ineff=
       F       F
Bank Sta=7099,7271
XS Rating Curve= 0 ,0
Exp/Cntr=0.3,0.1

Type RM Length L Ch R = 1 ,84959   ,512,475,221
BEGIN DESCRIPTION:
This cross section corresponds to cross section 84959 of the non-georeferenced CDC model which was the source of this model.
END DESCRIPTION:
XS GIS Cut Line= 5
 2451546.38565357030892.684361222451228.805908087031204.77297588
  2448559.7479267031205.354995712448354.105948847031077.09901863
  2445978.1664757030697.18212755
#Sta/Elev= 30
  1016.1     446  1127.3     420  1227.1     422  1288.7     432    1449     436
    1450     448    2250     448  2298.6     436  2605.3     438  2711.4     438
  2755.8     430  2960.7     436  3009.5     438    3040     430    3910     430
  4057.5     438  4136.9     438  4188.1     420    4215   414.6    4216   406.6
    4247   404.6    4272     405  4342.6     436  4407.1     438  6347.1     434
    6381     428  6514.3     426  6682.7     428  6716.3     434  6778.9     448
#Mann= 6 ,-1,0
  1016.1    .065       0  2605.3    .055       0  2960.7     .05       0
  4136.9    .055       0  4407.1     .07       0  6716.3     .03       0
#XS Ineff= 2 , 0
            2250     450
Permanent Ineff=
       F       F
Bank Sta=4136.9,4407.1
XS Rating Curve= 0 ,0
Exp/Cntr=0.3,0.1

Type RM Length L Ch R = 1 ,84436   ,900,956,650
BEGIN DESCRIPTION:
This cross section corresponds to cross section 84436 of the non-georeferenced CDC model which was the source of this model.
END DESCRIPTION:
XS GIS Cut Line= 3
2450143.405519847030683.264832562448828.647978757030744.41595696
2446012.520736997030510.55126722
#Sta/Elev= 30
    1006   448.2    1044   438.9    1087   437.4    1133   426.4    1281   421.5
    1400     426    1440     431    1542   430.7    1557   436.4    1576   436.8
    2357   437.2    2396   427.8    2451   406.6    2482  404.05    2500     405
    2506     419    2527   430.1    2560   429.5    2610   438.4    2827   441.1
    2918   437.4    3068   440.8    4697   436.5    4773   428.4    4918   425.5
    4931   428.5    5051   428.5    5089   435.8    5106   436.8    5148   448.8
#Mann= 5 ,-1,0
    1006     .03       0    1044    .045       0    2357     .05       0
    2610     .07       0    5089     .03       0
Bank Sta=2357,2610
XS Rating Curve= 0 ,0
Exp/Cntr=0.3,0.1

Type RM Length L Ch R = 1 ,83530   ,700,768,690
BEGIN DESCRIPTION:
This cross section corresponds to cross section 83530 of the non-georeferenced CDC model which was the source of this model.
END DESCRIPTION:
XS GIS Cut Line= 2
2450134.949828097029817.165514892446090.594727847029889.38584289
#Sta/Elev= 30
    1006     448    1026     441    1051   435.6    1076     434  1114.4  427.68
    1700  427.68    1720     435    2096   437.5    2125   423.6    2158   419.9
    2180   413.8    2183   409.8    2203   404.1    2210   408.3    2221   409.7
    2233   418.5    2252   428.7    2269   427.1    2300   433.7    2345   438.7
    2948   433.8    3770   436.1    4533   435.4    4625   434.2    4665   427.1
    4803   425.2    4954   426.9    4991   434.3    5009   435.1    5051   447.3
#Mann= 7 ,-1,0
    1006     .03       0    1051    .045       0  1114.4    .055       0
    1720     .12       0    2096     .05       0    2345     .07       0
    4954     .03       0
#XS Ineff= 2 , 0
            1098     450
Permanent Ineff=
       F       F
Bank Sta=2096,2345
XS Rating Curve= 0 ,0
Exp/Cntr=0.3,0.1

Type RM Length L Ch R = 1 ,82762   ,920,914,780
BEGIN DESCRIPTION:
This cross section corresponds to cross section 82762 of the non-georeferenced CDC model which was the source of this model.
END DESCRIPTION:
XS GIS Cut Line= 2
2450139.973768177029120.920844382446178.006298427029211.37670022
#Sta/Elev= 30
    1006   447.8    1048   436.1    1080     435    1096   432.1 1110.11  426.24
 1666.53  426.24    1692  436.75    1781   436.5    1831     434    1853   430.5
    1869   418.9    1890   413.8    1893   409.8    1913  404.23    1920   408.3
    1941   409.7    1966   420.9    1972   420.3    1991   426.8    2007   428.1
    2045   437.3    3429   434.1    4496   435.5    4532   435.1    4584   427.2
    4722   424.7    4874   427.2    4906   432.9    4928   434.4    4969   447.4
#Mann= 7 ,-1,0
    1006     .03       0    1048    .045       0 1110.11    .055       0
    1692     .12       0    1781     .05       0    2045     .07       0
    4928     .03       0
#XS Ineff= 2 , 0
            1298     450
Permanent Ineff=
       F       F
Bank Sta=1781,2045
XS Rating Curve= 0 ,0
Exp/Cntr=0.3,0.1