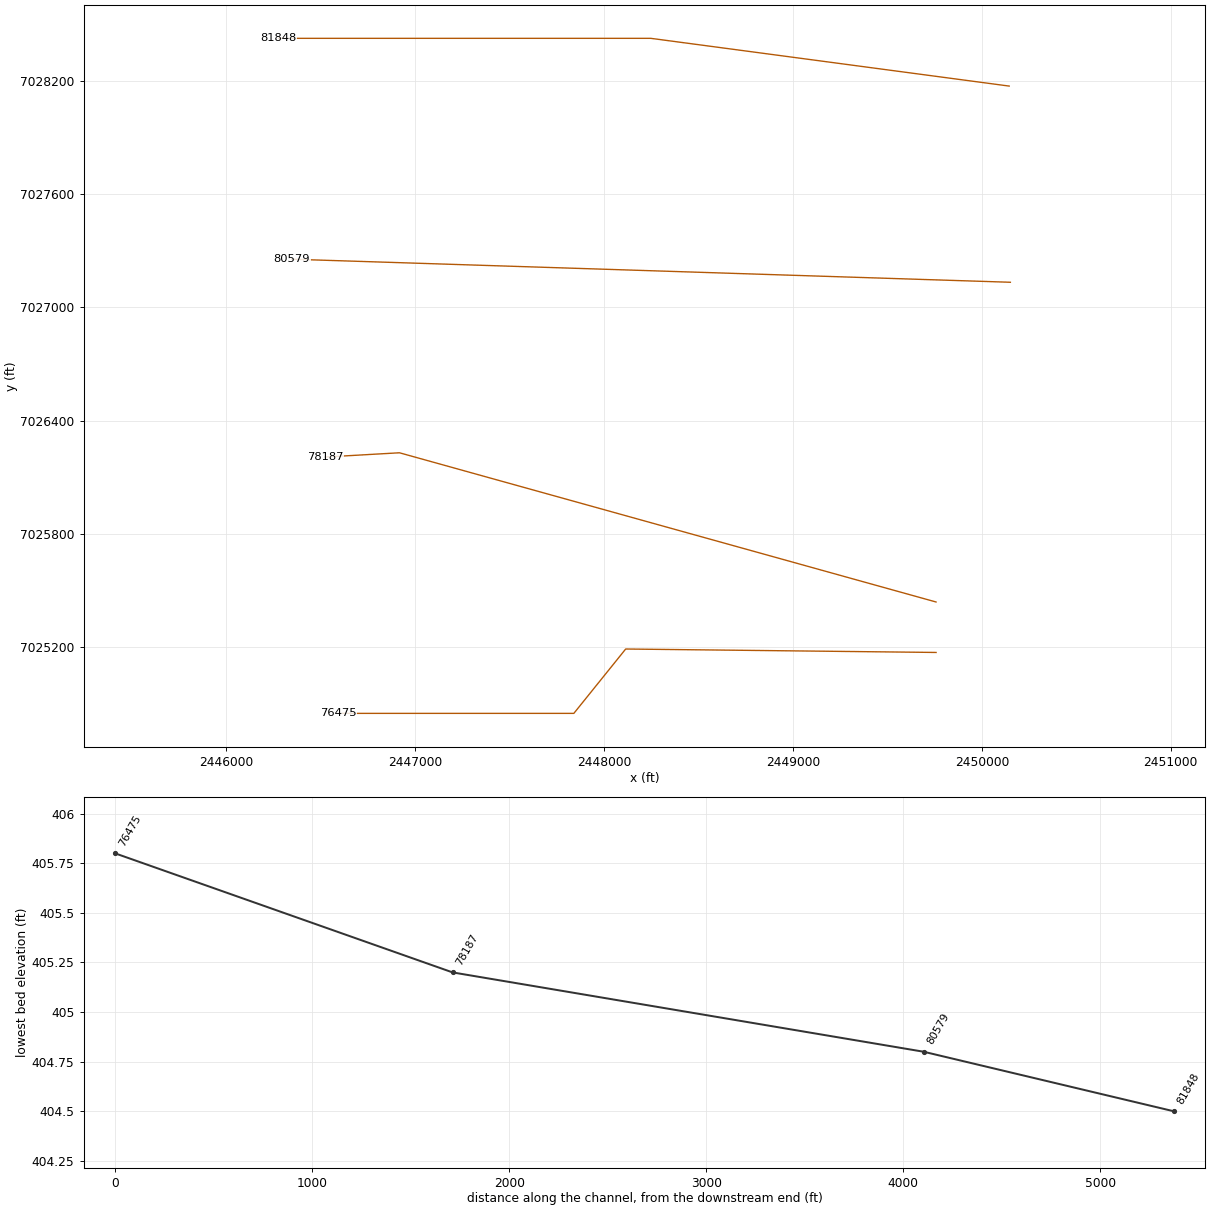
HEC-RAS study CDC_Consolidated_Model.prj: Upper Trinity CDC Consolidated Model

--- CDC_Consolidated_Model.g13 (geometry) --- (continued)

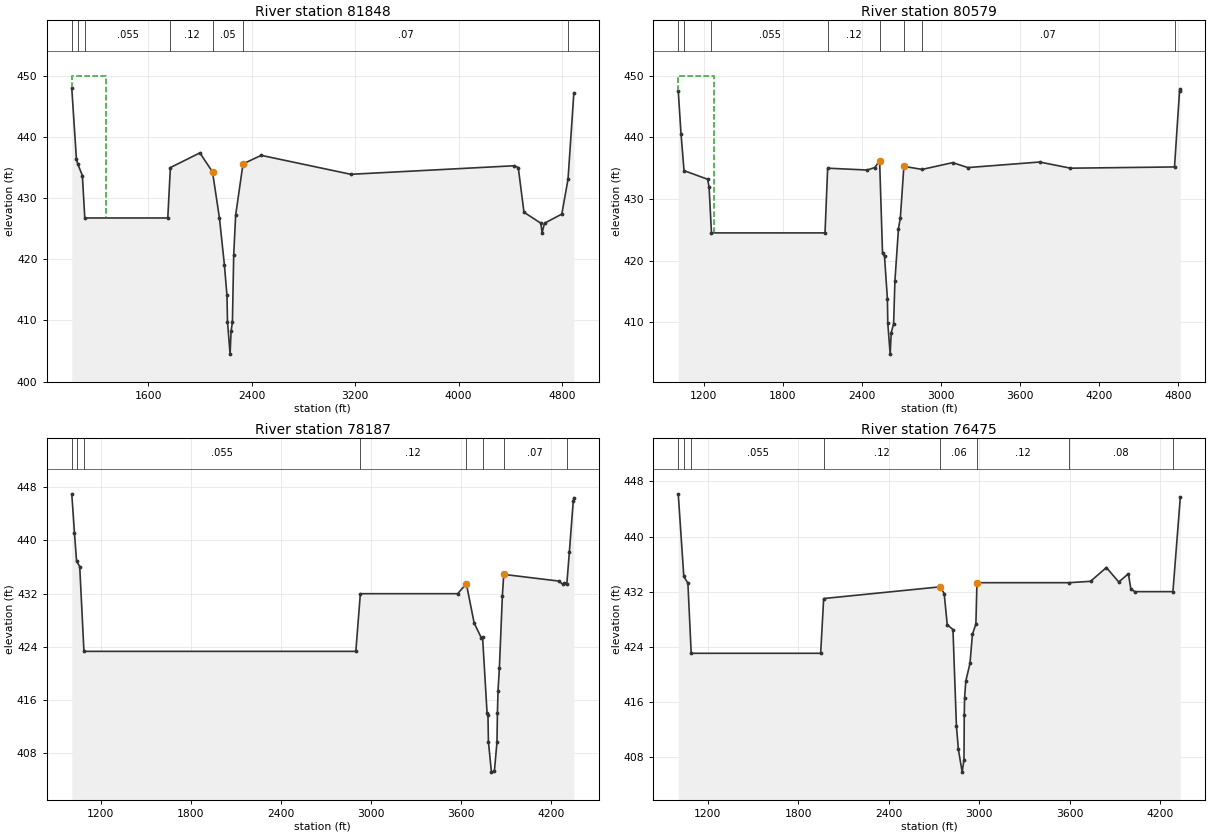
Type RM Length L Ch R = 1 ,81848   ,1090,1269,1200
BEGIN DESCRIPTION:
This cross section corresponds to cross section 81848 of the non-georeferenced CDC model which was the source of this model.
END DESCRIPTION:
XS GIS Cut Line= 3
2450144.67126533 7028172.55627132448247.31088683 7028425.5380488
2446276.46246633 7028425.5380488
#Sta/Elev= 30
    1007     448    1043   436.4    1053   435.6    1089   433.7  1107.8  426.76
    1750  426.76    1770     435    1998   437.4    2096   434.3    2150   426.7
    2188   419.1    2208   414.1    2212   409.8    2232   404.5    2240   408.3
    2250   409.7    2260   420.7    2275   427.2    2332   435.6    2473     437
    3166   433.9    4432   435.3    4462     435    4506   427.7    4637   425.9
    4646   424.3    4665   425.9    4799   427.4    4847   433.1    4892   447.2
#Mann= 7 ,-1,0
    1007     .03       0    1053    .045       0  1107.8    .055       0
    1770     .12       0    2096     .05       0    2332     .07       0
    4847     .03       0
#XS Ineff= 2 , 0
            1274     450
Permanent Ineff=
       F       F
Bank Sta=2096,2332
XS Rating Curve= 0 ,0
Exp/Cntr=0.3,0.1

Type RM Length L Ch R = 1 ,80579   ,1599,2391,1030
BEGIN DESCRIPTION:
This cross section corresponds to cross section 80579 of the non-georeferenced CDC model which was the source of this model.
END DESCRIPTION:
XS GIS Cut Line= 2
2450151.002617517027133.076722962446345.963639687027255.25626864
#Sta/Elev= 30
    1007   447.6    1028   440.6    1051   434.6    1230   433.2    1241   431.9
    1259  424.49    2120  424.49    2140     435    2439   434.7    2497   435.1
    2534   436.2    2556   421.2    2571   420.7    2593   413.8    2596   409.8
    2614   404.8    2622   408.3    2640   409.7    2650   416.7    2677   425.2
    2691   426.9    2718   435.3    2856   434.8    3088   435.9    3203   435.1
    3747     436    3981     435    4770   435.2    4808   447.5    4814   447.8
#Mann= 8 ,-1,0
    1007     .03       0    1051    .045       0    1259    .055       0
    2140     .12       0    2534    .055       0    2718     .12       0
    2856     .07       0    4770     .03       0
#XS Ineff= 2 , 0
            1279     450
Permanent Ineff=
       F       F
Bank Sta=2534,2718
XS Rating Curve= 0 ,0
Exp/Cntr=0.3,0.1

Type RM Length L Ch R = 1 ,78187   ,800,1712,1380
BEGIN DESCRIPTION:
This cross section corresponds to cross section 78187 of the non-georeferenced CDC model which was the source of this model.
END DESCRIPTION:
XS GIS Cut Line= 3
2449757.539821747025438.934770052446916.428049927026229.58115463
2446522.145373917026207.05101597
#Sta/Elev= 30
    1008     447    1026   441.1    1040   436.9    1061  436.07 1089.14  423.34
    2900  423.34    2930     432    3578     432    3636   433.5    3688   427.6
    3735   425.4    3744   425.5    3774   414.1    3780   413.8    3783   409.8
    3803   405.2    3823   405.4    3840   409.7    3843   414.1    3847   417.4
    3856   420.8    3876   431.7    3885   434.9    4250   433.9    4280   433.4
    4289   433.6    4305   433.4    4322   438.2    4348   445.9    4352   446.4
#Mann= 8 ,-1,0
    1008     .03       0    1040    .045       0 1089.14    .055       0
    2930     .12       0    3636     .12       0    3744    .055       0
    3885     .07       0    4305     .03       0
Bank Sta=3636,3885
XS Rating Curve= 0 ,0
Exp/Cntr=0.3,0.1

Type RM Length L Ch R = 1 ,76475   ,1740,3762,1200
BEGIN DESCRIPTION:
This cross section corresponds to cross section 76475 of the non-georeferenced CDC model which was the source of this model.
END DESCRIPTION:
XS GIS Cut Line= 4
2449757.729453927025171.567522632448114.222898427025189.82896905
2447839.728040587024848.789952962446593.120297587024848.78995296
#Sta/Elev= 30
    1006   446.2    1043   434.2    1070  433.24 1091.99  423.05    1950  423.05
    1970     431    2743   432.7    2769   431.7    2789   427.2    2827   426.5
    2850   412.5    2863   409.1    2888   405.8    2900   407.6    2902   414.1
    2904   416.5    2912     419    2940   421.6    2956   425.8    2979   427.3
    2986   433.3    3595   433.3    3739   433.5    3844   435.5    3926   433.4
    3990   434.6    4006   432.4    4032     432    4285     432    4334   445.7
#Mann= 8 ,-1,0
    1006     .03       0    1043    .045       0 1091.99    .055       0
    1970     .12       0    2743     .06       0    2986     .12       0
    3595     .08       0    4285     .03       0
Bank Sta=2743,2986
XS Rating Curve= 0 ,0
Exp/Cntr=0.3,0.1