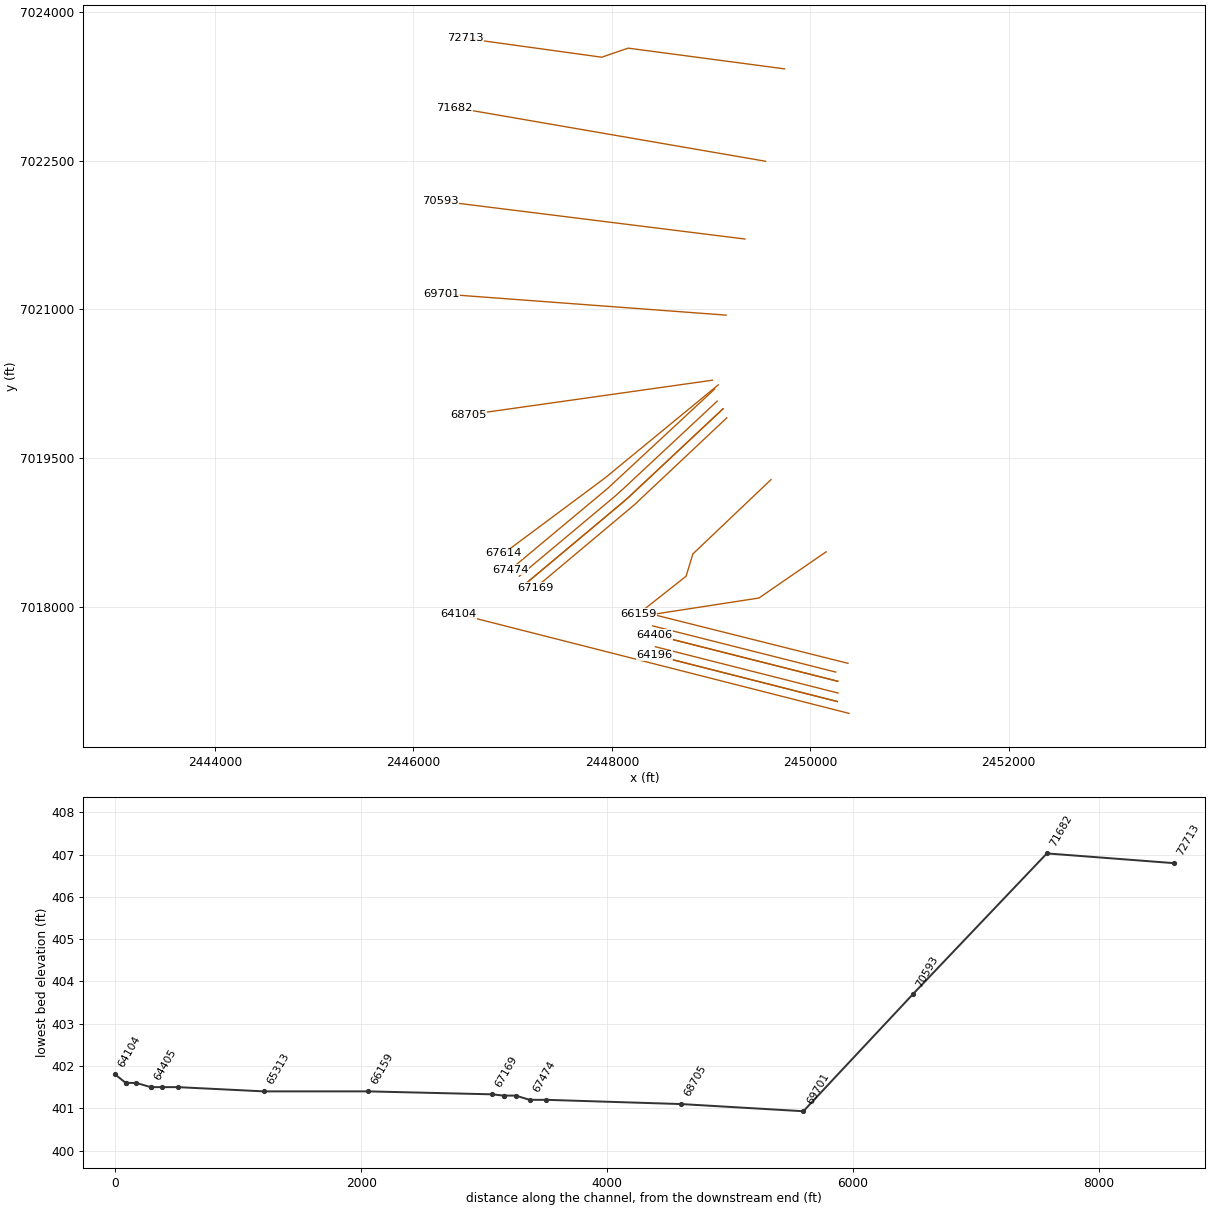
HEC-RAS study CDC_Consolidated_Model.prj: Upper Trinity CDC Consolidated Model

--- CDC_Consolidated_Model.g13 (geometry) --- (continued)

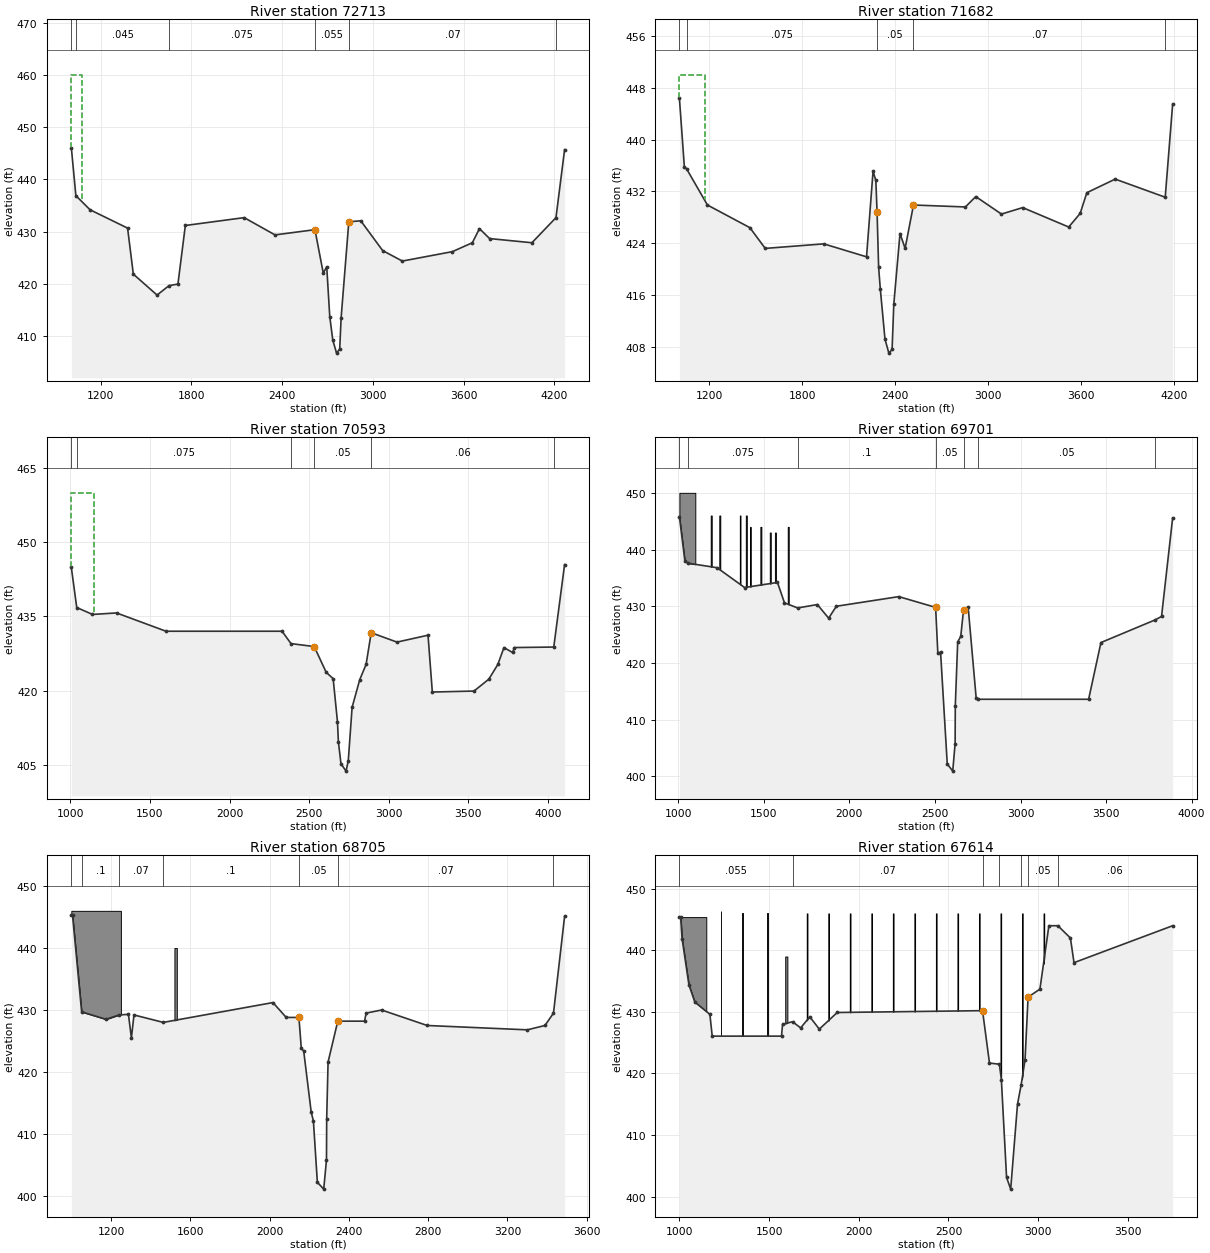
Type RM Length L Ch R = 1 ,72713   ,940,1031,740
BEGIN DESCRIPTION:
This cross section corresponds to cross section 72713 of the non-georeferenced CDC model which was the source of this model.
END DESCRIPTION:
XS GIS Cut Line= 4
2449740.069056187023425.39581813 2448164.13093517023634.35898288
2447897.953974017023542.861134382446520.236257027023733.20392954
#Sta/Elev= 30
    1006   446.1    1036   436.9    1130   434.2    1378   430.7    1416   421.9
    1573   417.9    1652   419.7    1711     420    1760   431.2    2149   432.7
    2353   429.4    2617   430.4    2672   422.1    2695   423.3    2715   413.8
    2735   409.3    2760   406.8    2781   407.6    2790   413.5    2841   431.9
    2920   432.1    3065   426.4    3195   424.4    3526   426.2    3658   427.9
    3705   430.6    3772   428.7    4052   427.9    4211   432.7    4268   445.7
#Mann= 6 ,-1,0
    1006     .03       0    1036    .045       0    1652    .075       0
    2617    .055       0    2841     .07       0    4211     .03       0
#XS Ineff= 2 , 0
            1077     460
Permanent Ineff=
       F       F
Bank Sta=2617,2841
XS Rating Curve= 0 ,0
Exp/Cntr=0.3,0.1

Type RM Length L Ch R = 1 ,71682   ,850,1089,920
BEGIN DESCRIPTION:
This cross section corresponds to cross section 71682 of the non-georeferenced CDC model which was the source of this model.
END DESCRIPTION:
XS GIS Cut Line= 2
  2449549.1829557022493.442301472446411.683324527023035.61608589
#Sta/Elev= 30
    1008   446.4    1040   435.8    1054   435.5    1189   429.9    1463   426.4
    1562   423.2    1940   423.9    2216   421.9    2258   435.1    2276   433.7
    2284   428.8    2294   420.3    2305   416.9    2335   409.2    2360  407.03
    2381   407.6    2392   414.6    2432   425.5    2465   423.2    2519   429.9
    2854   429.6    2921   431.2    3087   428.5    3224   429.5    3521   426.5
    3595   428.6    3638   431.8    3821   433.9    4144   431.1    4192   445.5
#Mann= 5 ,-1,0
    1008     .03       0    1054    .075       0    2284     .05       0
    2519     .07       0    4144     .03       0
#XS Ineff= 2 , 0
            1171     450
Permanent Ineff=
       F       F
Bank Sta=2284,2519
XS Rating Curve= 0 ,0
Exp/Cntr=0.3,0.1

Type RM Length L Ch R = 1 ,70593   ,829,891,899
BEGIN DESCRIPTION:
This cross section corresponds to cross section 70593 of the non-georeferenced CDC model which was the source of this model.
END DESCRIPTION:
XS GIS Cut Line= 2
2449341.456992517021709.253253042446266.247591767022092.51364139
#Sta/Elev= 30
    1006   444.9    1040   436.8    1139   435.4    1290   435.7    1601     432
    2330     432    2386   429.5    2532   428.9    2607   423.7    2651   422.4
    2678   413.7    2684   409.6    2700   405.2    2732   403.7    2746   405.8
    2770   416.6    2818   422.2    2858   425.3    2890   431.7    3052   429.8
    3247   431.2    3274   419.7    3536   419.9    3629   422.3    3686   425.3
    3724   428.7    3778   427.7    3790   428.7    4037   428.8    4105   445.5
#Mann= 6 ,-1,0
    1006     .03       0    1040    .075       0    2386      .1       0
    2532     .05       0    2890     .06       0    4037     .03       0
#XS Ineff= 2 , 0
            1148     460
Permanent Ineff=
       F       F
Bank Sta=2532,2890
XS Rating Curve= 0 ,0
Exp/Cntr=0.3,0.1

Type RM Length L Ch R = 1 ,69701   ,800,996,1100
BEGIN DESCRIPTION:
This cross section corresponds to cross section 69701 of the non-georeferenced CDC model which was the source of this model.
END DESCRIPTION:
XS GIS Cut Line= 2
2449151.346480347020941.635365712446277.318763857021155.84917614
#Sta/Elev= 30
    1007   445.8    1039     438    1056   437.6    1227   436.8    1388   433.3
    1580   434.2    1621   430.6    1698   429.7    1813   430.3    1879   427.9
    1924     430    2289   431.7    2504   429.8    2517   421.7    2533   421.9
    2572   402.2    2604  400.93    2618   405.8    2619   412.4    2633   423.7
    2651   424.7    2667   429.3    2694   429.9    2741   413.8    2749   413.6
    3398   413.6    3470   423.6    3787   427.6    3824   428.2    3889   445.6
#Mann= 7 ,-1,0
    1007     .03       0    1056    .075       0    1698      .1       0
    2504     .05       0    2667      .1       0    2749     .05       0
    3787     .03       0
#Block Obstruct= 10 ,-1
    1007    1100     450    1190    1196     446    1240    1246     446
    1360    1364     446    1395    1401     446    1420    1424     444
    1480    1486     444    1535    1541     443    1565    1571     443
    1640    1646     444
#XS Lid=4
    1160     449     445    1620     445     441    1620   447.5   443.5
    1665   447.5   443.5
Bank Sta=2504,2667
XS Rating Curve= 0 ,0
Exp/Cntr=0.3,0.1

Type RM Length L Ch R = 1 ,68705   ,581,1093,1087
BEGIN DESCRIPTION:
This cross section corresponds to cross section 68705 of the non-georeferenced CDC model which was the source of this model.
END DESCRIPTION:
XS GIS Cut Line= 2
2449013.525889847020285.36108771 2446550.06920267019936.75811039
#Sta/Elev= 30
    1000   445.3    1006   445.3    1052   429.7    1175   428.5    1240   429.2
    1288   429.3    1303   425.5    1316   429.2    1464     428    2017   431.2
    2084   428.8    2148   428.8    2160   423.8    2172   423.4    2210   413.5
    2221   412.1    2241   402.2    2273   401.1    2287   405.8    2288   412.4
    2295   421.6    2344   428.2    2479   428.2    2487   429.5    2565     430
    2795   427.5    3300   426.8    3389   427.5    3432   429.5    3488   445.1
#Mann= 7 ,-1,0
    1000     .03       0    1052      .1       0    1240     .07       0
    1464      .1       0    2148     .05       0    2344     .07       0
    3432     .03       0
#Block Obstruct= 2 ,-1
    1000    1250     446    1520    1532     440
#XS Lid=2
    1490  441.63  437.46    1570  446.11  441.94
Bank Sta=2148,2344
XS Rating Curve= 0 ,0
Exp/Cntr=0.3,0.1

Type RM Length L Ch R = 1 ,67614   ,166,137,161
BEGIN DESCRIPTION:
This cross section corresponds to cross section 67474 of the non-georeferenced CDC model which was the source of this model.
END DESCRIPTION:
XS GIS Cut Line= 3
2449072.05825308 7020238.17450232447929.897151597019298.86306071
  2446910.4126427018539.51418571
#Sta/Elev= 30
    1000   445.4    1007   445.4    1015   441.9    1053   434.4    1086   431.6
    1170   429.6 1182.88  426.06 1569.37  426.06 1575.14  427.99    1631   428.4
    1676   427.4    1727   429.2    1780   427.2    1880   429.9    2690   430.2
 2728.77  421.68    2784   421.5    2795     419    2824   403.1    2847   401.2
    2885     415    2905   418.1    2927   422.2    2944   432.4    3010   433.7
    3060     444    3110     444    3180     442    3200     438    3750     444
#Mann= 7 ,-1,0
    1000    .055       0    1631     .07       0    2690     .05       0
    2784     .05       0    2905     .07       0    2944     .05       0
    3110     .06       0
#Block Obstruct= 17 ,-1
    1000    1150   445.4    1230    1234  446.42    1350    1354     446
    1490    1494     446    1590    1602     439    1710    1714     446
    1830    1834     446    1950    1954     446    2070    2074     446
    2190    2194     446    2310    2314     446    2430    2434     446
    2550    2554     446    2670    2674     446    2790    2794     446
    2910    2914     446    3030    3034     446
#XS Lid=2
    1554  440.97   436.8    1634  444.33  440.16
Bank Sta=2690,2944
XS Rating Curve= 0 ,0
Exp/Cntr=0.3,0.1

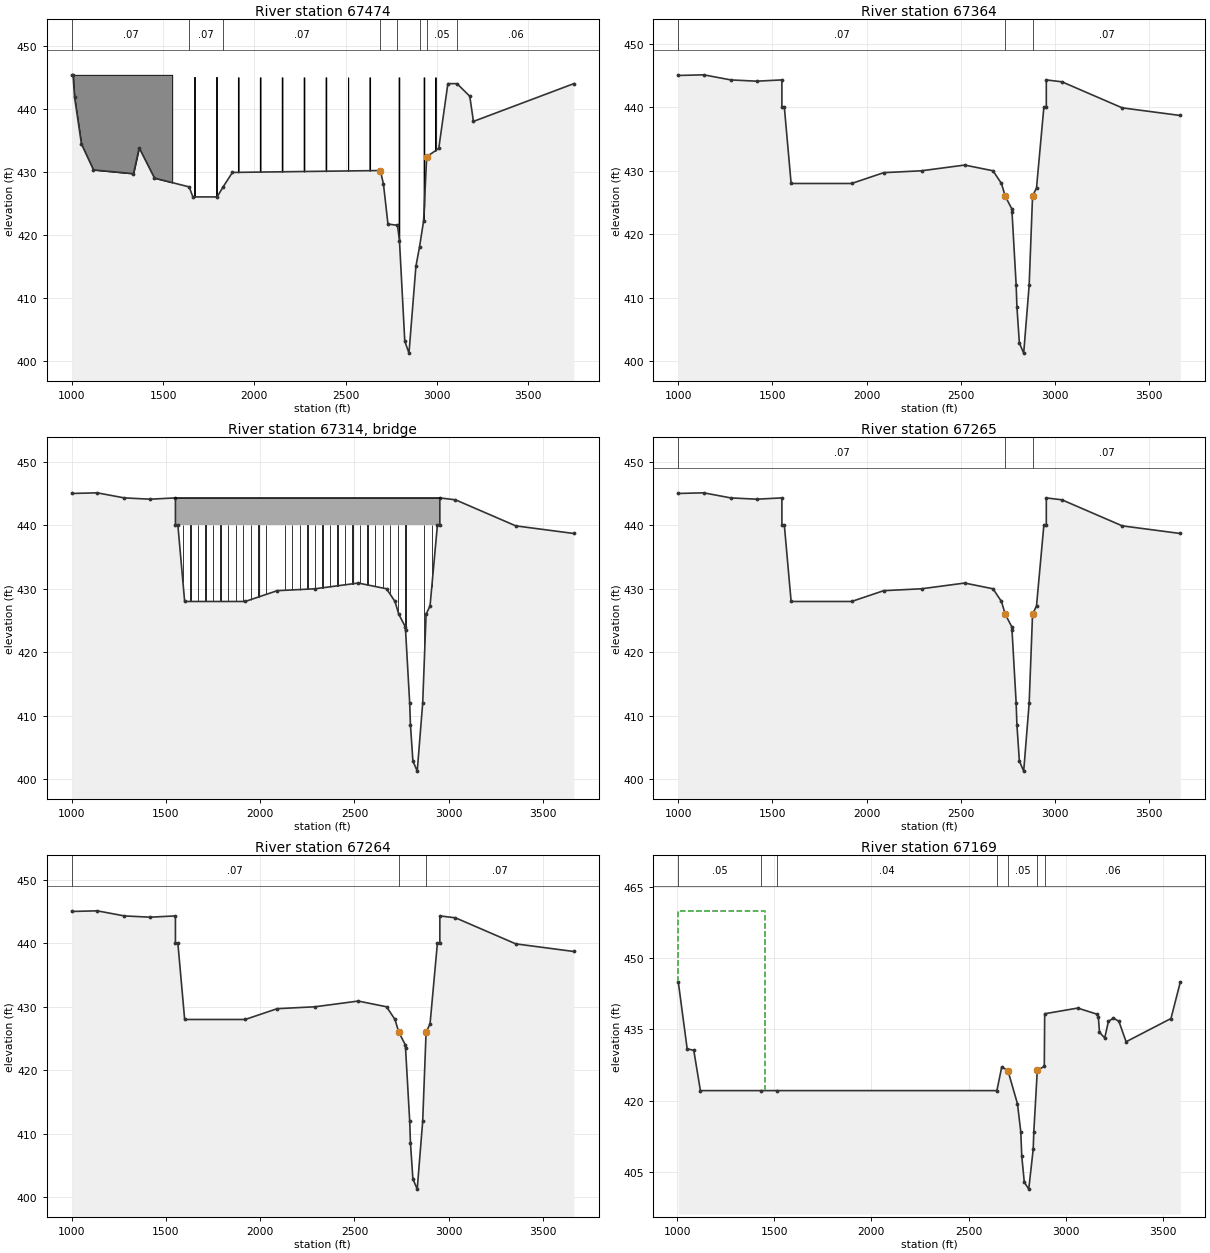
Type RM Length L Ch R = 1 ,67474   ,113,113,113
BEGIN DESCRIPTION:
This cross section corresponds to cross section 67474 of the non-georeferenced CDC model which was the source of this model.
---------------------------------------------------------------------
CDC CAR012102-1 President George Bush Turnpike
Cross-section 67474 - 110074
---------------------------------------------------------------------
END DESCRIPTION:
XS GIS Cut Line= 3
2449035.995989267020196.284166132447959.731081437019196.17199314
2446976.700567197018375.14804463
#Sta/Elev= 30
    1000   445.4    1007   445.4    1015   441.9    1053   434.4    1119   430.3
    1338   429.7    1369   433.8    1453     429    1643   427.6  1663.4  426.01
 1796.24  426.01 1827.56  427.54    1880   429.9    2690   430.2 2707.26  428.04
 2731.85   421.7    2784   421.5    2795     419    2824   403.1    2847   401.2
    2885     415    2905   418.1    2927   422.2    2944   432.4    3010   433.7
    3060     444    3110     444    3180     442    3200     438    3750     444
#Mann= 8 ,-1,0
    1000     .07       0    1643     .07       0 1827.56     .07       0
    2690     .05       0    2784     .05       0    2905     .07       0
    2944     .05       0    3110     .06       0
#Block Obstruct= 13 ,-1
    1000    1550   445.4    1670    1674     445    1790    1794     445
    1910    1914     445    2030    2034     445    2150    2154     445
    2270    2274     445    2390    2394     445 2513.51    2514     445
    2630    2634     445    2790    2794     445    2927    2931     445
    2990    2994     445
Bank Sta=2690,2944
XS Rating Curve= 0 ,0
Exp/Cntr=0.3,0.1

Type RM Length L Ch R = 1 ,67364   ,98,98,98
BEGIN DESCRIPTION:
This cross section corresponds to cross section 67364 of the non-georeferenced CDC model which was the source of this model.
END DESCRIPTION:
XS GIS Cut Line= 4
2449061.80860168 7020074.49766432448108.346597857019184.48664905
2448027.991443577019112.388696132447067.966788837018309.14620814
#Sta/Elev= 30
    1000     445    1135   445.1    1279   444.3    1416   444.1    1550   444.3
    1550     440    1563     440    1599     428    1920     428    2090   429.7
    2291     430    2520   430.9    2670     430    2715     428    2735     426
    2769  424.06    2771   423.5    2793     412    2797   408.6    2810   402.9
    2833   401.3    2862     412    2880     426    2901   427.3    2940     440
    2953     440    2953   444.3    3036     444    3356   439.9    3664   438.7
#Mann= 3 ,0,0
    1000     .07       0    2735     .05       0    2880     .07       0
Bank Sta=2735,2880
XS Rating Curve= 0 ,0
Exp/Cntr=0.5,0.3

Type RM Length L Ch R = 3 ,67314   ,,,
BEGIN DESCRIPTION:
Valley View Lane
END DESCRIPTION:
Node Name=Valley View Lane
Bridge Culvert--1,0,-1,-1, 0
Deck Dist Width WeirC Skew NumUp NumDn MinLoCord MaxHiCord MaxSubmerge Is_Ogee
2,95,2.6,0, 49, 49, , , 0.95, 0, ,,,
    1550    1589    1591    1628    1632    1709    1711    1748    1752    1829
    1831    1868    1872    1949    1951    1989    1991    2029    2031    2129
    2131    2169    2171    2171    2208    2212    2289    2291    2328    2332
    2409    2411    2448    2452    2529    2531    2568    2572    2649    2651
    2688    2692    2769    2771    2869    2871    2909    2911    2953
   444.3   444.3   444.3   444.3   444.3   444.3   444.3   444.3   444.3   444.3
   444.3   444.3   444.3   444.3   444.3   444.3   444.3   444.3   444.3   444.3
   444.3   444.3   444.3   444.3   444.3   444.3   444.3   444.3   444.3   444.3
   444.3   444.3   444.3   444.3   444.3   444.3   444.3   444.3   444.3   444.3
   444.3   444.3   444.3   444.3   444.3   444.3   444.3   444.3   444.3
     440     440     440     440     440     440     440     440     440     440
     440     440     440     440     440     440     440     440     440     440
     440     440     440     440     440     440     440     440     440     440
     440     440     440     440     440     440     440     440     440     440
     440     440     440     440     440     440     440     440     440
    1550    1589    1591    1628    1632    1709    1711    1748    1752    1829
    1831    1868    1872    1949    1951    1989    1991    2029    2031    2129
    2131    2169    2171    2171    2208    2212    2289    2291    2328    2332
    2409    2411    2448    2452    2529    2531    2568    2572    2649    2651
    2688    2692    2769    2771    2869    2871    2909    2911    2953
   444.3   444.3   444.3   444.3   444.3   444.3   444.3   444.3   444.3   444.3
   444.3   444.3   444.3   444.3   444.3   444.3   444.3   444.3   444.3   444.3
   444.3   444.3   444.3   444.3   444.3   444.3   444.3   444.3   444.3   444.3
   444.3   444.3   444.3   444.3   444.3   444.3   444.3   444.3   444.3   444.3
   444.3   444.3   444.3   444.3   444.3   444.3   444.3   444.3   444.3
     440     440     440     440     440     440     440     440     440     440
     440     440     440     440     440     440     440     440     440     440
     440     440     440     440     440     440     440     440     440     440
     440     440     440     440     440     440     440     440     440     440
     440     440     440     440     440     440     440     440     440
Pier Skew, UpSta & Num, DnSta & Num=  ,1590, 2 ,1590, 2 , 0 , 0 , 0 ,,
       2       2
     410     442
       2       2
     410     442
Pier Skew, UpSta & Num, DnSta & Num=  ,1630, 2 ,1630, 2 , 0 , 0 , 0 ,,
       2       2
     410     442
       2       2
     410     442
Pier Skew, UpSta & Num, DnSta & Num=  ,1670, 2 ,1670, 2 , 0 , 0 , 0 ,,
       2       2
     410     442
       2       2
     410     442
Pier Skew, UpSta & Num, DnSta & Num=  ,1710, 2 ,1710, 2 , 0 , 0 , 0 ,,
       2       2
     410     442
       2       2
     410     442
Pier Skew, UpSta & Num, DnSta & Num=  ,1750, 2 ,1750, 2 , 0 , 0 , 0 ,,
       2       2
     410     442
       2       2
     410     442
Pier Skew, UpSta & Num, DnSta & Num=  ,1790, 2 ,1790, 2 , 0 , 0 , 0 ,,
       2       2
     410     442
       2       2
     410     442
Pier Skew, UpSta & Num, DnSta & Num=  ,1830, 2 ,1830, 2 , 0 , 0 , 0 ,,
       2       2
     410     442
       2       2
     410     442
Pier Skew, UpSta & Num, DnSta & Num=  ,1870, 2 ,1870, 2 , 0 , 0 , 0 ,,
       2       2
     410     442
       2       2
     410     442
Pier Skew, UpSta & Num, DnSta & Num=  ,1910, 2 ,1910, 2 , 0 , 0 , 0 ,,
       2       2
     410     442
       2       2
     410     442
Pier Skew, UpSta & Num, DnSta & Num=  ,1950, 2 ,1950, 2 , 0 , 0 , 0 ,,
       2       2
     410     442
       2       2
     410     442
Pier Skew, UpSta & Num, DnSta & Num=  ,1990, 2 ,1990, 2 , 0 , 0 , 0 ,,
       2       2
     410     442
       2       2
     410     442
Pier Skew, UpSta & Num, DnSta & Num=  ,2030, 2 ,2030, 2 , 0 , 0 , 0 ,,
       2       2
     410     442
       2       2
     410     442
Pier Skew, UpSta & Num, DnSta & Num=  ,2130, 2 ,2130, 2 , 0 , 0 , 0 ,,
       2       2
     410     442
       2       2
     410     442
Pier Skew, UpSta & Num, DnSta & Num=  ,2170, 2 ,2170, 2 , 0 , 0 , 0 ,,
       2       2
     410     442
       2       2
     410     442
Pier Skew, UpSta & Num, DnSta & Num=  ,2210, 2 ,2210, 2 , 0 , 0 , 0 ,,
       2       2
     410     442
       2       2
     410     442
Pier Skew, UpSta & Num, DnSta & Num=  ,2250, 2 ,2250, 2 , 0 , 0 , 0 ,,
       2       2
     410     442
       2       2
     410     442
Pier Skew, UpSta & Num, DnSta & Num=  ,2290, 2 ,2290, 2 , 0 , 0 , 0 ,,
       2       2
     410     442
       2       2
     410     442
Pier Skew, UpSta & Num, DnSta & Num=  ,2330, 2 ,2330, 2 , 0 , 0 , 0 ,,
       2       2
     410     442
       2       2
     410     442
Pier Skew, UpSta & Num, DnSta & Num=  ,2370, 2 ,2370, 2 , 0 , 0 , 0 ,,
       2       2
     410     442
       2       2
     410     442
Pier Skew, UpSta & Num, DnSta & Num=  ,2410, 2 ,2410, 2 , 0 , 0 , 0 ,,
       2       2
     410     442
       2       2
     410     442
Pier Skew, UpSta & Num, DnSta & Num=  ,2450, 2 ,2450, 2 , 0 , 0 , 0 ,,
       2       2
     410     442
       2       2
     410     442
Pier Skew, UpSta & Num, DnSta & Num=  ,2490, 2 ,2490, 2 , 0 , 0 , 0 ,,
       2       2
     410     442
       2       2
     410     442
Pier Skew, UpSta & Num, DnSta & Num=  ,2530, 2 ,2530, 2 , 0 , 0 , 0 ,,
       2       2
     410     442
       2       2
     410     442
Pier Skew, UpSta & Num, DnSta & Num=  ,2570, 2 ,2570, 2 , 0 , 0 , 0 ,,
       2       2
     410     442
       2       2
     410     442
Pier Skew, UpSta & Num, DnSta & Num=  ,2610, 2 ,2610, 2 , 0 , 0 , 0 ,,
       2       2
     410     442
       2       2
     410     442
Pier Skew, UpSta & Num, DnSta & Num=  ,2650, 2 ,2650, 2 , 0 , 0 , 0 ,,
       2       2
     410     442
       2       2
     410     442
Pier Skew, UpSta & Num, DnSta & Num=  ,2690, 2 ,2690, 2 , 0 , 0 , 0 ,,
       2       2
     410     442
       2       2
     410     442
Pier Skew, UpSta & Num, DnSta & Num=  ,2730, 2 ,2730, 2 , 0 , 0 , 0 ,,
       2       2
     410     442
       2       2
     410     442
Pier Skew, UpSta & Num, DnSta & Num=  ,2770, 2 ,2770, 2 , 0 , 0 , 0 ,,
       2       2
     410     442
       2       2
     410     442
Pier Skew, UpSta & Num, DnSta & Num=  ,2870, 2 ,2870, 2 , 0 , 0 , 0 ,,
       2       2
     410     442
       2       2
     410     442
Pier Skew, UpSta & Num, DnSta & Num=  ,2910, 2 ,2910, 2 , 0 , 0 , 0 ,,
       2       2
     410     442
       2       2
     410     442
BR Coef= 1 , 0 , 0 ,1.05, 0 ,,,0.8,-1,0.5,1,
WSPro=,,,, 1 ,,,, 0 ,,,, 0 ,,,,-1 ,-1 ,-1 , 0 , 0 , 0 , 0 , 0
BC Design=,, 0 ,, 0 ,,,,,,
BC HTab HWMax=445.1
BC Use User HTab Curves=0
BC User HTab FreeFlow(D)= 0

Type RM Length L Ch R = 1 ,67265   ,1,1,1
BEGIN DESCRIPTION:
This cross section corresponds to cross section 67265 of the non-georeferenced CDC model which was the source of this model.
END DESCRIPTION:
XS GIS Cut Line= 4
2449119.763210187019997.30195256  2448169.327447 7019106.3460573
2448089.431937527019036.988584472447127.216998437018230.56336005
#Sta/Elev= 30
    1000     445    1135   445.1    1279   444.3    1416   444.1    1550   444.3
    1550     440    1563     440    1599     428    1920     428    2090   429.7
    2291     430    2520   430.9    2670     430    2715     428    2735     426
    2769  424.06    2771   423.5    2793     412    2797   408.6    2810   402.9
    2833   401.3    2862     412    2880     426    2901   427.3    2940     440
    2953     440    2953   444.3    3036     444    3356   439.9    3664   438.7
#Mann= 3 ,0,0
    1000     .07       0    2735     .05       0    2880     .07       0
Bank Sta=2735,2880
XS Rating Curve= 0 ,0
Exp/Cntr=0.5,0.3

Type RM Length L Ch R = 1 ,67264   ,94,94,94
BEGIN DESCRIPTION:
This cross section corresponds to cross section 67264 of the non-georeferenced CDC model which was the source of this model.
END DESCRIPTION:
XS GIS Cut Line= 4
2449120.164128017019996.349854722448169.94555601 7019105.5586573
2448090.052671167019036.227103052447127.622509427018229.60732521
#Sta/Elev= 30
    1000     445    1135   445.1    1279   444.3    1416   444.1    1550   444.3
    1550     440    1563     440    1599     428    1920     428    2090   429.7
    2291     430    2520   430.9    2670     430    2715     428    2735     426
    2769  424.06    2771   423.5    2793     412    2797   408.6    2810   402.9
    2833   401.3    2862     412    2880     426    2901   427.3    2940     440
    2953     440    2953   444.3    3036     444    3356   439.9    3664   438.7
#Mann= 3 ,0,0
    1000     .07       0    2735     .05       0    2880     .07       0
Bank Sta=2735,2880
XS Rating Curve= 0 ,0
Exp/Cntr=0.3,0.1

Type RM Length L Ch R = 1 ,67169   ,769,1009,899
BEGIN DESCRIPTION:
This cross section corresponds to cross section 67169 of the non-georeferenced CDC model which was the source of this model.
LOMR#14-06-2597P & CDC# FB100113-1 Mercer Crossing
Cross-sections 67169 & 62351.  Fill was added in innefective flow area so no physical cross-section change.
END DESCRIPTION:
XS GIS Cut Line= 3
2449158.240167357019905.903185222448228.452000687019030.56504089
2447227.433005337018190.19861138
#Sta/Elev= 30
    1006   445.1    1052   430.9    1086   430.6    1120   422.1    1433   422.1
    1516   422.1    2646   422.1    2671   427.1    2703   426.3    2752   419.3
    2769   413.4    2774   408.3    2787   402.8    2810  401.33    2833   409.8
    2836   413.4    2854   426.4    2890   427.2    2892   438.3    3062   439.5
    3162   438.2    3168   437.7    3174   434.4    3201   433.2    3220   436.7
    3246   437.4    3274   436.7    3311   432.4    3542   437.3    3590     445
#Mann= 7 ,-1,0
    1006     .05       0    1433     .03       0    1516     .04       0
    2646     .08       0    2703     .05       0    2854     .08       0
    2892     .06       0
#XS Ineff= 2 , 0
            1450     460
Permanent Ineff=
       F       F
Bank Sta=2703,2854
XS Rating Curve= 0 ,0
Exp/Cntr=0.3,0.1

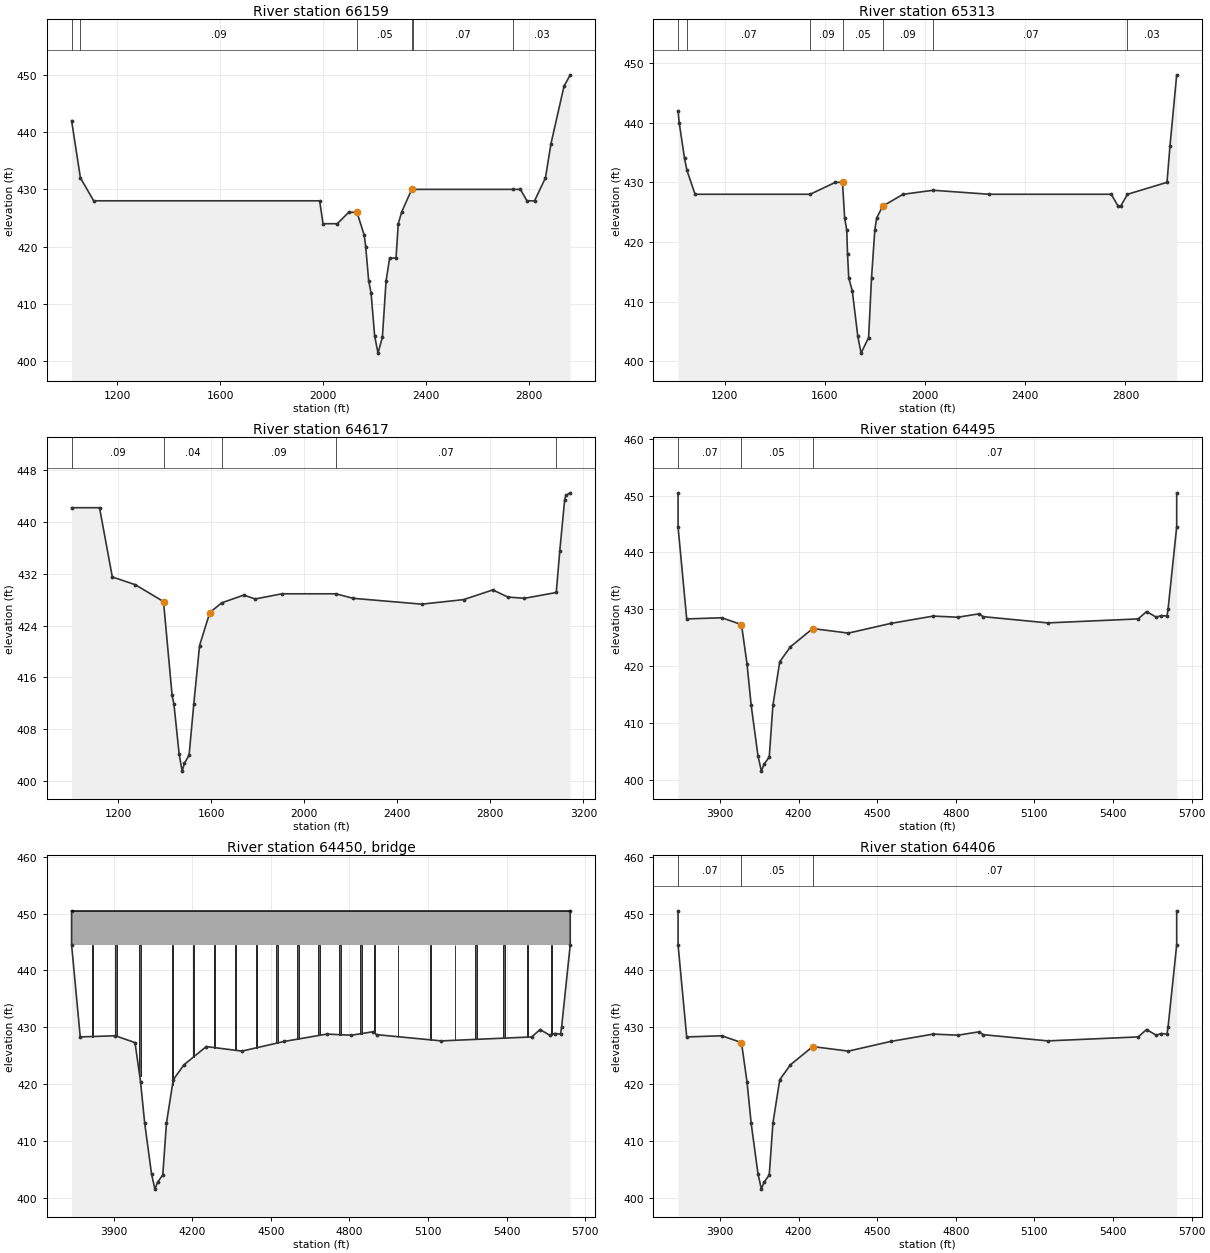
Type RM Length L Ch R = 1 ,66159   ,851,847,400
BEGIN DESCRIPTION:
This cross section corresponds to cross section 66159 of the non-georeferenced CDC model which was the source of this model.
END DESCRIPTION:
XS GIS Cut Line= 4
2449603.804564927019282.871622892448816.365851077018533.54306905
2448747.909951277018308.544175222448264.921087837017927.13942622
#Sta/Elev= 30
  1022.3     442  1056.6     432  1108.3     428  1986.3     428  1999.2     424
  2054.6     424  2099.3     426  2131.2     426  2159.4     422  2165.1     420
  2176.8     414    2186   411.9    2200   404.4    2213   401.4    2230   404.2
  2244.3     414  2258.1     418    2283     418  2291.7     424  2304.6     426
    2344     430  2349.3     430  2736.8     430  2766.1     430  2791.8     428
  2821.3     428  2863.6     432  2885.2     438  2935.7     448  2959.9     450
#Mann= 6 ,-1,0
  1022.3     .03       0  1056.6     .09       0  2131.2     .05       0
    2344     .09       0  2349.3     .07       0  2736.8     .03       0
Bank Sta=2131.2,2344
XS Rating Curve= 0 ,0
Exp/Cntr=0.3,0.1

Type RM Length L Ch R = 1 ,65313   ,951,697,351
BEGIN DESCRIPTION:
This cross section corresponds to cross section 65313 of the non-georeferenced CDC model which was the source of this model.
END DESCRIPTION:
XS GIS Cut Line= 3
2450159.545579437018554.918682472449482.115831917018088.76508722
2448328.394386087017910.71393414
#Sta/Elev= 30
  1014.7     442  1019.2     440  1040.5     434  1050.2     432  1082.5     428
  1541.9     428  1642.4     430  1670.9     430  1679.5     424  1687.9     422
  1690.9     418  1695.8     414    1710   411.8    1732   404.2    1745   401.4
    1775     404  1786.8  414.06  1799.8     422  1807.1     424  1830.8     426
  1912.7     428  2032.7  428.67  2256.5     428  2743.4     428  2770.7     426
  2780.6     426  2808.1     428  2965.8     430  2977.4     436  3004.4     448
#Mann= 7 ,-1,0
  1014.7     .03       0  1050.2     .07       0  1541.9     .09       0
  1670.9     .05       0  1830.8     .09       0  2032.7     .07       0
  2808.1     .03       0
Bank Sta=1670.9,1830.8
XS Rating Curve= 0 ,0
Exp/Cntr=0.3,0.1

Type RM Length L Ch R = 1 ,64617   ,131,131,131
BEGIN DESCRIPTION:
This cross section corresponds to cross section 64617 of the non-georeferenced CDC model which was the source of this model.
END DESCRIPTION:
XS GIS Cut Line= 3
2450379.504128997017430.195210132448417.995912917017922.35433079
2448298.746479517017903.75791129
#Sta/Elev= 30
    1000   442.2    1120   442.2    1175   431.5    1274   430.3    1395   427.7
    1432   413.2    1440   411.8    1462   404.2    1475   401.5    1485   402.7
    1505     404    1525   411.8    1550   420.9    1594     426    1645   427.5
    1740   428.7    1789   428.1    1904   428.9    2136   428.9    2210   428.2
    2505   427.3    2685     428    2810   429.5    2875   428.4    2946   428.2
    3083   429.1    3098   435.5    3119   443.4    3124   444.1    3143   444.5
#Mann= 5 ,-1,0
    1000     .09       0    1395     .04       0    1645     .09       0
    2136     .07       0    3083     .03       0
Bank Sta=1395,1594
XS Rating Curve= 0 ,0
Exp/Cntr=0.3,0.1

Type RM Length L Ch R = 1 ,64495   ,90,90,90
BEGIN DESCRIPTION:
This cross section corresponds to cross section 64495 of the non-georeferenced CDC model which was the source of this model.
END DESCRIPTION:
XS GIS Cut Line= 2
2450255.885609847017341.984428552448410.824667427017807.98710546
#Sta/Elev= 30
    3740   450.5    3740   444.5    3773   428.3    3907   428.5    3982   427.3
    4003  420.44    4019   413.1    4045   404.2    4058   401.5    4068   402.7
    4088     404    4102   413.1    4128  420.76    4169   423.4    4254   426.6
    4390   425.8    4551   427.5    4714   428.8    4808   428.6    4889   429.2
    4904   428.7    5151   427.6    5496   428.3    5528   429.6    5565   428.6
    5584   428.9    5606   428.8    5610     430    5643   444.5    5643   450.5
#Mann= 3 ,0,0
    3740     .07       0    3982     .05       0    4254     .07       0
Bank Sta=3982,4254
XS Rating Curve= 0 ,0
Exp/Cntr=0.5,0.3

Type RM Length L Ch R = 3 ,64450   ,,,
BEGIN DESCRIPTION:
IH 635/LBJ Freeway West Bound
END DESCRIPTION:
Node Name=IH 635
Bridge Culvert--1,0,-1,-1, 0
Deck Dist Width WeirC Skew NumUp NumDn MinLoCord MaxHiCord MaxSubmerge Is_Ogee
2,85,2.6,0, 44, 44, , , 0.95, 0, ,,,
    3740    3817    3823    3907    3913    3997    4003    4122    4128    4202
    4208    4282    4288    4362    4368    4442    4448    4522    4528    4602
    4608    4682    4688    4762    4768    4842    4848  4893.5  4896.5  4984.5
  4987.5  5109.5  5112.5  5201.5  5204.5    5283    5289    5387    5393    5477
    5483    5567    5573    5643
   450.5   450.5   450.5   450.5   450.5   450.5   450.5   450.5   450.5   450.5
   450.5   450.5   450.5   450.5   450.5   450.5   450.5   450.5   450.5   450.5
   450.5   450.5   450.5   450.5   450.5   450.5   450.5   450.5   450.5   450.5
   450.5   450.5   450.5   450.5   450.5   450.5   450.5   450.5   450.5   450.5
   450.5   450.5   450.5   450.5
   444.5   444.5   444.5   444.5   444.5   444.5   444.5   444.5   444.5   444.5
   444.5   444.5   444.5   444.5   444.5   444.5   444.5   444.5   444.5   444.5
   444.5   444.5   444.5   444.5   444.5   444.5   444.5   444.5   444.5   444.5
   444.5   444.5   444.5   444.5   444.5   444.5   444.5   444.5   444.5   444.5
   444.5   444.5   444.5   444.5
    3740    3817    3823    3907    3913    3997    4003    4122    4128    4202
    4208    4282    4288    4362    4368    4442    4448    4522    4528    4602
    4608    4682    4688    4762    4768    4842    4848  4893.5  4896.5  4984.5
  4987.5  5109.5  5112.5  5201.5  5204.5    5283    5289    5387    5393    5477
    5483    5567    5573    5643
   450.5   450.5   450.5   450.5   450.5   450.5   450.5   450.5   450.5   450.5
   450.5   450.5   450.5   450.5   450.5   450.5   450.5   450.5   450.5   450.5
   450.5   450.5   450.5   450.5   450.5   450.5   450.5   450.5   450.5   450.5
   450.5   450.5   450.5   450.5   450.5   450.5   450.5   450.5   450.5   450.5
   450.5   450.5   450.5   450.5
   444.5   444.5   444.5   444.5   444.5   444.5   444.5   444.5   444.5   444.5
   444.5   444.5   444.5   444.5   444.5   444.5   444.5   444.5   444.5   444.5
   444.5   444.5   444.5   444.5   444.5   444.5   444.5   444.5   444.5   444.5
   444.5   444.5   444.5   444.5   444.5   444.5   444.5   444.5   444.5   444.5
   444.5   444.5   444.5   444.5
Pier Skew, UpSta & Num, DnSta & Num=  ,3820, 2 ,3820, 2 , 0 , 0 , 0 ,,
       6       6
     415     450
       6       6
     415     450
Pier Skew, UpSta & Num, DnSta & Num=  ,3910, 2 ,3910, 2 , 0 , 0 , 0 ,,
       6       6
     415     450
       6       6
     415     450
Pier Skew, UpSta & Num, DnSta & Num=  ,4000, 2 ,4000, 2 , 0 , 0 , 0 ,,
       6       6
     415     450
       6       6
     415     450
Pier Skew, UpSta & Num, DnSta & Num=  ,4125, 2 ,4125, 2 , 0 , 0 , 0 ,,
       6       6
     415     450
       6       6
     415     450
Pier Skew, UpSta & Num, DnSta & Num=  ,4205, 2 ,4205, 2 , 0 , 0 , 0 ,,
       6       6
     415     450
       6       6
     415     450
Pier Skew, UpSta & Num, DnSta & Num=  ,4285, 2 ,4285, 2 , 0 , 0 , 0 ,,
       6       6
     415     450
       6       6
     415     450
Pier Skew, UpSta & Num, DnSta & Num=  ,4365, 2 ,4365, 2 , 0 , 0 , 0 ,,
       6       6
     415     450
       6       6
     415     450
Pier Skew, UpSta & Num, DnSta & Num=  ,4445, 2 ,4445, 2 , 0 , 0 , 0 ,,
       6       6
     415     450
       6       6
     415     450
Pier Skew, UpSta & Num, DnSta & Num=  ,4525, 2 ,4525, 2 , 0 , 0 , 0 ,,
       6       6
     415     450
       6       6
     415     450
Pier Skew, UpSta & Num, DnSta & Num=  ,4605, 2 ,4605, 2 , 0 , 0 , 0 ,,
       6       6
     415     450
       6       6
     415     450
Pier Skew, UpSta & Num, DnSta & Num=  ,4685, 2 ,4685, 2 , 0 , 0 , 0 ,,
       6       6
     415     450
       6       6
     415     450
Pier Skew, UpSta & Num, DnSta & Num=  ,4765, 2 ,4765, 2 , 0 , 0 , 0 ,,
       6       6
     415     450
       6       6
     415     450
Pier Skew, UpSta & Num, DnSta & Num=  ,4845, 2 ,4845, 2 , 0 , 0 , 0 ,,
       6       6
     415     450
       6       6
     415     450
Pier Skew, UpSta & Num, DnSta & Num=  ,4895, 2 ,4895, 2 , 0 , 0 , 0 ,,
       3       3
     415     450
       3       3
     415     450
Pier Skew, UpSta & Num, DnSta & Num=  ,4986, 2 ,4986, 2 , 0 , 0 , 0 ,,
       3       3
     415     450
       3       3
     415     450
Pier Skew, UpSta & Num, DnSta & Num=  ,5111, 2 ,5111, 2 , 0 , 0 , 0 ,,
       3       3
     415     450
       3       3
     415     450
Pier Skew, UpSta & Num, DnSta & Num=  ,5203, 2 ,5203, 2 , 0 , 0 , 0 ,,
       3       3
     415     450
       3       3
     415     450
Pier Skew, UpSta & Num, DnSta & Num=  ,5283, 2 ,5283, 2 , 0 , 0 , 0 ,,
       6       6
     415     450
       6       6
     415     450
Pier Skew, UpSta & Num, DnSta & Num=  ,5390, 2 ,5390, 2 , 0 , 0 , 0 ,,
       6       6
     415     450
       6       6
     415     450
Pier Skew, UpSta & Num, DnSta & Num=  ,5480, 2 ,5480, 2 , 0 , 0 , 0 ,,
       6       6
     415     450
       6       6
     415     450
Pier Skew, UpSta & Num, DnSta & Num=  ,5571, 2 ,5571, 2 , 0 , 0 , 0 ,,
       6       6
     415     450
       6       6
     415     450
BR Coef= 1 , 0 , 0 ,1.05, 0 ,,,0.8,-1,0.5,1,
WSPro=,,,, 1 ,,,, 0 ,,,, 0 ,,,,-1 ,-1 ,-1 , 0 , 0 , 0 , 0 , 0
BC Design=,, 0 ,, 0 ,,,,,,
BC HTab HWMax=450.5
BC Use User HTab Curves=0
BC User HTab FreeFlow(D)= 0

Type RM Length L Ch R = 1 ,64406   ,1,1,1
BEGIN DESCRIPTION:
This cross section corresponds to cross section 64406 of the non-georeferenced CDC model which was the source of this model.
END DESCRIPTION:
XS GIS Cut Line= 2
2450277.056499247017249.557776142448432.189782177017716.32948038
#Sta/Elev= 30
    3740   450.5    3740   444.5    3773   428.3    3907   428.5    3982   427.3
    4003  420.44    4019   413.1    4045   404.2    4058   401.5    4068   402.7
    4088     404    4102   413.1    4128  420.76    4169   423.4    4254   426.6
    4390   425.8    4551   427.5    4714   428.8    4808   428.6    4889   429.2
    4904   428.7    5151   427.6    5496   428.3    5528   429.6    5565   428.6
    5584   428.9    5606   428.8    5610     430    5643   444.5    5643   450.5
#Mann= 3 ,0,0
    3740     .07       0    3982     .05       0    4254     .07       0
Bank Sta=3982,4254
XS Rating Curve= 0 ,0
Exp/Cntr=0.5,0.3

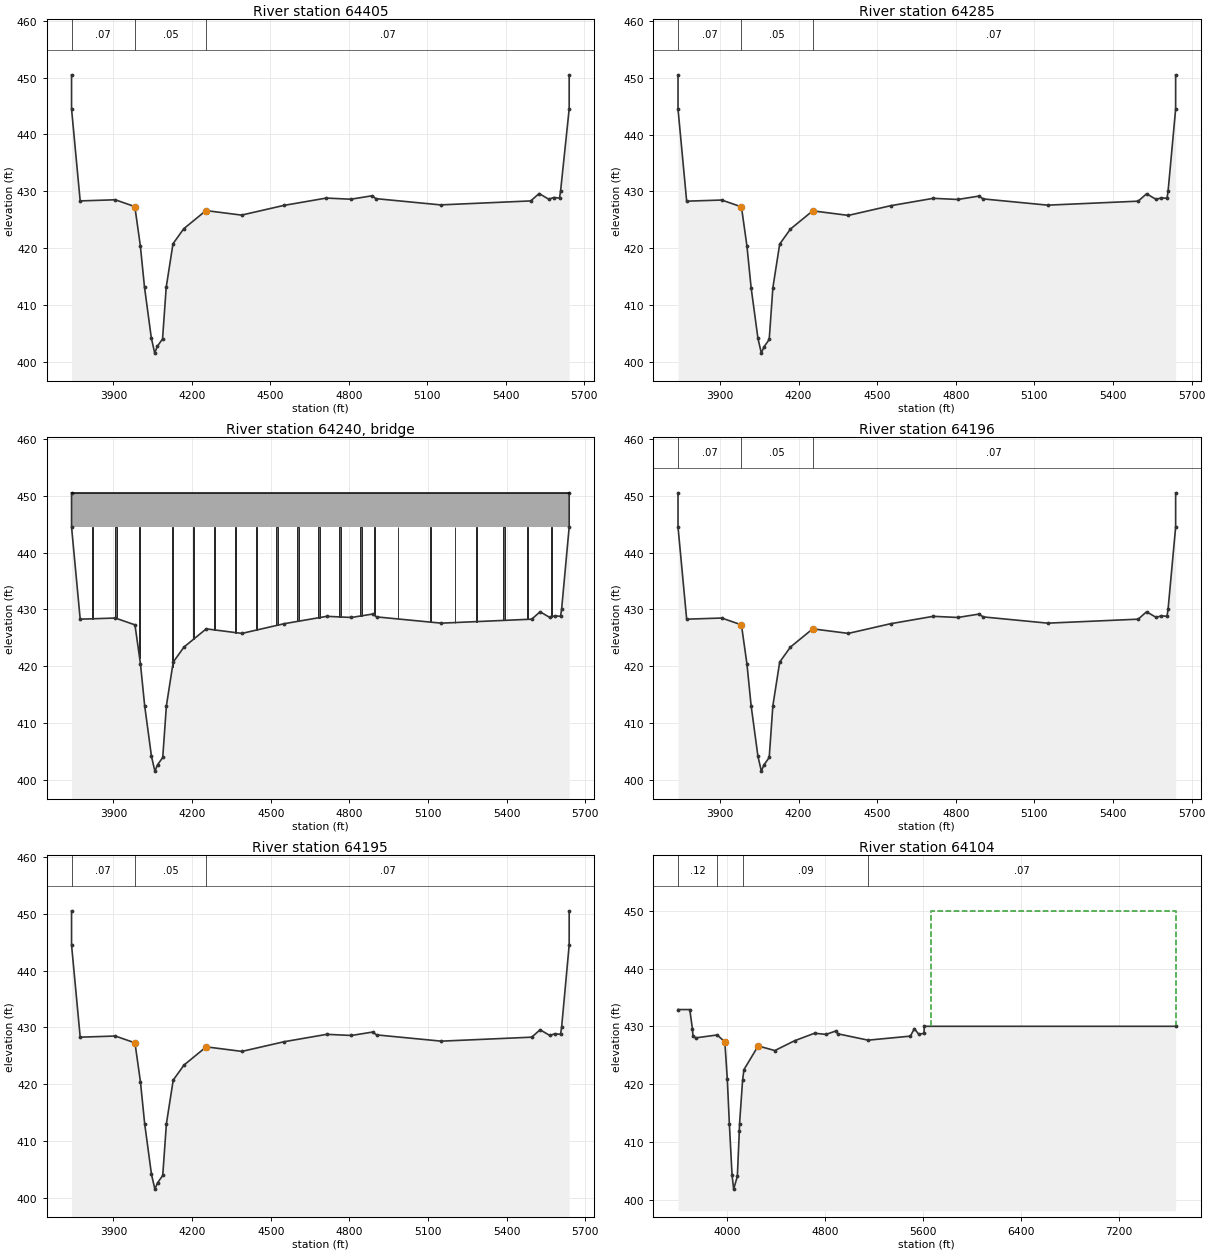
Type RM Length L Ch R = 1 ,64405   ,117,117,117
BEGIN DESCRIPTION:
This cross section corresponds to cross section 64405 of the non-georeferenced CDC model which was the source of this model.
END DESCRIPTION:
XS GIS Cut Line= 2
2450277.07618424 7017248.57418232448432.211763777017715.35441671
#Sta/Elev= 30
    3740   450.5    3740   444.5    3773   428.3    3907   428.5    3982   427.3
    4003  420.44    4019   413.1    4045   404.2    4058   401.5    4068   402.7
    4088     404    4102   413.1    4128  420.76    4169   423.4    4254   426.6
    4390   425.8    4551   427.5    4714   428.8    4808   428.6    4889   429.2
    4904   428.7    5151   427.6    5496   428.3    5528   429.6    5565   428.6
    5584   428.9    5606   428.8    5610     430    5643   444.5    5643   450.5
#Mann= 3 ,0,0
    3740     .07       0    3982     .05       0    4254     .07       0
Bank Sta=3982,4254
XS Rating Curve= 0 ,0
Exp/Cntr=0.5,0.3

Type RM Length L Ch R = 1 ,64285   ,85,85,85
BEGIN DESCRIPTION:
This cross section corresponds to cross section 64285 of the non-georeferenced CDC model which was the source of this model.
END DESCRIPTION:
XS GIS Cut Line= 2
2450279.475457677017130.556373722448438.749152247017597.38286789
#Sta/Elev= 30
    3740   450.5    3740   444.5    3773   428.3    3907   428.5    3982   427.3
    4003  420.44    4019   413.1    4045   404.2    4058   401.6    4068   402.7
    4088     404    4102   413.1    4128  420.76    4169   423.4    4254   426.6
    4390   425.8    4551   427.5    4714   428.8    4808   428.6    4889   429.2
    4904   428.7    5151   427.6    5496   428.3    5528   429.6    5565   428.6
    5584   428.9    5606   428.8    5610     430    5639   444.5    5639   450.5
#Mann= 3 ,0,0
    3740     .07       0    3982     .05       0    4254     .07       0
Bank Sta=3982,4254
XS Rating Curve= 0 ,0
Exp/Cntr=0.5,0.3

Type RM Length L Ch R = 3 ,64240   ,,,
BEGIN DESCRIPTION:
IH 635/L BJ Freeway East Bound
END DESCRIPTION:
Node Name=IH 635
Bridge Culvert--1,0,-1,-1, 0
Deck Dist Width WeirC Skew NumUp NumDn MinLoCord MaxHiCord MaxSubmerge Is_Ogee
2,82,2.6,0, 45, 45, , , 0.95, 0, ,,,
    3740    3817    3823    3907    3913    3997    4003    4122    4128    4202
    4208    4282    4288    4362    4368    4368    4442    4448    4522    4528
    4602    4608    4682    4688    4762    4768    4842    4848  4893.5  4896.5
  4984.5  4987.5  5109.5  5112.5  5201.5  5204.5    5283    5289    5387    5393
    5477    5483    5568    5574    5639
   450.5   450.5   450.5   450.5   450.5   450.5   450.5   450.5   450.5   450.5
   450.5   450.5   450.5   450.5   450.5   450.5   450.5   450.5   450.5   450.5
   450.5   450.5   450.5   450.5   450.5   450.5   450.5   450.5   450.5   450.5
   450.5   450.5   450.5   450.5   450.5   450.5   450.5   450.5   450.5   450.5
   450.5   450.5   450.5   450.5   450.5
   444.5   444.5   444.5   444.5   444.5   444.5   444.5   444.5   444.5   444.5
   444.5   444.5   444.5   444.5   444.5   444.5   444.5   444.5   444.5   444.5
   444.5   444.5   444.5   444.5   444.5   444.5   444.5   444.5   444.5   444.5
   444.5   444.5   444.5   444.5   444.5   444.5   444.5   444.5   444.5   444.5
   444.5   444.5   444.5   444.5   444.5
    3740    3817    3823    3907    3913    3997    4003    4122    4128    4202
    4208    4282    4288    4362    4368    4368    4442    4448    4522    4528
    4602    4608    4682    4688    4762    4768    4842    4848  4893.5  4896.5
  4984.5  4987.5  5109.5  5112.5  5201.5  5204.5    5283    5289    5387    5393
    5477    5483    5568    5574    5639
   450.5   450.5   450.5   450.5   450.5   450.5   450.5   450.5   450.5   450.5
   450.5   450.5   450.5   450.5   450.5   450.5   450.5   450.5   450.5   450.5
   450.5   450.5   450.5   450.5   450.5   450.5   450.5   450.5   450.5   450.5
   450.5   450.5   450.5   450.5   450.5   450.5   450.5   450.5   450.5   450.5
   450.5   450.5   450.5   450.5   450.5
   444.5   444.5   444.5   444.5   444.5   444.5   444.5   444.5   444.5   444.5
   444.5   444.5   444.5   444.5   444.5   444.5   444.5   444.5   444.5   444.5
   444.5   444.5   444.5   444.5   444.5   444.5   444.5   444.5   444.5   444.5
   444.5   444.5   444.5   444.5   444.5   444.5   444.5   444.5   444.5   444.5
   444.5   444.5   444.5   444.5   444.5
Pier Skew, UpSta & Num, DnSta & Num=  ,3820, 2 ,3820, 2 , 0 , 0 , 0 ,,
       6       6
     415     450
       6       6
     415     450
Pier Skew, UpSta & Num, DnSta & Num=  ,3910, 2 ,3910, 2 , 0 , 0 , 0 ,,
       6       6
     415     450
       6       6
     415     450
Pier Skew, UpSta & Num, DnSta & Num=  ,4000, 2 ,4000, 2 , 0 , 0 , 0 ,,
       6       6
     415     450
       6       6
     415     450
Pier Skew, UpSta & Num, DnSta & Num=  ,4125, 2 ,4125, 2 , 0 , 0 , 0 ,,
       6       6
     415     450
       6       6
     415     450
Pier Skew, UpSta & Num, DnSta & Num=  ,4205, 2 ,4205, 2 , 0 , 0 , 0 ,,
       6       6
     415     450
       6       6
     415     450
Pier Skew, UpSta & Num, DnSta & Num=  ,4285, 2 ,4285, 2 , 0 , 0 , 0 ,,
       6       6
     415     450
       6       6
     415     450
Pier Skew, UpSta & Num, DnSta & Num=  ,4365, 2 ,4365, 2 , 0 , 0 , 0 ,,
       6       6
     415     450
       6       6
     415     450
Pier Skew, UpSta & Num, DnSta & Num=  ,4445, 2 ,4445, 2 , 0 , 0 , 0 ,,
       6       6
     415     450
       6       6
     415     450
Pier Skew, UpSta & Num, DnSta & Num=  ,4525, 2 ,4525, 2 , 0 , 0 , 0 ,,
       6       6
     415     450
       6       6
     415     450
Pier Skew, UpSta & Num, DnSta & Num=  ,4605, 2 ,4605, 2 , 0 , 0 , 0 ,,
       6       6
     415     450
       6       6
     415     450
Pier Skew, UpSta & Num, DnSta & Num=  ,4685, 2 ,4685, 2 , 0 , 0 , 0 ,,
       6       6
     415     450
       6       6
     415     450
Pier Skew, UpSta & Num, DnSta & Num=  ,4765, 2 ,4765, 2 , 0 , 0 , 0 ,,
       6       6
     415     450
       6       6
     415     450
Pier Skew, UpSta & Num, DnSta & Num=  ,4845, 2 ,4845, 2 , 0 , 0 , 0 ,,
       6       6
     415     450
       6       6
     415     450
Pier Skew, UpSta & Num, DnSta & Num=  ,4895, 2 ,4895, 2 , 0 , 0 , 0 ,,
       3       3
     415     450
       3       3
     415     450
Pier Skew, UpSta & Num, DnSta & Num=  ,4986, 2 ,4986, 2 , 0 , 0 , 0 ,,
       3       3
     415     450
       3       3
     415     450
Pier Skew, UpSta & Num, DnSta & Num=  ,5111, 2 ,5111, 2 , 0 , 0 , 0 ,,
       3       3
     415     450
       3       3
     415     450
Pier Skew, UpSta & Num, DnSta & Num=  ,5203, 2 ,5203, 2 , 0 , 0 , 0 ,,
       3       3
     415     450
       3       3
     415     450
Pier Skew, UpSta & Num, DnSta & Num=  ,5285, 2 ,5285, 2 , 0 , 0 , 0 ,,
       6       6
     415     450
       6       6
     415     450
Pier Skew, UpSta & Num, DnSta & Num=  ,5390, 2 ,5390, 2 , 0 , 0 , 0 ,,
       6       6
     415     450
       6       6
     415     450
Pier Skew, UpSta & Num, DnSta & Num=  ,5480, 2 ,5480, 2 , 0 , 0 , 0 ,,
       6       6
     415     450
       6       6
     415     450
Pier Skew, UpSta & Num, DnSta & Num=  ,5571, 2 ,5571, 2 , 0 , 0 , 0 ,,
       6       6
     415     450
       6       6
     415     450
BR Coef= 1 , 0 , 0 ,1.05, 0 ,,,0.8,-1,0.5,1,
WSPro=,,,, 1 ,,,, 0 ,,,, 0 ,,,,-1 ,-1 ,-1 , 0 , 0 , 0 , 0 , 0
BC Design=,, 0 ,, 0 ,,,,,,
BC HTab HWMax=450.5
BC Use User HTab Curves=0
BC User HTab FreeFlow(D)= 0

Type RM Length L Ch R = 1 ,64196   ,1,1,1
BEGIN DESCRIPTION:
This cross section corresponds to cross section 64196 of the non-georeferenced CDC model which was the source of this model.
END DESCRIPTION:
XS GIS Cut Line= 2
2450271.562415757017045.48863047 2448431.02803917017513.07102863
#Sta/Elev= 30
    3740   450.5    3740   444.5    3773   428.3    3907   428.5    3982   427.3
    4003  420.44    4019   413.1    4045   404.2    4058   401.6    4068   402.7
    4088     404    4102   413.1    4128  420.76    4169   423.4    4254   426.6
    4390   425.8    4551   427.5    4714   428.8    4808   428.6    4889   429.2
    4904   428.7    5151   427.6    5496   428.3    5528   429.6    5565   428.6
    5584   428.9    5606   428.8    5610     430    5639   444.5    5639   450.5
#Mann= 3 ,0,0
    3740     .07       0    3982     .05       0    4254     .07       0
Bank Sta=3982,4254
XS Rating Curve= 0 ,0
Exp/Cntr=0.5,0.3

Type RM Length L Ch R = 1 ,64195   ,86,86,86
BEGIN DESCRIPTION:
This cross section corresponds to cross section 64195 of the non-georeferenced CDC model which was the source of this model.
END DESCRIPTION:
XS GIS Cut Line= 2
2450271.582756947017044.505036642448431.050348767017512.09629305
#Sta/Elev= 30
    3740   450.5    3740   444.5    3773   428.3    3907   428.5    3982   427.3
    4003  420.44    4019   413.1    4045   404.2    4058   401.6    4068   402.7
    4088     404    4102   413.1    4128  420.76    4169   423.4    4254   426.6
    4390   425.8    4551   427.5    4714   428.8    4808   428.6    4889   429.2
    4904   428.7    5151   427.6    5496   428.3    5528   429.6    5565   428.6
    5584   428.9    5606   428.8    5610     430    5639   444.5    5639   450.5
#Mann= 3 ,0,0
    3740     .07       0    3982     .05       0    4254     .07       0
Bank Sta=3982,4254
XS Rating Curve= 0 ,0
Exp/Cntr=0.3,0.1

Type RM Length L Ch R = 1 ,64104   ,751,724,721
BEGIN DESCRIPTION:
This cross section corresponds to cross section 64104 of the non-georeferenced CDC model which was the source of this model.
END DESCRIPTION:
XS GIS Cut Line= 3
2450389.696037777016925.415707892448393.332576427017433.48293322
2446455.115480987017926.75212034
#Sta/Elev= 30
    3600   432.9    3696   432.9    3718   429.5    3722   428.3    3745     428
    3920   428.5    3982   427.3    4002   420.9    4019   413.1    4041   404.2
    4054   401.8    4084     404    4100   411.8    4102   413.1    4127   420.7
    4138   422.5    4254   426.6    4390   425.8    4551   427.5    4714   428.8
    4808   428.6    4889   429.2    4904   428.7    5151   427.6    5496   428.3
    5528   429.6    5565   428.6    5606   428.8    5610     430    7660     430
#Mann= 4 ,-1,0
    3600     .12       0    3920     .05       0    4127     .09       0
    5151     .07       0
#XS Ineff= 2 , 0
                            5660             450
Permanent Ineff=
       F       F
Bank Sta=3982,4254
XS Rating Curve= 0 ,0
Exp/Cntr=0.3,0.1