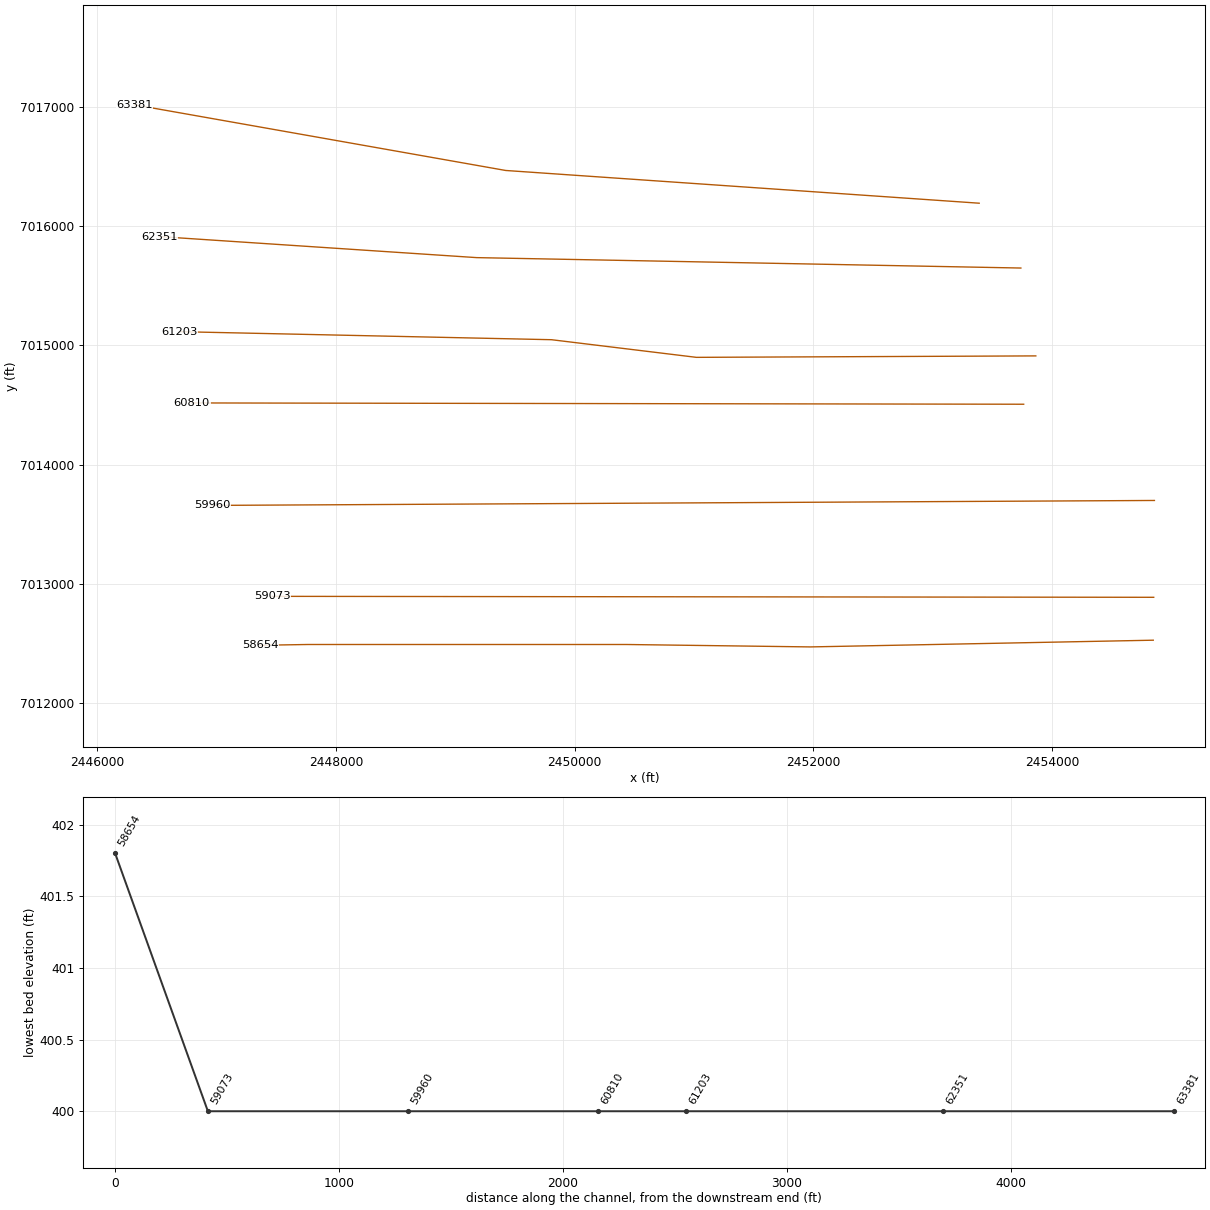
HEC-RAS study CDC_Consolidated_Model.prj: Upper Trinity CDC Consolidated Model

--- CDC_Consolidated_Model.g13 (geometry) --- (continued)

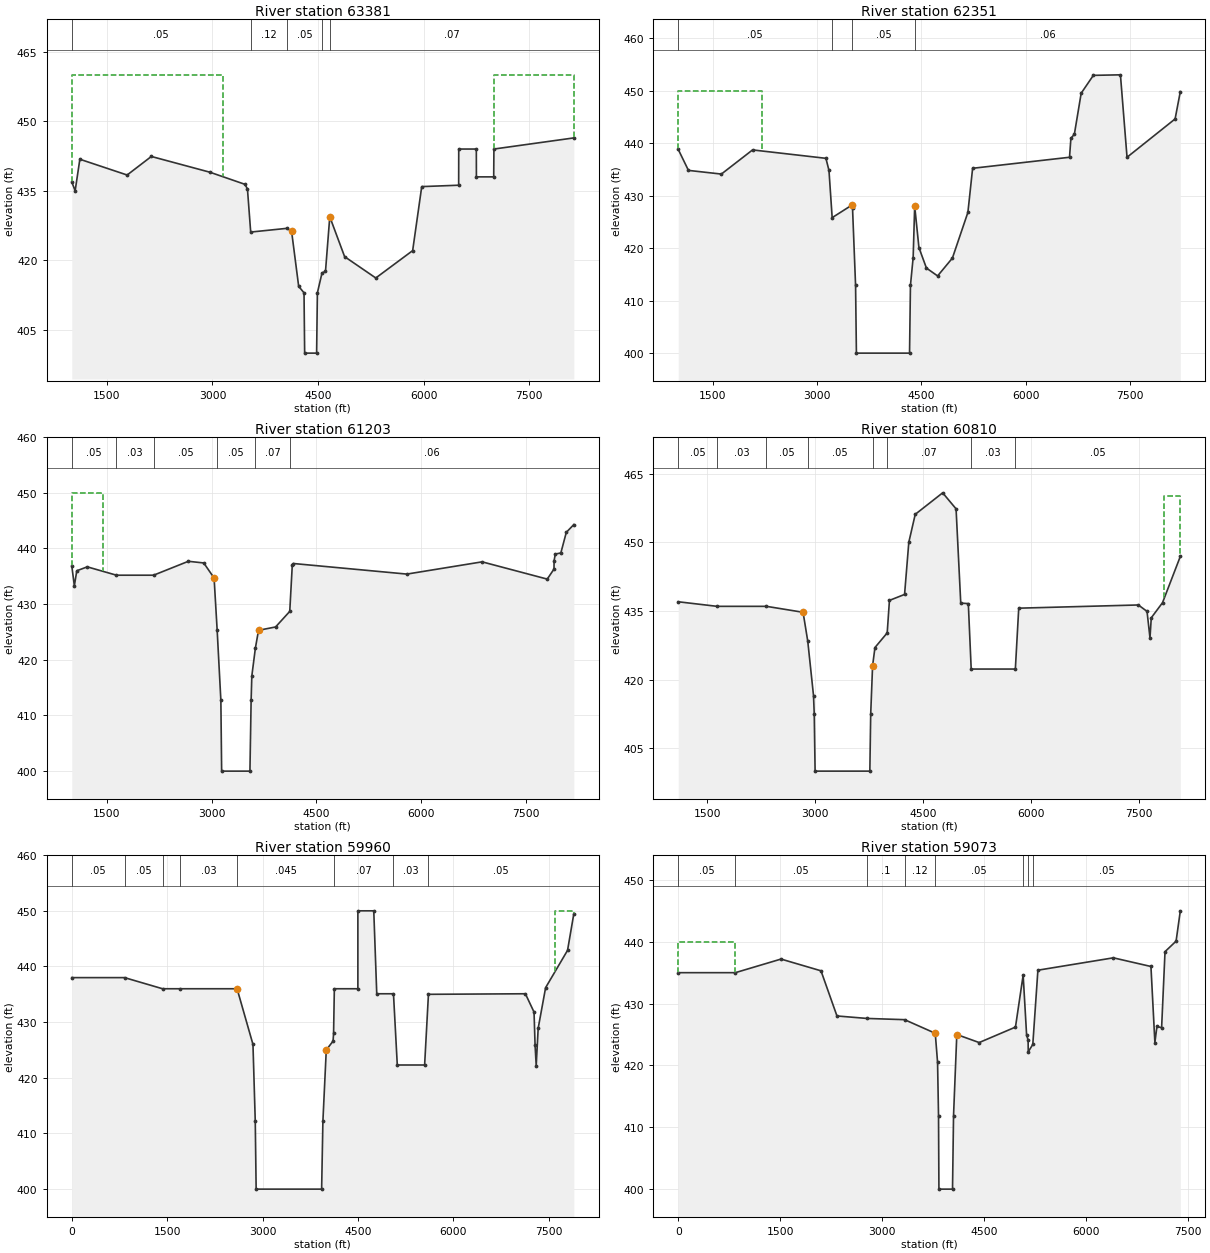
Type RM Length L Ch R = 1 ,63381   ,1000,1030,1100
BEGIN DESCRIPTION:
This cross section corresponds to cross section 63381 of the non-georeferenced CDC model which was the source of this model.
END DESCRIPTION:
XS GIS Cut Line= 3
2453390.246795187016192.570060722449422.949939767016467.05901305
2446312.103471167017017.78232105
#Sta/Elev= 30
    1000   436.9    1048     435    1115   441.8    1787   438.4    2131   442.4
    2964     439    3460   436.4    3497   435.4    3543   426.1    4056   426.9
    4124   426.3    4225   414.4    4301     413    4310     400    4480     400
    4491     413    4557   417.3    4606   417.6    4667   429.4    4878   420.8
    5321   416.2    5845   422.1    5974   435.9    6499   436.2    6500     444
    6750     444    6751     438    6997     438    7000     444    8136   446.4
#Mann= 5 ,-1,0
    1000     .05       0    3543     .12       0    4056     .05       0
    4557     .12       0    4667     .07       0
#XS Ineff= 2 , 0
            3150     460    7000             460
Permanent Ineff=
       F       F
Bank Sta=4124,4667
XS Rating Curve= 0 ,0
Exp/Cntr=0.3,0.1

Type RM Length L Ch R = 1 ,62351   ,800,1148,700
BEGIN DESCRIPTION:
This cross section corresponds to cross section 62351 of the non-georeferenced CDC model which was the source of this model.
---------------------------------------------------------------------
LOMR#14-06-2597P & CDC# FB100113-1 Mercer Crossing
Cross-sections 67169 & 62351.  Fill was added in innefective flow area so no physical cross-section change.
---------------------------------------------------------------------
END DESCRIPTION:
XS GIS Cut Line= 3
2453739.509876167015648.992079632449179.379888837015736.34918839
2446518.20542118 7015913.0335463
#Sta/Elev= 30
    1000   438.8    1147   434.8    1621   434.1    2070   438.7    3126   437.1
    3170   434.8    3216   425.8    3501   428.2    3509   427.7    3553   412.9
    3565     400    4330     400    4343   412.9    4382   418.2    4404     428
    4465   420.1    4573   416.2    4734   414.7    4947   418.1    5170   426.8
    5238   435.2    6633   437.3    6653   440.9    6703   441.7    6801   449.5
    6976   452.9    7366     453    7461   437.3    8153   444.6    8228   449.8
#Mann= 4 ,-1,0
    1000     .05       0    3216      .1       0    3501     .05       0
    4404     .06       0
#XS Ineff= 2 , 0
            2200     450
Permanent Ineff=
       F       F
Bank Sta=3501,4404
XS Rating Curve= 0 ,0
Exp/Cntr=0.3,0.1

Type RM Length L Ch R = 1 ,61203   ,400,393,550
BEGIN DESCRIPTION:
This cross section corresponds to cross section 61203 of the non-georeferenced CDC model which was the source of this model.
END DESCRIPTION:
XS GIS Cut Line= 4
2453864.556870167014912.291125222451020.959867097014900.08609714
2449806.514133247015048.058242132446688.293335597015115.47936714
#Sta/Elev= 30
    1000   436.9    1037   433.3    1072     436    1222   436.7    1640   435.2
    2171   435.2    2669   437.7    2889   437.4    3037   434.7    3081   425.3
    3134   412.7    3145     400    3550     400    3567   412.7    3577   417.1
    3628   422.1    3673   425.3    3917   425.9    4120   428.7    4156     437
    4173   437.3    5796   435.4    6873   437.6    7805   434.5    7902   436.3
    7903   437.8    7921     439    8000   439.2    8078   442.9    8186   444.3
#Mann= 6 ,-1,0
    1000     .05       0    1640     .03       0    2171     .05       0
    3081     .05       0    3628     .07       0    4120     .06       0
#XS Ineff= 2 , 0
            1450     450
Permanent Ineff=
       F       F
Bank Sta=3037,3673
XS Rating Curve= 0 ,0
Exp/Cntr=0.3,0.1

Type RM Length L Ch R = 1 ,60810   ,830,850,850
BEGIN DESCRIPTION:
This cross section corresponds to cross section 60810 of the non-georeferenced CDC model which was the source of this model.
END DESCRIPTION:
XS GIS Cut Line= 2
 2453763.08200757014506.986161542446793.090698187014517.86606105
#Sta/Elev= 30
    1100     437    1640     436    2325     436    2833   434.7    2898   428.4
    2978   416.5    2988   412.5    3000     400    3760     400    3772   412.5
    3798     423    3831     427    4001   430.2    4032   437.3    4242   438.6
    4301     450    4390   456.1    4771   460.8    4957   457.3    5022   436.7
    5127   436.6    5167   422.3    5780   422.3    5827   435.6    7487   436.3
    7608   434.9    7649   429.1    7667   433.5    7823   436.8    8070   446.9
#Mann= 8 ,-1,0
    1100     .05       0    1640     .03       0    2325     .05       0
    2898     .05       0    3798     .08       0    4001     .07       0
    5167     .03       0    5780     .05       0
#XS Ineff= 2 , 0
                            7850             460
Permanent Ineff=
       F       F
Bank Sta=2833,3798
XS Rating Curve= 0 ,0
Exp/Cntr=0.3,0.1

Type RM Length L Ch R = 1 ,59960   ,805,892,784
BEGIN DESCRIPTION:
This cross section corresponds to cross section 59960 of the non-georeferenced CDC model which was the source of this model.
END DESCRIPTION:
XS GIS Cut Line= 3
2454858.365645387013700.116963382454028.377080597013695.76009372
2446961.474547747013658.66371122
#Sta/Elev= 30
       0     438     830     438    1428     436    1700     436    2600     436
    2850     426    2886   412.2    2900     400    3930     400    3950   412.2
    4003     425    4110   426.6    4118     428    4130     436    4500     436
    4500     450    4750     450    4797   435.1    5060   435.1    5120   422.3
    5550   422.3    5610     435    7135   435.1    7271   431.8    7287   425.9
    7305   422.2    7336   428.9    7453   436.2    7798   442.9    7897   449.5
#Mann= 8 ,-1,0
       0     .05       0     830     .05       0    1428     .06       0
    1700     .03       0    2600    .045       0    4130     .07       0
    5060     .03       0    5610     .05       0
#XS Ineff= 2 , 0
                            7600             450
Permanent Ineff=
       F       F
Bank Sta=2600,4003
XS Rating Curve= 0 ,0
Exp/Cntr=0.3,0.1

Type RM Length L Ch R = 1 ,59073   ,414,414,414
BEGIN DESCRIPTION:
This cross section corresponds to cross section 59073 of the non-georeferenced CDC model which was the source of this model.
END DESCRIPTION:
XS GIS Cut Line= 3
2454852.64957959 7012888.10723532454012.650077917012889.02220589
2447466.653983597012896.15244097
#Sta/Elev= 30
       0     435     840     435    1512   437.2    2100   435.3    2335     428
    2777   427.6    3330   427.4    3781   425.2    3815   420.5    3829   411.9
    3835     400    4035     400    4050   411.9    4098     425    4427   423.7
    4961   426.2    5074   434.6    5125   424.9    5147   424.1    5149   422.2
    5216   423.4    5291   435.4    6401   437.4    6954     436    7012   423.7
    7042   426.3    7111   426.1    7161   438.4    7324   440.1    7386     445
#Mann= 8 ,-1,0
       0     .05       0     840     .05       0    2777      .1       0
    3330     .12       0    3781     .05       0    5074     .07       0
    5147     .02       0    5216     .05       0
#XS Ineff= 2 , 0
             840     440
Permanent Ineff=
       F       F
Bank Sta=3781,4098
XS Rating Curve= 0 ,0
Exp/Cntr=0.3,0.1

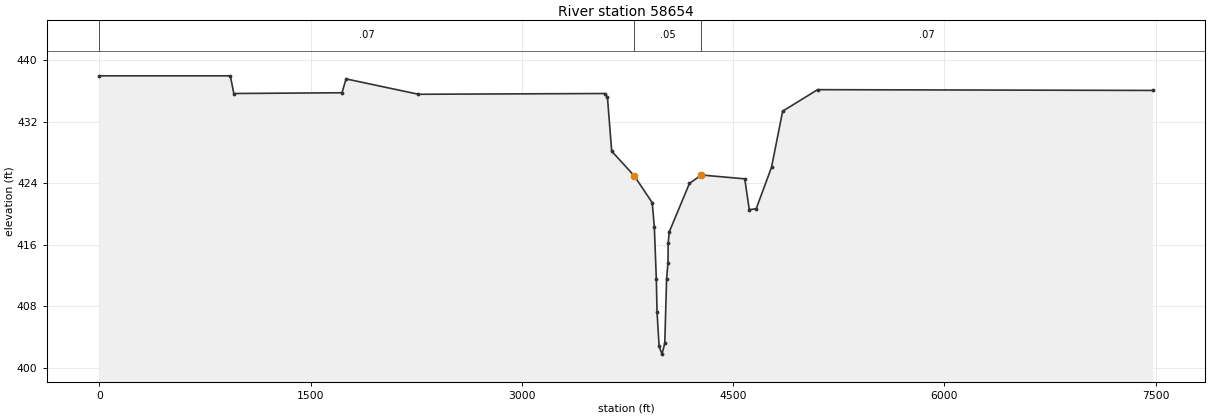
Type RM Length L Ch R = 1 ,58654   ,42,42,42
BEGIN DESCRIPTION:
This cross section corresponds to cross section 58654 of the non-georeferenced CDC model which was the source of this model.
END DESCRIPTION:
XS GIS Cut Line= 6
2454848.755781297012528.446664872453998.919134267012511.78313097
2451975.095097937012472.100139472450436.093910847012492.41604371
2447764.428978597012492.416043712447369.497353767012485.82517764
#Sta/Elev= 30
       0     438     930     438     955   435.7    1723   435.8    1752   437.6
    2266   435.6    3590   435.7    3608   435.2    3638   428.2    3798     425
    3926   421.5    3941   418.3    3955   411.6    3960   407.3    3975   402.8
    3995   401.8    4015   403.2    4028   411.6    4038   413.7    4039   416.2
    4047   417.7    4190     424    4275   425.1    4583   424.6    4615   420.6
    4664   420.7    4773   426.1    4852   433.4    5100   436.2    7480   436.1
#Mann= 3 ,0,0
       0     .07       0    3798     .05       0    4275     .07       0
Bank Sta=3798,4275
XS Rating Curve= 0 ,0
Exp/Cntr=0.3,0.1