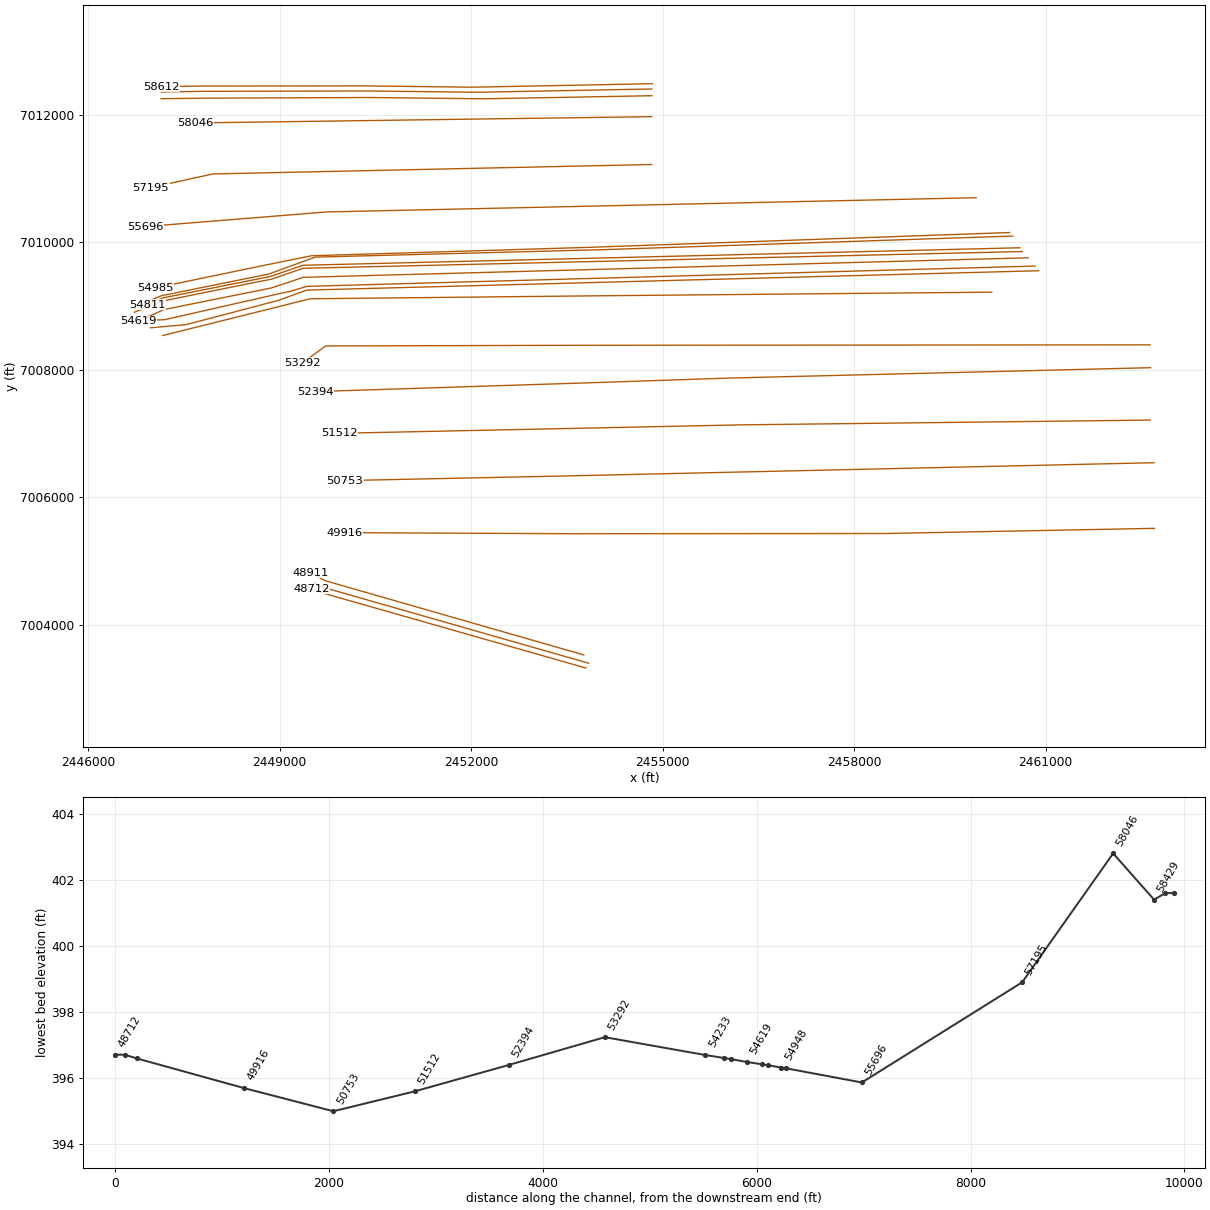
HEC-RAS study CDC_Consolidated_Model.prj: Upper Trinity CDC Consolidated Model

--- CDC_Consolidated_Model.g13 (geometry) --- (continued)

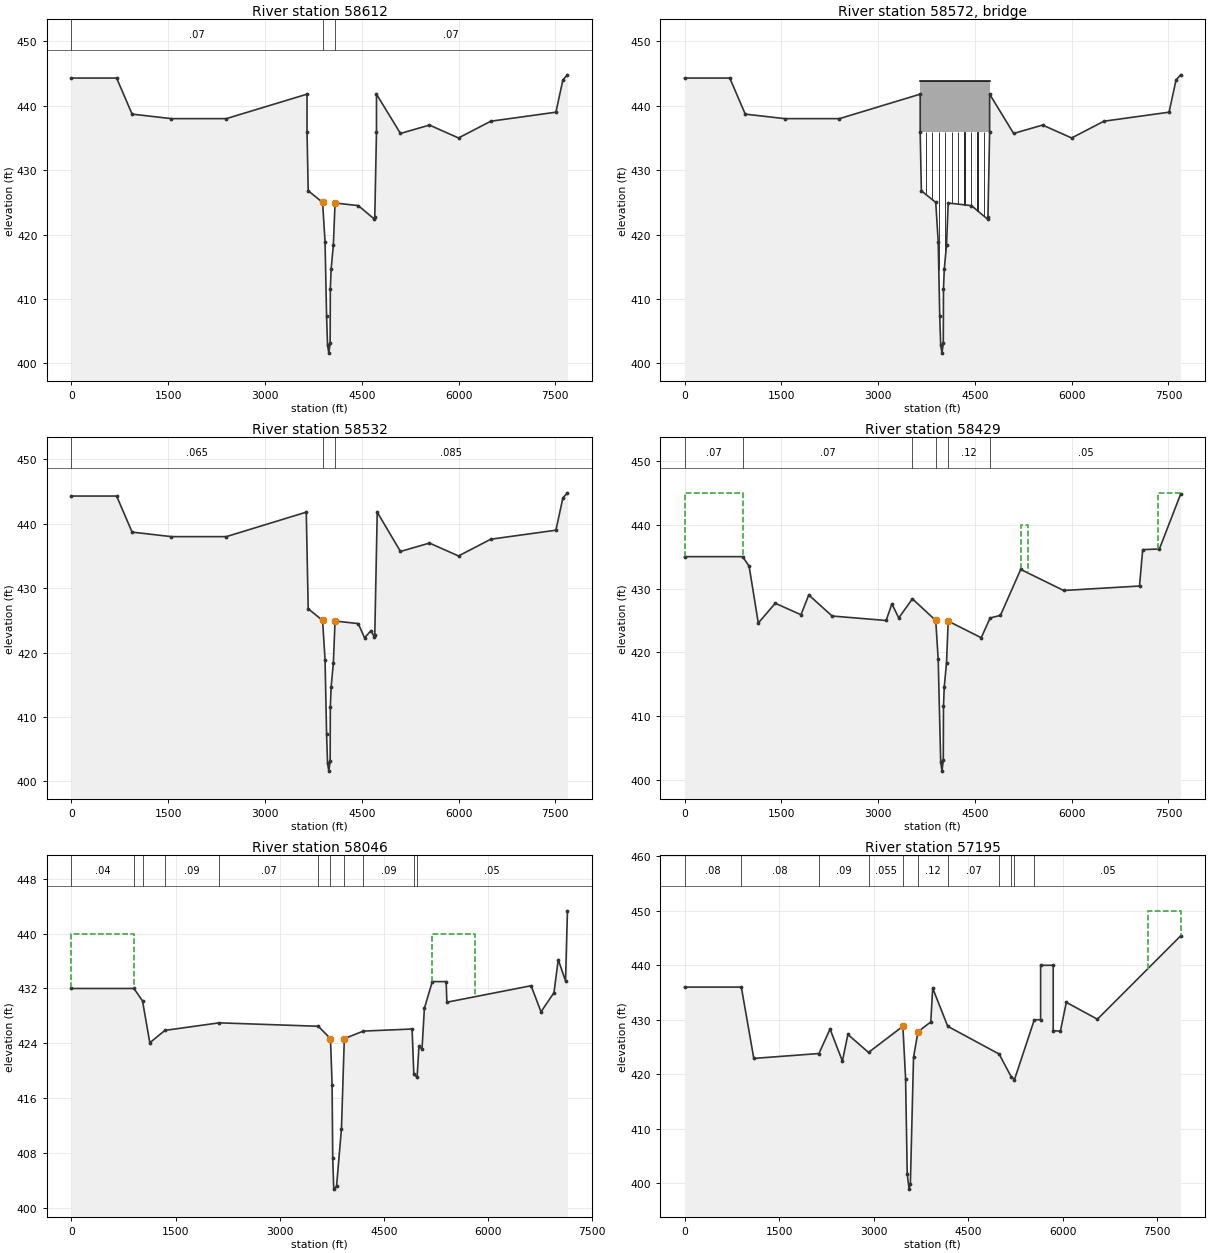
Type RM Length L Ch R = 1 ,58612   ,79,79,79
BEGIN DESCRIPTION:
This cross section corresponds to cross section 58612 of the non-georeferenced CDC model which was the source of this model.
END DESCRIPTION:
XS GIS Cut Line= 6
2454840.271420717012485.239766162452198.67831218 7012433.9302683
2451977.422849187012430.837426722450352.339813267012450.69893555
2447789.279650667012448.807535132447151.997460667012438.79607221
#Sta/Elev= 30
       0   444.3     700   444.3     940   438.7    1550     438    2400     438
  3651.8   441.8  3651.8   435.9    3670   426.8    3893     425    3931   418.9
    3955   407.3    3970   402.8    3990   401.6    4010   403.2    4013   411.6
    4025   414.6    4060   418.4    4086   424.9    4446   424.5    4696   422.4
    4702   422.7  4728.3  435.88  4728.3   441.8    5100   435.7    5550     437
    6000     435    6500   437.6    7510     439    7618     444    7689   444.8
#Mann= 3 ,0,0
       0     .07       0    3893     .05       0    4086     .07       0
Bank Sta=3893,4086
XS Rating Curve= 0 ,0
Exp/Cntr=0.5,0.3

Type RM Length L Ch R = 3 ,58572   ,,,
BEGIN DESCRIPTION:
Royal Lane
END DESCRIPTION:
Node Name=Royal Lane
Bridge Culvert--1,0,-1,-1, 0
Deck Dist Width WeirC Skew NumUp NumDn MinLoCord MaxHiCord MaxSubmerge Is_Ogee
1,77,2.6,0, 22, 22, , , 0.95, 0, ,,,
  3651.8  3738.5  3741.5  3838.5  3841.5  3938.5  3941.5  4038.5  4041.5  4138.5
  4141.5  4238.5  4241.5  4338.5  4341.5  4438.5  4441.5  4538.5  4541.5  4638.5
  4641.5  4728.3
   443.8   443.8   443.8   443.8   443.8   443.8   443.8   443.8   443.8   443.8
   443.8   443.8   443.8   443.8   443.8   443.8   443.8   443.8   443.8   443.8
   443.8   443.8
   435.9   435.9   435.9   435.9   435.9   435.9   435.9   435.9   435.9   435.9
   435.9   435.9   435.9   435.9   435.9   435.9   435.9   435.9   435.9   435.9
   435.9   435.9
  3651.8  3738.5  3741.5  3838.5  3841.5  3938.5  3941.5  4038.5  4041.5  4138.5
  4141.5  4238.5  4241.5  4338.5  4341.5  4438.5  4441.5  4538.5  4541.5  4638.5
  4641.5  4728.3
   443.8   443.8   443.8   443.8   443.8   443.8   443.8   443.8   443.8   443.8
   443.8   443.8   443.8   443.8   443.8   443.8   443.8   443.8   443.8   443.8
   443.8   443.8
   435.9   435.9   435.9   435.9   435.9   435.9   435.9   435.9   435.9   435.9
   435.9   435.9   435.9   435.9   435.9   435.9   435.9   435.9   435.9   435.9
   435.9   435.9
Pier Skew, UpSta & Num, DnSta & Num=  ,3740, 2 ,3740, 2 , 0 , 0 , 0 ,,
       3       3
     410     440
       3       3
     410     440
Pier Skew, UpSta & Num, DnSta & Num=  ,3840, 2 ,3840, 2 , 0 , 0 , 0 ,,
       3       3
     410     440
       3       3
     410     440
Pier Skew, UpSta & Num, DnSta & Num=  ,3940, 2 ,3940, 2 , 0 , 0 , 0 ,,
       3       3
     410     440
       3       3
     410     440
Pier Skew, UpSta & Num, DnSta & Num=  ,4040, 2 ,4040, 2 , 0 , 0 , 0 ,,
       3       3
     410     440
       3       3
     410     440
Pier Skew, UpSta & Num, DnSta & Num=  ,4140, 2 ,4140, 2 , 0 , 0 , 0 ,,
       3       3
     410     440
       3       3
     410     440
Pier Skew, UpSta & Num, DnSta & Num=  ,4240, 2 ,4240, 2 , 0 , 0 , 0 ,,
       3       3
     410     440
       3       3
     410     440
Pier Skew, UpSta & Num, DnSta & Num=  ,4340, 2 ,4340, 2 , 0 , 0 , 0 ,,
       3       3
     410     440
       3       3
     410     440
Pier Skew, UpSta & Num, DnSta & Num=  ,4440, 2 ,4440, 2 , 0 , 0 , 0 ,,
       3       3
     410     440
       3       3
     410     440
Pier Skew, UpSta & Num, DnSta & Num=  ,4540, 2 ,4540, 2 , 0 , 0 , 0 ,,
       3       3
     410     440
       3       3
     410     440
Pier Skew, UpSta & Num, DnSta & Num=  ,4640, 2 ,4640, 2 , 0 , 0 , 0 ,,
       3       3
     410     440
       3       3
     410     440
BR Coef= 1 , 0 , 0 ,1.05, 0 ,,,0.8,-1,0.5,1,
WSPro=,,,, 1 ,,,, 0 ,,,, 0 ,,,,-1 ,-1 ,-1 , 0 , 0 , 0 , 0 , 0
BR D #Sta/Elev= 88
     700   444.3     940   438.7    1550     438    1650     438    2050     438
    2150     438    2300     438    2400     438    3620   441.7    3640   441.8
  3651.8   441.8  3651.8   435.9    3670   426.8  3738.5  426.05  3741.5  426.02
    3743     426    3759   425.7    3789   425.4  3838.5  425.77  3841.5   425.8
    3842   425.8    3869   425.6    3893     425    3921   420.3    3931   418.9
  3938.5   415.6  3941.5  414.26    3943   413.6    3948   411.6    3955   407.3
    3970   402.8    3990   401.6    4010   403.2    4013   411.6    4025   414.6
    4031   415.7  4038.5   416.4  4041.5  416.68    4060   418.4    4086   424.9
    4102   425.6  4138.5   425.6  4141.5   425.6    4143   425.6    4205     425
  4238.5  424.81  4241.5   424.8    4259   424.7    4297   424.2  4338.5     424
  4341.5  423.94    4381   423.7    4411   423.8  4438.5  424.35  4441.5   424.4
    4446   424.5    4481   422.9    4512   422.8  4538.5  422.37  4541.5   422.3
    4543   422.3    4598   422.3    4625   422.5  4638.5  423.14  4641.5   423.3
    4644   423.4    4650     423    4678     423    4696   422.4    4702   422.7
  4728.3  435.88  4728.3   441.8    4740   441.8    4760   441.7    5100   435.7
    5200   435.7    5450     437    5550     437    5900     435    6000     435
    6500   437.6    7510     439    7543   439.9    7586   442.4    7600   442.8
    7618     444    7646   444.6    7689   444.8
BR D #Mann= 3
     700     .07    3893     .05    4086     .07
BC Design=,, 0 ,, 0 ,,,,,,
BC HTab HWMax=444.8
BC Use User HTab Curves=0
BC User HTab FreeFlow(D)= 0

Type RM Length L Ch R = 1 ,58532   ,104,104,104
BEGIN DESCRIPTION:
This cross section corresponds to cross section 58532 of the non-georeferenced CDC model which was the source of this model.
END DESCRIPTION:
XS GIS Cut Line= 6
 2454829.11679827012402.706492852452200.856129357012352.91796313
2451981.86083242 7012352.24145532450373.41063726 7012371.2374803
2447836.61452976 7012365.74339682447140.775698337012356.11513522
#Sta/Elev= 30
       0   444.3     700   444.3     940   438.7    1550     438    2400     438
    3640   441.8    3670   426.8    3893     425    3931   418.9    3955   407.3
    3970   402.8    3990   401.6    4010   403.2    4013   411.6    4025   414.6
    4060   418.4    4086   424.9    4446   424.5    4543   422.3    4644   423.4
    4696   422.4    4702   422.7    4740   441.8    5100   435.7    5550     437
    6000     435    6500   437.6    7510     439    7618     444    7689   444.8
#Mann= 3 ,0,0
       0    .065       0    3893     .05       0    4086    .085       0
Bank Sta=3893,4086
XS Rating Curve= 0 ,0
Exp/Cntr=0.3,0.1

Type RM Length L Ch R = 1 ,58429   ,330,383,360
BEGIN DESCRIPTION:
This cross section corresponds to cross section 58429 of the non-georeferenced CDC model which was the source of this model.
END DESCRIPTION:
XS GIS Cut Line= 6
2454833.31214267 7012296.90878872453933.463884597012280.38267513
2452203.658945267012248.614037892450400.539848097012268.93092638
2447891.41002384 7012258.77313832447144.939075837012250.27053063
#Sta/Elev= 30
       0     435     900     435    1000   433.5    1142   424.6    1405   427.7
    1804   425.9    1924     429    2287   425.7    3124     425    3213   427.6
    3320   425.4    3531   428.4    3893     425    3931   418.9    3970   402.8
    3990   401.4    4010   403.2    4013   411.6    4025   414.6    4060   418.4
    4086   424.9    4598   422.3    4736   425.4    4896   425.8    5210     433
    5876   429.7    7052   430.4    7101   436.1    7360   436.2    7689   444.8
#Mann= 6 ,-1,0
       0     .07       0     900     .07       0    3531     .12       0
    3893     .05       0    4086     .12       0    4736     .05       0
#XS Ineff= 3 ,-1
       0     900     445    5210    5330     440    7340    7689     445
Permanent Ineff=
       F       F       F
Bank Sta=3893,4086
XS Rating Curve= 0 ,0
Exp/Cntr=0.3,0.1

Type RM Length L Ch R = 1 ,58046   ,780,851,790
BEGIN DESCRIPTION:
This cross section corresponds to cross section 58046 of the non-georeferenced CDC model which was the source of this model.
---------------------------------------------------------------------
CDC IRV101405-1 North Hills School Addition
Cross-section 58046 - 58429
Located in ROB within ineffective flow area.
---------------------------------------------------------------------
END DESCRIPTION:
XS GIS Cut Line= 3
2454829.654837617011968.325749982453929.740138777011955.93483321
  2447682.3323587011869.91433597
#Sta/Elev= 30
       0     432     900     432    1024   430.2    1129   424.1    1347   425.9
    2128     427    3557   426.5    3733   424.7    3756     418    3765   407.3
    3780   402.8    3820   403.2    3891   411.6    3932   424.7    4207   425.8
    4909   426.1    4934   419.5    4981   419.1    5008   423.6    5052   423.2
    5086   429.1    5200     433    5400     433    5410     430    6624   432.4
    6767   428.6    6954   431.4    7015   436.2    7120   433.1    7148   443.3
#Mann= 11 ,-1,0
       0     .04       0     900     .04       0    1024     .12       0
    1347     .09       0    2128     .07       0    3557     .12       0
    3733     .05       0    3932     .12       0    4207     .09       0
    4934    .035       0    4981     .05       0
#XS Ineff= 2 ,-1
       0     900     440    5200    5810     440
Permanent Ineff=
       F       F
Bank Sta=3733,3932
XS Rating Curve= 0 ,0
Exp/Cntr=0.3,0.1

Type RM Length L Ch R = 1 ,57195   ,640,1499,640
BEGIN DESCRIPTION:
This cross section corresponds to cross section 57195 of the non-georeferenced CDC model which was the source of this model.
END DESCRIPTION:
XS GIS Cut Line= 4
 2454830.46863997011217.681086772453930.677800927011198.27886821
2447956.673016677011069.46121247 2446983.06243117010856.60632321
#Sta/Elev= 30
       0     436     900     436    1098   422.9    2132   423.8    2308   428.3
    2504   422.4    2591   427.3    2919     424    3464   428.8    3507   419.2
    3533   401.7    3563   398.9    3583   399.9    3633   423.1    3704   427.8
    3907   429.6    3937   435.8    4176   428.8    4992   423.7    5184   419.5
    5235     419    5550     430    5650     430    5650     440    5850     440
    5850     428    5964   427.9    6058   433.2    6551   430.1    7872   445.4
#Mann= 11 ,-1,0
       0     .08       0     900     .08       0    2132     .09       0
    2919    .055       0    3464     .05       0    3704     .12       0
    4176     .07       0    4992     .15       0    5184    .035       0
    5235     .15       0    5550     .05       0
#XS Ineff= 2 , 0
                            7350             450
Permanent Ineff=
       F       F
Bank Sta=3464,3704
XS Rating Curve= 0 ,0
Exp/Cntr=0.3,0.1

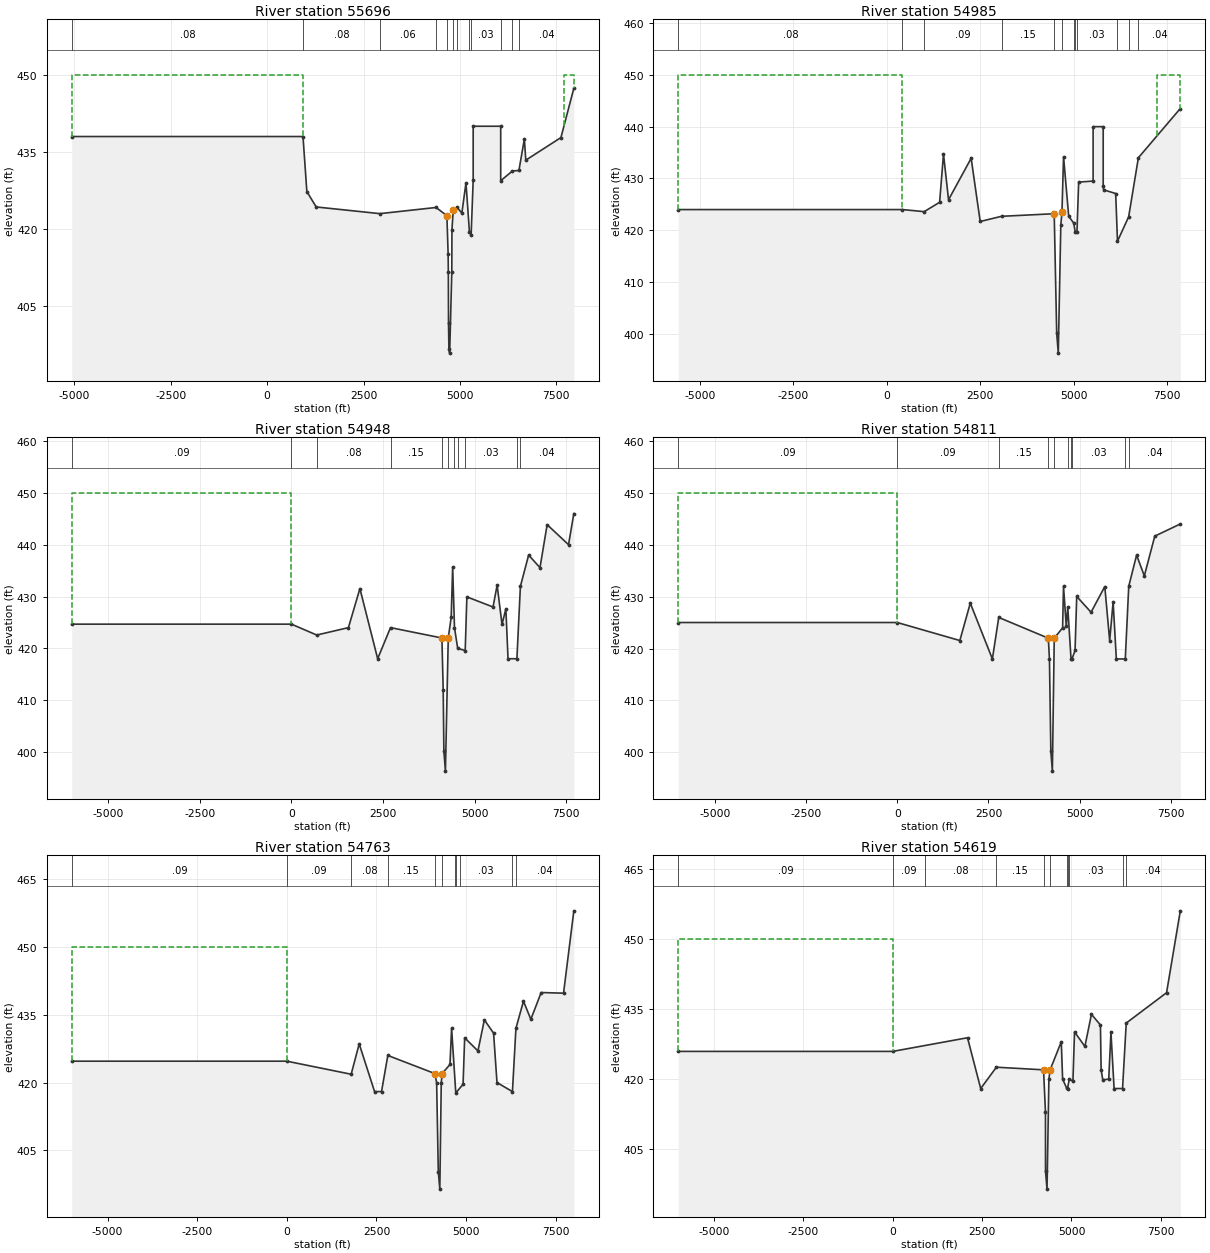
Type RM Length L Ch R = 1 ,55696   ,671,712,681
BEGIN DESCRIPTION:
This cross section corresponds to cross section 55696 of the non-georeferenced CDC model which was the source of this model.
END DESCRIPTION:
XS GIS Cut Line= 4
2459912.197360127010696.939828932453913.643058097010565.23453063
2449742.268854927010473.647115382446895.903156587010243.92907089
#Sta/Elev= 30
   -5070     438     930     438    1030   427.3    1272   424.3    2925     423
    4383   424.2    4664   422.6    4696   415.1    4701   411.7    4706   401.7
    4716   396.6    4736  395.87    4791   411.7    4795   419.9    4829   423.7
    4930   424.2    5052   423.1    5159     429    5249   419.4    5293   418.9
    5346   429.5    5346     440    6060     440    6060   429.4    6365   431.3
    6533   431.4    6674   437.5    6711   433.4    7623   437.8    7958   447.4
#Mann= 12 ,-1,0
   -5070     .08       0     930     .08       0    2925     .06       0
    4383     .15       0    4664     .05       0    4829     .15       0
    4930     .07       0    5249    .035       0    5293     .03       0
    6060     .03       0    6365     .03       0    6533     .04       0
#XS Ineff= 2 , 0
             930     450    7700             450
Permanent Ineff=
       F       F
Bank Sta=4664,4829
XS Rating Curve= 0 ,0
Exp/Cntr=0.3,0.1

Type RM Length L Ch R = 1 ,54985   ,41,41,36
BEGIN DESCRIPTION:
This cross section corresponds to cross section 54985 of the non-georeferenced CDC model which was the source of this model.
END DESCRIPTION:
XS GIS Cut Line= 6
2460434.000396017010150.277736982454437.727967927009938.81386746
2453841.462100097009917.786022382449500.831017587009786.25905447
2448716.278124757009627.22820455  2447058.5816377009282.15540388
#Sta/Elev= 30
   -5580     424     420     424    1000   423.6    1413   425.4    1517   434.7
    1652   425.9    2257   433.9    2499   421.7    3070   422.7    4479   423.2
    4546   400.1    4588   396.3    4656     421    4687   423.6    4729   434.2
    4867   422.7    5001   421.4    5041   419.7    5088   419.7    5133   429.3
    5520   429.5    5520     440    5790     440    5790   428.6    5803   427.8
    6124   427.1    6172   417.9    6471   422.6    6731     434    7853   443.5
#Mann= 12 ,-1,0
   -5580     .08       0     420     .08       0    1000     .09       0
    3070     .15       0    4479     .05       0    4687     .15       0
    5001     .03       0    5041    .035       0    5088     .03       0
    6172     .03       0    6471      .1       0    6731     .04       0
#XS Ineff= 2 , 0
             420     450    7220             450
Permanent Ineff=
       F       F
Bank Sta=4479,4687
XS Rating Curve= 0 ,0
Exp/Cntr=0.3,0.1

Type RM Length L Ch R = 1 ,54948   ,111,129,116
BEGIN DESCRIPTION:
This cross section corresponds to cross section 54948 of the non-georeferenced CDC model which was the source of this model.
Added cross-section.
END DESCRIPTION:
XS GIS Cut Line= 6
2460485.525092127010094.774753622454103.001603257009882.74344155
2449558.522175167009764.589150292448830.744103167009499.31113756
2447148.799960497009159.033602882446881.189931427009049.55875622
#Sta/Elev= 30
   -6000  424.67       0  424.67   690.5  422.57 1556.15     424 1869.25  431.53
 2354.41     418 2705.24     424 4108.81     422 4144.18     412 4162.89  400.12
 4204.89  396.32 4282.43     422 4362.55     426 4402.65  435.67  4452.4     424
 4539.91     420 4745.25  419.57 4790.68  429.93 5505.49  427.98 5617.18  432.19
 5750.67  424.62 5855.45  427.61 5914.93     418 6157.12     418  6252.7  431.96
 6477.66     438  6787.6  435.56 6982.84  443.86 7566.92     440 7712.33     446
#Mann= 11 ,-1,0
   -6000     .09       0       0     .09       0   690.5     .08       0
 2705.24     .15       04108.811     .05       0 4282.43     .15       0
  4452.4     .03       0 4539.91    .035       0 4745.25     .03       0
 6157.12      .1       0  6252.7     .04       0
#XS Ineff= 2 , 0
               0     450
Permanent Ineff=
       F       F
Bank Sta=4108.81,4282.43
XS Rating Curve= 0 ,0
Exp/Cntr=0.3,0.1

Type RM Length L Ch R = 1 ,54811   ,48,52,48
BEGIN DESCRIPTION:
This cross section corresponds to cross section 54811 of the non-georeferenced CDC model which was the source of this model.
Added cross-section.
END DESCRIPTION:
XS GIS Cut Line= 6
 2460597.34534917009911.40009636     2454599.138     7009764.742
     2449366.855     7009636.811     2448858.522     7009461.811
     2447169.633     7009124.311     2446929.876      7009020.63
#Sta/Elev= 30
   -6000  425.02       0  425.02 1715.04  421.55 2001.19  428.75 2606.32     418
 2780.57     426 4138.89     422 4169.77     418 4207.94400.1937 4249.94396.3937
 4301.16     422 4530.47     424 4554.75     432 4631.26  424.28 4671.66     428
 4760.88  418.03 4787.54     418 4871.11  419.63 4917.09  430.04 5309.55     427
 5685.95  431.94 5819.71  421.53 5914.26  429.01 6002.21     418 6247.61     418
 6342.29     432  6557.4     438 6769.19     434 7055.69  441.66 7754.95     444
#Mann= 10 ,-1,0
   -6000     .09       0       0     .09       0 2780.57     .15       0
4138.891     .05       0 4301.16     .15       0 4671.66     .03       0
 4760.88    .035       0 4787.54     .03       06247.609      .1       0
 6342.29     .04       0
#XS Ineff= 2 , 0
               0     450
Permanent Ineff=
       F       F
Bank Sta=4138.89,4301.16
XS Rating Curve= 0 ,0
Exp/Cntr=0.3,0.1

Type RM Length L Ch R = 1 ,54763   ,138,143,138
BEGIN DESCRIPTION:
This cross section corresponds to cross section 54763 of the non-georeferenced CDC model which was the source of this model.
Added cross-section.
END DESCRIPTION:
XS GIS Cut Line= 6
2460634.365638187009852.24708952     2449369.633     7009589.589
     2448875.189     7009418.756     2448533.522     7009352.089
     2447182.133     7009078.478     2446726.534     7008900.202
#Sta/Elev= 30
   -6000  424.73       0  424.73 1793.61  421.84 2017.31  428.56 2446.63     418
 2640.34     418 2815.68     426 4125.45     422 4125.65  421.97 4177.49     420
 4224.37400.2197 4266.37396.4197 4306.41     420 4332.47     422 4549.08     424
 4595.11     432 4711.43  417.71 4914.75  419.61 4959.31   429.9 5329.96     427
 5508.38  433.87 5765.74  430.94 5861.01     420 6291.74     418 6389.23     432
  6599.8     438 6805.26     434 7093.43  439.92 7717.38  439.78  8004.8     458
#Mann= 11 ,-1,0
   -6000     .09       0       0     .09       0 1793.61     .08       0
2814.189     .15       0 4125.65     .05       04332.471     .15       0
4678.029     .03       0 4711.43    .035       04822.609     .03       0
 6291.74      .1       0 6389.23     .04       0
#XS Ineff= 2 , 0
               0     450
Permanent Ineff=
       F       F
Bank Sta=4125.45,4332.47
XS Rating Curve= 0 ,0
Exp/Cntr=0.3,0.1

Type RM Length L Ch R = 1 ,54619   ,142,145,142
BEGIN DESCRIPTION:
This cross section corresponds to cross section 54619 of the non-georeferenced CDC model which was the source of this model.
Added cross-section.
END DESCRIPTION:
XS GIS Cut Line= 6
2460723.948535237009753.93098975     2454726.128     7009592.225
       2449373.8     7009447.922     2448872.411     7009281.256
     2447185.189     7008940.978     2446785.782     7008757.914
#Sta/Elev= 30
   -6000  425.94       0  425.94 2091.55  428.86 2460.78     418 2899.64  422.56
 4218.74     422 4272.39  412.98    4274  400.29    4316  396.49 4368.42     420
 4402.73     422 4715.03     428 4752.29     420 4860.93  418.17 4888.96     418
  4938.3     420 5040.44  419.57 5085.41  430.11 5375.45     427 5558.46  433.87
 5810.17  431.59 5829.54     422 5875.75  419.88 6041.98     420 6104.45     430
 6192.12     418 6428.58     418  6531.8     432 7660.01  438.49  8044.5     456
#Mann= 11 ,-1,0
   -6000     .09       0       0     .09       0899.8301     .08       0
 2899.64     .15       0 4218.74     .05       0 4402.73     .15       0
 4860.93    .035       0 4888.96     .03       0  4938.3     .03       0
 6428.58      .1       0  6531.8     .04       0
#XS Ineff= 2 , 0
               0     450
Permanent Ineff=
       F       F
Bank Sta=4218.74,4402.73
XS Rating Curve= 0 ,0
Exp/Cntr=0.3,0.1

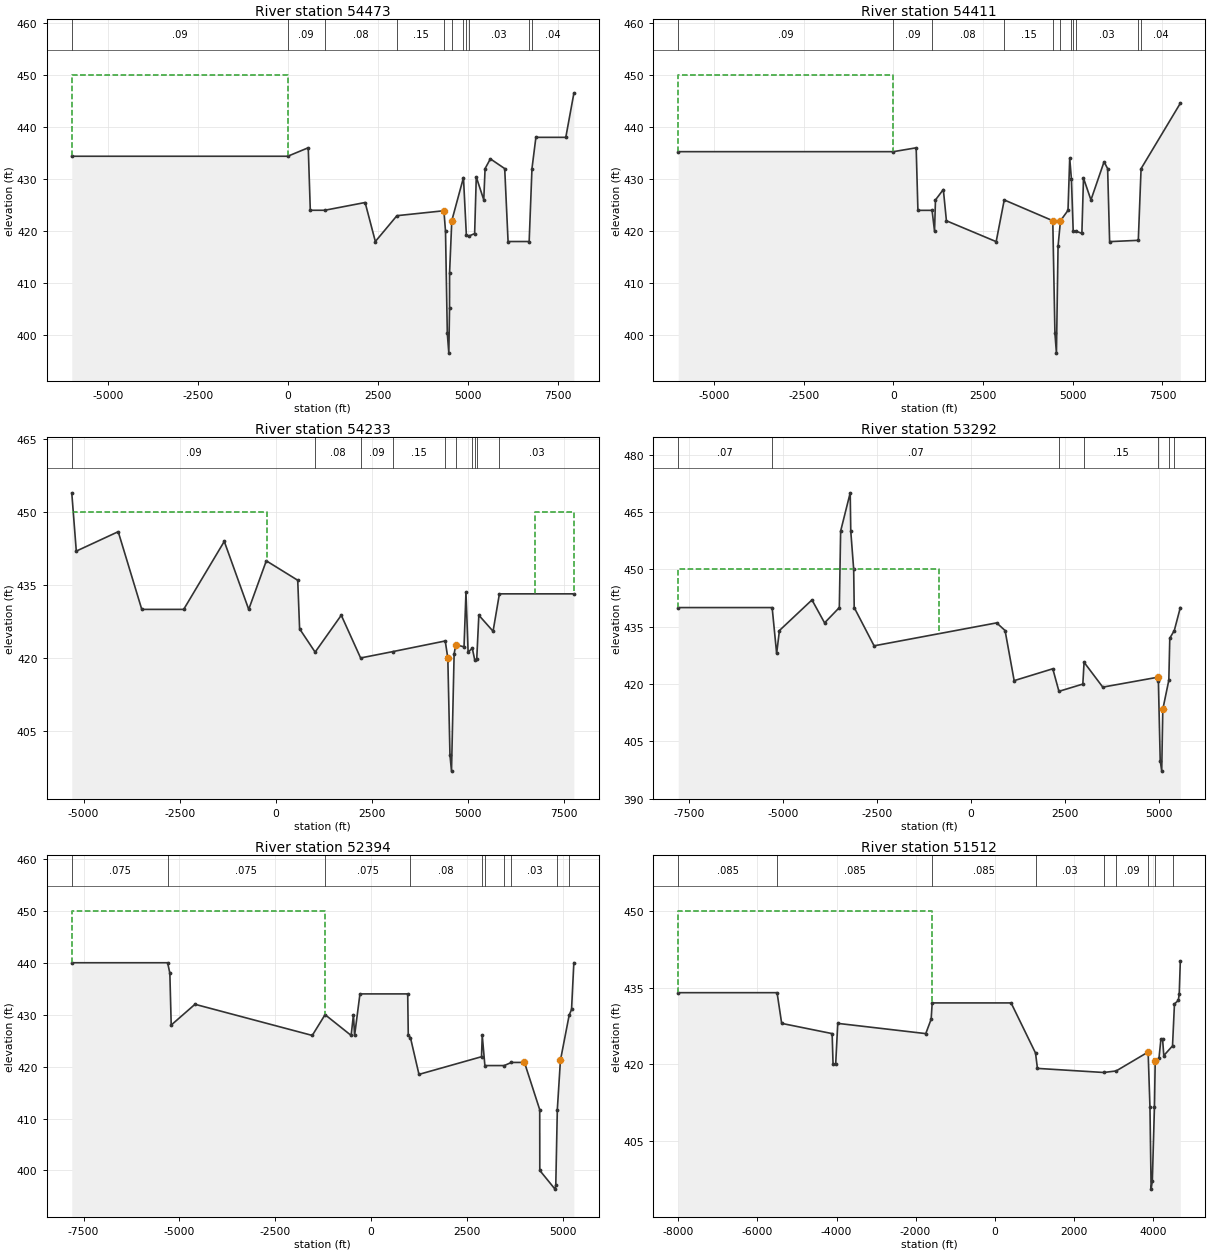
Type RM Length L Ch R = 1 ,54473   ,60,65,60
BEGIN DESCRIPTION:
This cross section corresponds to cross section 54473 of the non-georeferenced CDC model which was the source of this model.
Added cross-section.
END DESCRIPTION:
XS GIS Cut Line= 6
2460833.692508357009624.18970525     2449432.411     7009306.256
     2449164.355     7009227.089     2449025.466     7009197.922
     2447197.689     7008782.645     2446951.207     7008773.992
#Sta/Elev= 30
   -6000  434.37       0  434.37  569.76     436  626.72     424 1027.08     424
 2149.49  425.49 2433.63     418 3033.15  422.96 4338.48  423.91 4382.75  419.96
 4432.84400.3761 4474.84 396.576 4494.84405.1761  4495.9     412 4557.45     422
 4881.58  430.27 4962.84  419.16 5041.88  419.08 5192.06  419.52 5237.71  430.38
 5445.68     426  5482.1     432 5628.97  433.87 6027.36     432 6120.94     418
  6706.9     418 6784.83     432 6893.92     438 7724.56     438 7948.13  446.43
#Mann= 11 ,-1,0
   -6000     .09       0       0     .09       0 1027.08     .08       0
 3033.15     .15       0 4338.48     .05       0 4557.45     .15       0
 4881.58     .03       0 4962.84    .035       0 5041.88     .03       0
  6706.9      .1       0 6784.83     .04       0
#XS Ineff= 2 , 0
               0     450
Permanent Ineff=
       F       F
Bank Sta=4338.48,4557.45
XS Rating Curve= 0 ,0
Exp/Cntr=0.3,0.1

Type RM Length L Ch R = 1 ,54411   ,178,177,144
BEGIN DESCRIPTION:
This cross section corresponds to cross section 54411 of the non-georeferenced CDC model which was the source of this model.
Added cross-section.
END DESCRIPTION:
XS GIS Cut Line= 6
2460888.397187287009550.96967853     2454890.503     7009392.019
     2449425.141     7009247.181      2448979.98     7009085.748
     2447536.222     7008705.196     2446979.194     7008655.734
#Sta/Elev= 30
   -6000  435.26       0  435.26   633.4     436  682.35     424 1077.04     424
 1145.62     420 1171.65     426 1390.86     428 1476.88     422 2863.96     418
 3088.74     426 4442.25  422.01 4502.11400.4098 4544.11396.6098 4589.17  417.11
 4656.45     422 4866.49     424  4914.3     434 4962.01     430 5011.57     420
 5088.25     420 5253.37  419.58 5298.47  430.19 5506.35     426 5871.92  433.32
 5971.28     432 6026.83     418  6826.5  418.25  6903.9     432  7997.7  444.54
#Mann= 11 ,-1,0
   -6000     .09       0       0     .09       0 1077.04     .08       0
 3088.74     .15       0 4442.25     .05       0 4656.45     .15       0
 4962.01     .03       0 5011.57    .035       0 5088.25     .03       0
  6826.5      .1       0  6903.9     .04       0
#XS Ineff= 2 , 0
               0     450
Permanent Ineff=
       F       F
Bank Sta=4442.25,4656.45
XS Rating Curve= 0 ,0
Exp/Cntr=0.3,0.1

Type RM Length L Ch R = 1 ,54233   ,749,940,899
BEGIN DESCRIPTION:
This cross section corresponds to cross section 54233 of the non-georeferenced CDC model which was the source of this model.
---------------------------------------------------------------------
CDC IRV012908-1 O'Connor Substation
Cross-section 54233 - 54985
Located in ROB.
---------------------------------------------------------------------
END DESCRIPTION:
XS GIS Cut Line= 5
2460156.426504257009215.047926552453838.89091101 7009156.4230438
2449479.97705668 7009111.29124432448139.793713427008776.59998456
2447169.590845877008534.30595697
#Sta/Elev= 30
 -5308.3     454 -5190.6     442 -4100.4     446 -3487.4     430 -2397.8     430
 -1341.9     444  -706.1     430    -249     440  568.51     436   617.4     426
    1021   421.2    1701   428.8    2204     420    3036   421.3    4405   423.5
    4472     420    4528     400    4568   396.7    4636   420.8    4678   422.7
    4894   422.3    4944   433.5    5000   421.2    5109     422    5172   419.6
    5224   419.7    5279   428.8    5649   425.5    5814   433.2    7750   433.2
#Mann= 10 ,-1,0
 -5308.3     .09       0    1021     .08       0    2204     .09       0
    3036     .15       0    4405     .05       0    4678     .15       0
    5109     .05       0    5172    .035       0    5224     .05       0
    5814     .03       0
#XS Ineff= 2 , 0
            -240     450    6750             450
Permanent Ineff=
       F       F
Bank Sta=4472,4678
XS Rating Curve= 0 ,0
Exp/Cntr=0.3,0.1

Type RM Length L Ch R = 1 ,53292   ,650,898,650
BEGIN DESCRIPTION:
This cross section corresponds to cross section 53292 of the non-georeferenced CDC model which was the source of this model.
END DESCRIPTION:
XS GIS Cut Line= 5
2462636.30510629 7008388.26831812460136.30580959 7008386.3930878
2453834.382061757008381.666063132449723.352882277008370.99613696
2449356.613458257008105.19745597
#Sta/Elev= 30
 -7785.9     440 -5285.9     440 -5166.1     428 -5092.1     434 -4225.7     442
 -3890.1     436 -3497.5     440 -3462.4     460   -3208     470 -3193.1     460
 -3115.4     450 -3101.2     440 -2571.9     430   690.7     436   914.9     434
    1157   420.9    2185     424    2349   418.1    2985     420    3018   425.7
    3516   419.2    4986   421.8    4996   420.8    5045     400    5085  397.24
    5114   413.4    5274     421    5300     432    5420     434    5580     440
#Mann= 7 ,-1,0
 -7785.9     .07       0 -5285.9     .07       0    2349      .1       0
    3018     .15       0    4996     .05       0    5274     .08       0
    5420    .035       0
#XS Ineff= 2 , 0
            -850     450
Permanent Ineff=
       F       F
Bank Sta=4986,5114
XS Rating Curve= 0 ,0
Exp/Cntr=0.3,0.1

Type RM Length L Ch R = 1 ,52394   ,690,882,670
BEGIN DESCRIPTION:
This cross section corresponds to cross section 52394 of the non-georeferenced CDC model which was the source of this model.
END DESCRIPTION:
XS GIS Cut Line= 5
2462643.637375637008029.97173611  2460144.397328 7007968.3342126
 2456049.7188384 7007867.3491784  2453824.261019 7007792.2171108
 2449555.1091242 7007655.1809676
#Sta/Elev= 30
   -7806     440   -5306     440 -5248.2     438 -5212.6     428 -4592.5     432
 -1534.2     426   -1200     430    -520     426    -460     430    -430     426
    -290     434     955     434     970     426    1026   425.6    1249   418.5
    2880   421.9    2899     426    2968   420.2    3473   420.2    3659   420.8
    4000   420.8    4398   411.7    4400     400    4797   396.4    4817   397.2
    4857   411.7    4938   421.2    5166   429.9    5228     431    5288     440
#Mann= 10 ,-1,0
   -7806    .075       0   -5306    .075       0   -1200    .075       0
    1026     .08       0    2880    .035       0    2968     .02       0
    3473     .07       0    3659     .03       0    4857     .05       0
    5166    .035       0
#XS Ineff= 2 , 0
           -1200     450
Permanent Ineff=
       F       F
Bank Sta=4000,4938
XS Rating Curve= 0 ,0
Exp/Cntr=0.3,0.1

Type RM Length L Ch R = 1 ,51512   ,750,759,750
BEGIN DESCRIPTION:
This cross section corresponds to cross section 51512 of the non-georeferenced CDC model which was the source of this model.
END DESCRIPTION:
XS GIS Cut Line= 5
2462637.917126797007208.013196652460138.088286347007178.75967629
2456231.689931187007133.046185052449940.341293427007001.01167221
2449940.341293427007001.01167221
#Sta/Elev= 30
 -8003.4     434 -5503.4     434 -5387.2     428 -4110.6     426 -4087.5     420
 -4021.3     420 -3968.4     428 -1742.3     426 -1605.8  428.83   -1580     432
   415.7     432    1034   422.2    1082   419.2    2759   418.4    3073   418.7
    3882   422.4    3928   411.7    3958   395.6    3988   397.2    4042   411.7
    4061   420.6    4158   421.3    4205   424.9    4248   424.9    4278   421.7
    4499   423.6    4548   431.8    4646   432.5    4669   433.8    4696   440.1
#Mann= 9 ,-1,0
 -8003.4    .085       0 -5503.4    .085       0   -1580    .085       0
    1034     .03       0    2759     .02       0    3073     .09       0
    3882     .05       0    4061     .06       0    4499    .035       0
#XS Ineff= 2 , 0
           -1580     450
Permanent Ineff=
       F       F
Bank Sta=3882,4061
XS Rating Curve= 0 ,0
Exp/Cntr=0.3,0.1

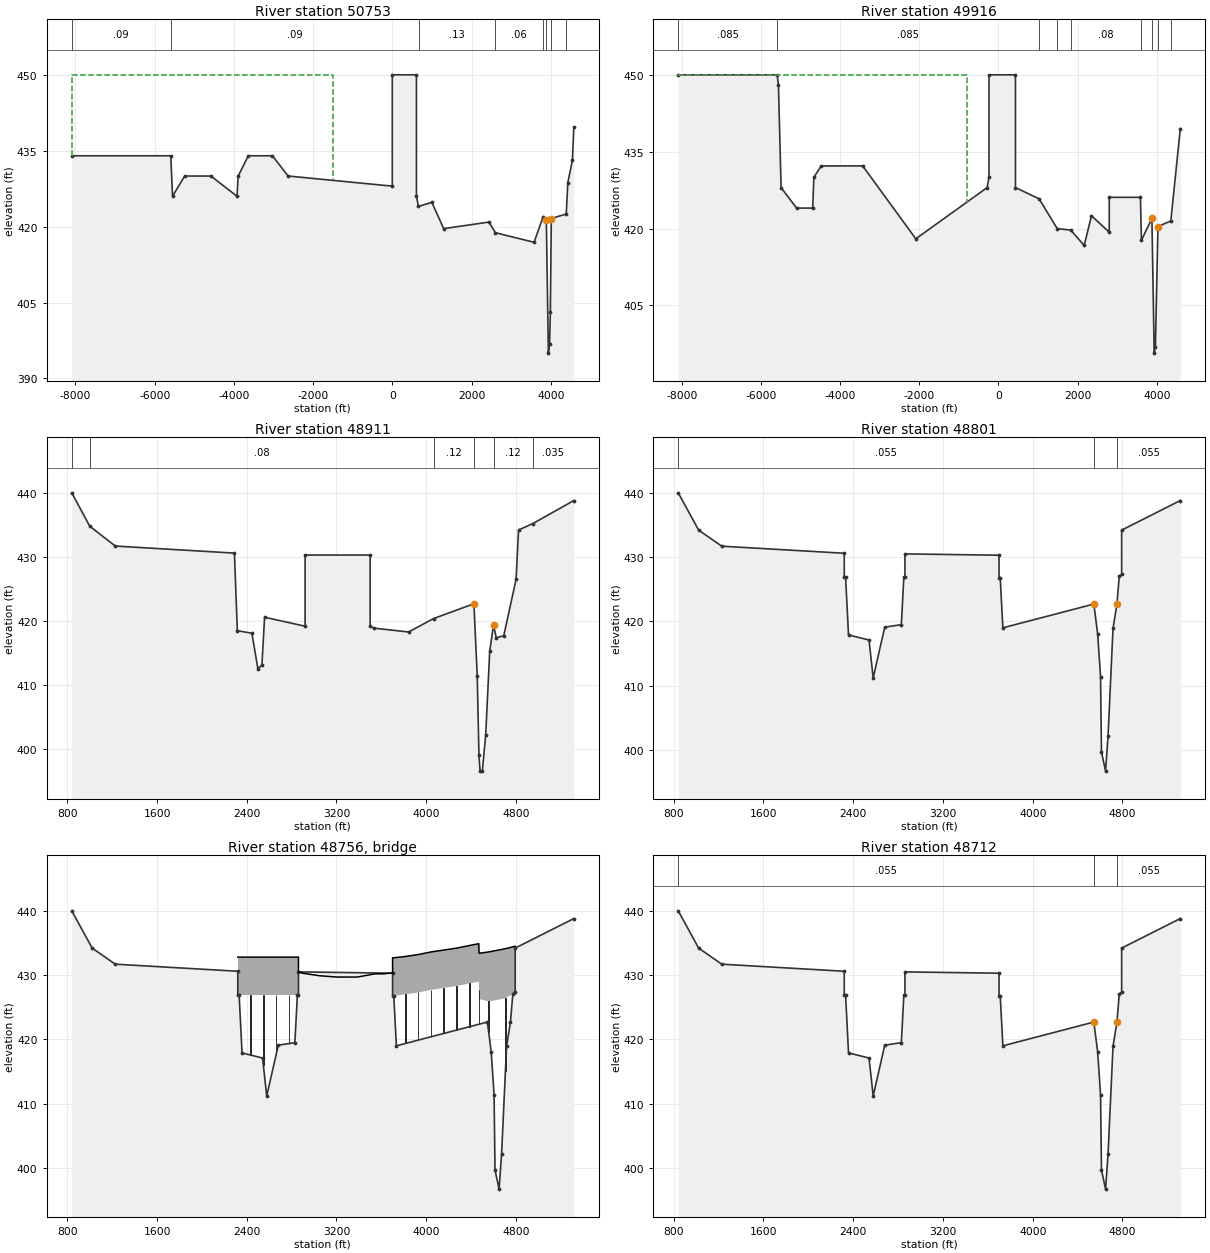
Type RM Length L Ch R = 1 ,50753   ,869,836,829
BEGIN DESCRIPTION:
This cross section corresponds to cross section 50753 of the non-georeferenced CDC model which was the source of this model.
END DESCRIPTION:
XS GIS Cut Line= 4
2462696.620144067006539.123915782460197.254506597006482.80864038
2453595.102028527006334.050079632450022.619015997006258.97313005
#Sta/Elev= 30
 -8093.1     434 -5593.1     434   -5549     426 -5242.1     430   -4580     430
 -3921.3     426 -3890.6     430 -3636.7     434 -3026.8     434   -2630     430
       0     428       0     450     610     450     610     426   658.8     424
    1000   424.8    1297   419.6    2441   420.9    2603   418.8    3581   416.9
    3809     422    3889   421.4    3941     395    3971   396.8    3991   403.2
    4015   421.6    4392   422.5    4432   428.7    4548   433.1    4584   439.7
#Mann= 8 ,-1,0
 -8093.1     .09       0 -5593.1     .09       0681.6997     .13       0
    2603     .06       0    3809     .15       0    3889     .05       0
    4015    .075       0    4392    .035       0
#XS Ineff= 2 , 0
         -1495.3     450
Permanent Ineff=
       F       F
Bank Sta=3889,4015
XS Rating Curve= 0 ,0
Exp/Cntr=0.3,0.1

Type RM Length L Ch R = 1 ,49916   ,1005,1005,1005
BEGIN DESCRIPTION:
This cross section corresponds to cross section 49916 of the non-georeferenced CDC model which was the source of this model.
END DESCRIPTION:
XS GIS Cut Line= 5
2462703.889352597005509.338557192460204.348652517005461.41895089
  2458483.9761097005428.437061472453607.589864437005425.03614964
2450015.204988847005441.82318956
#Sta/Elev= 30
 -8093.5     450 -5593.5     450 -5560.9     448 -5493.9     428 -5102.7     424
 -4694.8     424 -4665.5     430 -4480.2  432.22 -3431.6  432.23 -2089.6     418
 -285.75     428    -240     430    -240     450     430     450     430     428
    1028   425.8    1484     420    1827   419.7    2166   416.7    2351   422.5
    2800   419.3    2800   426.1    3588   426.1    3613   417.7    3878     422
    3936   395.7    3966   396.8    4031   420.4    4356   421.5    4596   439.5
#Mann= 9 ,-1,0
 -8093.5    .085       0 -5593.5    .085       0    1028     .05       0
    1484      .1       0    1827     .08       0    3613     .05       0
    3878     .05       0    4031     .15       0    4356    .035       0
#XS Ineff= 2 , 0
            -802     450
Permanent Ineff=
       F       F
Bank Sta=3878,4031
XS Rating Curve= 0 ,0
Exp/Cntr=0.3,0.1

Type RM Length L Ch R = 1 ,48911   ,111,111,111
BEGIN DESCRIPTION:
This cross section corresponds to cross section 48911 of the non-georeferenced CDC model which was the source of this model.
END DESCRIPTION:
XS GIS Cut Line= 3
2453766.362840837003523.163969132449718.07598993 7004687.1859193
2449485.64075926 7004811.7053553
#Sta/Elev= 30
     840     440    1000   434.8    1228   431.7    2290   430.6    2316   418.5
    2446   418.1    2499   412.6    2535   413.1    2559   420.6    2920   419.2
    2920   430.3    3500   430.3    3500   419.2    3533   418.9    3843   418.3
    4066   420.4    4425   422.7    4455   411.4    4470   399.1    4480   396.6
    4500   396.6    4530   402.2    4566   415.3    4600   419.4    4624   417.4
    4691   417.7    4801   426.5    4823   434.2    4950   435.2    5316   438.8
#Mann= 6 ,-1,0
     840      .1       0    1000     .08       0    4066     .12       0
    4425     .05       0    4600     .12       0    4950    .035       0
Bank Sta=4425,4600
XS Rating Curve= 0 ,0
Exp/Cntr=0.3,0.1

Type RM Length L Ch R = 1 ,48801   ,89,89,89
BEGIN DESCRIPTION:
This cross section corresponds to cross section 48801 of the non-georeferenced CDC model which was the source of this model.
END DESCRIPTION:
XS GIS Cut Line= 3
2453843.513605187003392.909636472449717.273498097004574.50438613
2449548.940173337004648.58068155
#Sta/Elev= 30
     840     440    1022   434.2    1228   431.7    2320   430.6    2320   426.9
    2332   426.9    2358   417.9    2541   417.1    2578   411.2    2681   419.1
    2829   419.5  2851.3   426.9    2861   426.9    2861   430.5    3700   430.3
    3700   426.8  3710.5   426.8    3734     419    4545   422.7    4579   418.1
    4605   411.4  4613.1  399.68  4649.6  396.71  4671.9  402.21    4716   418.9
    4751   422.7    4772  427.08    4793   427.3    4793   434.2    5316   438.8
#Mann= 3 ,0,0
     840    .055       0    4545     .05       0    4751    .055       0
Bank Sta=4545,4751
XS Rating Curve= 0 ,0
Exp/Cntr=0.5,0.3

Type RM Length L Ch R = 3 ,48756   ,,,
BEGIN DESCRIPTION:
SH 348/Northwest Highway
END DESCRIPTION:
Node Name=Northwest Highwa
Bridge Culvert--1,0,-1,-1, 0
Deck Dist Width WeirC Skew NumUp NumDn MinLoCord MaxHiCord MaxSubmerge Is_Ogee
2,86,2.6,0, 41, 41, , , 0.95, 0, ,,,
    2320    2431    2437    2545    2551    2659    2665    2773    2779    2861
    2861    2895    3050    3206    3386    3544    3623    3670    3700    3700
  3710.5    3811    3817    3925    3931    4039    4045    4153    4159    4267
    4273    4381    4387  4468.5  4471.5  4554.5  4557.5  4704.5  4707.5    4772
    4793
   432.8   432.8   432.8   432.8   432.8   432.8   432.8   432.8   432.8   432.8
   430.5   430.3   429.9   429.7   429.7   430.2   430.2   430.3   430.3   432.7
   432.7  432.89  432.91  433.19  433.21  433.59  433.61  433.89  433.91  434.19
  434.21  434.59  434.61  434.89   433.4   433.6  433.61   434.1  434.11   434.4
   434.5
   426.9   426.9   426.9   426.9   426.9   426.9   426.9   426.9   426.9   426.9
   430.5   430.3   429.9   429.7   429.7   430.2   430.2   430.3   430.3   426.8
   426.8  426.99  427.01  427.29  427.31  427.69  427.71  427.99  428.01  428.29
  428.31  428.69  428.71  428.99  426.29  425.91   425.9  426.39  426.42  427.08
   427.3
    2320    2431    2437    2545    2551    2659    2665    2773    2779    2861
    2861    2895    3050    3206    3386    3544    3623    3670    3700    3700
  3710.5    3811    3817    3925    3931    4039    4045    4153    4159    4267
    4273    4381    4387  4468.5  4471.5  4554.5  4557.5  4704.5  4707.5    4772
    4793
   432.8   432.8   432.8   432.8   432.8   432.8   432.8   432.8   432.8   432.8
   430.5   430.3   429.9   429.7   429.7   430.2   430.2   430.3   430.3   432.7
   432.7  432.89  432.91  433.19  433.21  433.59  433.61  433.89  433.91  434.19
  434.21  434.59  434.61  434.89   433.4   433.6  433.61   434.1  434.11   434.4
   434.5
   426.9   426.9   426.9   426.9   426.9   426.9   426.9   426.9   426.9   426.9
   430.5   430.3   429.9   429.7   429.7   430.2   430.2   430.3   430.3   426.8
   426.8  426.99  427.01  427.29  427.31  427.69  427.71  427.99  428.01  428.29
  428.31  428.69  428.71  428.99  426.29  425.91   425.9  426.39  426.42  427.08
   427.3
Pier Skew, UpSta & Num, DnSta & Num=  ,2434, 2 ,2434, 2 , 0 , 0 , 0 ,,
       6       6
     415     430
       6       6
     415     430
Pier Skew, UpSta & Num, DnSta & Num=  ,2548, 2 ,2548, 2 , 0 , 0 , 0 ,,
       6       6
     415     430
       6       6
     415     430
Pier Skew, UpSta & Num, DnSta & Num=  ,2662, 2 ,2662, 2 , 0 , 0 , 0 ,,
       6       6
     415     430
       6       6
     415     430
Pier Skew, UpSta & Num, DnSta & Num=  ,2776, 2 ,2776, 2 , 0 , 0 , 0 ,,
       6       6
     415     430
       6       6
     415     430
Pier Skew, UpSta & Num, DnSta & Num=  ,3814, 2 ,3814, 2 , 0 , 0 , 0 ,,
       6       6
     410     430
       6       6
     410     430
Pier Skew, UpSta & Num, DnSta & Num=  ,3928, 2 ,3928, 2 , 0 , 0 , 0 ,,
       6       6
     410     430
       6       6
     410     430
Pier Skew, UpSta & Num, DnSta & Num=  ,4042, 2 ,4042, 2 , 0 , 0 , 0 ,,
       6       6
     410     430
       6       6
     410     430
Pier Skew, UpSta & Num, DnSta & Num=  ,4156, 2 ,4156, 2 , 0 , 0 , 0 ,,
       6       6
     410     430
       6       6
     410     430
Pier Skew, UpSta & Num, DnSta & Num=  ,4270, 2 ,4270, 2 , 0 , 0 , 0 ,,
       6       6
     410     430
       6       6
     410     430
Pier Skew, UpSta & Num, DnSta & Num=  ,4384, 2 ,4384, 2 , 0 , 0 , 0 ,,
       6       6
     410     430
       6       6
     410     430
Pier Skew, UpSta & Num, DnSta & Num=  ,4470, 2 ,4470, 2 , 0 , 0 , 0 ,,
       3       3
     410     430
       3       3
     410     430
Pier Skew, UpSta & Num, DnSta & Num=  ,4556, 2 ,4556, 2 , 0 , 0 , 0 ,,
       3       3
     410     430
       3       3
     410     430
Pier Skew, UpSta & Num, DnSta & Num=  ,4706, 2 ,4706, 2 , 0 , 0 , 0 ,,
       3       3
     410     430
       3       3
     410     430
BR Coef= 1 , 0 , 0 ,1.05, 0 ,,,0.8,-1,0.5,1,
WSPro=,,,, 1 ,,,, 0 ,,,, 0 ,,,,-1 ,-1 ,-1 , 0 , 0 , 0 , 0 , 0
BC Design=,, 0 ,, 0 ,,,,,,
BC HTab HWMax=440
BC Use User HTab Curves=0
BC User HTab FreeFlow(D)= 0

Type RM Length L Ch R = 1 ,48712   ,1,1,1
BEGIN DESCRIPTION:
This cross section corresponds to cross section 48712 of the non-georeferenced CDC model which was the source of this model.
END DESCRIPTION:
XS GIS Cut Line= 4
2453798.242698347003318.449483542449716.046138357004483.49931879
2449503.06395274 7004561.47160382449499.307726687004562.84660105
#Sta/Elev= 30
     840     440    1022   434.2    1228   431.7    2320   430.6    2320   426.9
    2332   426.9    2358   417.9    2541   417.1    2578   411.2    2681   419.1
    2829   419.5  2851.3   426.9    2861   426.9    2861   430.5    3700   430.3
    3700   426.8  3710.5   426.8    3734     419    4545   422.7    4579   418.1
    4605   411.4  4613.1  399.68  4649.6  396.71  4671.9  402.21    4716   418.9
    4751   422.7    4772  427.08    4793   427.3    4793   434.2    5316   438.8
#Mann= 3 ,0,0
     840    .055       0    4545     .05       0    4751    .055       0
Bank Sta=4545,4751
XS Rating Curve= 0 ,0
Exp/Cntr=0.5,0.3