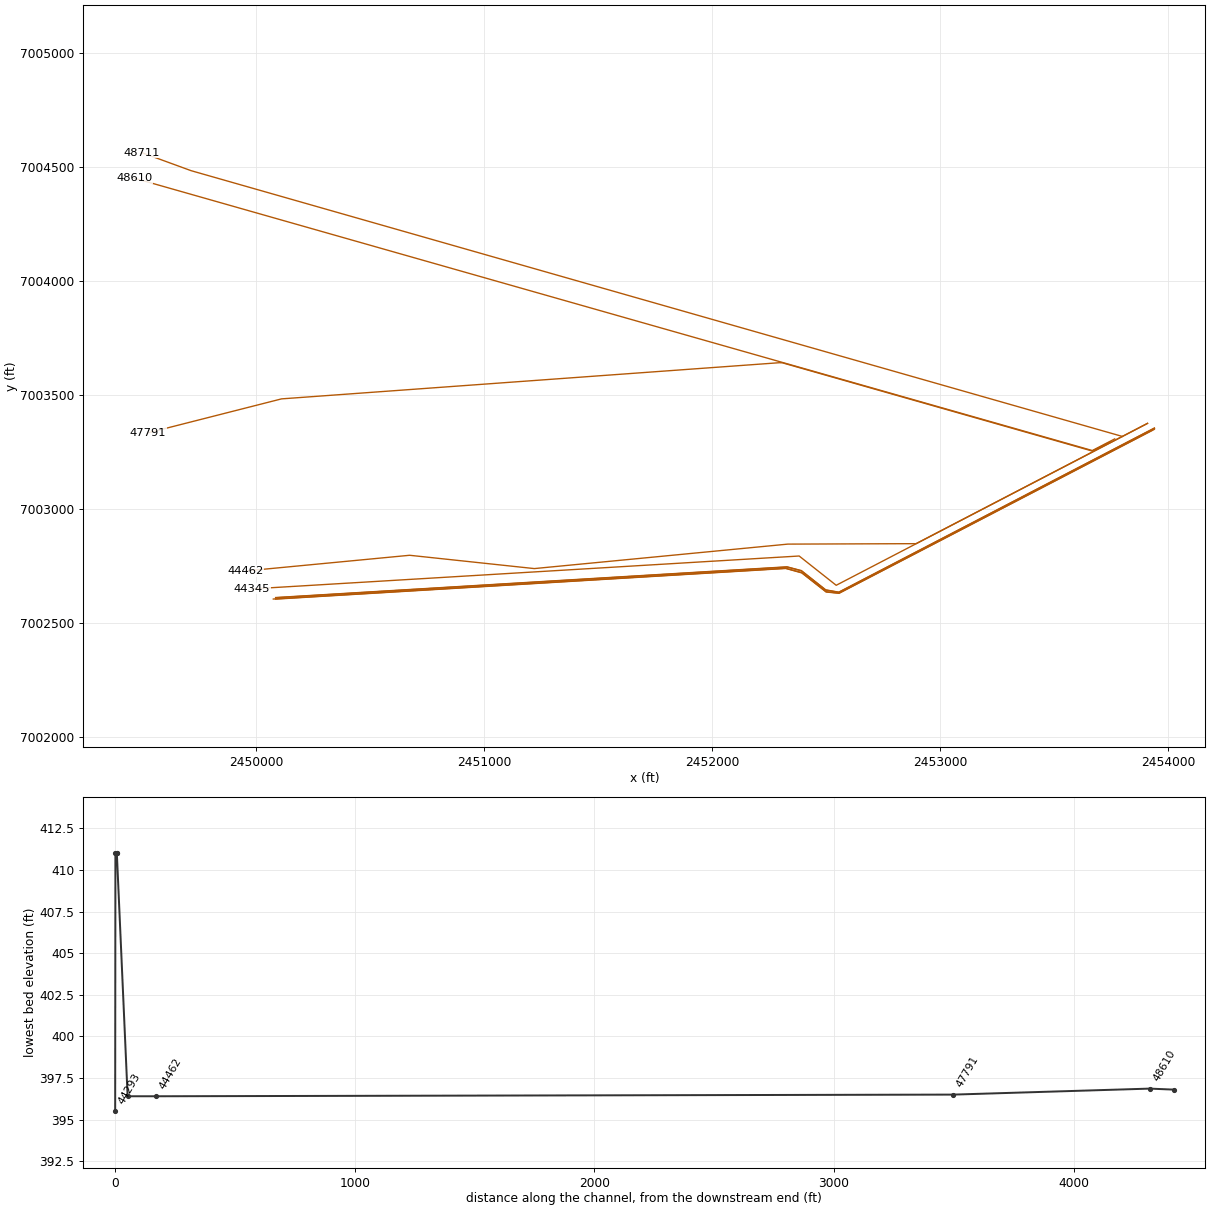
HEC-RAS study CDC_Consolidated_Model.prj: Upper Trinity CDC Consolidated Model

--- CDC_Consolidated_Model.g13 (geometry) --- (continued)

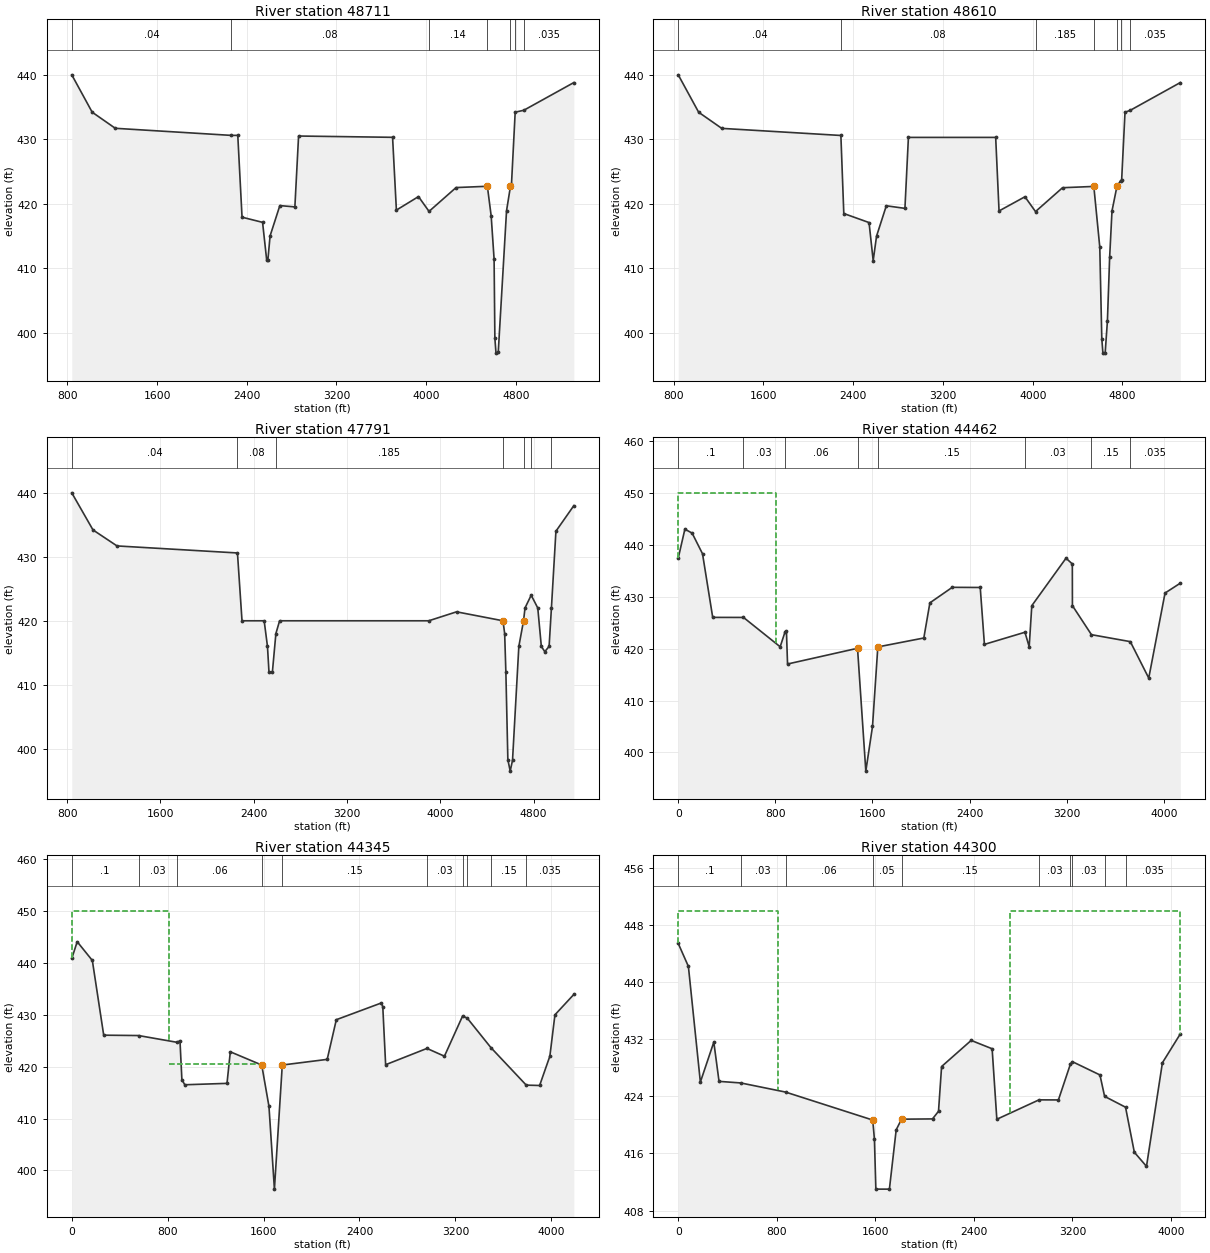
Type RM Length L Ch R = 1 ,48711   ,100,100,100
BEGIN DESCRIPTION:
This cross section corresponds to cross section 48711 of the non-georeferenced CDC model which was the source of this model.
END DESCRIPTION:
XS GIS Cut Line= 4
2453797.939221267003317.554144132449716.026781417004482.47832346
2449502.699452167004560.403036392449498.942569917004561.77540897
#Sta/Elev= 30
     840     440    1022   434.2    1228   431.7    2261   430.6    2320   430.6
    2358   417.9    2541   417.1    2578   411.2    2588   411.2    2608     415
    2695   419.7    2829   419.5    2862   430.5    3700   430.3    3734     419
    3931   421.1    4025   418.8    4266   422.5    4545   422.7    4579   418.1
    4605   411.4    4612   399.1    4622   396.8    4642   396.9    4716   418.9
    4751   422.7    4760     423    4793   434.2    4870   434.5    5316   438.8
#Mann= 7 ,-1,0
     840     .04       0    2261     .08       0    4025     .14       0
    4545     .04       0    4751     .12       0    4793     .06       0
    4870    .035       0
Bank Sta=4545,4751
XS Rating Curve= 0 ,0
Exp/Cntr=0.3,0.1

Type RM Length L Ch R = 1 ,48610   ,600,819,1000
BEGIN DESCRIPTION:
This cross section corresponds to cross section 48610 of the non-georeferenced CDC model which was the source of this model.
END DESCRIPTION:
XS GIS Cut Line= 4
 2453764.65516717003306.71722355 2453757.06069417003302.77366188
2453666.417174587003255.705842632449467.509890027004449.46526614
#Sta/Elev= 30
     840     440    1022   434.2    1228   431.7    2290   430.6    2316   418.5
    2541   417.1    2578   411.2    2608     415    2695   419.7    2861   419.3
    2892   430.3    3670   430.3    3700   418.9    3931   421.1    4025   418.8
    4266   422.5    4545   422.7    4598   413.3    4616   399.1    4626  396.86
    4646  396.86    4666   401.8    4686   411.7    4707   418.9    4751   422.7
    4784   423.6    4793   423.7    4823   434.2    4870   434.5    5316   438.8
#Mann= 7 ,-1,0
     840     .04       0    2290     .08       0    4025    .185       0
    4545     .04       0    4751     .12       0    4784     .06       0
    4870    .035       0
Bank Sta=4545,4751
XS Rating Curve= 0 ,0
Exp/Cntr=0.3,0.1

Type RM Length L Ch R = 1 ,47791   ,1095,3329,880
BEGIN DESCRIPTION:
47791
END DESCRIPTION:
XS GIS Cut Line= 6
  2453744.767739 7003293.9390339 2453666.1320702 7003253.4932486
 2452308.2004028 7003640.1292864 2452294.2509557 7003640.6821068
 2450112.6158833   7003482.20703 2449527.0612801 7003333.1381025
#Sta/Elev= 30
     840     440    1022   434.2    1228   431.7    2261   430.6    2300     420
    2490     420  2518.4     416  2531.2     412  2560.6     412  2590.6     418
  2622.4     420  3901.6     420    4140   421.4  4538.2     420  4552.6     418
  4562.9     412    4580   398.3    4600   396.5    4620   398.2  4674.2     416
  4714.6     420    4727     422    4780     424  4836.5     422    4867     416
  4896.7  415.17  4933.8     416  4953.6     422  4992.2     434  5145.9     438
#Mann= 7 ,-1,0
     840     .04       0    2261     .08       0  2590.6    .185       0
  4538.2     .05       0  4714.6     .12       0    4780     .06       0
  4953.6    .035       0
Bank Sta=4538.2,4714.6
XS Rating Curve= 0 ,0
Exp/Cntr=0.3,0.1

Type RM Length L Ch R = 1 ,44462   ,105,117,120
BEGIN DESCRIPTION:
KHA Added Cross Section
Lidar (TNRIS, 2009)
On-ground topo from Sta 2812-3466
END DESCRIPTION:
XS GIS Cut Line= 6
  2453908.407584 7003374.9057137 2452893.8685223 7002847.5104591
 2452331.8459528 7002845.5573341 2451220.3876195 7002738.2656674
 2450674.0334528 7002796.5990007 2449955.2834528 7002727.8490007
#Sta/Elev= 30
       0  437.42   54.69     443  114.39  442.24  199.99  438.26  283.91  426.01
  537.49     426   839.6  420.35  878.95  423.17  891.09  423.41  900.25  417.03
 1476.69  420.06    1545   396.4    1600     405 1643.93  420.32  2022.7  422.04
 2072.69  428.81 2257.19   431.8 2487.33  431.77 2521.82  420.81 2855.73  423.15
  2890.6  420.34    2912  428.26 3193.85  437.41 3245.83   436.3 3246.58  428.27
 3403.41  422.68 3723.38  421.34 3875.27  414.32 4009.48   430.7 4135.23   432.6
#Mann= 8 ,-1,0
       0      .1       0  537.49     .03       0  878.95     .06       0
 1476.69     .05       0 1643.93     .15       0 2855.73     .03       0
 3403.41     .15       0 3723.38    .035       0
#XS Ineff= 3 ,-1
       0     808     450     808    1476     420    1644 4135.23     420
Permanent Ineff=
       F       F       F
Bank Sta=1476.69,1643.93
XS Rating Curve= 0 ,0
Exp/Cntr=0.3,0.1

Type RM Length L Ch R = 1 ,44345   ,45,45,45
BEGIN DESCRIPTION:
44345
Cross-section EF062.  46 feet upstream of California Crossing Dam.  Effective flow limit set at sta 1350 in LOB, at Las Colinas Levee in ROB. Stemmons North Industrial District in LOB.
Channel data from COD Elm Fork channel survey.
**Updated with 2009 Lidar
**Updated with on-ground topo from sta 2912 to 3573
END DESCRIPTION:
XS GIS Cut Line= 6
 2453908.5928713 7003374.8102632 2453798.2945355 7003317.4527664
 2453675.0293621 7003253.3518447 2452543.7120709 7002665.0419977
 2452381.3360834 7002793.4160848 2449981.8576146 7002649.1909796
#Sta/Elev= 30
       0  440.82   45.35  444.05  171.58  440.44  266.43  426.05  556.81  425.98
   879.9  424.67  902.69  424.99  918.58   417.5  942.66   416.5 1294.99  416.77
 1322.62  422.85 1584.71   420.3    1645  412.34 1690.53   396.4 1756.13   420.3
 2130.83  421.39 2206.97  429.03 2583.23  432.26  2594.7  431.48  2618.3  420.36
 2963.08   423.5 3108.82     422 3259.93  429.72 3298.66  429.35 3495.98  423.67
 3791.36  416.43    3903  416.36 3988.47  422.02 4030.67  429.97 4188.43   433.9
#Mann= 10 ,-1,0
       0      .1       0  556.81     .03       0   879.9     .06       0
 1584.71     .05       0 1756.13     .15       0 2963.08     .03       0
 3259.93    .015       0 3298.66     .03       0 3495.98     .15       0
 3791.36    .035       0
#XS Ineff= 3 ,-1
       0     808     450     810    1583   420.5    1757 4188.43     420
Permanent Ineff=
       F       F       F
Bank Sta=1584.71,1756.13
XS Rating Curve= 0 ,0
Exp/Cntr=0.3,0.1

Type RM Length L Ch R = 1 ,44300   ,1,1,1
BEGIN DESCRIPTION:
44300
One-foot upstream of California Crossing Dam.
Duplication of cross-section 44243.  Effective flow limit set at sta 1350 in LOB, at Las Colinas Levee in ROB.  Ground points from sta 541.8 - 1873.9 generated from topographic file.  Stemmons North Industrial District in LOB.  Ineffective
flow from sta 3210 - 3960 due to structures - elev. set at 450.
Channel data from COD Elm Fork channel survey.
**Updated with 2009 Lidar
**Updated with on-ground topo from sta 2878 to 3531
END DESCRIPTION:
XS GIS Cut Line= 6
 2453938.6220108 7003354.4054484 2452554.9991218 7002634.8908113
 2452497.7403781 7002645.1473525 2452390.9964971 7002729.5385879
 2452327.9894052 7002746.0123082 2450086.7271555 7002611.2970265
#Sta/Elev= 30
       0  445.43   82.48  442.21  179.66     426  288.86   431.6  331.25   426.1
  507.78  425.88  871.57   424.6 1579.22  420.68 1592.94  417.98 1604.55     411
 1714.55     411 1769.68  419.32 1813.25   420.8 2064.55  420.84 2113.21  421.91
 2138.26  428.18 2378.41  431.84 2548.59  430.67 2586.81  420.79  2929.1  423.51
 3086.74   423.5 3183.59  428.49 3200.35  428.86 3424.02     427 3461.73     424
 3631.73  422.48 3703.15  416.17 3801.92  414.19 3931.16  428.71 4076.47  432.75
#Mann= 10 ,-1,0
       0      .1       0  507.78     .03       0  871.57     .06       0
 1579.22     .05       0 1813.25     .15       0  2929.1     .03       0
 3183.59    .015       0 3200.35     .03       0 3461.73     .15       0
 3631.73    .035       0
#XS Ineff= 4 ,-1
       0     808     450     872    1579   420.5  1813.5    2690   420.5
    2690 4076.47     450
Permanent Ineff=
       F       F       F       F
Bank Sta=1579.22,1813.25
XS Rating Curve= 0 ,0
Exp/Cntr=0.3,0.1

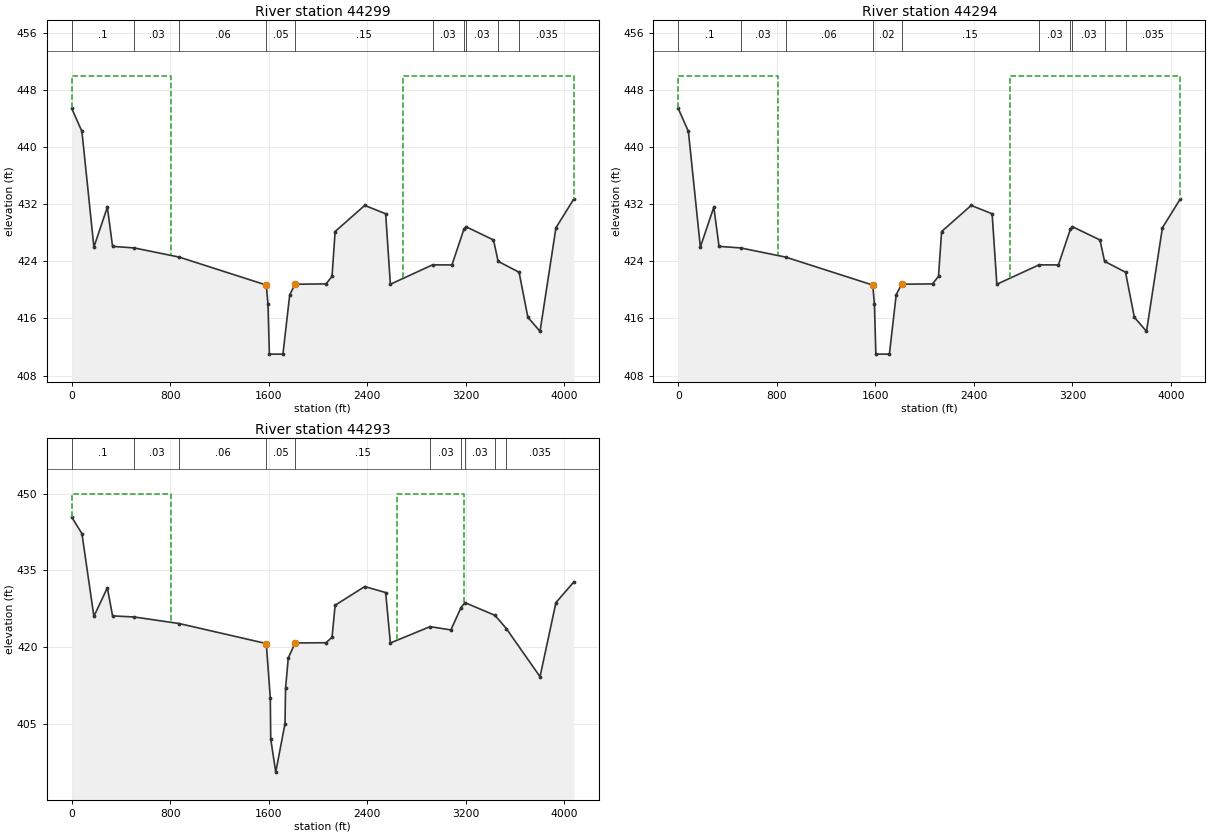
Type RM Length L Ch R = 1 ,44299   ,5,5,5
BEGIN DESCRIPTION:
44299
California Crossing Dam
**Updated with 2009 Lidar
**Updated with on-ground topo from sta 2878 to 3531
END DESCRIPTION:
XS GIS Cut Line= 6
  2453938.599373 7003353.5931141 2452555.1621793 7002634.1752615
 2452498.0097345 7002643.7844943  2452391.271759 7002728.0713992
 2452328.4808741 7002744.9591607 2450086.6179038 7002610.3085114
#Sta/Elev= 30
       0  445.43   82.48  442.21  179.66     426  288.86   431.6  331.25   426.1
  507.78  425.88  871.57   424.6 1579.22  420.68 1592.94  417.98 1604.55     411
 1714.55     411 1769.68  419.32 1813.25   420.8 2064.55  420.84 2113.21  421.91
 2138.26  428.18 2378.41  431.84 2548.59  430.67 2586.81  420.79  2929.1  423.51
 3086.74   423.5 3183.59  428.49 3200.35  428.86 3424.02     427 3461.73     424
 3631.73  422.48 3703.15  416.17 3801.92  414.19 3931.16  428.71 4076.47  432.75
#Mann= 10 ,-1,0
       0      .1       0  507.78     .03       0  871.57     .06       0
 1579.22     .05       0 1813.25     .15       0  2929.1     .03       0
 3183.59    .015       0 3200.35     .03       0 3461.73     .15       0
 3631.73    .035       0
#XS Ineff= 4 ,-1
       0     808     450     872    1579   420.5  1813.5    2690   420.5
    2690 4076.47     450
Permanent Ineff=
       F       F       F       F
Bank Sta=1579.22,1813.25
XS Rating Curve= 0 ,0
Exp/Cntr=0.3,0.1

Type RM Length L Ch R = 1 ,44294   ,1,1,1
BEGIN DESCRIPTION:
44294
California Crossing Dam
Weir crest elev. 411.0, weir length 170 feet.  Effective flow limit set at sta 1350 in LOB, at Las Colinas Levee in ROB.  Ground points from sta 541.8 - 1873.9 generated from topographic file.  Stemmons North Industrial District in LOB. Ineffective flow from sta 3210 - 3960 due to structures - elev. set at 450.0.
**Updated with 2009 Lidar
**Updated with on-ground topo from sta 2878 to 3531
END DESCRIPTION:
XS GIS Cut Line= 6
 2453929.6134986 7003344.9182626 2452555.9656553 7002630.5906231
 2452499.3601255 7002636.9731562 2452392.6533179 7002720.7302066
 2452322.2951909 7002739.7770845  2450076.272452 7002604.7760421
#Sta/Elev= 30
       0  445.43   82.48  442.21  179.66     426  288.86   431.6  331.25   426.1
  507.78  425.88  871.57   424.6 1579.22  420.68 1592.94  417.98 1604.55     411
 1714.55     411 1769.68  419.32 1813.25   420.8 2064.55  420.84 2113.21  421.91
 2138.26  428.18 2378.41  431.84 2548.59  430.67 2586.81  420.79  2929.1  423.51
 3086.74   423.5 3183.59  428.49 3200.35  428.86 3424.02     427 3461.73     424
 3631.73  422.48 3703.15  416.17 3801.92  414.19 3931.16  428.71 4076.47  432.75
#Mann= 10 ,-1,0
       0      .1       0  507.78     .03       0  871.57     .06       0
 1579.22     .02       0 1813.25     .15       0  2929.1     .03       0
 3183.59    .015       0 3200.35     .03       0 3461.73     .15       0
 3631.73    .035       0
#XS Ineff= 4 ,-1
       0     808     450     872    1579   420.5  1813.5    2690   420.5
    2690 4076.47     450
Permanent Ineff=
       F       F       F       F
Bank Sta=1579.22,1813.25
XS Rating Curve= 0 ,0
Exp/Cntr=0.3,0.1

Type RM Length L Ch R = 1 ,44293   ,7,7,7
BEGIN DESCRIPTION:
44293
Duplication of cross-section 44243.  One-foot downstream of California Crossing Dam.
**Updated with 2009 Lidar
**Updated with on-ground topo from sta 2878 to 3531
END DESCRIPTION:
XS GIS Cut Line= 6
 2453938.4628903 7003348.7194361 2452556.1146052 7002629.8678555
 2452499.6347313 7002635.6129227 2452392.9364539 7002719.2564562
 2452322.8391531  7002738.814488 2450086.2163298 7002604.3912004
#Sta/Elev= 30
       0  445.43   82.48  442.21  179.66     426  288.86   431.6  331.25   426.1
  507.78  425.88  871.57   424.6 1579.22  420.68 1611.93     410 1615.35     402
  1656.2   395.5 1731.22     405  1735.9  411.93  1757.8  417.84 1813.25   420.8
 2064.55  420.84 2113.21  421.91 2138.26  428.18 2378.41  431.84 2548.59  430.67
 2586.81  420.79 2909.15  423.99 3078.27  423.35 3160.32  427.72  3191.6   428.7
 3436.61   426.2 3528.72   423.6 3801.92  414.19 3931.16  428.71 4076.47  432.75
#Mann= 10 ,-1,0
       0      .1       0  507.78     .03       0  871.57     .06       0
 1579.22     .05       0 1813.25     .15       0 2909.15     .03       0
 3160.32    .015       0  3191.6     .03       0 3436.61     .15       0
 3528.72    .035       0
#XS Ineff= 5 ,-1
       0     808     450     872    1579   420.5  1813.5    2643   420.5
    2643    3185     450    3185 4076.47     422
Permanent Ineff=
       F       F       F       F       F
Bank Sta=1579.22,1813.25
XS Rating Curve= 0 ,0
Exp/Cntr=0.3,0.1