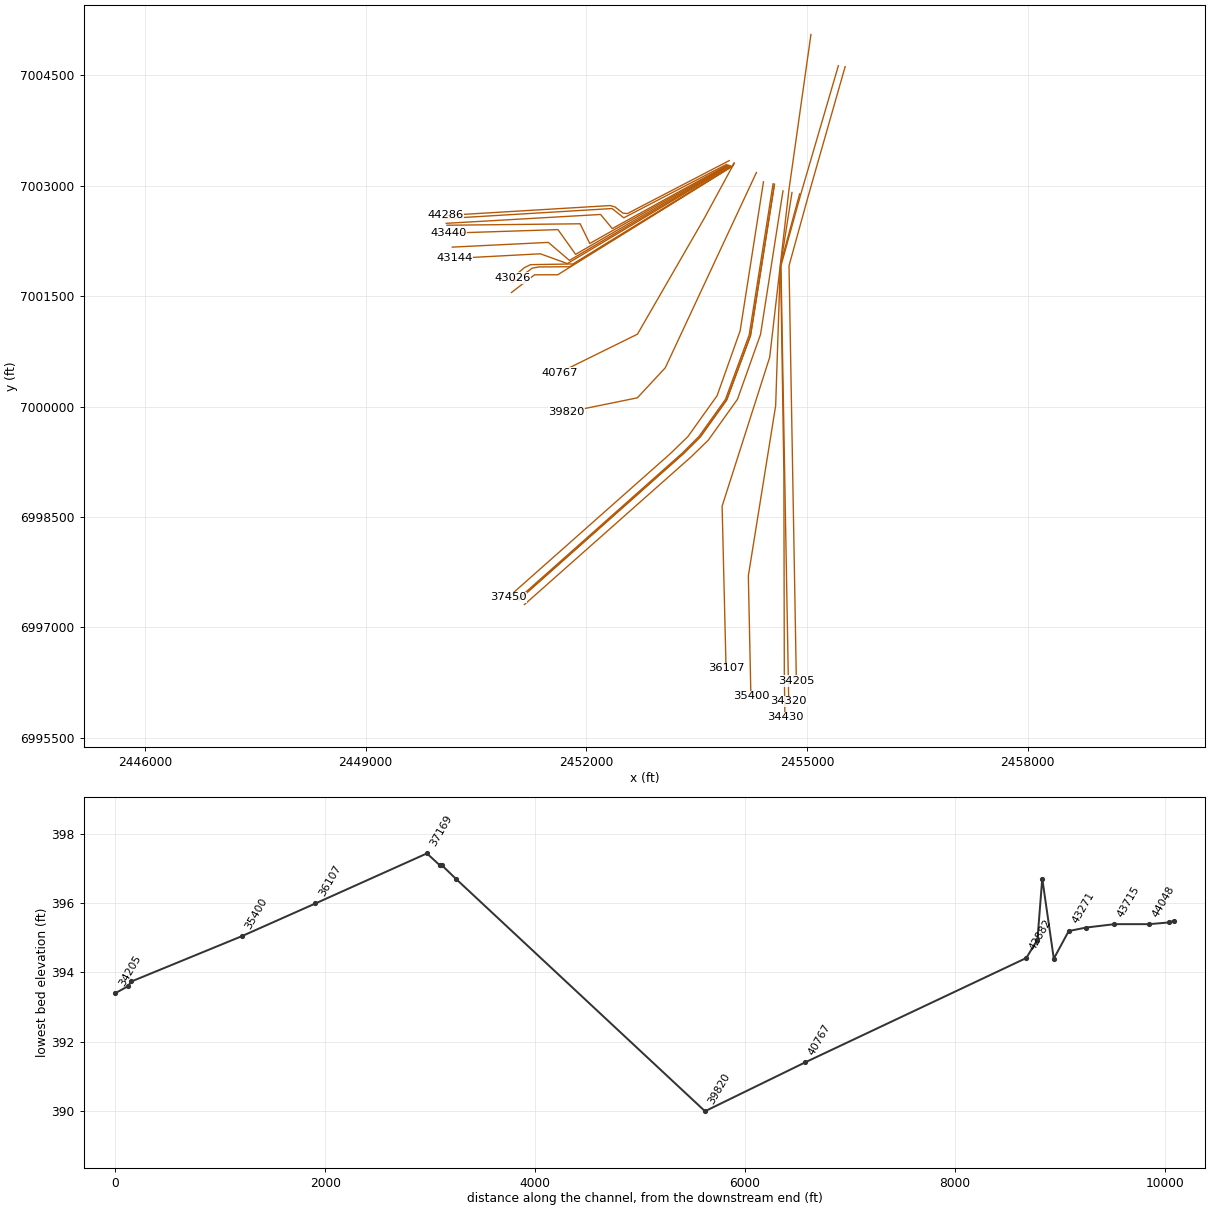
HEC-RAS study CDC_Consolidated_Model.prj: Upper Trinity CDC Consolidated Model

--- CDC_Consolidated_Model.g13 (geometry) --- (continued)

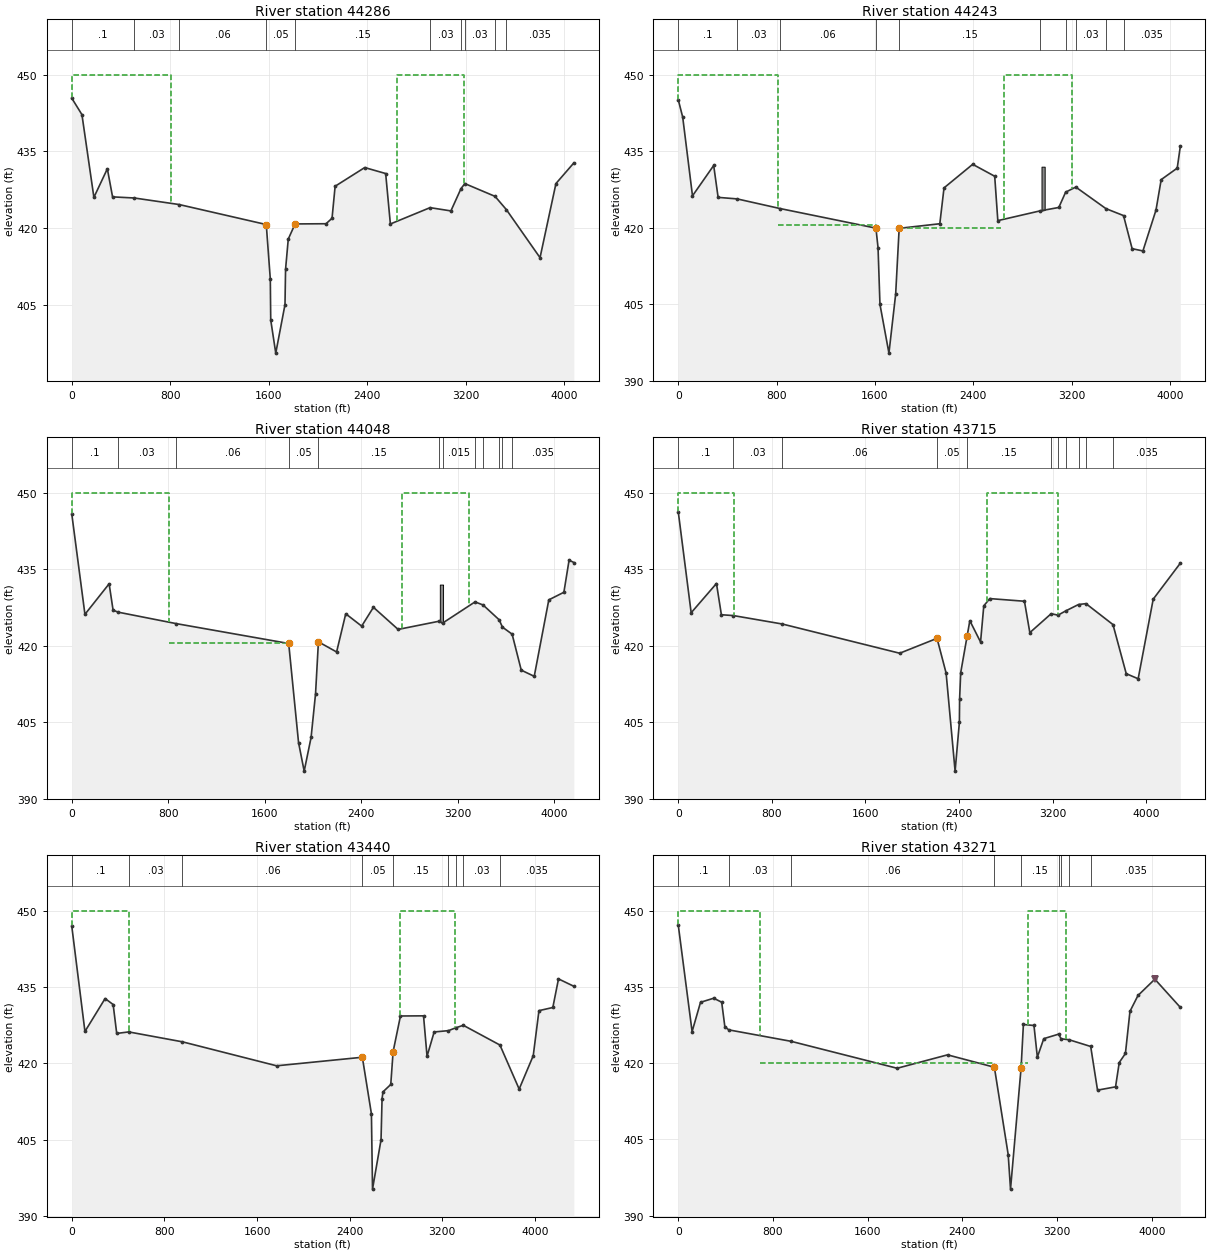
Type RM Length L Ch R = 1 ,44286   ,43,43,43
BEGIN DESCRIPTION:
KHA Added Cross Section
**Updated with 2009 Lidar
**Updated with on-ground topo from sta 2878 to 3531
END DESCRIPTION:
XS GIS Cut Line= 6
  2453941.692468  7003342.508975 2452557.4878334  7002622.692052
 2452496.9106353 7002628.8538943  2452389.619639 7002712.9620754
 2452322.9694148 7002731.8096858 2450086.6362791 7002597.4038087
#Sta/Elev= 30
       0  445.43   82.48  442.21  179.66     426  288.86   431.6  331.25   426.1
  507.78  425.88  871.57   424.6 1579.22  420.68 1611.93     410 1615.35     402
  1656.2   395.5 1731.22     405  1735.9  411.93  1757.8  417.84 1813.25   420.8
 2064.55  420.84 2113.21  421.91 2138.26  428.18 2378.41  431.84 2548.59  430.67
 2586.81  420.79 2909.15  423.99 3078.27  423.35 3160.32  427.72  3191.6   428.7
 3436.61   426.2 3528.72   423.6 3801.92  414.19 3931.16  428.71 4076.47  432.75
#Mann= 10 ,-1,0
       0      .1       0  507.78     .03       0  871.57     .06       0
 1579.22     .05       0 1813.25     .15       0 2909.15     .03       0
 3160.32    .015       0  3191.6     .03       0 3436.61     .15       0
 3528.72    .035       0
#XS Ineff= 5 ,-1
       0     808     450     872    1579   420.5  1813.5    2643   420.5
    2643    3185     450    3185 4076.47     422
Permanent Ineff=
       F       F       F       F       F
Bank Sta=1579.22,1813.25
XS Rating Curve= 0 ,0
Exp/Cntr=0.3,0.1

Type RM Length L Ch R = 1 ,44243   ,65,190,228
BEGIN DESCRIPTION:
44243
Cross-section EF060.  51 feet downstream of California Crossing Dam. Effective flow limit set at sta 1350 in LOB, at Las Colinas Levee in ROB. Ground points from sta 541.8 - 1873.9 generated from topographic file.  Stemmons North Industrial District in LOB.  Ineffective flow from sta 3175 - 3725 due to structures - elev. set at 450.0.
Channel data from COD Elm Fork channel survey.
**Updated with 2009 Lidar
**Updated with on-ground topo from sta 2892 to 3545
END DESCRIPTION:
XS GIS Cut Line= 4
 2453901.8382917 7003289.6506566  2452508.743965 7002565.2111606
 2452349.2488772 7002691.3070371 2450062.6940671 7002553.8693198
#Sta/Elev= 30
       0  445.13   36.31  441.71  115.91  426.28  288.29  432.23   324.3  425.98
  478.97  425.68  827.95  423.79 1607.55  419.95 1624.84  416.13 1640.48     405
 1713.39  395.45 1768.12     407 1796.61  419.91 2127.19  420.81 2161.42  427.84
 2394.63  432.46 2573.56  430.12 2598.91  421.42  2941.9  423.33 3094.82     424
 3150.38     427    3233     428 3478.31  423.77 3621.15  422.41 3691.14  415.92
 3778.91  415.48 3885.21  423.49 3927.45  429.46 4057.87  431.71 4082.96  435.97
#Mann= 10 ,-1,0
       0      .1       0  478.97     .03       0  827.95     .06       0
 1607.55     .05       0 1796.61     .15       0  2941.9     .03       0
 3150.38    .015       0    3233     .03       0 3478.31     .15       0
 3621.15    .035       0
#XS Ineff= 5 ,-1
       0     808     450     808    1607   420.5    1797    2622     420
    2650    3199     450    3199 4082.96     422
Permanent Ineff=
       F       F       F       T       F
#Block Obstruct= 1 ,-1
    2954    2980     432
Bank Sta=1607.55,1796.61
XS Rating Curve= 0 ,0
Exp/Cntr=0.3,0.1

Type RM Length L Ch R = 1 ,44048   ,28,331,108
BEGIN DESCRIPTION:
KHA Added Cross Section
**Updated with 2009 Lidar
**Updated with on-ground topo from sta 2993 to 3645
END DESCRIPTION:
XS GIS Cut Line= 4
   2453916.230467003282.372387562452352.102856557002418.76561673
2452193.682717687002610.822908392450096.026467657002490.56104495
#Sta/Elev= 30
       0  445.86  109.14  426.16  309.66  432.15  342.59  426.97  385.78  426.58
  866.01  424.34 1798.33  420.44    1880     401 1926.66   395.4 1983.88     402
 2020.87  410.57 2044.66  420.77 2195.48  418.78 2271.25  426.27 2403.24  423.85
 2500.75  427.54 2705.59   423.2 3042.92   424.8 3074.15  424.44 3342.94   428.6
 3409.47     428 3542.59   425.1 3570.34  423.65 3650.53  422.27 3726.14  415.21
 3833.79     414 3954.59     429 4079.63  430.49 4122.73  436.79 4162.17  436.33
#Mann= 12 ,-1,0
       0      .1       0  385.78     .03       0  866.01     .06       0
 1798.33     .05       0 2044.66     .15       0 3042.92     .03       0
 3074.15    .015       0 3342.94     .03       0 3409.47    .015       0
 3542.59     .03       0 3570.34     .15       0 3650.53    .035       0
#XS Ineff= 5 ,-1
       0     808     450     808    1798   420.5    2045    2642   420.5
    2737    3290     450    3290 4162.17     422
Permanent Ineff=
       F       F       F       F       F
#Block Obstruct= 1 ,-1
    3051    3078     432
Bank Sta=1798.33,2044.66
XS Rating Curve= 0 ,0
Exp/Cntr=0.3,0.1

Type RM Length L Ch R = 1 ,43715   ,34,274,84
BEGIN DESCRIPTION:
KHA Added Cross Section
**Updated with 2009 Lidar
**Updated with on-ground topo from sta 3137 to 3780
END DESCRIPTION:
XS GIS Cut Line= 4
  2453927.970912 7003280.1733135 2452046.3736899 7002215.9806051
 2451915.6445233 7002484.2097718 2450105.2278566 7002464.4181051
#Sta/Elev= 30
       0  446.32  110.53  426.47  326.78  432.21  368.84  426.08  470.94  425.92
  890.15  424.26 1893.09  418.53 2212.08  421.45 2289.85  414.64  2366.7   395.4
 2403.38     405 2405.16  409.54 2414.62  414.72  2469.4  421.88 2492.61  424.91
 2584.26  420.73 2611.92  427.83 2663.18  429.25 2959.47  428.73 3005.48  422.57
 3187.71  426.28 3246.66     426 3311.96  426.83 3421.77  428.09 3485.37  428.26
 3716.23  424.15 3829.52  414.52 3931.47  413.52 4060.18  429.14 4291.82  436.19
#Mann= 11 ,-1,0
       0      .1       0  470.94     .03       0  890.15     .06       0
 2212.08     .05       0  2469.4     .15       0 3187.71     .03       0
 3246.66    .015       0 3311.96     .03       0 3421.77    .015       0
 3485.37     .03       0 3716.23    .035       0
#XS Ineff= 5 ,-1
       0     480     450     480    2212     420    2470    2636     420
    2636    3242     450    3242    4200     422
Permanent Ineff=
       F       F       F       F       F
Bank Sta=2212.08,2469.4
XS Rating Curve= 0 ,0
Exp/Cntr=0.3,0.1

Type RM Length L Ch R = 1 ,43440   ,29,162,178
BEGIN DESCRIPTION:
KHA Added Cross Section
**Updated with 2009 Lidar
**Updated with on-ground topo from sta 3203 to 3750
END DESCRIPTION:
XS GIS Cut Line= 4
  2453937.085495 7003276.2670635 2451854.0993843  7002068.493626
 2451614.3424399 7002404.9519593 2450122.6757733 7002356.5144593
#Sta/Elev= 30
       0  446.99  113.77  426.29  287.96  432.76  357.43  431.58  388.21   425.9
  492.09   426.2  956.27  424.25 1769.19  419.54 2509.69  421.22    2588   410.1
 2597.52   395.3 2671.07     405 2679.97  413.09 2687.96  414.42  2755.1  415.87
 2775.43  422.32 2838.84  429.33 3038.12  429.36  3068.5  421.41 3129.88  426.19
 3253.73  426.45    3315     427    3382   427.5 3698.03  423.62 3864.14  414.97
 3985.63  421.52 4035.02  430.38 4154.88     431  4203.8  436.62 4336.37  435.17
#Mann= 9 ,-1,0
       0      .1       0  492.09     .03       0  956.27     .06       0
 2509.69     .05       0 2775.43     .15       0 3253.73     .03       0
    3315    .015       0    3382     .03       0 3698.03    .035       0
#XS Ineff= 5 ,-1
       0     492     450     492    2509     420    2776    2839     420
    2839    3307     450    3307    4200     422
Permanent Ineff=
       F       F       F       F       F
Bank Sta=2509.69,2775.43
XS Rating Curve= 0 ,0
Exp/Cntr=0.3,0.1

Type RM Length L Ch R = 1 ,43271   ,24,142,152
BEGIN DESCRIPTION:
KHA Added Cross Section
**Updated with 2009 Lidar
**Updated with on-ground topo from sta 3162 to 3528
END DESCRIPTION:
XS GIS Cut Line= 4
  2453947.5021627003272.360813482451770.505634347001986.39727181
2451483.005634377002231.188938472450177.797300997002167.12643845
#Sta/Elev= 30
       0  447.24  117.05  426.22  188.26  431.99  299.31  432.79  366.94  432.01
  393.62  427.19  426.61  426.56   952.1  424.31 1848.67     419 2274.07  421.64
 2669.76   419.2 2786.43     402 2806.08   395.2 2895.31  419.07 2914.85  427.62
  3004.1  427.42 3032.62  421.19 3086.97  424.83 3212.47  425.72  3232.9   424.8
 3301.26  424.61 3483.14  423.29 3540.84  414.69 3692.99  415.34 3724.32  420.13
 3776.37  421.91 3814.81  430.21 3882.59  433.33 4024.87  436.54 4239.95  430.99
#Mann= 9 ,-1,0
       0      .1       0  426.61     .03       0   952.1     .06       0
 2669.76     .05       0 2895.31     .15       0 3212.47     .03       0
  3232.9    .015       0 3301.26     .03       0 3483.14    .035       0
Levee=0,,,-1,4024.87,436.54,,
#XS Ineff= 5 ,-1
       0     693     450     693    2669     420  2895.5    2950     420
    2950    3274     450    3274    4200     422
Permanent Ineff=
       F       F       F       F       F
Bank Sta=2669.76,2895.31
XS Rating Curve= 0 ,0
Exp/Cntr=0.3,0.1

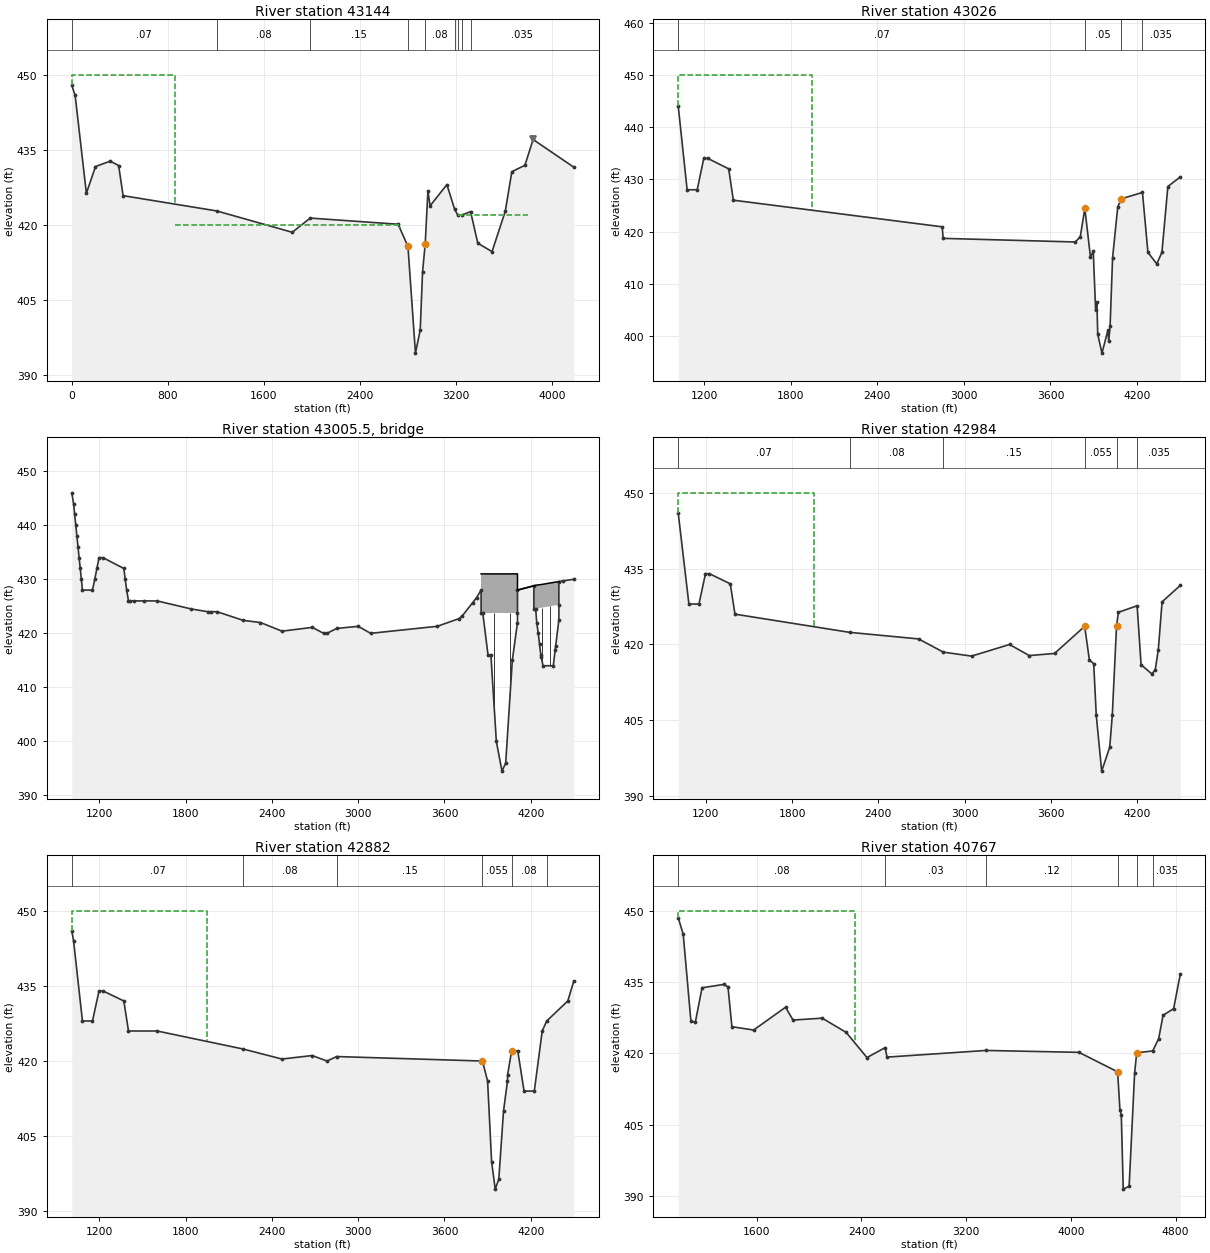
Type RM Length L Ch R = 1 ,43144   ,110,110,110
BEGIN DESCRIPTION:
43144
Cross-section EF059.  Effective flow limit set at sta 1950 in LOB, at Las Colinas Levee in ROB.  Ground points from sta 1007.8 - 3086.6 generated from topographic file.  Stemmons North Industrial District in LOB.
Channel data from COD Elm Fork channel survey.
**Updated with 2009 Lidar
**Updated with on-ground topo from sta 3130 to 3363
-----------------------------------------------
CDC IRV 053119-1 Las Colinas Dog Park
-----------------
Cross-section 43144 - 44462
Project located in ROB.
END DESCRIPTION:
XS GIS Cut Line= 4
  2453960.522995 7003269.7566468 2451741.6644886 7001942.9510912
 2451374.4769886 7002076.2844246 2450203.6436552 7002013.7844246
#Sta/Elev= 30
       0  447.88   27.99  445.92  121.66  426.32  197.37  431.67  320.24  432.76
  390.08  431.87  427.23  425.86 1206.23  422.81 1835.53  418.54 1984.66  421.38
 2716.33  420.15 2798.15  415.71 2860.67   394.4 2900.28     399  2919.6  410.58
 2941.74   416.2  2964.4  426.79 2982.28  423.82 3122.33  428.07 3186.65  423.16
 3212.01     422 3245.19  421.97 3319.63  422.67  3379.5  416.36 3498.06  414.68
 3608.26  422.74 3662.77  430.64 3771.88  431.93  3839.8  437.08    4179  431.54
#Mann= 9 ,-1,0
       0     .07       0 1206.23     .08       0 1984.66     .15       0
 2798.15     .05       0 2941.74     .08       0 3186.65     .03       0
 3212.01    .015       0 3245.19     .03       0 3319.63    .035       0
Levee=0,,,-1,3839.8,437.08,,
#XS Ineff= 3 ,-1
       0     861     450     861  2728.5     420  3215.6    3800     422
Permanent Ineff=
       F       F       F
Bank Sta=2798.15,2941.74
XS Rating Curve= 0 ,0
Exp/Cntr=0.3,0.1

Type RM Length L Ch R = 1 ,43026   ,46,46,46
BEGIN DESCRIPTION:
This cross section corresponds to cross section 43026 of the non-georeferenced CDC model which was the source of this model.
---------------------------------------------------------------------
CDC DAL071508-1 California Crossing
Cross-section 42984 - 43026
---------------------------------------------------------------------
Cross-section was imported from Geopak.
END DESCRIPTION:
XS GIS Cut Line= 6
2454008.696345697003310.946545792453987.395207177003270.87543172
 2451817.26732967001938.14548564 2451241.2389541 7001928.7367118
2451157.605263087001887.965139812450991.633810257001747.51069631
#Sta/Elev= 30
  1020.4     444    1082     428  1151.9     428  1197.3     434  1225.2     434
    1370     432  1402.3     426    2850   420.9 2856.34  418.69 3772.38     418
 3806.94  419.01 3838.27  424.44 3877.32   415.1  3896.7  416.22 3913.15  404.89
 3921.92  406.44 3927.63  400.32    3957  396.72 3998.06  401.09 4003.98  399.05
 4013.35  401.85 4030.62     415 4066.61  424.74  4091.7  426.27 4237.68  427.48
 4275.57     416 4336.88  413.81  4372.5  415.99 4413.74  428.62    4500  430.46
#Mann= 4 ,-1,0
  1020.4     .07       0 3838.27     .05       0  4091.7     .08       0
 4237.68    .035       0
#XS Ineff= 2 , 0
            1950     450
Permanent Ineff=
       F       F
Bank Sta=3838.27,4091.7
XS Rating Curve= 0 ,0
Exp/Cntr=0.5,0.3

Type RM Length L Ch R = 3 ,43005.5 ,,,
BEGIN DESCRIPTION:
California Crossing Road
Data from TXDOT bridge plans 2008.
END DESCRIPTION:
Node Name=California Cross
Bridge Culvert--1,0,-1,-1, 0
Deck Dist Width WeirC Skew NumUp NumDn MinLoCord MaxHiCord MaxSubmerge Is_Ogee
1.25,42.5,2.6,0, 13, 13, , , 0.95, 0, ,,,
    3855    4108    4108    4108 4221.94 4221.94 4234.44 4270.74 4273.44 4370.44
 4373.44 4373.44 4395.94
     431     431     428     428   428.8   428.8   428.9  429.02  429.03  429.47
  429.48  429.48  429.56
   423.7   423.7   423.7     428   428.8   424.5  424.56  424.72  424.73  425.17
  425.18  425.18  425.26
    3855    4108    4108    4108 4221.94 4221.94 4234.44 4270.74 4273.44 4370.44
 4373.44 4373.44 4395.94
     431     431     428     428   428.8   428.8   428.9  429.02  429.03  429.47
  429.48  429.48  429.56
   423.7   423.7   423.7     428   428.8   424.5  424.56  424.72  424.73  425.17
  425.18  425.18  425.26
Pier Skew, UpSta & Num, DnSta & Num=  ,3946, 2 ,3946, 2 , 0 , 0 , 0 ,,
     3.5     3.5
     405     425
     3.5     3.5
     405     425
Pier Skew, UpSta & Num, DnSta & Num=  ,4056, 2 ,4056, 2 , 0 , 0 , 0 ,,
     3.5     3.5
     405     425
     3.5     3.5
     405     425
Pier Skew, UpSta & Num, DnSta & Num=  ,4278.438, 2 ,4278.438, 2 , 0 , 0 , 0 ,,
       3       3
     405     425
       3       3
     405     425
Pier Skew, UpSta & Num, DnSta & Num=  ,4334.94, 2 ,4334.94, 2 , 0 , 0 , 0 ,,
       3       3
     405     426
       3       3
     405     426
BR Coef= 1 , 0 , 0 ,1.05, 0 ,,,0.8,-1,0.5,1,
WSPro=,,,, 1 ,,,, 0 ,,,, 0 ,,,,-1 ,-1 ,-1 , 0 , 0 , 0 , 0 , 0
BR U #Sta/Elev= 70
  1007.8     446  1020.4     444  1028.1     442  1035.8     440  1043.5     438
  1051.2     436  1058.8     434  1066.7     432  1074.5     430    1082     428
  1151.9     428  1167.6     430  1182.5     432  1197.3     434  1225.2     434
    1370     432  1379.6     430  1389.7     428  1402.3     426  1415.5     426
  1442.6     426  1509.2     426  1601.7     426    1840   424.5  1953.8     424
  1977.8     424  2018.2     424    2200   422.4  2320.3     422    2470   420.4
    2680   421.1  2759.6     420  2783.4     420    2850   420.9    3000   421.3
  3086.6     420    3550   421.3    3699   422.7    3723   423.2    3797   425.7
    3823   426.6    3855     428    3855   423.7  3866.9   423.7    3903     416
    3923     416    3961     400    4000   394.5    4026     396    4072     415
    4108     422    4108   423.7    4108     428 4221.94   428.8 4221.94   424.5
 4234.44  424.56 4241.94     422 4252.34     420 4261.34     418 4270.44     416
 4273.44  415.61 4285.74     414 4356.94     414 4370.44     417 4373.44   417.6
 4395.94  422.51 4395.94  425.26 4395.94  429.56 4421.94   429.7    4500     430
BR U #Mann= 1
  1007.8     .05
BR U Banks=3866.9,4108
BR D #Sta/Elev= 70
  1007.8     446  1020.4     444  1028.1     442  1035.8     440  1043.5     438
  1051.2     436  1058.8     434  1066.7     432  1074.5     430    1082     428
  1151.9     428  1167.6     430  1182.5     432  1197.3     434  1225.2     434
    1370     432  1379.6     430  1389.7     428  1402.3     426  1415.5     426
  1442.6     426  1509.2     426  1601.7     426    1840   424.5  1953.8     424
  1977.8     424  2018.2     424    2200   422.4  2320.3     422    2470   420.4
    2680   421.1  2759.6     420  2783.4     420    2850   420.9    3000   421.3
  3086.6     420    3550   421.3    3699   422.7    3723   423.2    3797   425.7
    3823   426.6    3855     428    3855   423.7  3866.9   423.7    3903     416
    3923     416    3961     400    4000   394.5    4026     396    4072     415
    4108     422    4108   423.7    4108     428 4221.94   428.8 4221.94   424.5
 4234.44  424.56 4241.94     422 4252.34     420 4261.34     418 4270.44     416
 4273.44  415.61 4285.74     414 4356.94     414 4370.44     417 4373.44   417.6
 4395.94  422.51 4395.94  425.26 4395.94  429.56 4421.94   429.7    4500     430
BR D #Mann= 1
  1007.8     .05
BR D Banks=3866.9,4108
BC Design=,, 0 ,, 0 ,,,,,,
BC HTab HWMax=446
BC Use User HTab Curves=0
BC User HTab FreeFlow(D)= 0

Type RM Length L Ch R = 1 ,42984   ,106,106,106
BEGIN DESCRIPTION:
This cross section corresponds to cross section 42984 of the non-georeferenced CDC model which was the source of this model.
---------------------------------------------------------------------
CDC DAL071508-1 California Crossing
Cross-section 42984 - 43026
---------------------------------------------------------------------
Cross-section was imported from Geopak.
END DESCRIPTION:
XS GIS Cut Line= 6
2454006.047400837003304.068934892453987.987069527003270.23829389
2451773.359609017001900.510062222451355.190169757001897.37391363
2451264.302884347001881.240415722450992.833939087001679.36352289
#Sta/Elev= 30
  1007.8     446    1082     428  1151.9     428  1197.3     434  1225.2     434
    1370     432  1402.3     426    2200   422.4    2680   421.1 2851.44  418.49
 3047.67   417.7 3312.26     420 3449.05  417.81 3625.17  418.22 3834.86   423.6
 3867.21     417 3897.69  416.17 3915.39     406 3953.03  394.95 4009.07  399.68
 4026.88     406 4056.57   423.7 4069.38  426.37 4199.62  427.66 4227.09     416
 4301.84  414.18 4325.73     415 4347.02     419 4373.27  428.44    4500  431.69
#Mann= 6 ,-1,0
  1007.8     .07       0    2200     .08       0 2851.44     .15       0
 3834.86    .055       0 4056.57     .08       0 4199.62    .035       0
#XS Ineff= 2 , 0
            1950     450
Permanent Ineff=
       F       F
Bank Sta=3834.86,4056.57
XS Rating Curve= 0 ,0
Exp/Cntr=0.5,0.3

Type RM Length L Ch R = 1 ,42882   ,796,2104,1343
BEGIN DESCRIPTION:
This cross section corresponds to cross section 42882 of the non-georeferenced CDC model which was the source of this model.
END DESCRIPTION:
XS GIS Cut Line= 4
2453974.397201667003259.504391462451611.506914357001791.61001755
2451295.09809834 7001790.61297232450982.647935847001550.47532922
#Sta/Elev= 30
  1007.8     446  1020.4     444    1082     428  1151.9     428  1197.3     434
  1225.2     434    1370     432  1402.3     426  1601.7     426    2200   422.4
    2470   420.4    2680   421.1  2783.4     420    2850   420.9  3864.3     420
  3900.1     416    3928   399.9    3953  394.42    3978   396.4  4010.8     410
  4038.4     416    4039   417.2    4067     422    4110     422  4153.8     414
    4225     414    4280     426  4311.3     428  4457.9     432    4500     436
#Mann= 6 ,-1,0
  1007.8     .07       0    2200     .08       0    2850     .15       0
  3864.3    .055       0    4067     .08       0  4311.3    .035       0
#XS Ineff= 2 , 0
            1950     450
Permanent Ineff=
       F       F
Bank Sta=3864.3,4067
XS Rating Curve= 0 ,0
Exp/Cntr=0.5,0.3

Type RM Length L Ch R = 1 ,40767   ,525,957,707
BEGIN DESCRIPTION:
This cross section corresponds to cross section 40767 of the non-georeferenced CDC model which was the source of this model.
END DESCRIPTION:
XS GIS Cut Line= 6
2454001.208171677003293.61259097 2453989.58155457003272.17201705
2453988.809902527003270.749447722453605.335931937002563.61798796
2452694.625154917000983.939060722451634.198798097000461.40992205
#Sta/Elev= 30
    1000   448.5    1038   445.1    1097   426.7    1131   426.6    1182   433.8
    1347   434.5    1380     434    1410   425.6    1576   424.9    1820   429.7
    1877     427    2100   427.4    2283   424.4    2442   419.1    2581   421.2
    2595   419.2    3352   420.6    4062   420.2    4357   416.1    4375     408
    4385   407.1    4400   391.4    4445     392    4487   415.9    4503   420.1
    4625   420.5    4671   423.1    4704     428    4785   429.4    4836   436.7
#Mann= 6 ,-1,0
    1000     .08       0    2581     .03       0    3352     .12       0
    4357    .055       0    4503    .185       0    4625    .035       0
#XS Ineff= 2 , 0
            2350     450
Permanent Ineff=
       F       F
Bank Sta=4357,4503
XS Rating Curve= 0 ,0
Exp/Cntr=0.5,0.3

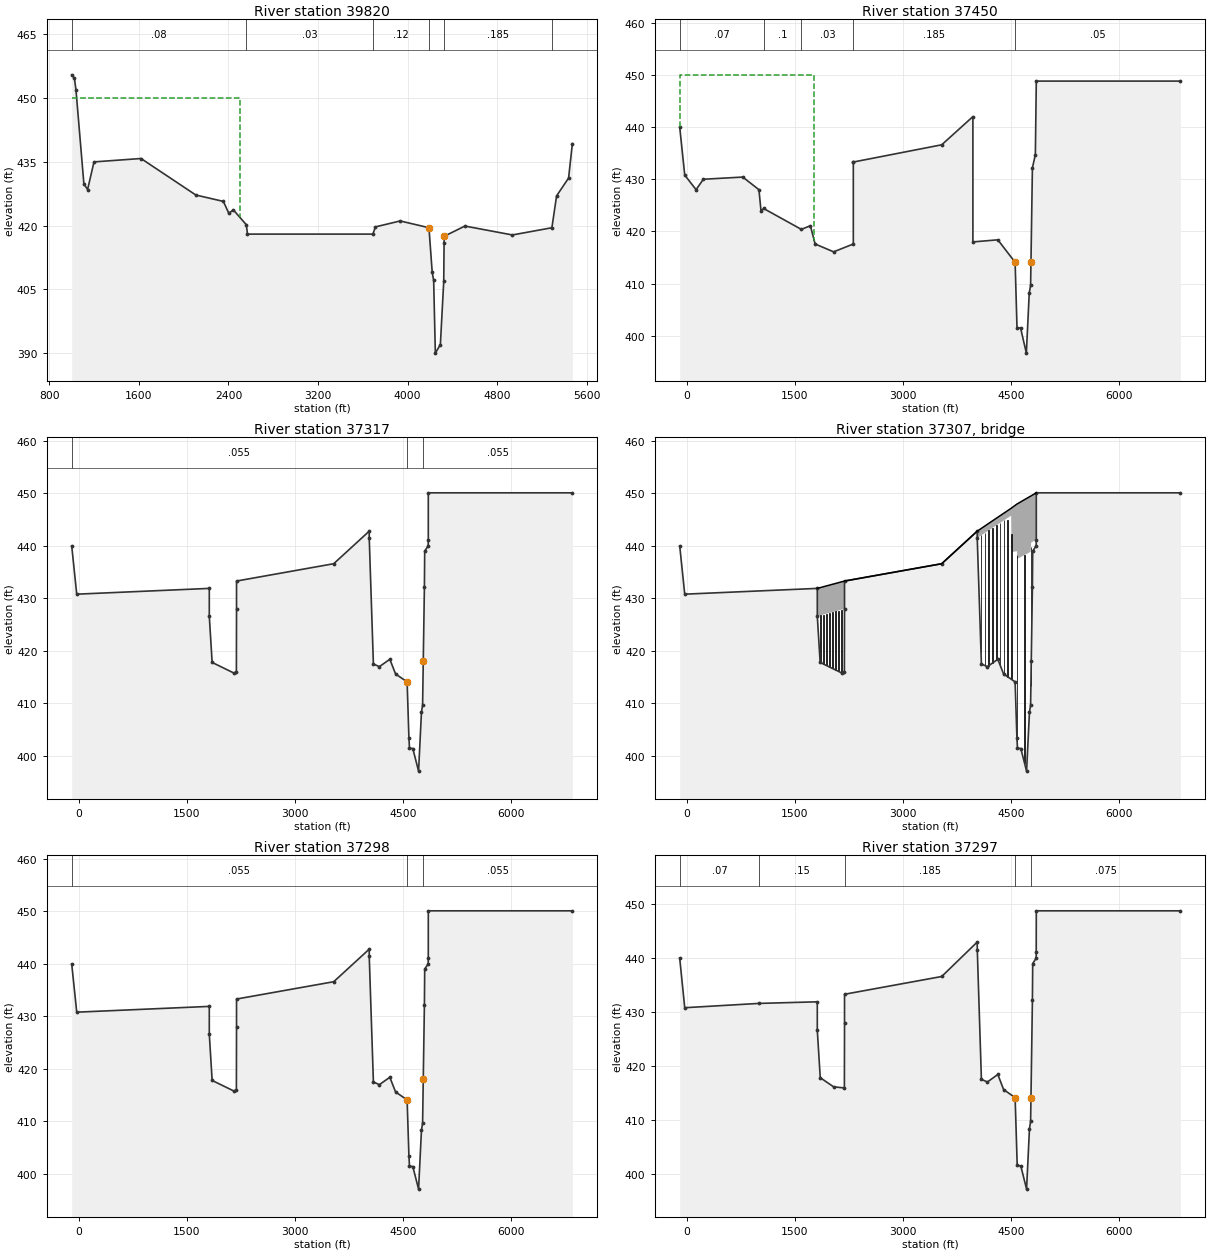
Type RM Length L Ch R = 1 ,39820   ,800,2369,1649
BEGIN DESCRIPTION:
This cross section corresponds to cross section 39820 of the non-georeferenced CDC model which was the source of this model.
END DESCRIPTION:
XS GIS Cut Line= 4
 2454311.15013717003180.989128542453072.949857597000527.49017046
2452693.306916097000118.645187632451727.137916686999922.39164314
#Sta/Elev= 30
    1000   455.5    1024   454.7    1038     452    1109   429.8    1142   428.5
    1199     435    1619   435.8    2109   427.2    2355   425.7    2403   422.9
    2444   423.7    2560   420.2    2570     418    3690     418    3713   419.7
    3934   421.1    4191   419.5    4220     409    4233   407.1    4248  389.98
    4293     392    4323   406.9    4326   415.9    4328   417.5    4512   419.9
    4936   417.8    5289   419.5    5331     427    5438   431.2    5472   439.3
#Mann= 6 ,-1,0
    1000     .08       0    2560     .03       0    3690     .12       0
    4191     .05       0    4328    .185       0    5289    .035       0
#XS Ineff= 2 , 0
            2500     450
Permanent Ineff=
       F       F
Bank Sta=4191,4328
XS Rating Curve= 0 ,0
Exp/Cntr=0.5,0.3

Type RM Length L Ch R = 1 ,37450   ,136,136,136
BEGIN DESCRIPTION:
This cross section corresponds to cross section 37450 of the non-georeferenced CDC model which was the source of this model.
END DESCRIPTION:
XS GIS Cut Line= 6
2454407.025273417003054.568121552454090.067902097001029.25524305
2453776.884145267000147.81409255   2453380.139866999592.24893072
2453144.702994916999363.637183222450936.798971556997406.74613178
#Sta/Elev= 30
    -100     440     -30   430.8  127.31     428  228.07     430  775.63  430.42
    1000     428    1029   423.9    1065   424.4    1589   420.4    1714   421.1
    1780   417.6    2037   416.1    2310   417.6    2310   433.3    2311   433.3
    3537   436.6    3970     442    3970     418    4316   418.4    4556   414.1
    4582   401.6    4632   401.5    4712   396.7    4752   408.2    4771   409.7
    4776   414.1    4796   432.2    4837   434.7    4850   448.8    6850   448.8
#Mann= 5 ,-1,0
    -100     .07       0    1065      .1       0    1589     .03       0
    2311    .185       0    4556     .05       0
#XS Ineff= 2 , 0
            1769     450
Permanent Ineff=
       F       F
Bank Sta=4556,4776
XS Rating Curve= 0 ,0
Exp/Cntr=0.5,0.3

Type RM Length L Ch R = 1 ,37317   ,19,19,19
BEGIN DESCRIPTION:
This cross section corresponds to cross section 37317 of the non-georeferenced CDC model which was the source of this model.
END DESCRIPTION:
XS GIS Cut Line= 6
2454537.668712917003028.402163392454213.076186277000974.06178388
2453890.112921427000096.861438542453534.077544246999598.14196356
2453302.281091846999366.248726552451066.22281674 6997379.8996082
#Sta/Elev= 30
    -100     440     -30   430.8    1810   431.9    1810   426.6  1849.5   417.8
  2148.5   415.8    2186   415.9    2188     428    2188   433.3    3537   436.6
    4030   442.8    4030   441.5    4088   417.5    4171     417    4316   418.4
    4396   415.6    4556   414.1    4581  403.38    4589  401.49    4635   401.4
    4715   397.1    4755   408.3    4771   409.7    4780     418    4796   432.2
    4800     439    4848     440    4850   441.2    4850   450.1    6850   450.1
#Mann= 3 ,0,0
    -100    .055       0    4556     .05       0    4780    .055       0
Bank Sta=4556,4780
XS Rating Curve= 0 ,0
Exp/Cntr=0.5,0.3

Type RM Length L Ch R = 3 ,37307   ,,,
BEGIN DESCRIPTION:
Burlington Northern Railroad
END DESCRIPTION:
Node Name=BN Railroad
Bridge Culvert--1,0,-1,-1, 0
Deck Dist Width WeirC Skew NumUp NumDn MinLoCord MaxHiCord MaxSubmerge Is_Ogee
2,16,2.6,0, 47, 47, , , 0.95, 0, ,,,
    1810  1849.5  1854.5  1891.5  1896.5  1933.5  1938.5  1975.5  1980.5  2017.5
  2022.5  2059.5  2064.5  2101.5  2106.5  2143.5  2148.5    2188    2188    3537
    4030    4030    4079    4087    4132    4140    4185    4193    4238    4246
    4291    4299    4344    4352    4397    4405    4450    4458    4501    4509
    4581    4589    4681    4689    4771    4779    4850
   431.9  432.05  432.06   432.2  432.22  432.36  432.38  432.51  432.53  432.67
  432.69  432.82  432.84  432.98     433  433.14  433.15   433.3   433.3   436.6
   442.8   442.8  443.25  443.33  443.74  443.82  444.24  444.31  444.73   444.8
  445.22  445.29  445.71  445.78   446.2  446.27  446.69  446.76  447.16  447.24
  447.96  448.02  448.76  448.82  449.47  449.53   450.1
   426.6  426.75  426.76   426.9  426.92  427.06  427.08  427.21  427.23  427.37
  427.39  427.52  427.54  427.68   427.7  427.84  427.85     428   433.3   436.6
   442.8   441.5  441.94  442.02  442.42   442.5   442.9  442.98  443.38  443.46
  443.86  443.94  444.34  444.41  444.82  444.89   445.3  445.37  445.76  438.81
  438.99  437.53  438.21  438.26  438.87  440.63   441.2
    1810  1849.5  1854.5  1891.5  1896.5  1933.5  1938.5  1975.5  1980.5  2017.5
  2022.5  2059.5  2064.5  2101.5  2106.5  2143.5  2148.5    2188    2188    3537
    4030    4030    4079    4087    4132    4140    4185    4193    4238    4246
    4291    4299    4344    4352    4397    4405    4450    4458    4501    4509
    4581    4589    4681    4689    4771    4779    4850
   431.9  432.05  432.06   432.2  432.22  432.36  432.38  432.51  432.53  432.67
  432.69  432.82  432.84  432.98     433  433.14  433.15   433.3   433.3   436.6
   442.8   442.8  443.25  443.33  443.74  443.82  444.24  444.31  444.73   444.8
  445.22  445.29  445.71  445.78   446.2  446.27  446.69  446.76  447.16  447.24
  447.96  448.02  448.76  448.82  449.47  449.53   450.1
   426.6  426.75  426.76   426.9  426.92  427.06  427.08  427.21  427.23  427.37
  427.39  427.52  427.54  427.68   427.7  427.84  427.85     428   433.3   436.6
   442.8   441.5  441.94  442.02  442.42   442.5   442.9  442.98  443.38  443.46
  443.86  443.94  444.34  444.41  444.82  444.89   445.3  445.37  445.76  438.81
  438.99  437.53  438.21  438.26  438.87  440.63   441.2
Pier Skew, UpSta & Num, DnSta & Num=  ,1852, 2 ,1852, 2 , 0 , 0 , 0 ,,
       5       5
     415     430
       5       5
     415     430
Pier Skew, UpSta & Num, DnSta & Num=  ,1894, 2 ,1894, 2 , 0 , 0 , 0 ,,
       5       5
     415     430
       5       5
     415     430
Pier Skew, UpSta & Num, DnSta & Num=  ,1936, 2 ,1936, 2 , 0 , 0 , 0 ,,
       5       5
     415     430
       5       5
     415     430
Pier Skew, UpSta & Num, DnSta & Num=  ,1978, 2 ,1978, 2 , 0 , 0 , 0 ,,
       5       5
     415     430
       5       5
     415     430
Pier Skew, UpSta & Num, DnSta & Num=  ,2020, 2 ,2020, 2 , 0 , 0 , 0 ,,
       5       5
     415     430
       5       5
     415     430
Pier Skew, UpSta & Num, DnSta & Num=  ,2062, 2 ,2062, 2 , 0 , 0 , 0 ,,
       5       5
     415     430
       5       5
     415     430
Pier Skew, UpSta & Num, DnSta & Num=  ,2104, 2 ,2104, 2 , 0 , 0 , 0 ,,
       5       5
     415     430
       5       5
     415     430
Pier Skew, UpSta & Num, DnSta & Num=  ,2146, 2 ,2146, 2 , 0 , 0 , 0 ,,
       5       5
     415     430
       5       5
     415     430
Pier Skew, UpSta & Num, DnSta & Num=  ,4083, 2 ,4083, 2 , 0 , 0 , 0 ,,
       8       8
     410     442
       8       8
     410     442
Pier Skew, UpSta & Num, DnSta & Num=  ,4136, 2 ,4136, 2 , 0 , 0 , 0 ,,
       8       8
     410     443
       8       8
     410     443
Pier Skew, UpSta & Num, DnSta & Num=  ,4189, 2 ,4189, 2 , 0 , 0 , 0 ,,
       8       8
     410     444
       8       8
     410     444
Pier Skew, UpSta & Num, DnSta & Num=  ,4242, 2 ,4242, 2 , 0 , 0 , 0 ,,
       8       8
     410     444
       8       8
     410     444
Pier Skew, UpSta & Num, DnSta & Num=  ,4295, 2 ,4295, 2 , 0 , 0 , 0 ,,
       8       8
     410     444
       8       8
     410     444
Pier Skew, UpSta & Num, DnSta & Num=  ,4348, 2 ,4348, 2 , 0 , 0 , 0 ,,
       8       8
     410     445
       8       8
     410     445
Pier Skew, UpSta & Num, DnSta & Num=  ,4401, 2 ,4401, 2 , 0 , 0 , 0 ,,
       8       8
     410     445
       8       8
     410     445
Pier Skew, UpSta & Num, DnSta & Num=  ,4454, 2 ,4454, 2 , 0 , 0 , 0 ,,
       8       8
     410     445
       8       8
     410     445
Pier Skew, UpSta & Num, DnSta & Num=  ,4505, 2 ,4505, 2 , 0 , 0 , 0 ,,
       8       8
     390     446
       8       8
     390     446
Pier Skew, UpSta & Num, DnSta & Num=  ,4585, 2 ,4585, 2 , 0 , 0 , 0 ,,
       8       8
     390     446
       8       8
     390     446
Pier Skew, UpSta & Num, DnSta & Num=  ,4685, 2 ,4685, 2 , 0 , 0 , 0 ,,
       8       8
     390     446
       8       8
     390     446
Pier Skew, UpSta & Num, DnSta & Num=  ,4775, 2 ,4775, 2 , 0 , 0 , 0 ,,
       8       8
     390     446
       8       8
     390     446
BR Coef= 1 , 0 , 0 ,1.05, 0 ,,,0.8,-1,0.5,1,
WSPro=,,,, 1 ,,,, 0 ,,,, 0 ,,,,-1 ,-1 ,-1 , 0 , 0 , 0 , 0 , 0
BC Design=,, 0 ,, 0 ,,,,,,
BC HTab HWMax=450.1
BC Use User HTab Curves=0
BC User HTab FreeFlow(D)= 0

Type RM Length L Ch R = 1 ,37298   ,1,1,1
BEGIN DESCRIPTION:
This cross section corresponds to cross section 37298 of the non-georeferenced CDC model which was the source of this model.
END DESCRIPTION:
XS GIS Cut Line= 6
 2454555.66933317003020.430066472454230.642752177000966.15300705
2453906.289070167000089.583565972453549.882630776999591.12885422
2453317.539919596999359.582073212451081.265758266997373.63392849
#Sta/Elev= 30
    -100     440     -30   430.8    1810   431.9    1810   426.6  1849.5   417.8
  2148.5   415.8    2186   415.9    2188     428    2188   433.3    3537   436.6
    4030   442.8    4030   441.5    4088   417.5    4171     417    4316   418.4
    4396   415.6    4556   414.1    4581  403.38    4589  401.49    4635   401.4
    4715   397.1    4755   408.3    4771   409.7    4780     418    4796   432.2
    4800     439    4848     440    4850   441.2    4850   450.1    6850   450.1
#Mann= 3 ,0,0
    -100    .055       0    4556     .05       0    4780    .055       0
Bank Sta=4556,4780
XS Rating Curve= 0 ,0
Exp/Cntr=0.5,0.3

Type RM Length L Ch R = 1 ,37297   ,98,125,98
BEGIN DESCRIPTION:
This cross section corresponds to cross section 37297 of the non-georeferenced CDC model which was the source of this model.
END DESCRIPTION:
XS GIS Cut Line= 6
2454556.616837777003020.010447892454231.56729099 7000965.7366693
2453907.140446427000089.20036463  2453550.7143226999590.75943239
2453318.336834016999359.225118552451082.057928556997373.30469787
#Sta/Elev= 30
    -100     440     -30   430.8    1000   431.6    1810   431.9    1810   426.6
    1851   417.8    2037   416.1    2186   415.9    2188     428    2188   433.3
    3537   436.6    4030     443    4031   441.5    4088   417.5    4171     417
    4316   418.4    4396   415.6    4556   414.1    4585   401.5    4635   401.4
    4715   397.1    4755   408.3    4771   409.7    4776   414.1    4796   432.2
    4800     439    4848     440    4849   441.2    4850   448.8    6850   448.8
#Mann= 5 ,-1,0
    -100     .07       0    1000     .15       0    2188    .185       0
    4556     .05       0    4776    .075       0
Bank Sta=4556,4776
XS Rating Curve= 0 ,0
Exp/Cntr=0.3,0.1

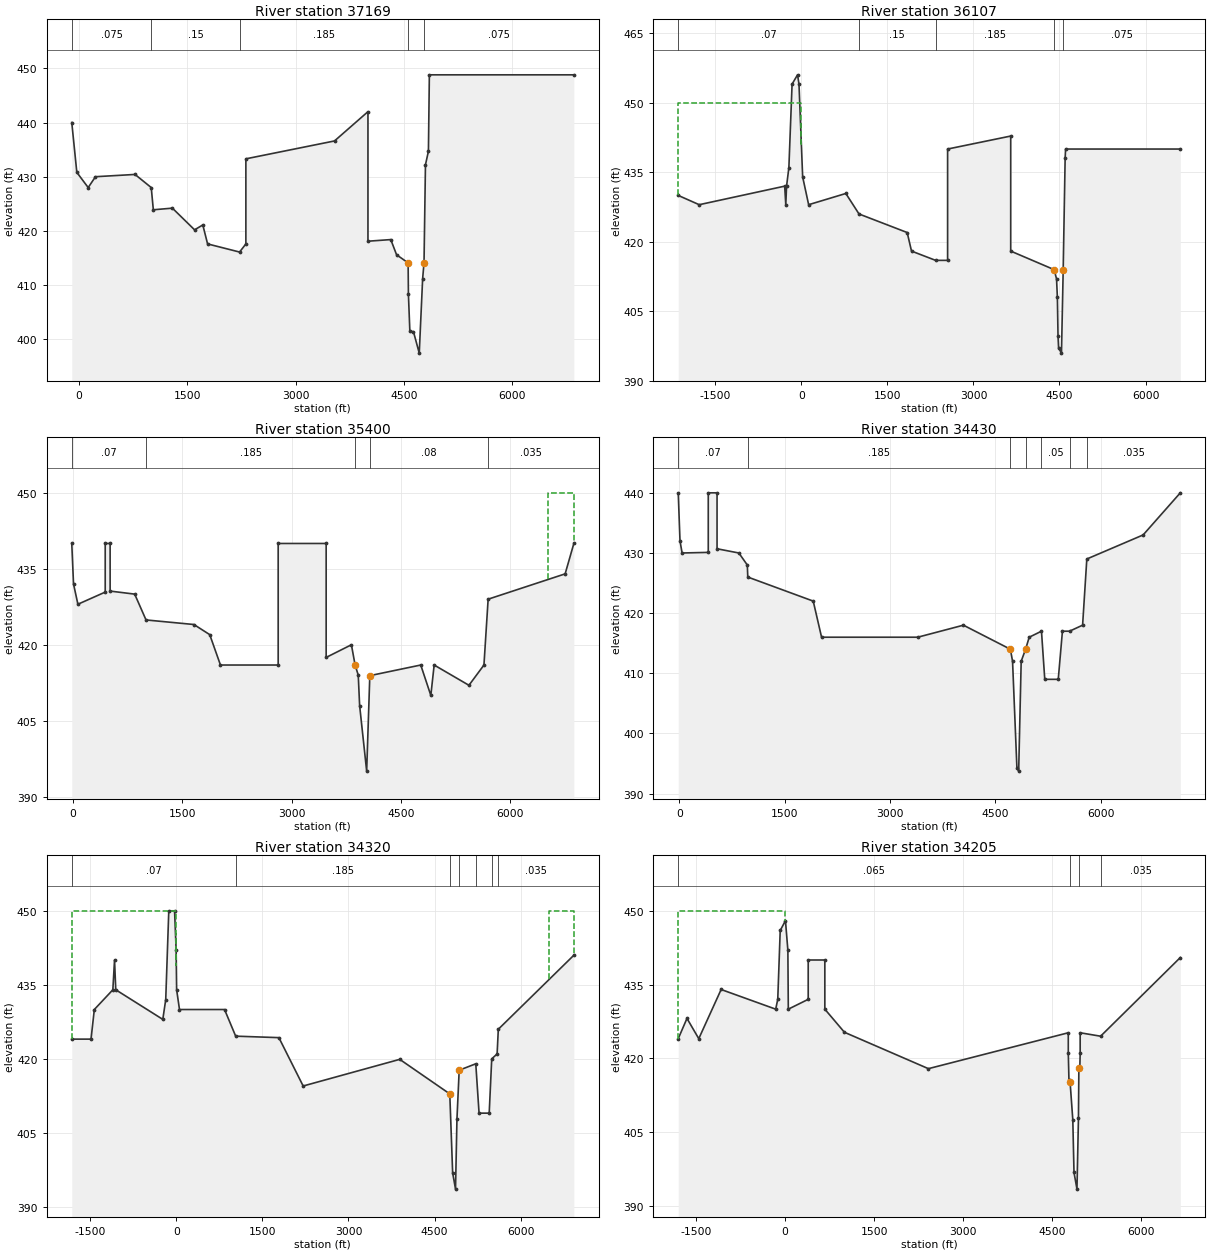
Type RM Length L Ch R = 1 ,37169   ,600,1062,1150
BEGIN DESCRIPTION:
This cross section corresponds to cross section 37169 of the non-georeferenced CDC model which was the source of this model.
END DESCRIPTION:
XS GIS Cut Line= 6
2454672.473233347002931.723879052454367.111967417000980.50894947
2454053.927882497000099.068127052453657.183925336999543.50296521
2453421.747060276999314.891217722451157.647179466997308.33043539
#Sta/Elev= 30
    -100     440     -30   430.8  127.31     428  228.07     430  775.63  430.42
    1000     428    1029   423.9    1293   424.2    1600   420.2    1714   421.1
    1780   417.6    2223   416.1    2310   417.6    2310   433.3    3537   436.6
    4000     442    4000   418.1    4316   418.4    4396   415.6    4556   414.1
    4560   408.3    4580   401.5    4630   401.4    4710  397.45    4757   411.2
    4776   414.1    4796   432.2    4837   434.7    4850   448.8    6850   448.8
#Mann= 5 ,-1,0
    -100    .075       0    1000     .15       0    2223    .185       0
    4556     .05       0    4776    .075       0
Bank Sta=4556,4776
XS Rating Curve= 0 ,0
Exp/Cntr=0.3,0.1

Type RM Length L Ch R = 1 ,36107   ,438,703,547
BEGIN DESCRIPTION:
This cross section corresponds to cross section 36107 of the non-georeferenced CDC model which was the source of this model.
END DESCRIPTION:
XS GIS Cut Line= 6
2455052.236909517005056.261624722454752.938951677002941.94269063
2454491.786914917000670.694936542453845.071016766998646.27214813
2453850.06280467 6998440.25549982453898.508629526996440.84233538
#Sta/Elev= 30
 -2146.1     430 -1780.4     428  -290.3     432  -271.1     428  -257.6     432
  -217.2     436  -161.4     454   -66.1     456     -41     454   22.95     434
  127.31     428  775.63  430.42  1005.5     426  1845.3     422  1920.6     418
  2340.7     416    2550     416    2550     440    3650   442.8    3650     418
  4406.9     414  4449.1     412  4463.7     408    4475   399.6    4485   397.1
    4535     396  4565.1     414    4599     438  4606.8     440  6606.8     440
#Mann= 5 ,-1,0
 -2146.1     .07       0  1005.5     .15       0  2340.7    .185       0
  4406.9     .05       0  4565.1    .075       0
#XS Ineff= 2 , 0
        1.030029     450
Permanent Ineff=
       F       F
Bank Sta=4406.9,4565.1
XS Rating Curve= 0 ,0
Exp/Cntr=0.3,0.1

Type RM Length L Ch R = 1 ,35400   ,314,1050,195
BEGIN DESCRIPTION:
This cross section corresponds to cross section 35400 of the non-georeferenced CDC model which was the source of this model.
STA 354+00  New X-section
---------------------------------------------------------------------
CDC IRV082109-1 NORTHWEST LEVEE SEEPAGE CONTROL
CROSS-SECTION 13293 - 55400
UPSTREAM END
---------------------------------------------------------------------
END DESCRIPTION:
XS GIS Cut Line= 6
 2454794.62948517002909.716705222454637.936885097001911.17605138
2454633.30369225 7001849.90616082454572.889114927000012.10799913
2454201.420369686997699.429553632454236.189985196996065.33177197
#Sta/Elev= 30
   -18.7     440     5.4     432    65.4     428   440.1   430.4   440.1     440
   507.6     440   507.6   430.6   844.5     430    1000   424.9  1656.8     424
    1874     422  2021.1     416    2813     416    2813     440  3471.3     440
  3471.3   417.5  3817.6     420  3868.4     416  3911.5     414  3930.4     408
    4027  395.05  4070.2   413.9  4768.9     416  4907.2     410  4952.9     416
  5430.1     412    5636     416 5693.44     429 6749.83     434 6869.23     440
#Mann= 5 ,-1,0
   -18.7     .07       0    1000    .185       0  3868.4     .05       0
  4070.2     .08       0 5693.44    .035       0
#XS Ineff= 2 , 0
                            6520             450
Permanent Ineff=
       F       F
Bank Sta=3868.4,4070.2
XS Rating Curve= 0 ,0
Exp/Cntr=0.3,0.1

Type RM Length L Ch R = 1 ,34430   ,15,34,43
BEGIN DESCRIPTION:
This cross section corresponds to cross section 34430 of the non-georeferenced CDC model which was the source of this model.
STA 344+30  New X-section
END DESCRIPTION:
XS GIS Cut Line= 6
    2454898.32587002890.412609962454651.234102587001975.48563404
2454640.112733757001901.505467042454684.47156891 6999091.0475053
2454690.305874826996401.708067722454698.22777501 6995778.5521618
#Sta/Elev= 30
   -14.1     440    11.1     432    40.9     430   413.3   430.1   413.3     440
   538.3     440   538.3   430.7   848.6     430     969     428   975.7     426
  1907.1     422  2025.8     416  3394.6     416  4044.7     418  4713.2     414
 4743.91     412    4806  394.24    4831  393.74  4866.7     412  4929.3     414
    4981     416 5155.58     417 5202.36     409 5394.21     409 5453.74     417
  5554.8     417  5740.8     418  5800.8     429 6602.11     433 7131.39     440
#Mann= 7 ,-1,0
   -14.1     .07       0   975.7    .185       0  4713.2     .05       0
  4929.3     .08       0 5155.58     .05       0  5554.8     .08       0
  5800.8    .035       0
Bank Sta=4713.2,4929.3
XS Rating Curve= 0 ,0
Exp/Cntr=0.3,0.1

Type RM Length L Ch R = 1 ,34320   ,120,120,120
BEGIN DESCRIPTION:
This cross section corresponds to cross section 34320 of the non-georeferenced CDC model which was the source of this model.
END DESCRIPTION:
XS GIS Cut Line= 4
2455424.882489687004631.867788462454908.776566517002867.75747155
2454645.024141257001914.231163382454750.396633926995993.25678489
#Sta/Elev= 30
 -1822.3     424 -1486.8     424 -1429.2     430 -1106.3     434 -1077.2     440
 -1055.5     434    -236     428  -184.9     432  -131.6     450   -30.8     450
    -3.4     442       5     434      55     430     840     430    1034   424.6
    1787   424.3    2210   414.5    3893   419.9    4765   412.9    4815   396.9
    4865   393.6    4890   407.8    4929   417.7    5218     419 5275.34     409
    5452     409    5496     420    5590     421  5610.7     426    6927     441
#Mann= 7 ,-1,0
 -1822.3     .07       0    1034    .185       0    4765     .05       0
    4929     .08       0    5218     .05       0    5496     .08       0
  5610.7    .035       0
#XS Ineff= 2 , 0
               0     450    6500             450
Permanent Ineff=
       F       F
Bank Sta=4765,4929
XS Rating Curve= 0 ,0
Exp/Cntr=0.3,0.1

Type RM Length L Ch R = 1 ,34205   ,25,25,25
BEGIN DESCRIPTION:
This cross section corresponds to cross section 34205 of the non-georeferenced CDC model which was the source of this model.
END DESCRIPTION:
XS GIS Cut Line= 5
2455517.159536097004620.04596172 2455013.12117417002852.50717397
2454756.784416417001922.592695222454754.500300267001905.58682372
2454854.076872776996271.02460206
#Sta/Elev= 30
 -1798.8     424 -1651.7  428.12   -1453     424 -1076.4     434  -157.4     430
  -122.8     432   -81.4     446     6.8     448    47.5     442      55     430
     390     432     390     440     670     440     670     430    1000   425.3
    2414   417.9    4770   425.2    4770     421    4781   415.6    4800   415.2
    4846   407.5    4866   396.8    4916   393.4    4941   407.8    4948     418
    4964     418    4970     421    4970   425.2    5314   424.5  6656.4   440.5
#Mann= 4 ,-1,0
 -1798.8    .065       0    4800     .05       0    4948    .065       0
    5314    .035       0
#XS Ineff= 2 , 0
               0     450
Permanent Ineff=
       F       F
Bank Sta=4800,4948
XS Rating Curve= 0 ,0
Exp/Cntr=0.5,0.3