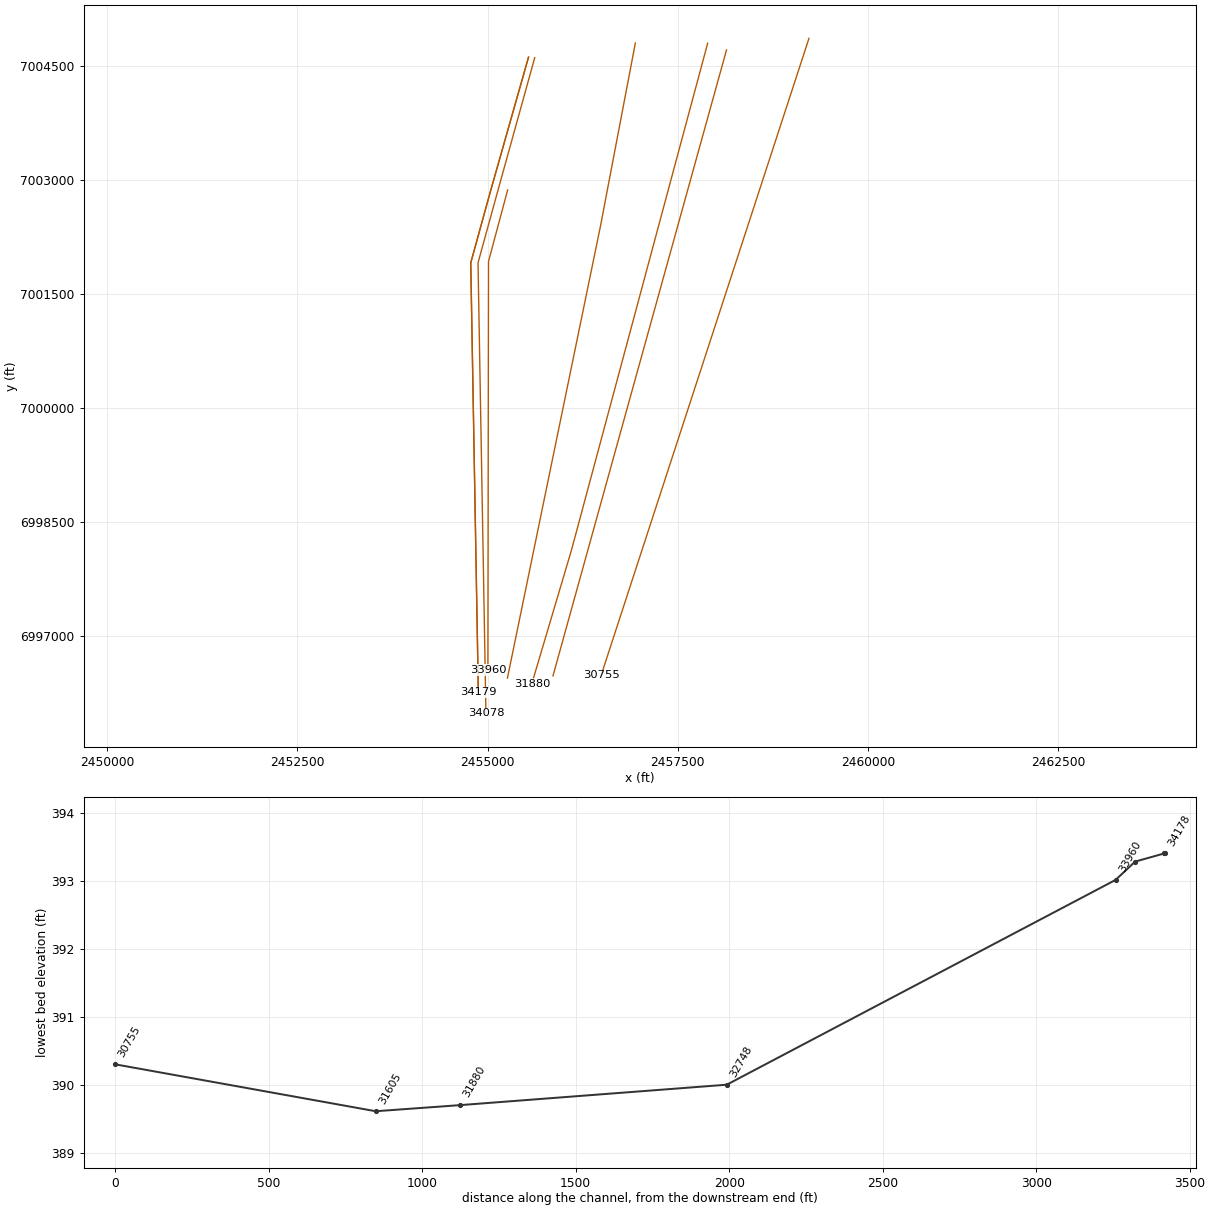
HEC-RAS study CDC_Consolidated_Model.prj: Upper Trinity CDC Consolidated Model

--- CDC_Consolidated_Model.g13 (geometry) --- (continued)

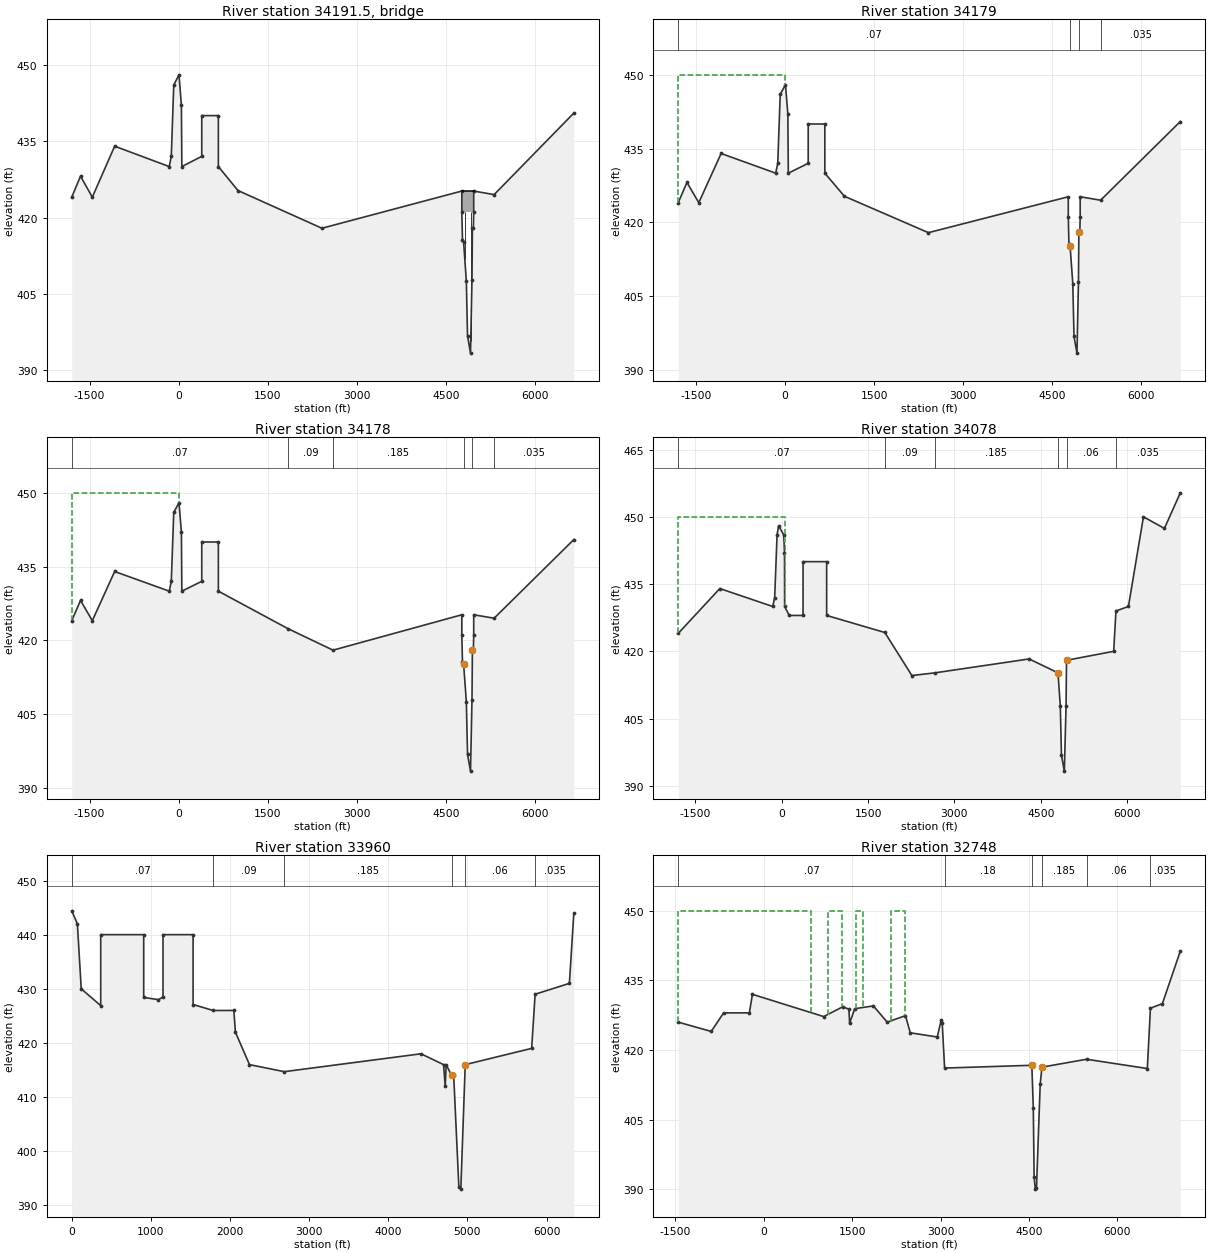
Type RM Length L Ch R = 3 ,34191.5 ,,,
BEGIN DESCRIPTION:
Wildwood Drive
END DESCRIPTION:
Node Name=Wildwood Drive
Bridge Culvert--1,0,-1,-1, 0
Deck Dist Width WeirC Skew NumUp NumDn MinLoCord MaxHiCord MaxSubmerge Is_Ogee
2,22,2.6,0, 6, 6, , , 0.95, 0, ,,,
    4770  4818.5  4821.5  4918.5  4921.5    4970
   425.2   425.2   425.2   425.2   425.2   425.2
     421     421     421     421     421     421
    4770  4818.5  4821.5  4918.5  4921.5    4970
   425.2   425.2   425.2   425.2   425.2   425.2
     421     421     421     421     421     421
Pier Skew, UpSta & Num, DnSta & Num=  ,4820, 2 ,4820, 2 , 0 , 0 , 0 ,,
       3       3
     390     424
       3       3
     390     424
Pier Skew, UpSta & Num, DnSta & Num=  ,4920, 2 ,4920, 2 , 0 , 0 , 0 ,,
       3       3
     390     424
       3       3
     390     424
BR Coef= 1 , 0 , 0 ,1.05, 0 ,,,0.8,-1,0.5,1,
WSPro=,,,, 1 ,,,, 0 ,,,, 0 ,,,,-1 ,-1 ,-1 , 0 , 0 , 0 , 0 , 0
BC Design=,, 0 ,, 0 ,,,,,,
BC HTab HWMax=446
BC Use User HTab Curves=0
BC User HTab FreeFlow(D)= 0

Type RM Length L Ch R = 1 ,34179   ,1,1,1
BEGIN DESCRIPTION:
This cross section corresponds to cross section 34179 of the non-georeferenced CDC model which was the source of this model.
END DESCRIPTION:
XS GIS Cut Line= 5
2455538.244467687004618.132579712455037.095535587002850.36938296
2454781.011074017001920.719011312454779.250906917001903.66359922
2454878.685747416996268.18996204
#Sta/Elev= 30
 -1798.8     424 -1651.7  428.12   -1453     424 -1076.4     434  -157.4     430
  -122.8     432   -81.4     446     6.8     448    47.5     442      55     430
     390     432     390     440     670     440     670     430    1000   425.3
    2414   417.9    4770   425.2    4770     421    4781   415.6    4800   415.2
    4846   407.5    4866   396.8    4916   393.4    4941   407.8    4948     418
    4964     418    4970     421    4970   425.2    5314   424.5  6656.4   440.5
#Mann= 4 ,-1,0
 -1798.8     .07       0    4800     .05       0    4948    .065       0
    5314    .035       0
#XS Ineff= 2 , 0
               0     450
Permanent Ineff=
       F       F
Bank Sta=4800,4948
XS Rating Curve= 0 ,0
Exp/Cntr=0.5,0.3

Type RM Length L Ch R = 1 ,34178   ,95,95,95
BEGIN DESCRIPTION:
This cross section corresponds to cross section 34178 of the non-georeferenced CDC model which was the source of this model.
END DESCRIPTION:
XS GIS Cut Line= 5
 2455539.05516167004618.059089052455038.017777837002850.28736213
2454781.943158757001920.648473382454780.203004757001903.58978046
2454879.631939776996268.08169454
#Sta/Elev= 30
 -1798.8     424 -1651.7  428.12   -1453     424 -1076.4     434  -157.4     430
  -122.8     432   -81.4     446     6.8     448    47.5     442      55     430
     390     432     390     440     670     440     670     430    1838   422.4
    2601     418    4770   425.2    4770     421    4781   415.6    4800   415.2
    4846   407.5    4866   396.8    4916   393.4    4941   407.8    4948     418
    4964     418    4970     421    4970   425.2    5314   424.5  6656.4   440.5
#Mann= 6 ,-1,0
 -1798.8     .07       0    1838     .09       0    2601    .185       0
    4800     .05       0    4948    .075       0    5314    .035       0
#XS Ineff= 2 , 0
               0     450
Permanent Ineff=
       F       F
Bank Sta=4800,4948
XS Rating Curve= 0 ,0
Exp/Cntr=0.3,0.1

Type RM Length L Ch R = 1 ,34078   ,64,64,64
BEGIN DESCRIPTION:
This cross section corresponds to cross section 34078 of the non-georeferenced CDC model which was the source of this model.
Right Overbank updated with 2007 levee topo.
END DESCRIPTION:
XS GIS Cut Line= 4
2455620.150471847004610.700507972455127.401129257002831.86515488
2454875.096843847001913.347963052454978.987712176995988.55961581
#Sta/Elev= 30
 -1798.8     424 -1076.4     434  -157.4     430  -122.8     432   -81.4     446
   -54.9     448    34.2     446    47.5     442      50     430     130     428
     370     428     370     440     780     440     780     428    1791   424.2
    2261   414.6    2661   415.2    4298   418.3    4800   415.2    4840   407.8
    4860   396.8    4910  393.28    4940   407.8    4948     418  5767.6     420
    5807     429  6023.7     430 6284.87     450 6649.01  447.41 6925.26  455.35
#Mann= 6 ,-1,0
 -1798.8     .07       0    1791     .09       0    2661    .185       0
    4800     .05       0    4948     .06       0    5807    .035       0
#XS Ineff= 2 , 0
              50     450
Permanent Ineff=
       F       F
Bank Sta=4800,4948
XS Rating Curve= 0 ,0
Exp/Cntr=0.3,0.1

Type RM Length L Ch R = 1 ,33960   ,752,1266,533
BEGIN DESCRIPTION:
This cross section corresponds to cross section 33960 of the non-georeferenced CDC model which was the source of this model.
STA 339+60  New X-section
END DESCRIPTION:
XS GIS Cut Line= 3
2455264.355907837002871.339485382455012.740597437001931.38795322
2455004.753408676996558.94036479
#Sta/Elev= 30
       0   444.4    70.9     442   119.6     430   365.8   426.9   365.8     440
   909.1     440   909.1   428.4  1096.1     428  1153.1   428.5  1153.1     440
  1533.4     440  1533.4   427.1    1786     426  2048.5     426    2068     422
  2246.1     416  2686.1   414.7  4413.4     418  4699.3     416  4719.6     412
  4732.3     416  4800.2     414  4827.1     414    4892  393.47    4917  393.01
  4972.7     416 5812.31     419 5856.16     429  6289.1     431  6345.5     444
#Mann= 6 ,-1,0
       0     .07       0    1786     .09       0  2686.1    .185       0
  4800.2     .05       0  4972.7     .06       0 5856.16    .035       0
Bank Sta=4800.2,4972.7
XS Rating Curve= 0 ,0
Exp/Cntr=0.3,0.1

Type RM Length L Ch R = 1 ,32748   ,620,868,430
BEGIN DESCRIPTION:
This cross section corresponds to cross section 32748 of the non-georeferenced CDC model which was the source of this model.
Right Overbank updated with 2007 levee topo.
END DESCRIPTION:
XS GIS Cut Line= 3
2456942.421121277004805.130893382456482.853142777002390.61210038
2455261.452370356996452.72502606
#Sta/Elev= 30
 -1453.4     426  -893.5     424 -683.27     428  -246.2     428  -194.6     432
    1015   427.2    1337   429.3    1443   428.8    1455   425.8    1542   428.9
    1858   429.5    2093     426    2403   427.4    2484   423.7    2942   422.8
    3010   426.5    3026   425.9    3067   416.1    4547   416.7    4572   407.5
    4586   392.6    4606     390    4626   390.2    4689   412.6    4719   416.3
    5476     418    6507     416  6559.7     429  6762.7     430 7066.67  441.31
#Mann= 6 ,-1,0
 -1453.4     .07       0    3067     .18       0    4547     .05       0
    4719    .185       0    5476     .06       0  6559.7    .035       0
#XS Ineff= 4 ,-1
 -1453.4799.9999     450    1080    1320     450    1560    1680     450
    2150    2400     450
Permanent Ineff=
       F       F       F       F
Bank Sta=4547,4719
XS Rating Curve= 0 ,0
Exp/Cntr=0.3,0.1

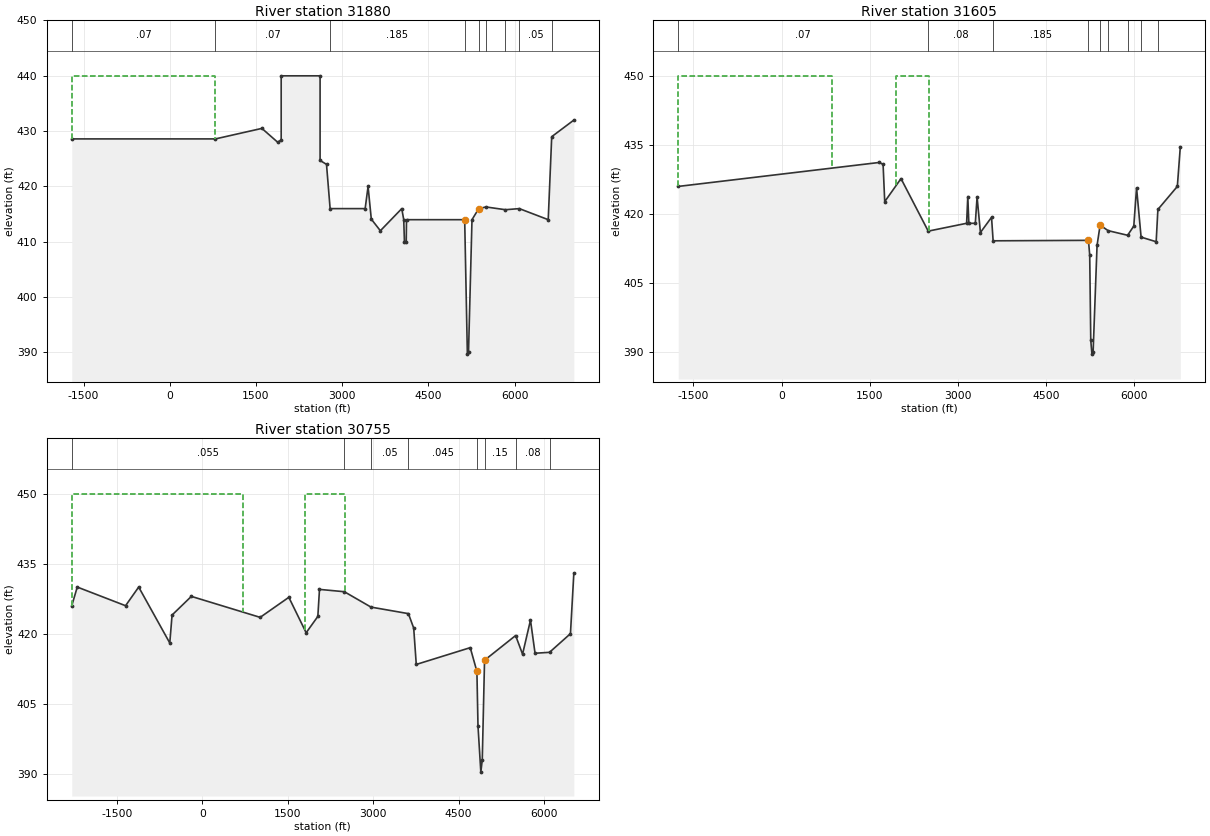
Type RM Length L Ch R = 1 ,31880   ,275,275,275
BEGIN DESCRIPTION:
This cross section corresponds to cross section 31880 of the non-georeferenced CDC model which was the source of this model.
STA 318+80  New X-section
END DESCRIPTION:
XS GIS Cut Line= 4
2457892.258667017004800.988710142457244.051751587002386.48514013
2456102.621947836998134.777436212455581.752910856996378.02766888
#Sta/Elev= 30
 -1704.2   428.6   795.8   428.6  1603.4   430.5  1877.7     428  1938.9   428.4
  1938.9     440  2615.7     440  2615.7   424.7  2727.4     424  2790.4     416
  3399.8     416  3450.5     420  3506.7   414.1  3664.4     412  4036.6     416
    4071     414  4083.3     410  4114.3     410  4119.1     414  5131.3     414
    5178   389.7    5198   390.1  5258.5     414  5375.5     416    5502   416.3
  5840.1   415.8 6081.62     416 6584.64     414 6645.38     429  7030.4     432
#Mann= 9 ,-1,0
 -1704.2     .07       0   795.8     .07       0  2790.4    .185       0
  5131.3     .05       0  5375.5    .185       0    5502     .06       0
  5840.1      .1       0 6081.62     .05       0 6645.38    .035       0
#XS Ineff= 2 , 0
           795.8     440
Permanent Ineff=
       F       F
Bank Sta=5131.3,5375.5
XS Rating Curve= 0 ,0
Exp/Cntr=0.3,0.1

Type RM Length L Ch R = 1 ,31605   ,739,849,649
BEGIN DESCRIPTION:
This cross section corresponds to cross section 31605 of the non-georeferenced CDC model which was the source of this model.
Right Overbank updated with 2007 levee topo.
---------------------------------------------------------------------
CDC Irving 050301-1 University of Dallas
Cross-section 31605 - 35400
Located in ROB.
---------------------------------------------------------------------
Irving 012607-1 Widening of SH114
---------------------------------------------------------------------
END DESCRIPTION:
XS GIS Cut Line= 2
 2458140.08736117004712.652075722455859.869480586996481.62555879
#Sta/Elev= 30
 -1758.7     426    1661   431.2    1726   430.8    1754   422.7    2031   427.7
    2494   416.3    3147     418    3167   423.8    3185     418    3295     418
    3325   423.7    3382     416    3571   419.3    3598   414.2    5220   414.3
    5241   411.1    5259   392.6    5279  389.61    5299   390.1    5366   413.2
    5418   417.6    5555   416.4    5886   415.4    5991   417.4    6038   425.7
 6115.18     415  6371.6     414  6400.9     421 6731.81     426 6782.33   434.6
#Mann= 9 ,-1,0
 -1758.7     .07       0    2494     .08       0    3598    .185       0
    5220     .05       0    5418     .13       0    5555     .06       0
    5886     .13       0 6115.18     .05       06400.899     .13       0
#XS Ineff= 2 ,-1
 -1758.7     850     450    1950    2500     450
Permanent Ineff=
       F       F
Bank Sta=5220,5418
XS Rating Curve= 0 ,0
Exp/Cntr=0.3,0.1

Type RM Length L Ch R = 1 ,30755   ,1091,1217,901
BEGIN DESCRIPTION:
This cross section corresponds to cross section 30755 of the non-georeferenced CDC model which was the source of this model.
Right Overbank updated with 2007 levee topo
END DESCRIPTION:
XS GIS Cut Line= 2
2459223.183948167004865.41456546 2456492.74616766996490.03006954
#Sta/Elev= 30
 -2288.4     426 -2191.9     430 -1344.5     426 -1114.3     430  -568.7     418
  -528.6     424  -190.3     428    1017   423.5    1520   427.8    1824   420.2
    2029   423.7    2058   429.5    2494     429    2962   425.7    3618   424.3
    3711   421.2    3756   413.4    4703     417    4820   411.9    4839   400.2
    4889   390.3    4914   392.9    4954   414.3    5499   419.6    5621   415.6
    5760   422.9    5840   415.8    6094     416 6461.37     420 6520.82     433
#Mann= 8 ,-1,0
 -2288.4    .055       0    2494     .06       0    2962     .05       0
    3618    .045       0    4820     .05       0    4954     .15       0
    5499     .08       0    6094     .12       0
#XS Ineff= 2 ,-1
 -2288.4     720     450    1800    2500     450
Permanent Ineff=
       F       F
Bank Sta=4820,4954
XS Rating Curve= 0 ,0
Exp/Cntr=0.3,0.1