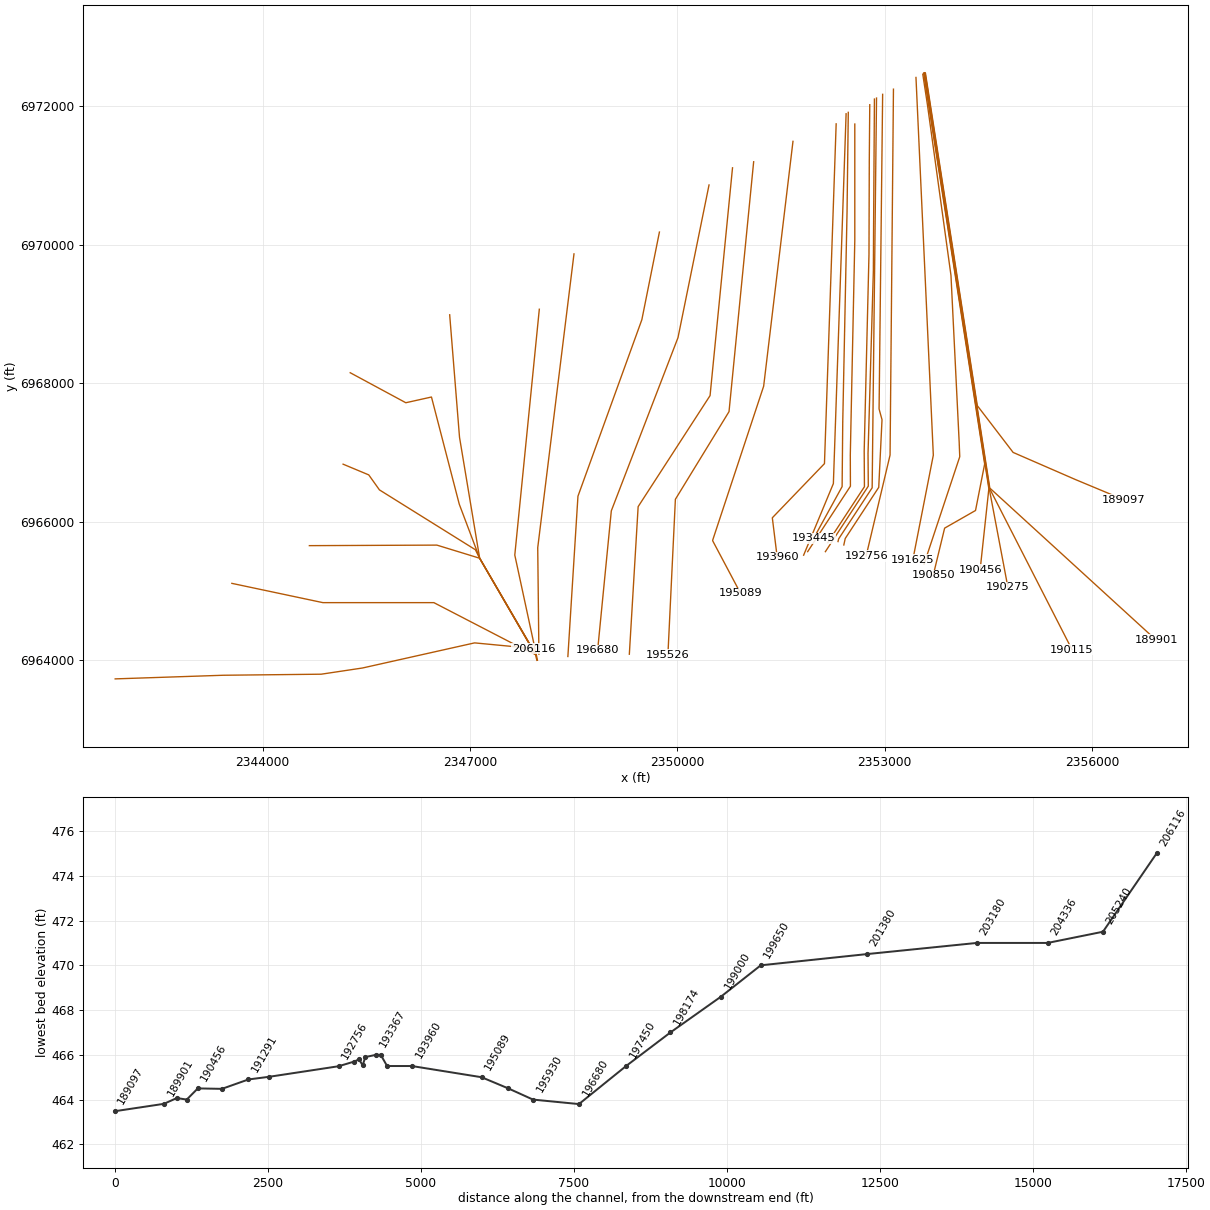
HEC-RAS study CDC_Consolidated_Model.prj: Upper Trinity CDC Consolidated Model

--- CDC_Consolidated_Model.g13 (geometry) --- (continued)

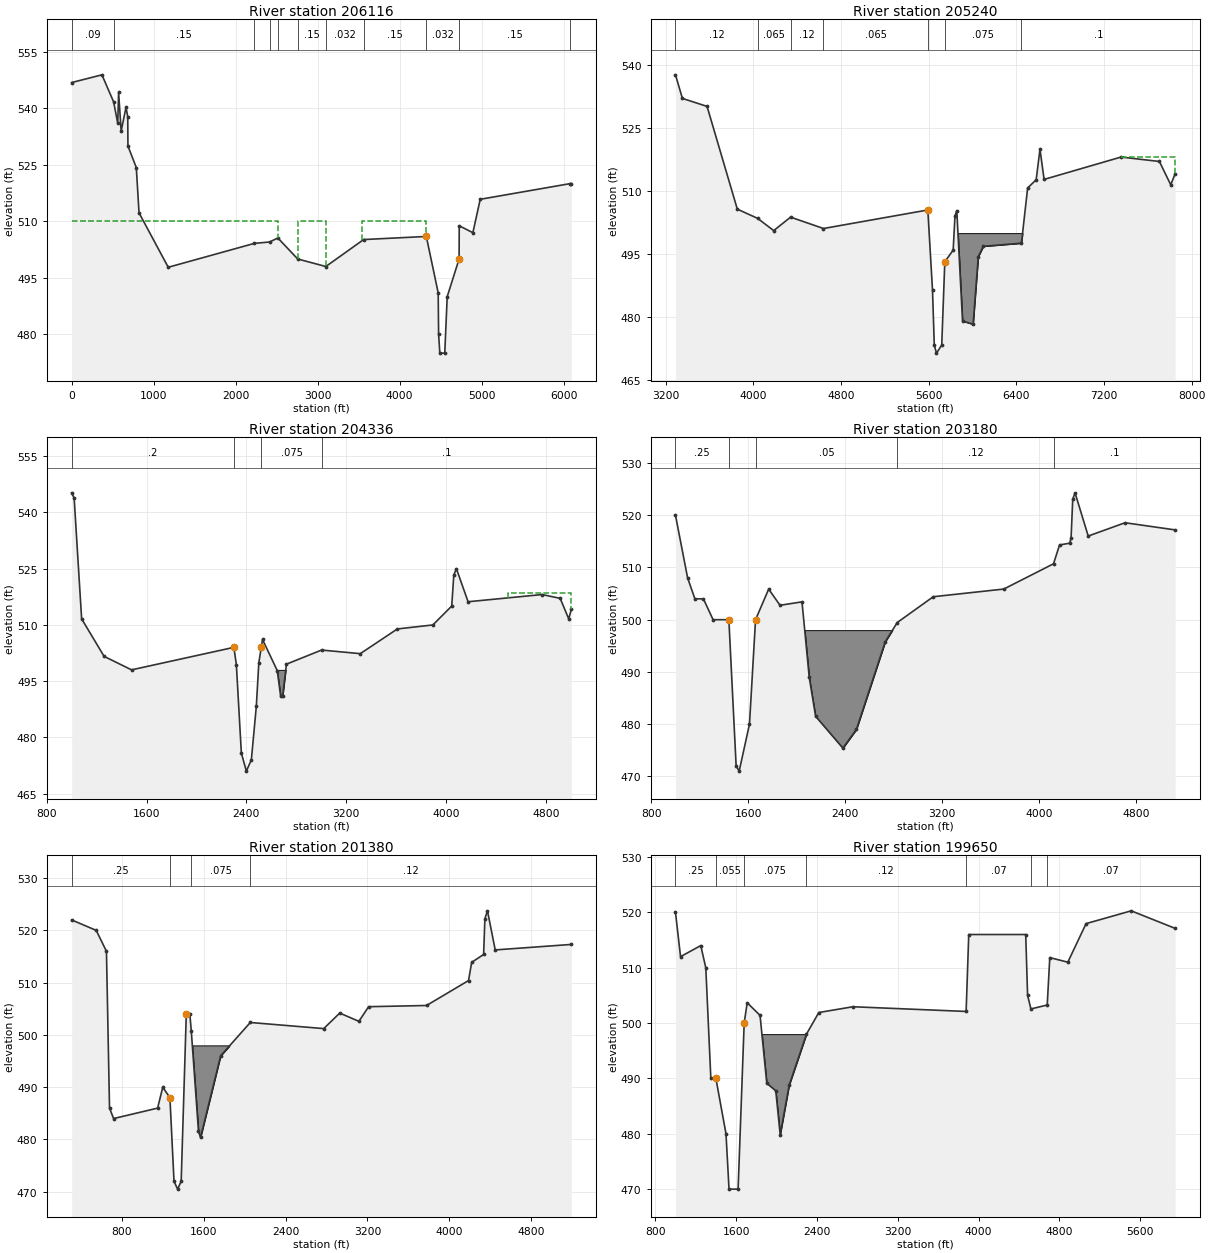
Type RM Length L Ch R = 1 ,206116  ,780,876,358
BEGIN DESCRIPTION:
Downstream bounding cross-section East 1st Street.
206116
---------------------------------------------------------------------
CDC East 1st Street FW 040113-01
---------------------------------------------------------------------
END DESCRIPTION:
XS GIS Cut Line= 6
  2341865.0194766963733.20492262 2343429.50436816963785.60684001
2344846.53599986 6963800.78917042345444.975670556963890.46353647
2347066.944641866964252.92478897 2347920.67087966964171.72651552
#Sta/Elev= 30
       0  546.85  369.23   548.9  512.04  541.71  562.18  536.03  572.53  544.23
  603.81  533.98  663.08  540.28  684.12  537.77  686.41     530  788.51  524.26
  821.63  512.25  1177.8   497.8 2227.97  504.14 2413.28  504.51    2515  505.57
 2756.74     500  3099.7     498 3560.99  505.16    4325  505.98    4470     491
    4475     480    4490     475    4550     475    4580     490    4725     500
 4726.55  508.82 4892.94  506.98 4982.56  515.85 6076.14     520 6093.63     520
#Mann= 11 ,-1,0
       0     .09       0  512.04     .15       0 2227.97     .06       0
 2413.28     .15       0    2515    .032       0 2756.74     .15       0
  3099.7    .032       0 3560.99     .15       0    4325    .032       0
 4726.55     .15       0 6076.14    .035       0
#XS Ineff= 3 ,-1
       0    2515     510    2755    3105     510    3545    4325     510
Permanent Ineff=
       F       F       F
Bank Sta=4325,4725
XS Rating Curve= 0 ,0
Exp/Cntr=0.3,0.1

Type RM Length L Ch R = 1 ,205240  ,800,904,900
BEGIN DESCRIPTION:
ROB updated with 2009 TNRIS LiDAR
END DESCRIPTION:
XS GIS Cut Line= 6
2343553.770143826965112.22718057   2344871.03011      6964833.93
   2346477.14501      6964833.93 2347670.1078499 6964217.5993343
     2347947.246     6964085.0922347968.191686126964001.06927625
#Sta/Elev= 30
    3291   537.6    3354     532    3579   530.1    3855   505.7    4041   503.5
    4187   500.6    4341   503.8    4641   501.1    5593   505.5    5636   486.4
    5652   473.4    5672   471.5    5720   473.4    5748   493.2 5824.32  495.96
 5840.89  504.11  5857.3  505.35 5909.68  479.13 6006.13  478.36  6053.3  494.42
  6099.2  496.87 6447.21  497.62 6503.68  510.73 6581.57  512.68 6616.27  519.92
 6653.93  512.76  7355.7  518.07 7705.91  517.02 7809.26  511.48 7849.67  514.11
#Mann= 7 ,-1,0
    3291     .12       0    4041    .065       0    4341     .12       0
    4641    .065       0    5593    .055       0    5748    .075       0
 6447.21      .1       0
#XS Ineff= 3 ,-1
    3291    5593   505.5    5748 7358.97   493.2 7358.97 7849.67  518.05
Permanent Ineff=
       F       F       F
#Block Obstruct= 1 ,-1
 5861.35 6480.54     500
Bank Sta=5593,5748
XS Rating Curve= 0 ,0
Exp/Cntr=0.3,0.1

Type RM Length L Ch R = 1 ,204336  ,1000,1156,200
BEGIN DESCRIPTION:
ROB updated with Halff Survey & 2009 TNRIS LiDAR
END DESCRIPTION:
XS GIS Cut Line= 6
     2344675.495     6965656.765     2344766.751     6965657.144
     2346520.754     6965664.422     2347139.385     6965475.194
 2347946.74364766964085.956933832347946.994879386964085.52463464
#Sta/Elev= 30
    1000   545.2    1020   543.8    1080   511.6    1260   501.6    1480     498
    2300     504    2320   499.4    2360   475.8    2400     471    2440     474
    2480   488.3    2500   499.9    2520   504.1 2529.47  506.11 2647.55  497.81
  2674.9     491 2690.71     491 2721.35  499.52 3002.93  503.28 3313.06  502.32
 3610.27  508.91 3894.45  509.97 4045.89  515.01 4062.53  523.31 4083.48  524.97
 4176.83  516.16 4770.05  518.08 4914.96  517.06 4983.21  511.61 5004.37   514.1
#Mann= 4 ,-1,0
    1000      .2       0    2300    .055       0    2520    .075       0
 3002.93      .1       0
#XS Ineff= 3 ,-1
    1000    2300     504    2520 4494.78   504.1 4494.78 5004.37  518.51
Permanent Ineff=
       F       F       F
#Block Obstruct= 1 ,-1
 2628.13 2742.16     498
Bank Sta=2300,2520
XS Rating Curve= 0 ,0
Exp/Cntr=0.3,0.1

Type RM Length L Ch R = 1 ,203180  ,1500,1800,200
BEGIN DESCRIPTION:
New XS from 99 topo, interpolated FL, ROB updated with Halff Survey & 2009 TNRIS LiDAR
END DESCRIPTION:
XS GIS Cut Line= 6
      2345163.49      6966832.88      2345534.79      6966678.18
      2345689.49      6966461.59      2347077.94      6965597.59
       2347139.5     6965475.2162347948.487997476964084.05120195
#Sta/Elev= 30
    1000     520    1100     508    1160     504    1230     504    1310     500
    1440     500    1500     472    1525     471    1610     480    1660     500
 1768.15  505.86 1861.89  502.76 2043.01  503.42 2102.64  488.94 2155.16   481.5
 2379.83  475.41 2491.72     479 2729.01  495.77 2828.13  499.46 3124.91   504.4
 3706.36  505.87 4116.31  510.71 4166.18  514.32 4248.99  514.65 4260.97  515.57
 4274.86  523.08 4293.79   524.3 4402.38  516.02 4705.99  518.57 5119.25   517.2
#Mann= 5 ,-1,0
    1000     .25       0    1440    .055       0    1660     .05       0
 2828.13     .12       0 4116.31      .1       0
#XS Ineff= 2 , 0
            1440     500 1768.15          505.86
Permanent Ineff=
       F       F
#Block Obstruct= 1 ,-1
    2040    2840     498
Bank Sta=1440,1660
XS Rating Curve= 0 ,0
Exp/Cntr=0.3,0.1

Type RM Length L Ch R = 1 ,201380  ,1350,1730,550
BEGIN DESCRIPTION:
New XS from 99 topo, ROB updated with Halff Survey & 2009 TNRIS LiDAR
END DESCRIPTION:
XS GIS Cut Line= 6
      2345266.63      6968153.05       2346071.1      6967719.87
       2346442.4      6967802.38      2346844.64      6966255.32
      2347139.74      6965475.342347945.940442246964095.00547947
#Sta/Elev= 30
     310     522     550     520     650     516     680     486     720     484
    1150     486    1200     490    1270     488    1310     472    1345   470.5
    1380     472    1430     504 1464.58  504.03 1478.78  500.75  1549.1  481.54
 1568.96  480.38 1765.56     496 2055.38  502.38 2772.55  501.21 2929.15  504.18
 3116.13   502.6 3211.09   505.4 3777.11  505.63 4187.32   510.4 4217.82  513.88
 4334.55  515.39 4347.11  522.23 4372.27  523.74 4447.89  516.26 5191.53  517.31
#Mann= 4 ,-1,0
     310     .25       0    1270    .055       0 1478.78    .075       0
 2055.38     .12       0
#XS Ineff= 2 , 0
            1270     488    1430             504
Permanent Ineff=
       F       F
#Block Obstruct= 1 ,-1
    1450    1850     498
Bank Sta=1270,1430
XS Rating Curve= 0 ,0
Exp/Cntr=0.3,0.1

Type RM Length L Ch R = 1 ,199650  ,750,650,300
BEGIN DESCRIPTION:
New XS from 99 topo, ROB updated with Halff Survey & 2009 TNRIS LiDAR
END DESCRIPTION:
XS GIS Cut Line= 6
2346705.969551196968989.37062247     2346709.982     6968939.532
     2346848.265     6967221.919      2347139.86      6965475.38
     2347900.201     6964175.2772347925.442715766964132.11632553
#Sta/Elev= 30
    1000     520    1050     512    1250     514    1300     510    1350     490
    1400     490    1500     480    1530     470    1620     470    1680     500
 1710.03  503.67 1837.22  501.39 1903.67  489.13 1992.62  487.77 2036.58  479.85
 2125.81   488.8 2296.56     498 2419.07  501.91  2756.9  502.95 3877.32   502.1
 3903.31     516 4467.21     516 4485.82     505 4518.55  502.55 4680.23  503.27
 4705.46  511.83 4884.01     511  5064.8  517.97  5511.5  520.28 5946.79  517.11
#Mann= 7 ,-1,0
    1000     .25       0    1400    .055       0    1680    .075       0
 2296.56     .12       0 3877.32     .07       0 4518.55     .12       0
 4680.23     .07       0
#XS Ineff= 2 , 0
            1400     490 1710.03          503.67
Permanent Ineff=
       F       F
#Block Obstruct= 1 ,-1
 1837.06 2346.15     498
Bank Sta=1400,1680
XS Rating Curve= 0 ,0
Exp/Cntr=0.3,0.1

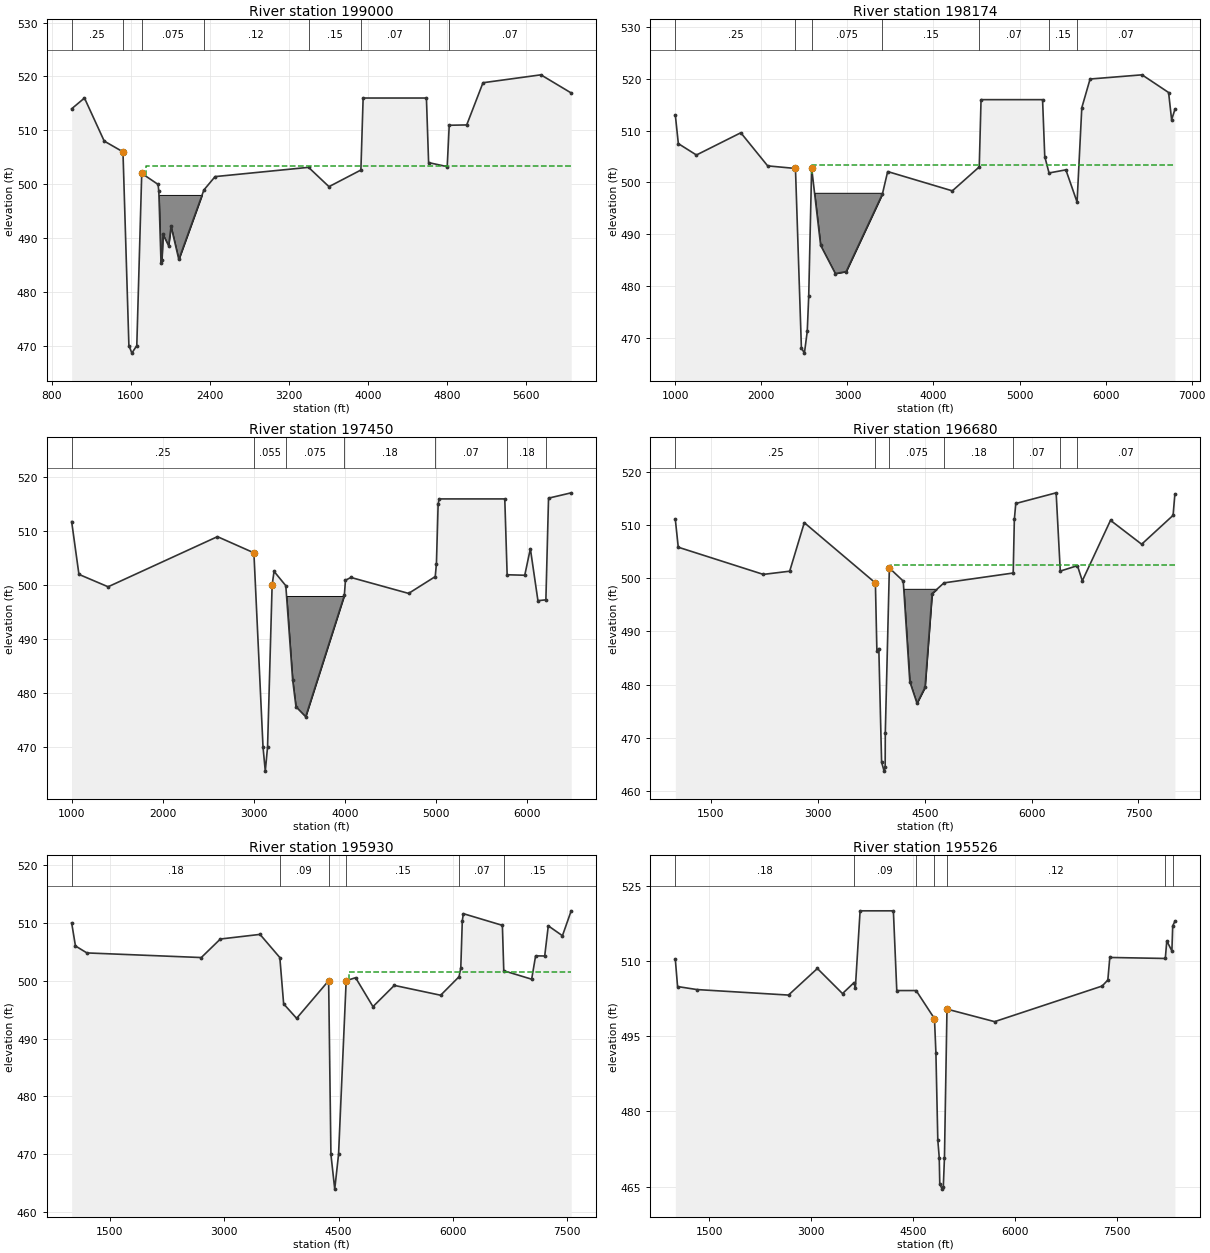
Type RM Length L Ch R = 1 ,199000  ,800,826,750
BEGIN DESCRIPTION:
ROB updated with Halff Survey & 2009 TNRIS LiDAR
END DESCRIPTION:
XS GIS Cut Line= 4
     2348003.085     6969069.651     2347648.191     6965520.706
     2347906.296     6964326.969     2347976.465     6964002.435
#Sta/Elev= 30
    1000     514    1130     516    1330     508    1520     506    1580     470
    1610   468.6    1660     470    1710     502 1875.43  499.95 1883.11  498.64
 1905.52   485.3 1914.73  485.94 1925.51  490.66 1982.34  488.55 2007.16  492.15
 2085.73     486 2339.86  498.92 2453.16   501.4  3399.9  503.12 3606.91  499.53
 3930.15  502.62 3952.88     516    4594     516 4616.11     504 4804.64  503.25
 4824.95  510.94  5002.2     511 5167.04  518.84 5753.77  520.31 6060.59  516.94
#Mann= 8 ,-1,0
    1000     .25       0    1520    .055       0    1710    .075       0
 2339.86     .12       0  3399.9     .15       0 3930.15     .07       0
 4616.11     .15       0 4824.95     .07       0
#XS Ineff= 2 , 0
            1520     506 1749.35          503.34
Permanent Ineff=
       F       F
#Block Obstruct= 1 ,-1
 1840.91 2392.05     498
Bank Sta=1520,1710
XS Rating Curve= 0 ,0
Exp/Cntr=0.3,0.1

Type RM Length L Ch R = 1 ,198174  ,805,724,580
BEGIN DESCRIPTION:
ROB updated with Halff Survey & 2009 TNRIS LiDAR
END DESCRIPTION:
XS GIS Cut Line= 4
      2348504.95     6969868.623     2348502.254     6969846.832
      2347980.22      6965626.85      2347997.38      6964089.91
#Sta/Elev= 30
    1000     513    1035   507.5    1245   505.3    1761   509.6    2073   503.2
    2396   502.7    2465     468    2500     467    2533   471.2    2550     478
    2584   502.8 2688.58  487.83 2859.56  482.38 2985.18  482.76 3406.38  497.76
 3467.49   502.1 4218.93  498.37 4531.75     503 4552.65     516 5267.57     516
    5293     505 5342.63  501.83 5538.47  502.43 5668.55   496.2 5723.42  514.44
 5819.85  519.99 6423.42   520.8 6732.17  517.38 6767.22  512.11 6805.11   514.1
#Mann= 7 ,-1,0
    1000     .25       0    2396    .055       0    2584    .075       0
 3406.38     .15       0 4531.75     .07       0 5342.63     .15       0
 5668.55     .07       0
#XS Ineff= 2 , 0
            2396   502.7 2592.56          503.36
Permanent Ineff=
       F       F
#Block Obstruct= 1 ,-1
 2602.27 3460.23     498
Bank Sta=2396,2584
XS Rating Curve= 0 ,0
Exp/Cntr=0.3,0.1

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
Type RM Length L Ch R = 1 ,197450  ,855,770,650
BEGIN DESCRIPTION:
New XS from 99 topo, interpolated FL, ROB updated with Halff Survey & 2009 TNRIS LiDAR
END DESCRIPTION:
XS GIS Cut Line= 5
   2349741.33176 6970183.8905078 2349487.1895125 6968919.0894779
 2348562.3127533 6966370.3012684 2348476.2778204 6965004.4949449
 2348416.5537532 6964056.3741531
#Sta/Elev= 30
    1000   511.8    1080     502    1400   499.7    2600     509    3000     506
    3100     470    3125   465.5    3150     470    3200     500  3221.2  502.56
 3350.16   499.9 3424.87  482.49 3461.66  477.45 3568.31   475.6 3992.64  498.11
 4004.66  500.91 4064.85  501.43  4697.8  498.47  4990.1  501.59 5003.08     504
 5021.71     515 5032.14     516 5753.18     516 5779.05  501.93 5972.35  501.84
 6033.88  506.77 6117.03  497.12 6204.19  497.28 6233.31  516.14 6481.95  517.13
#Mann= 7 ,-1,0
    1000     .25       0    3000    .055       0 3350.16    .075       0
 3992.64     .18       0  4990.1     .07       0 5779.05     .18       0
 6204.19     .07       0
#XS Ineff= 3 ,-1
    1000    3000     506  3221.2 6033.82  502.56 6033.82 6222.04  506.74
Permanent Ineff=
       F       F       T
#Block Obstruct= 1 ,-1
 3335.23 4034.09     498
Bank Sta=3000,3200
XS Rating Curve= 0 ,0
Exp/Cntr=0.3,0.1

Type RM Length L Ch R = 1 ,196680  ,550,750,450
BEGIN DESCRIPTION:
ROB updated with Halff Survey & 2009 TNRIS LiDAR
END DESCRIPTION:
XS GIS Cut Line= 4
   2350459.27714   6970863.80901   2350010.07593   6968659.57294
   2349045.13003   6966159.15996 2348846.7584696 6964144.5914655
#Sta/Elev= 30
    1000     511    1041   505.8    2235   500.7    2605   501.3    2810   510.4
    3808   499.1    3829   486.3    3856   486.8    3895   465.5    3930   463.8
    3945   464.5    3947     471    4004   501.9 4198.79  499.45 4290.71  480.59
 4391.66  476.52 4504.75  479.51 4604.34  497.11 4770.88  499.11 5742.08  500.96
 5758.21     511 5778.32     514 6344.68     516 6402.86  501.32 6643.71  502.34
 6712.02  499.49 7107.86  510.84 7544.96  506.36 7986.24  511.78  8011.3  515.76
#Mann= 7 ,-1,0
    1000     .25       0    3808    .055       0    4004    .075       0
 4770.88     .18       0 5742.08     .07       0 6402.86     .18       0
 6643.71     .07       0
#XS Ineff= 2 , 0
            3808   499.1 4030.27          502.37
Permanent Ineff=
       F       F
#Block Obstruct= 1 ,-1
 4166.67 4666.67     498
Bank Sta=3808,4004
XS Rating Curve= 0 ,0
Exp/Cntr=0.3,0.1

Type RM Length L Ch R = 1 ,195930  ,250,404,400
BEGIN DESCRIPTION:
ROB updated with Halff Survey & 2009 TNRIS LiDAR
END DESCRIPTION:
XS GIS Cut Line= 6
  2350799.201946 6971111.4184422 2350474.2049269 6967822.7110932
 2349433.4176384 6966219.7402178 2349358.1369491 6964961.4776425
 2349325.0781095 6964408.9229156 2349305.9669784 6964089.4941056
#Sta/Elev= 30
    1000     510    1050     506    1200   504.8    2700     504    2950   507.2
    3470     508    3730     504    3780     496    3950   493.5    4370     500
    4400     470    4450     464    4500     470    4600     500 4723.58  500.52
 4951.34  495.52 5231.25  499.19  5838.8  497.49 6080.13  500.69 6102.97  502.21
 6122.73  510.33 6136.62  511.58  6648.4  509.56 6666.56  501.72 7032.26  500.26
 7083.97  504.29  7203.4  504.27 7250.21  509.48 7435.83  507.77  7550.7  512.07
#Mann= 6 ,-1,0
    1000     .18       0    3730     .09       0    4370    .055       0
    4600     .15       0 6080.13     .07       0 6666.56     .15       0
#XS Ineff= 2 , 0
            4370     500 4643.21          501.49
Permanent Ineff=
       F       F
#Block Obstruct= 2 , 0
                            6100             508
Bank Sta=4370,4600
XS Rating Curve= 0 ,0
Exp/Cntr=0.3,0.1

Type RM Length L Ch R = 1 ,195526  ,500,437,700
BEGIN DESCRIPTION:
195526
END DESCRIPTION:
XS GIS Cut Line= 5
  2351105.088864  6971198.753877   2351105.06685   6971198.53111
   2350748.60005   6967591.37494   2349972.41984   6966325.86402
   2349864.37806   6964083.99515
#Sta/Elev= 30
    1000   510.3    1033   504.9    1317   504.3    2666   503.2    3091   508.5
    3461   503.5    3632   505.7    3650   504.6    3720     520    4210     520
    4260   504.1    4545   504.1    4815   498.5    4836   491.7    4864   474.3
    4885   470.8    4893   465.5    4928   464.5    4945     465    4962   470.8
    4999   500.4    5700   497.9    7283     505    7367   506.2    7396   510.7
    8213   510.5    8235     514    8310     512    8322     517    8354   517.9
#Mann= 7 ,-1,0
    1000     .18       0    3632     .09       0    4545      .1       0
    4815    .055       0    4999     .12       0    8213     .04       0
    8322     .12       0
#XS Ineff= 2 , 0
            4815   498.5    4999           500.4
Permanent Ineff=
       F       F
Bank Sta=4815,4999
XS Rating Curve= 0 ,0
Exp/Cntr=0.3,0.1

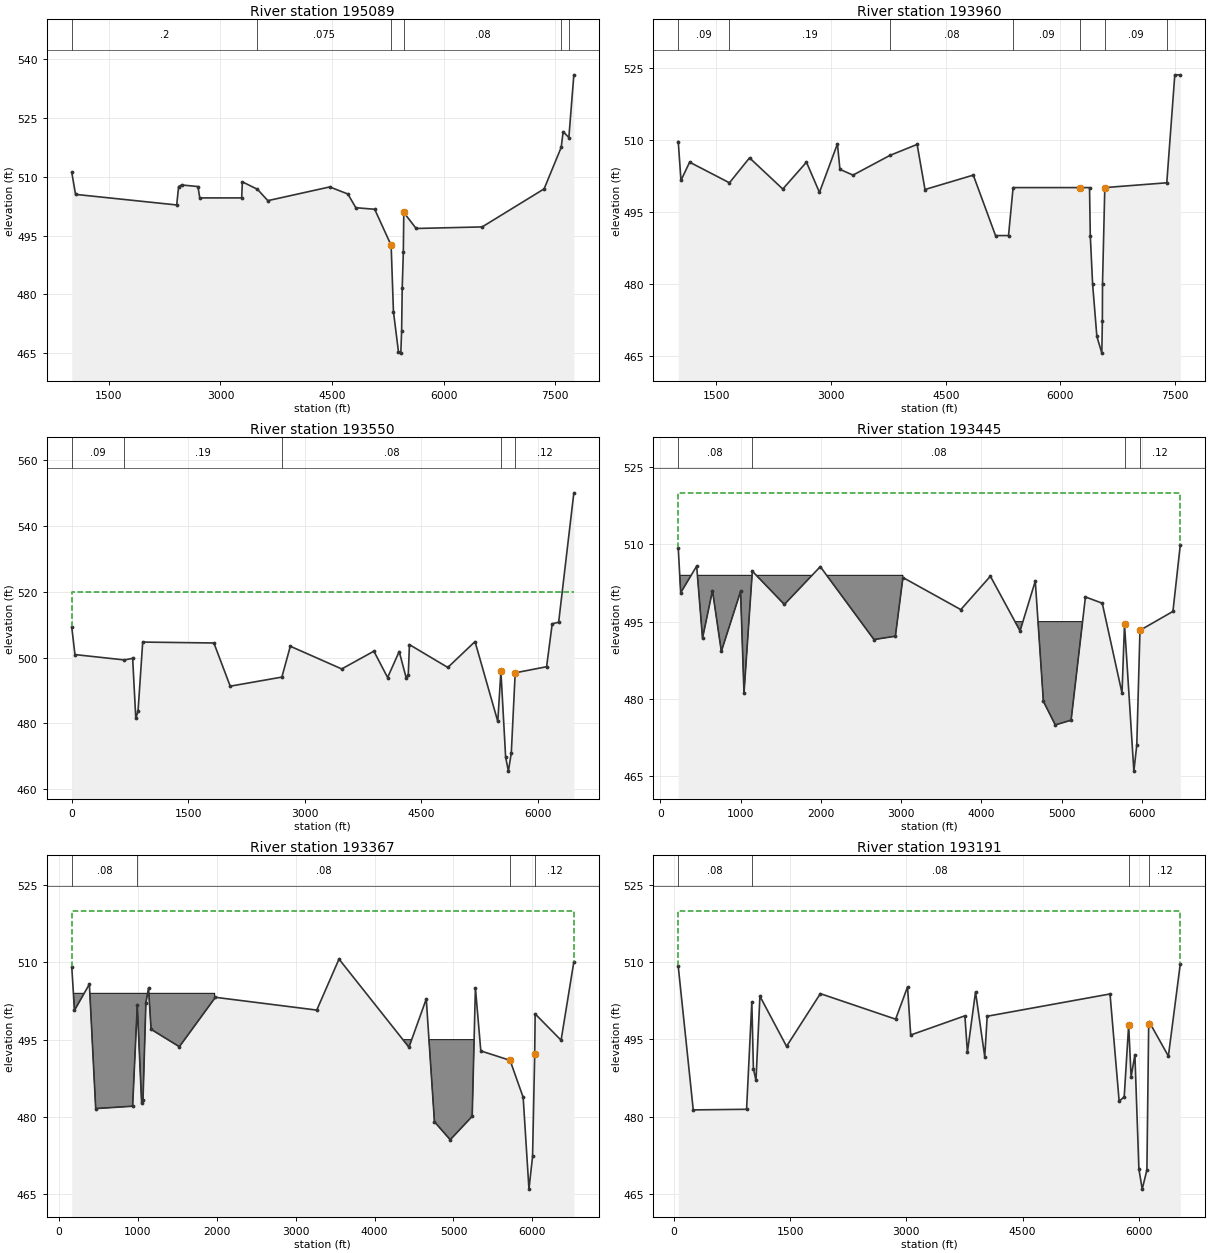
Type RM Length L Ch R = 1 ,195089  ,1140,1139,827
BEGIN DESCRIPTION:
This cross section corresponds to cross section 195089 of the non-georeferenced CDC model which was the source of this model.
END DESCRIPTION:
XS GIS Cut Line= 6
   2351674.21992   6971493.79496   2351249.84084   6967958.91883
   2350512.53293   6965737.03055   2350512.53293   6965726.17985
   2350695.08309   6965382.96893   2350913.68502   6964971.97598
#Sta/Elev= 30
    1000   511.1    1051   505.5    2411   502.8    2437   507.5    2476   507.9
    2697   507.5    2721   504.6    3285   504.6    3294   508.7    3497   506.8
    3637   503.9    4469   507.4    4713   505.6    4820   502.1    5074   501.7
    5295   492.5    5326   475.6    5393   465.4    5425     465    5436   470.7
    5444   481.7    5459   490.8    5465   500.9    5631   496.8    6519   497.2
    7352   506.9    7582   517.5    7608   521.5    7685     520    7752     536
#Mann= 6 ,-1,0
    1000      .2       0    3497    .075       0    5295     .05       0
    5465     .08       0    7582     .04       0    7685     .08       0
#XS Ineff= 2 , 0
            5295   492.5    5465           500.9
Permanent Ineff=
       F       F
Bank Sta=5295,5465
XS Rating Curve= 0 ,0
Exp/Cntr=0.3,0.1

Type RM Length L Ch R = 1 ,193960  ,158,404,739
BEGIN DESCRIPTION:
This cross section corresponds to cross section 193960 of the non-georeferenced CDC model which was the source of this model.
END DESCRIPTION:
XS GIS Cut Line= 6
  2352299.126757 6971745.9850765 2352208.5338073 6969120.7800194
 2352129.8380986 6966840.8078733 2351752.5311104 6966449.8037341
 2351375.2149359 6966058.8038599  2351445.887498 6965487.9918045
#Sta/Elev= 30
    1000   509.6    1036   501.5    1149   505.3    1670     501    1933   506.2
    2368   499.7    2678   505.3    2848     499    3083   509.1    3116   503.8
    3287   502.6    3769   506.7    4126     509    4229   499.6    4861   502.6
    5152     490    5322     490    5382     500    6262     500    6382     500
    6392     490    6422     480    6478     469    6543   465.5    6550   472.2
    6552     480    6582     500    7393     501    7498   523.5    7570   523.5
#Mann= 7 ,-1,0
    1000     .09       0    1670     .19       0    3769     .08       0
    5382     .09       0    6262    .055       0    6582     .09       0
    7393     .04       0
#XS Ineff= 2 , 0
            6262     500    6582             500
Permanent Ineff=
       F       F
Bank Sta=6262,6582
XS Rating Curve= 0 ,0
Exp/Cntr=0.3,0.1

Type RM Length L Ch R = 1 ,193550  ,106,104,61
BEGIN DESCRIPTION:
This cross section corresponds to cross section 193550 of the non-georeferenced CDC model which was the source of this model.
END DESCRIPTION:
XS GIS Cut Line= 3
  2352443.025935 6971891.6115285 2352258.7703713  6966552.700172
 2351828.4115221 6965519.1106147
#Sta/Elev= 30
       0  509.18   41.13   500.9  677.13  499.27  783.58  499.76  824.05  481.51
  852.93  483.73  912.97   504.7 1829.18  504.42 2039.15   491.3 2703.93  494.06
  2812.7  503.43 3474.17  496.54 3888.24  501.93 4064.79  493.93 4214.01  501.83
 4304.49  493.79 4330.97   494.8 4345.66  503.93 4839.83  496.99 5189.74  504.85
 5482.76  480.59 5522.98  495.82 5583.86  469.74 5619.12   465.5 5656.59  470.97
 5706.85  495.36 6111.13  497.21 6183.22  510.26 6266.13  510.73  6461.7  550.03
#Mann= 5 ,-1,0
       0     .09       0  677.13     .19       0 2703.93     .08       0
 5522.98    .055       0 5706.85     .12       0
#XS Ineff= 2 , 0
               0     520
Permanent Ineff=
       F       F
#Block Obstruct= 2 , 0
            2751     504
Bank Sta=5522.98,5706.85
XS Rating Curve= 0 ,0
Exp/Cntr=0.3,0.1

Type RM Length L Ch R = 1 ,193445  ,122,78,51
BEGIN DESCRIPTION:
This cross section corresponds to cross section 193445 of the non-georeferenced CDC model which was the source of this model.
END DESCRIPTION:
XS GIS Cut Line= 6
2352474.617988956971912.11832126  2352471.779015 6971686.2161615
 2352456.5881012 6970477.4485659 2352394.3050893 6967434.9139686
 2352385.2775483 6966508.8721855 2351974.1408146  6965763.491814
#Sta/Elev= 30
  224.08  509.32  254.81  500.62  453.74  505.78   526.7  491.79  650.64  501.03
  761.17  489.23  1000.6  500.87 1043.32  481.13 1147.23   504.8 1546.14  498.34
 1994.09  505.68 2662.67  491.53 2929.41  492.18 3023.46  503.57 3744.55  497.34
 4112.99  503.82 4482.76  493.21 4672.53  502.87 4773.32  479.55 4921.56  474.97
 5118.77  475.88 5297.32   499.8 5506.87  498.58  5753.1  481.14 5784.16  494.47
 5900.72     466 5937.01  471.06 5976.78  493.32 6387.44  496.99 6479.37  509.94
#Mann= 4 ,-1,0
  224.08     .08       0 1147.23     .08       0 5784.16    .055       0
 5976.78     .12       0
#XS Ineff= 2 , 0
          224.08     520 6479.37             520
Permanent Ineff=
       F       F
#Block Obstruct= 2 ,-1
       0    3023     504    4194    5273     495
Bank Sta=5784.16,5976.78
XS Rating Curve= 0 ,0
Exp/Cntr=0.3,0.1

Type RM Length L Ch R = 1 ,193367  ,205,174,200
BEGIN DESCRIPTION:
This cross section corresponds to cross section 193367 of the non-georeferenced CDC model which was the source of this model.
END DESCRIPTION:
XS GIS Cut Line= 5
2352568.827706016971743.13759569 2352568.8277062 6970066.9018148
 2352503.7235057 6966965.3394484 2352505.5683183  6966515.035559
 2351886.8615504 6965570.2654669
#Sta/Elev= 30
  166.21  509.13  200.37   500.7  389.26  505.77  469.18  481.63  936.98  482.09
  995.79  501.69 1050.82  482.71 1068.34  483.31 1104.48  502.09 1138.52  505.03
 1170.41  497.01 1528.56  493.63 1985.19  503.22 3268.55  500.74 3550.35  510.64
 4436.17  493.53 4655.42  502.89 4759.06  479.07  4958.8  475.58 5237.04  480.12
 5277.69  505.07 5346.19  492.82 5716.61  490.99 5882.44  483.82 5955.94     466
 6001.45  472.34 6028.73   492.3 6034.24     500 6362.69  494.89 6524.33  510.11
#Mann= 4 ,-1,0
  166.21     .08       0  995.79     .08       0 5716.61    .055       0
 6034.24     .12       0
#XS Ineff= 2 , 0
          166.21     520 6524.33             520
Permanent Ineff=
       F       F
#Block Obstruct= 2 ,-1
       0    1976     504    4287    5277     495
Bank Sta=5716.61,6028.73
XS Rating Curve= 0 ,0
Exp/Cntr=0.3,0.1

Type RM Length L Ch R = 1 ,193191  ,57,43,48
BEGIN DESCRIPTION:
This cross section corresponds to cross section 193190 of the non-georeferenced CDC model which was the source of this model.
END DESCRIPTION:
XS GIS Cut Line= 6
 2352785.36338596972022.06525592 2352778.4631137 6971204.4018364
 2352774.1228992 6969863.2558966 2352704.7654264 6967023.4121669
 2352708.2375323 6966507.4401017 2352176.3939033 6965698.3965122
#Sta/Elev= 30
   53.99  509.21  247.89   481.3  936.48  481.42 1004.48   502.3 1024.63   489.3
 1057.99  487.03 1108.82   503.4 1452.78  493.66  1889.3   503.9 2861.37  498.94
 3015.24  505.21 3055.94  495.86 3755.73  499.59  3788.4  492.53 3893.22  504.23
 4012.21  491.64 4043.83  499.51 5630.05  503.84  5747.9  482.99 5813.19  483.84
 5870.72  497.81 5902.14  487.69 5951.19  492.03 6002.89  469.82 6045.64   465.9
 6106.29  469.63 6129.35  498.03 6137.41  498.39 6383.54  491.76 6537.71  509.71
#Mann= 4 ,-1,0
   53.99     .08       0 1004.48     .08       0 5870.72    .055       0
 6137.41     .12       0
#XS Ineff= 2 , 0
           53.99     520 6537.71             520
Permanent Ineff=
       F       F
#Block Obstruct= 2 , 0
            1889     504
Bank Sta=5870.72,6129.35
XS Rating Curve= 0 ,0
Exp/Cntr=0.3,0.1

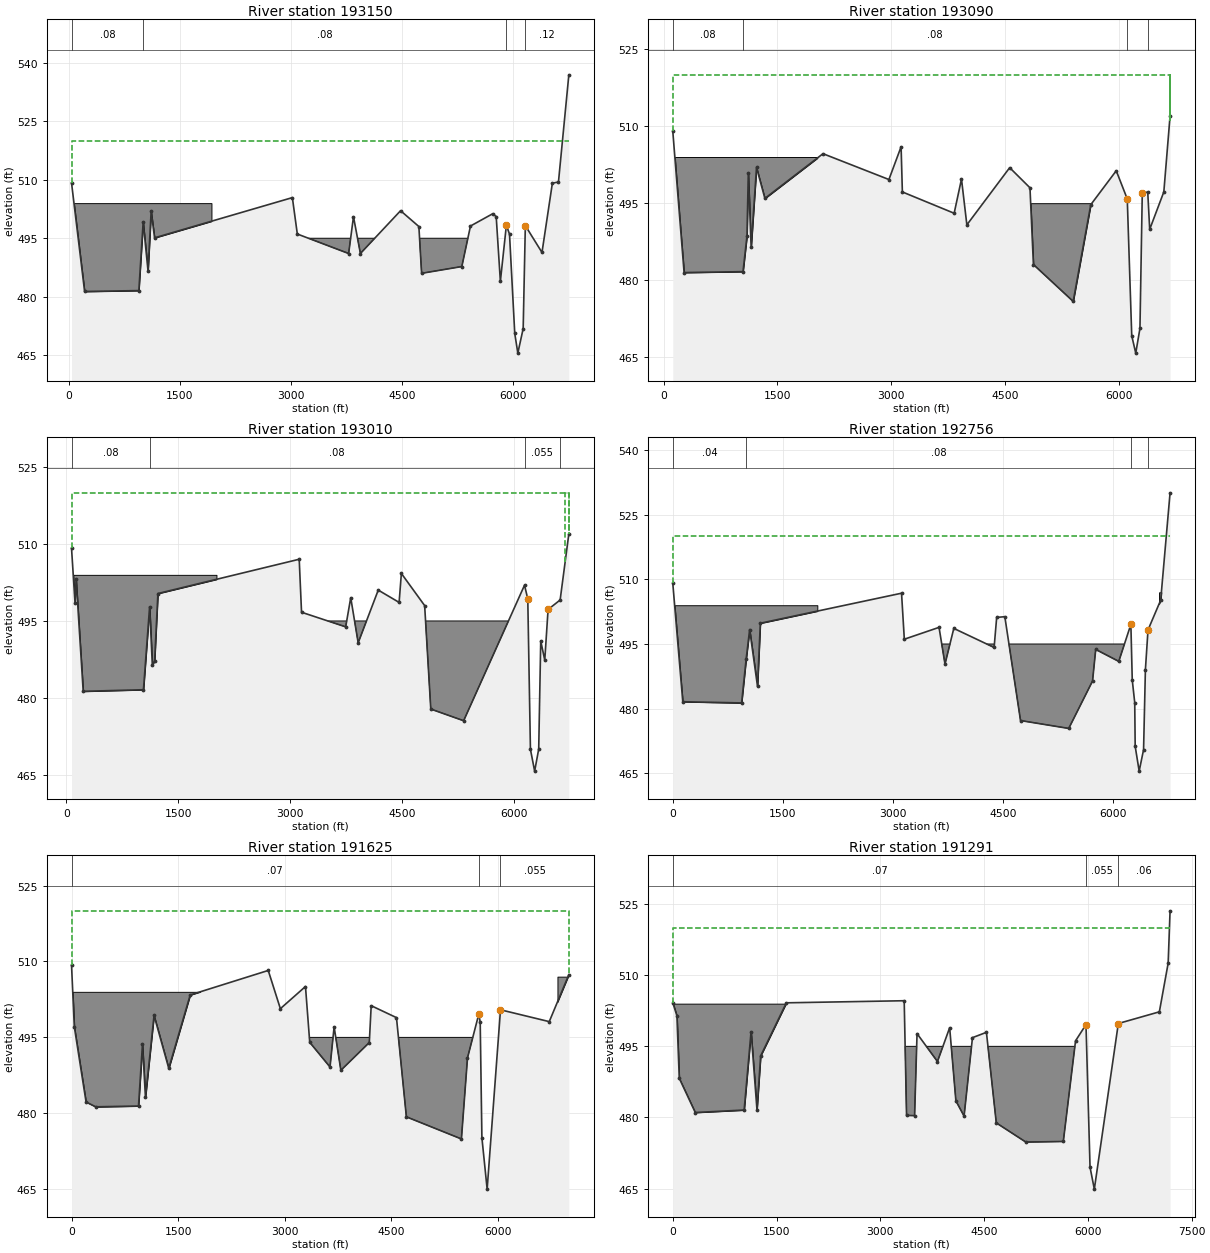
Type RM Length L Ch R = 1 ,193150  ,60,60,66
BEGIN DESCRIPTION:
This cross section corresponds to cross section 193150 of the non-georeferenced CDC model which was the source of this model.
END DESCRIPTION:
XS GIS Cut Line= 6
 2352852.87840286972104.08080362 2352840.5612366 6970218.7025511
 2352837.4241144 6969621.6036281 2352760.3903363  6966987.815267
 2352764.1084071  6966515.620283 2352143.1905934   6965569.92899
#Sta/Elev= 30
   35.86   509.2  212.61  481.34  945.59  481.57 1004.06  499.15 1069.66  486.64
 1112.03   501.9 1158.23   495.1 3020.37  505.42 3087.22  496.08 3780.94  491.08
 3846.26  500.52 3939.83  491.08 4482.74  502.06    4730     498    4767     486
 5310.69  487.74 5427.39  498.13 5728.71  501.29 5775.07  500.54 5831.45  483.94
 5912.64  498.34 5955.03  496.02 6025.82  470.57 6067.43  465.53 6139.66  471.83
 6168.79  498.23 6393.85  491.35 6534.23  509.12 6616.55  509.43 6756.83  536.91
#Mann= 4 ,-1,0
   35.86     .08       0 1004.06     .08       0 5912.64    .055       0
 6168.79     .12       0
#XS Ineff= 2 , 0
           35.86     520
Permanent Ineff=
       F       F
#Block Obstruct= 2 ,-1
       0    1927     504    3029    5483     495
Bank Sta=5912.64,6168.79
XS Rating Curve= 0 ,0
Exp/Cntr=0.3,0.1

Type RM Length L Ch R = 1 ,193090  ,123,77,86
BEGIN DESCRIPTION:
This cross section corresponds to cross section 193090 of the non-georeferenced CDC model which was the source of this model.
END DESCRIPTION:
XS GIS Cut Line= 5
      2352883.33      6972118.35 2352820.0121124 6966491.7834846
 2352334.5736959 6965753.6684197 2352327.35962016965720.95626289
2352326.231097676965715.83898887
#Sta/Elev= 30
   120.9  509.08  270.24  481.49 1046.04  481.67 1098.25   488.6 1115.99  500.87
 1153.14  486.41 1223.99  501.96 1334.13  495.93 2099.58  504.64  2967.5  499.61
 3127.86  505.99 3144.69  497.19 3826.58  493.04 3923.29   499.7 3993.92  490.78
  4557.8  501.92    4825     498 4870.25  483.06 5394.06  475.87 5625.78  494.71
 5961.22  501.32 6106.15  495.83 6165.19  469.18    6218   465.8 6273.41  470.62
 6304.06  497.07 6375.99  497.14 6401.74  489.91 6587.76   497.2    6670     512
#Mann= 4 ,-1,0
   120.9     .08       0 1046.04     .08       0 6106.15    .055       0
 6375.99     .12       0
#XS Ineff= 2 , 0
           120.9     520 6664.76             520
Permanent Ineff=
       F       F
#Block Obstruct= 2 ,-1
       0    2024     504    4778    5940     495
Bank Sta=6106.15,6304.06
XS Rating Curve= 0 ,0
Exp/Cntr=0.3,0.1

Type RM Length L Ch R = 1 ,193010  ,130,257,335
BEGIN DESCRIPTION:
This cross section corresponds to cross section 193010 of the non-georeferenced CDC model which was the source of this model.
END DESCRIPTION:
XS GIS Cut Line= 6
 2352971.71732316972172.17847792 2352920.2764783 6967629.3866767
 2352962.6376141 6967475.2199903 2352915.2525382  6966498.299372
 2352430.4598727 6965760.04428682352410.057336856965666.74295198
#Sta/Elev= 30
   71.23  509.17  117.97  498.57  132.87  503.14  227.51  481.27 1034.38  481.58
 1117.05  497.77 1153.08  486.43 1183.83  487.18    1228  500.35 3120.14  507.04
 3151.34   496.7 3742.62  493.85 3810.14  499.54 3909.82  490.74 4178.56  501.02
  4458.1  498.62 4488.22  504.27    4800     498 4882.31  477.81 5322.27  475.53
 6137.45  501.98 6181.08   499.3 6216.49  469.96 6273.04   465.7 6327.41  469.99
 6354.58   491.1 6408.59  487.36 6452.91  497.24 6614.36  499.09    6731     512
#Mann= 4 ,-1,0
   71.23     .08       0 1117.05     .08       0 6137.45    .055       0
 6614.36     .12       0
#XS Ineff= 2 , 0
           71.23     520 6681.76             520
Permanent Ineff=
       F       F
#Block Obstruct= 2 ,-1
       0    2012     504    3136    6169     495
Bank Sta=6181.08,6452.91
XS Rating Curve= 0 ,0
Exp/Cntr=0.3,0.1

Type RM Length L Ch R = 1 ,192756  ,607,1131,666
BEGIN DESCRIPTION:
This cross section corresponds to cross section 192756 of the non-georeferenced CDC model which was the source of this model.
---------------------------------------------------------------------
CDC FW121411-01 Goodman A Gas Well Site Pad
Cross-section 192756 - 193191
Project located in LOB.
---------------------------------------------------------------------
END DESCRIPTION:
XS GIS Cut Line= 3
 2353128.2404482 6972246.6721883 2353079.1993948 6966964.3987254
 2352733.0660952 6965508.0504607
#Sta/Elev= 30
       0  509.18  136.61   481.6  938.54  481.32 1000.06  491.43 1048.26  498.35
 1155.25  485.19 1193.84  499.82 3118.81  506.79  3156.6  496.11 3629.96  498.86
 3711.19  490.33 3831.21  498.62 4380.82  494.19 4415.66  501.17 4526.84  501.34
 4740.87  477.23 5398.19   475.4 5722.52   486.4 5765.83  493.74 6080.24  490.96
 6245.12  499.56 6263.85  486.66 6297.54   481.4 6303.81  471.25 6358.17  465.49
 6418.16  470.47 6443.12  489.03 6478.67  498.26 6651.54  505.18 6779.42  530.09
#Mann= 4 ,-1,0
       0     .04       0 1000.06     .08       0 6245.12    .055       0
 6478.67     .07       0
#XS Ineff= 2 , 0
               0     520
Permanent Ineff=
       F       F
#Block Obstruct= 3 ,-1
       0    1971     504    3128    6172     495    6629    6662     507
Bank Sta=6245.12,6478.67
XS Rating Curve= 0 ,0
Exp/Cntr=0.3,0.1

Type RM Length L Ch R = 1 ,191625  ,400,341,222
BEGIN DESCRIPTION:
This cross section corresponds to cross section 191625 of the non-georeferenced CDC model which was the source of this model.
END DESCRIPTION:
XS GIS Cut Line= 3
 2353454.1551259 6972415.7538811  2353705.260242 6966962.8503038
 2353408.5971956  6965451.957321
#Sta/Elev= 30
       0  509.26      39  497.12   204.5  482.24  340.91  481.28  942.64  481.44
  998.62  493.66 1040.32  483.14 1161.26  499.33 1368.44  488.88  1670.2  503.38
 2768.11  508.22 2938.86  500.67  3292.2  505.05 3352.13  494.02 3637.63  489.14
 3695.25  497.09 3790.16  488.49 4190.42  493.98    4217  501.26 4572.67   498.9
 4712.12   479.3 5486.61  474.93 5572.24  490.94 5732.33  499.66 5751.04  497.95
 5774.91  475.17 5848.65  465.02 6036.57  500.45 6722.72  498.11 6998.43  507.39
#Mann= 3 ,-1,0
       0     .07       0 5732.33    .055       0 6036.57    .055       0
#XS Ineff= 2 , 0
               0     520 6998.43             520
Permanent Ineff=
       F       F
#Block Obstruct= 3 ,-1
       0    2106     504    3305    5693     495    6838    6998     507
Bank Sta=5732.33,6036.57
XS Rating Curve= 0 ,0
Exp/Cntr=0.3,0.1

Type RM Length L Ch R = 1 ,191291  ,284,433,141
BEGIN DESCRIPTION:
This cross section corresponds to cross section 191291 of the non-georeferenced CDC model which was the source of this model.
END DESCRIPTION:
XS GIS Cut Line= 6
  2353552.599145 6972462.9669784 2353620.0158925 6972021.9690989
 2353960.6323372 6969558.7702851 2354079.3820998  6967149.916179
 2354087.7157445 6966940.5412697 2353571.0487988 6965390.5410888
#Sta/Elev= 30
       0  504.23   60.11  501.43   94.05  488.26  325.34  481.05 1031.92  481.57
 1131.88  498.08 1217.34  481.61 1270.59  492.99 1642.22  504.17 3345.13  504.61
 3379.14  480.43  3495.4  480.39 3530.82  497.68 3825.93  491.79 4002.17  498.93
 4092.24  483.51 4210.62  480.29 4331.85  496.83 4533.62  497.95  4676.1  478.86
 5103.96  474.81  5644.9  474.94 5821.76  496.16 5972.63  499.58 6031.15  469.52
  6093.2   464.9 6440.01  499.81 7033.03  502.27 7160.27  512.52 7187.94  523.56
#Mann= 3 ,-1,0
       0     .07       0 5972.63    .055       0 6440.01     .06       0
#XS Ineff= 2 , 0
               0     520
Permanent Ineff=
       F       F
#Block Obstruct= 2 ,-1
       0    2088     504    3343    5836     495
Bank Sta=5972.63,6440.01
XS Rating Curve= 0 ,0
Exp/Cntr=0.3,0.1

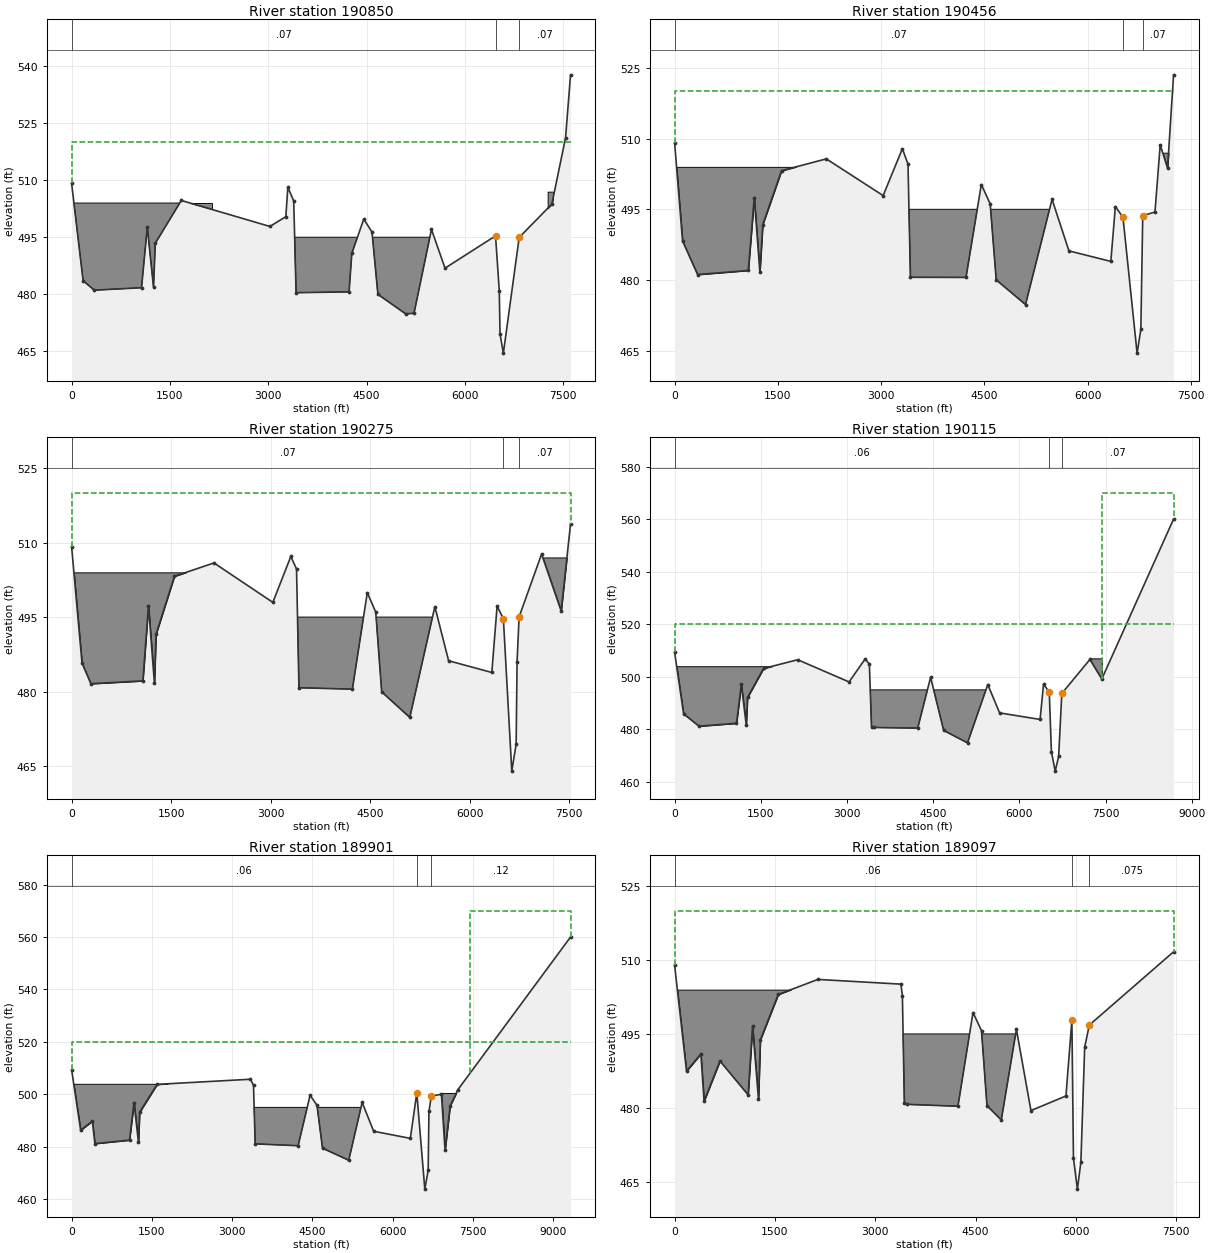
Type RM Length L Ch R = 1 ,190850  ,5,394,616
BEGIN DESCRIPTION:
This cross section corresponds to cross section 190850 of the non-georeferenced CDC model which was the source of this model.
END DESCRIPTION:
XS GIS Cut Line= 6
 2353565.9566837 6972477.4829845 2354046.7762485 6969402.5125301
 2354448.1848144 6966835.3648757 2354315.9538162   6966164.24788
 2353868.8366297 6965909.4975494 2353703.2560966 6965227.3501749
#Sta/Elev= 30
       0  509.16  175.37  483.55  345.87  481.05 1066.59   481.7 1154.68  497.65
 1249.49  481.85 1276.82  493.41 1673.24  504.68 3024.75  497.83 3268.02  500.41
 3298.54  508.16 3388.31  504.54 3424.13  480.39 4232.66  480.61 4274.88  490.77
 4456.81  499.76 4582.46  496.35 4672.22  479.96 5097.04   474.8 5223.47  474.98
  5489.5  497.04 5696.43  486.85 6466.94  495.36 6523.81  480.92 6535.53   469.5
 6586.55  464.48 6827.82  494.95 7326.43  503.73 7535.27  521.21 7611.25  537.75
#Mann= 3 ,0,0
       0     .07       0 6466.94     .05       0 6827.82     .07       0
#XS Ineff= 2 , 0
               0     520
Permanent Ineff=
       F       F
#Block Obstruct= 3 ,-1
       0    2144     504    3399    5489     495    7262    7342     507
Bank Sta=6466.94,6827.82
XS Rating Curve= 0 ,0
Exp/Cntr=0.3,0.1

Type RM Length L Ch R = 1 ,190456  ,1,181,319
BEGIN DESCRIPTION:
This cross section corresponds to cross section 190456 of the non-georeferenced CDC model which was the source of this model.
END DESCRIPTION:
XS GIS Cut Line= 6
 2353570.8966569 6972478.2554258 2354051.7162213 6969403.2849736
 2354317.7046715 6967702.1903658 2354448.8880042 6966863.2331041
 2354508.9223442 6966479.2914287  2354382.983564 6965311.0014349
#Sta/Elev= 30
       0   509.1  115.02  488.27  333.58  481.16 1070.24  482.03 1156.45  497.47
 1238.06  481.67 1280.55  491.77 1552.48  503.18 2203.02  505.69  3028.6   497.9
 3308.18  507.85 3389.58  504.58 3425.07  480.58 4232.14  480.55 4454.99  500.25
 4583.56  496.13 4670.93  480.03 5096.61   474.8 5482.09   497.1 5727.24  486.18
 6335.81  483.95 6401.47  495.59 6512.03   493.3 6717.22   464.5 6771.75  469.52
 6799.31  493.64 6976.88  494.42    7053  508.67 7159.46   503.7 7246.92  523.51
#Mann= 3 ,0,0
       0     .07       0 6512.03     .05       0 6799.31     .07       0
#XS Ineff= 2 , 0
               0     520
Permanent Ineff=
       F       F
#Block Obstruct= 3 ,-1
       0    2140     504    3398    5482     495    7053    7199     507
Bank Sta=6512.03,6799.31
XS Rating Curve= 0 ,0
Exp/Cntr=0.3,0.1

Type RM Length L Ch R = 1 ,190275  ,1,161,285
BEGIN DESCRIPTION:
This cross section corresponds to cross section 190275 of the non-georeferenced CDC model which was the source of this model.
---------------------------------------------------------------------
CDC FW021297-1 Randol Mill Road
Located in ROB.
Cross-sections 190275 - 205240
---------------------------------------------------------------------
END DESCRIPTION:
XS GIS Cut Line= 6
 2353575.8366299 6972479.0278671  2354056.656194 6969404.0574172
 2354322.6446458 6967702.9627996 2354453.8279779 6966864.0055417
 2354510.9875144 6966498.4492909 2354783.9703103 6965058.0982749
#Sta/Elev= 30
       0  509.18  156.65  485.75  289.52  481.59 1073.51  482.16 1158.47  497.29
  1248.1  481.67  1271.9  491.53 1548.96   503.2  2145.3  505.89 3032.45  497.96
  3303.7   507.2 3389.61  504.67    3426  480.78  4231.6  480.49 4455.97  499.91
 4583.31  496.01 4672.98  479.95 5096.75  474.81 5474.35  497.09 5681.61  486.21
 6332.68  483.85 6412.19  497.19 6506.91  494.69 6633.52     464 6699.51  469.43
 6713.28  486.03 6743.96  495.03 7082.81  507.67 7377.54  496.23 7519.24  513.74
#Mann= 3 ,-1,0
       0     .07       0 6506.91     .05       0 6743.96     .07       0
#XS Ineff= 2 , 0
               0     520
Permanent Ineff=
       F       F
#Block Obstruct= 3 ,-1
       0    2145     504    3398    5474     495    7082    7471     507
Bank Sta=6506.91,6743.96
XS Rating Curve= 0 ,0
Exp/Cntr=0.3,0.1

Type RM Length L Ch R = 1 ,190115  ,1,213,381
BEGIN DESCRIPTION:
This cross section corresponds to cross section 190115 of the non-georeferenced CDC model which was the source of this model.
END DESCRIPTION:
XS GIS Cut Line= 6
 2353580.7766031 6972479.8003084 2354061.5961679 6969404.8298539
 2354327.5846207 6967703.7352294 2354458.7679521 6966864.7779757
 2354518.2680876 6966484.25273452355711.847711056964156.86448458
#Sta/Elev= 30
       0  509.27  156.15  485.88  423.91  481.18 1076.79  482.29 1160.49  497.11
 1246.54  481.62 1268.72  492.12 1547.06  503.14  2142.1  506.47  3036.3  498.02
 3316.84   506.8 3389.63  504.77 3426.94  480.97 3473.23  480.68 4231.08  480.43
  4455.1  499.77 4682.52  479.56 5098.08  474.82 5450.68  497.03  5656.1  486.23
    6361  483.74 6421.42  497.21 6520.72  494.14 6557.71   471.5 6623.91  464.07
 6683.91  469.66  6738.8  493.62 7228.24  506.57 7434.86  499.13    8684     560
#Mann= 3 ,0,0
       0     .06       0 6520.72     .05       0  6738.8     .07       0
#XS Ineff= 2 , 0
               0     520 7434.86             570
Permanent Ineff=
       F       F
#Block Obstruct= 3 ,-1
       0    2142     504    3399    5467     495    7228 7434.86     507
Bank Sta=6520.72,6738.8
XS Rating Curve= 0 ,0
Exp/Cntr=0.3,0.1

Type RM Length L Ch R = 1 ,189901  ,1,803,909
BEGIN DESCRIPTION:
This cross section corresponds to cross section 189901 of the non-georeferenced CDC model which was the source of this model.
END DESCRIPTION:
XS GIS Cut Line= 6
 2353582.5178905 6972482.2357489 2353586.2020718 6972477.4678726
 2354066.5361417 6969405.6022906 2354332.5245957 6967704.5076593
 2354522.7915073 6966487.68918842356929.134977186964294.15155086
#Sta/Elev= 30
       0   509.4   168.6  486.31  387.15  489.74  434.83  481.18  1082.1  482.52
 1166.09  496.83 1249.35  481.64 1270.99  493.16 1597.54  503.78 3342.72  505.74
 3399.29  503.39 3430.76  481.08 4233.43  480.37 4456.98  499.67 4585.68  495.78
 4688.84  479.43 5179.28  474.82 5430.01  496.91 5644.99  485.89 6330.29  483.18
 6451.17  500.51 6600.84  463.81 6663.77  470.97 6678.48  493.45 6722.35  499.35
 6911.75     500 6979.17  478.61 7073.91  495.56 7218.78  501.75 9324.67     560
#Mann= 3 ,0,0
       0     .06       0 6451.17     .05       0 6722.35     .12       0
#XS Ineff= 2 , 0
               0     520 7443.67             570
Permanent Ineff=
       F       F
#Block Obstruct= 3 ,-1
       0    2074     504    3300    5430     495    6898    7218   500.5
Bank Sta=6451.17,6722.35
XS Rating Curve= 0 ,0
Exp/Cntr=0.3,0.1

Type RM Length L Ch R = 1 ,189097  ,739,856,528
BEGIN DESCRIPTION:
This cross section corresponds to cross section 189097 of the non-georeferenced CDC model which was the source of this model.
END DESCRIPTION:
XS GIS Cut Line= 6
 2353583.9913032 6972482.6603119 2353590.8445572 6972480.1428294
 2354341.7134457 6967678.1069597 2354860.0492788 6967002.4654647
 2355765.3872703 6966609.4866348  2356461.301574 6966320.0472803
#Sta/Elev= 30
       0  508.92  177.87  487.46  392.64  490.94  440.08  481.34  677.63   489.5
 1098.92  482.62 1165.15  496.57 1253.87  481.72 1281.94   493.8 1549.34  503.01
 2142.02  506.07 3383.74  505.11 3405.36   502.8 3434.92  481.03 3468.25   480.7
  4236.1  480.31 4461.13  499.34 4588.63  495.66 4669.68  480.44 4884.29  477.52
 5110.34  495.92 5327.62  479.43 5851.01   482.4 5939.63  497.83 5963.16  469.77
 6021.95  463.48 6074.14  468.98 6130.96  492.31 6200.58   496.8 7459.91  511.68
#Mann= 3 ,0,0
       0     .06       0 5939.63     .05       0 6200.58    .075       0
#XS Ineff= 2 , 0
               0     520
Permanent Ineff=
       F       F
#Block Obstruct= 2 ,-1
       0    2078     504    3410    5110     495
Bank Sta=5939.63,6200.58
XS Rating Curve= 0 ,0
Exp/Cntr=0.3,0.1