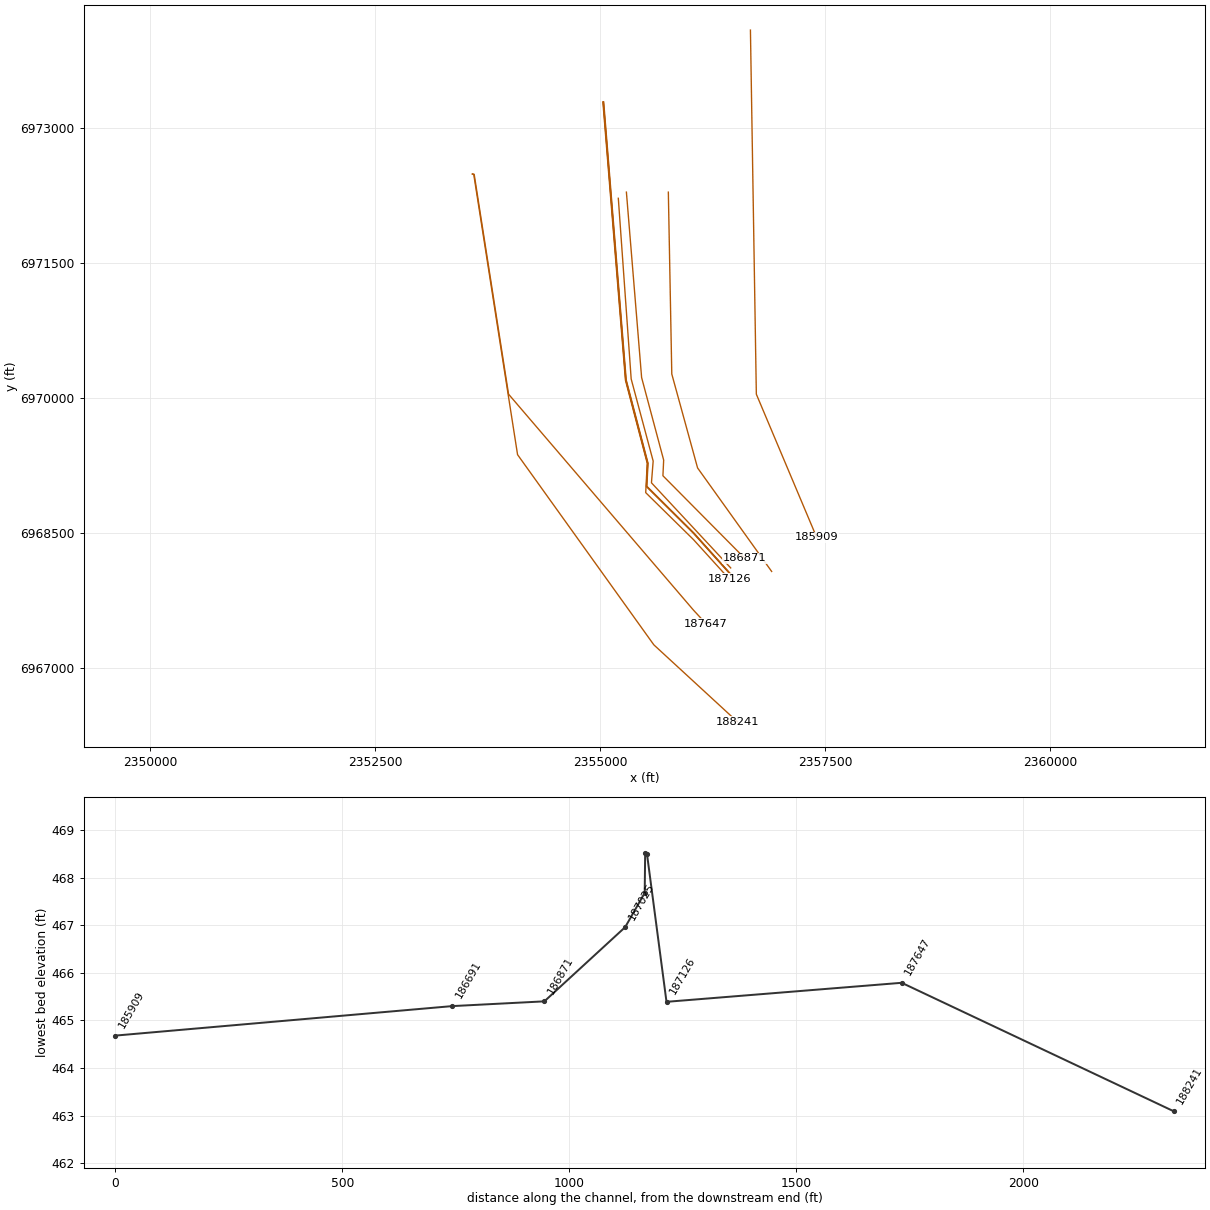
HEC-RAS study CDC_Consolidated_Model.prj: Upper Trinity CDC Consolidated Model

--- CDC_Consolidated_Model.g13 (geometry) --- (continued)

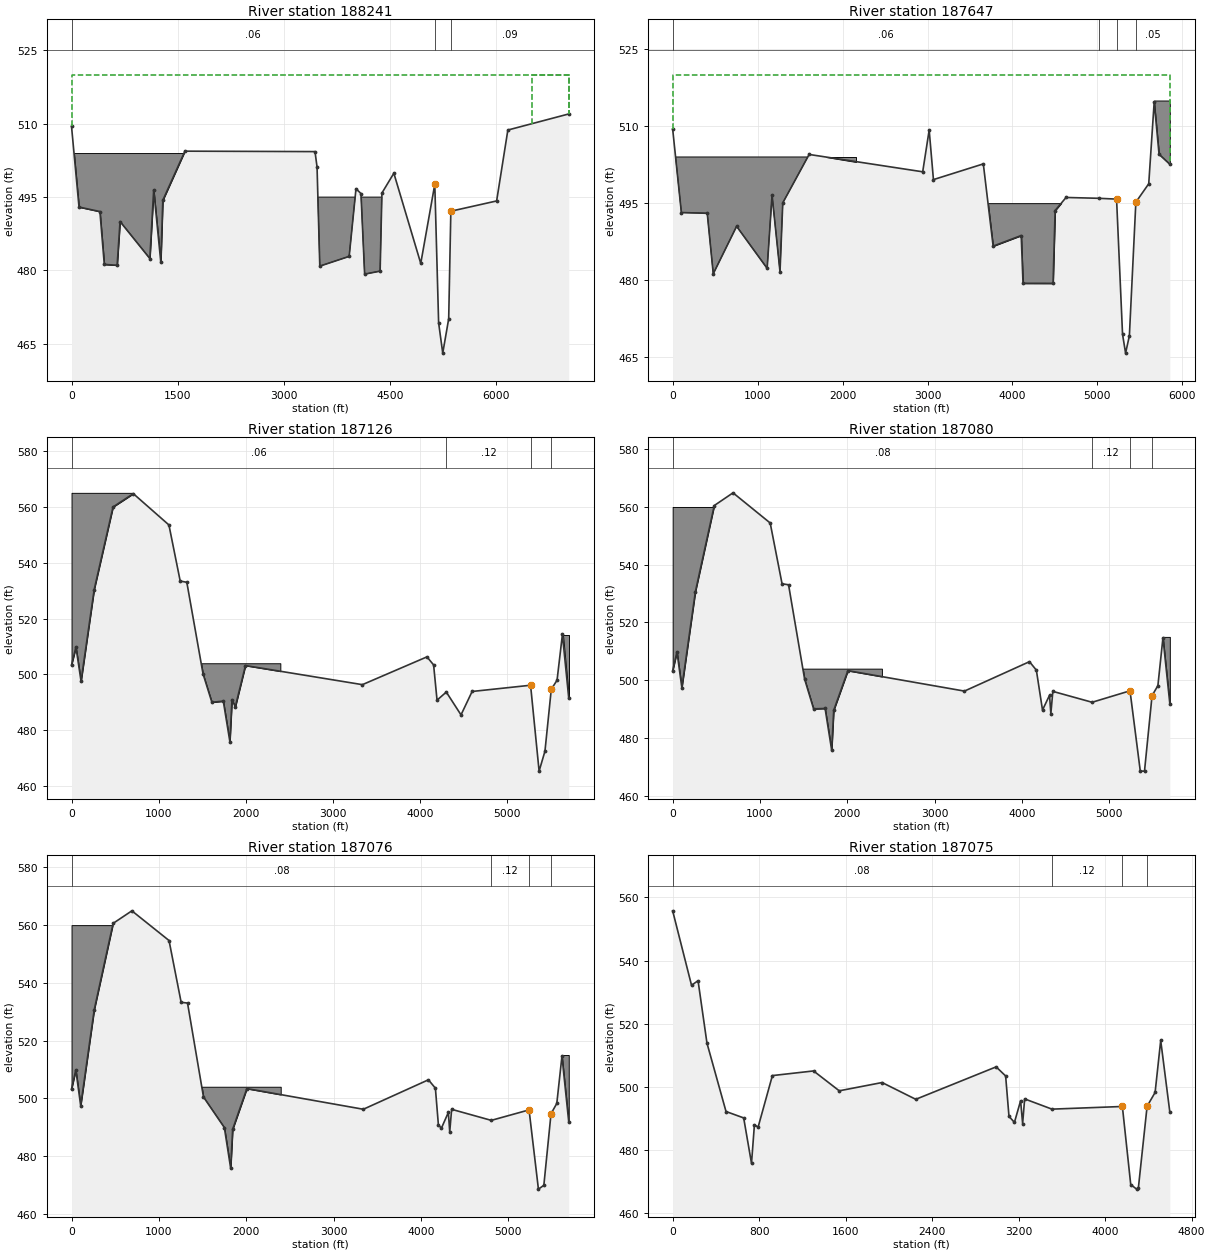
Type RM Length L Ch R = 1 ,188241  ,510,599,593
BEGIN DESCRIPTION:
This cross section corresponds to cross section 188241 of the non-georeferenced CDC model which was the source of this model.
END DESCRIPTION:
XS GIS Cut Line= 6
 2353581.7955356 6972484.7269168 2353595.8144979   6972480.72362
  2353971.235672 6970079.8026428 2354082.5483857 6969367.9295718
 2355596.2065314 6967255.89486392356522.372424766966403.34221972
#Sta/Elev= 30
       0  509.45     106  492.96  400.85  492.04  462.83  481.23  644.41  481.06
  685.35     490 1106.09  482.43 1160.58  496.49 1260.87   481.7 1289.47  494.35
  1601.1  504.39 3438.74   504.3 3467.57  501.17  3506.5  480.88 3921.21  482.87
 4017.81  496.72  4088.1  495.71 4139.76  479.24 4358.53  479.86  4383.9  495.83
 4552.26  499.88 4932.25  481.44 5130.54  497.61 5184.75  469.27 5242.88  463.09
 5326.84  470.11 5357.36  492.11 6003.91  494.21 6162.45  508.71 7022.45     512
#Mann= 3 ,-1,0
       0     .06       0 5130.54     .05       0 5357.36     .09       0
#XS Ineff= 2 , 0
               0     520 6501.45             520
Permanent Ineff=
       F       F
#Block Obstruct= 2 ,-1
       0    2087     504    3470    4606     495
Bank Sta=5130.54,5357.36
XS Rating Curve= 0 ,0
Exp/Cntr=0.3,0.1

Type RM Length L Ch R = 1 ,187647  ,569,518,549
BEGIN DESCRIPTION:
This cross section corresponds to cross section 187647 of the non-georeferenced CDC model which was the source of this model.
END DESCRIPTION:
XS GIS Cut Line= 5
 2353580.5039075 6972486.0831262 2353600.7024976 6972481.8284456
 2353982.4950238  6970040.160931  2356037.893289 6967639.7841515
 2356174.1682879 6967492.6854555
#Sta/Elev= 30
       0  509.46  102.74  493.17   407.1  493.03  478.08  481.25  753.03  490.49
 1112.37   482.3 1170.07  496.54 1263.72  481.65 1296.32  495.06 1606.63  504.49
 2943.26  501.11 3019.47  509.24 3069.56  499.59 3656.78  502.65 3772.41  486.63
 4102.78   488.7 4124.08  479.39 4477.81  479.38 4501.99  493.57 4630.64  496.11
 5014.72  495.95 5225.24  495.79 5295.56  469.46  5331.3  465.79 5376.07  469.17
 5452.24  495.19 5603.94  498.78 5667.98   514.7 5725.35  504.53 5852.64  502.57
#Mann= 4 ,-1,0
       0     .06       0 5014.72     .09       0 5225.24    .035       0
 5452.24     .05       0
#XS Ineff= 2 , 0
               0     520
Permanent Ineff=
       F       F
#Block Obstruct= 3 ,-1
       0    2159     504    3694    5111     495    5667    5852     515
Bank Sta=5225.24,5452.24
XS Rating Curve= 0 ,0
Exp/Cntr=0.3,0.1

Type RM Length L Ch R = 1 ,187126  ,43,43,43
BEGIN DESCRIPTION:
This cross section corresponds to cross section 187126 of the non-georeferenced CDC model which was the source of this model.
END DESCRIPTION:
XS GIS Cut Line= 6
 2355030.2006701 6973284.3490503 2355280.5893523 6970196.0734002
 2355522.6350467 6969272.7090083 2355505.8401202 6968946.4146536
 2356036.5789468 6968424.6031872 2356432.0792441  6967988.981145
#Sta/Elev= 30
       0  503.41   50.84  509.79  109.41   497.6  260.38  530.39  476.96  559.94
  709.88   564.7 1118.95   553.5 1248.57  533.42 1324.54  532.98 1511.29  500.15
 1612.46  490.04 1743.67  490.44 1819.25  475.95 1843.53  490.99 1881.54  488.39
 1998.17  503.18 3341.56  496.34  4083.6  506.29 4159.82   503.4 4199.24  490.79
  4305.7  493.69  4474.6  485.52 4602.23   493.9 5273.85  496.13 5371.85  465.39
 5439.07  472.53 5511.69  494.67 5578.13  497.94 5639.62  514.31 5712.37  491.52
#Mann= 4 ,-1,0
       0     .06       0  4305.7     .12       0 5273.85    .035       0
 5511.69     .08       0
#Block Obstruct= 3 ,-1
       0     704     565     704    2399     504    5639    5712     514
Bank Sta=5273.85,5511.69
XS Rating Curve= 0 ,0
Exp/Cntr=0.3,0.1

Type RM Length L Ch R = 1 ,187080  ,4,4,4
BEGIN DESCRIPTION:
This cross section corresponds to cross section 187080 of the non-georeferenced CDC model which was the source of this model.
END DESCRIPTION:
XS GIS Cut Line= 6
  2355034.187587 6973284.6722984 2355284.5478373  6970196.747333
 2355526.6616585 6969273.1230483 2355513.3928139  6969015.339526
 2356035.0545063 6968495.8877612 2356466.7776305 6968014.9053763
#Sta/Elev= 30
       0  503.24   49.53  509.82  105.24  497.43  260.12  530.62  476.48  560.48
  691.35  564.89 1116.93  554.44 1252.75  533.39 1327.21  533.04 1511.03  500.37
 1613.98  490.07 1745.62   490.2 1820.96  475.76 1844.45  489.57  2006.8   503.3
 3341.13  496.22 4085.83  506.41 4164.83  503.47 4235.12  489.66 4315.64  494.78
 4330.75  488.38  4353.4  496.12 4803.16  492.35 5237.14  496.32 5354.82   468.5
 5403.08   468.5 5489.58  494.65  5556.4  498.11 5614.38  514.71 5693.55  491.76
#Mann= 4 ,-1,0
       0     .08       0 4803.16     .12       0 5237.14    .035       0
 5489.58     .05       0
#Block Obstruct= 3 ,-1
       0     516     560     516    2396     504    5614    5693     515
Bank Sta=5237.14,5489.58
XS Rating Curve= 0 ,0
Exp/Cntr=0.3,0.1

Type RM Length L Ch R = 1 ,187076  ,1,1,1
BEGIN DESCRIPTION:
This cross section corresponds to cross section 187076 of the non-georeferenced CDC model which was the source of this model.
END DESCRIPTION:
XS GIS Cut Line= 6
  2355035.184316 6973284.7531104 2355285.5374585 6970196.9158162
 2355527.6683105 6969273.2265619 2355514.4145365 6969015.7359138
 2356038.0448299 6968498.5444441 2356469.6945313 6968017.6424713
#Sta/Elev= 30
       0   503.2   49.21  509.83  104.83  497.43  260.06  530.68  476.36  560.62
  691.03  564.96 1116.42  554.67 1255.07  533.25 1328.19     533 1510.97  500.43
 1749.73  489.85 1822.09  475.76 1845.08  489.26 2007.47  503.35 3341.02  496.19
 4086.21   506.4 4166.09  503.49 4200.56  490.74  4235.2  489.65 4314.54   495.1
 4330.31  488.39  4352.1  496.17 4805.91  492.34 5238.52  495.97 5345.77  468.51
 5407.83  469.83 5490.04  494.64  5556.1  498.21 5615.22   514.6 5692.93  491.83
#Mann= 4 ,-1,0
       0     .08       0 4805.91     .12       0 5238.52    .035       0
 5490.04     .05       0
#Block Obstruct= 3 ,-1
       0     740     560     740    2395     504    5615 5692.93     515
Bank Sta=5238.52,5490.04
XS Rating Curve= 0 ,0
Exp/Cntr=0.3,0.1

Type RM Length L Ch R = 1 ,187075  ,43,43,43
BEGIN DESCRIPTION:
This cross section corresponds to cross section 187075 of the non-georeferenced CDC model which was the source of this model.
END DESCRIPTION:
XS GIS Cut Line= 6
  2355039.171234 6973285.0763584 2355289.4959434  6970197.589749
 2355531.6949215 6969273.6406049 2355518.5014268 6969017.3214648
 2356038.8417115 6968499.1848483 2356470.4237565 6968018.3267451
#Sta/Elev= 30
       0  555.77  174.51  532.21  234.91  533.65  317.32   513.9  493.54  492.25
  656.89  490.22  729.26  475.85   756.2  488.05  790.39   487.3  922.41  503.62
 1303.07  505.09 1540.76   498.8  1936.9  501.42 2248.44  496.11 2991.78  506.38
 3079.52   503.5 3110.52   490.7 3160.91  488.81 3217.99  495.65 3236.73  488.42
 3255.28  496.24    3508     493 4159.15  493.84 4236.47  469.14 4290.62  467.68
 4307.57  468.18 4387.91  493.91 4461.84  498.28 4513.72  514.73 4598.45  491.96
#Mann= 4 ,-1,0
       0     .08       0    3508     .12       0 4159.15    .035       0
 4387.91    .065       0
#Block Obstruct= 2 , 0
            1303     504    4513             514
Bank Sta=4159.15,4387.91
XS Rating Curve= 0 ,0
Exp/Cntr=0.3,0.1

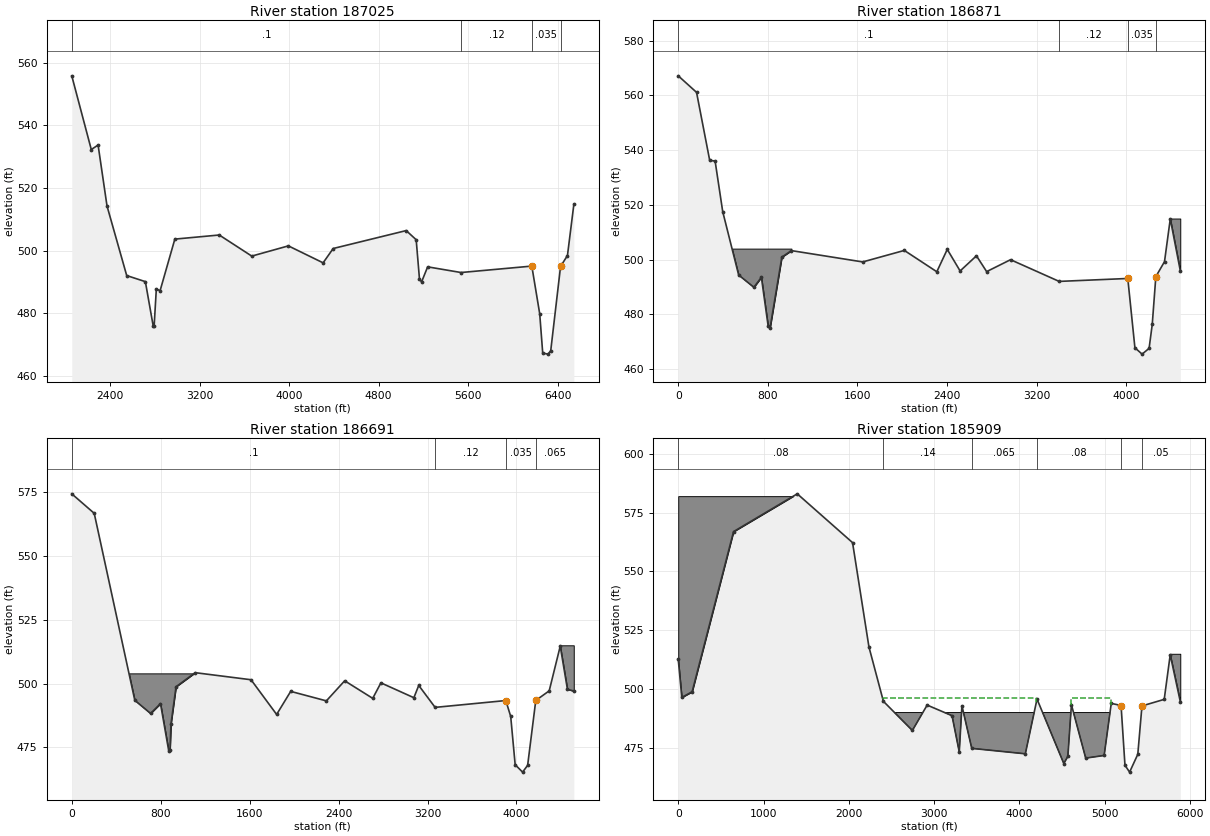
Type RM Length L Ch R = 1 ,187025  ,176,178,178
BEGIN DESCRIPTION:
This cross section corresponds to cross section 187025 of the non-georeferenced CDC model which was the source of this model.
END DESCRIPTION:
XS GIS Cut Line= 6
  2355201.526031 6972215.7832028      2355279.36      6971122.88
      2355344.47      6970208.64      2355588.63      6969297.12
      2355569.64      6969055.67  2356449.925915 6968110.2180641
#Sta/Elev= 30
    2056  555.76 2230.47  532.24 2291.39  533.68 2371.23  514.22 2547.28  492.03
 2714.14  490.09 2784.76  475.83 2792.64  475.94 2812.17  487.74 2845.76  487.19
 2977.72  503.66  3374.9  504.97 3665.66  498.24    3993   501.5 4303.61  496.09
 4393.71  500.66 5046.75  506.38 5135.99  503.46 5165.48   490.9 5184.14     490
  5238.5  494.81    5537     493 6170.02  495.05  6240.6  479.85 6267.54   467.3
  6314.8  466.96 6339.24  468.06  6427.1  494.93  6488.7  498.42 6545.89  514.71
#Mann= 4 ,-1,0
    2056      .1       0    5537     .12       0 6170.02    .035       0
  6427.1    .065       0
#Block Obstruct= 2 , 0
            3361     504
Bank Sta=6170.02,6427.1
XS Rating Curve= 0 ,0
Exp/Cntr=0.3,0.1

Type RM Length L Ch R = 1 ,186871  ,199,203,207
BEGIN DESCRIPTION:
This cross section corresponds to cross section 186871 of the non-georeferenced CDC model which was the source of this model.
END DESCRIPTION:
XS GIS Cut Line= 6
  2355291.337509 6972284.4097219  2355368.410033 6971345.3615282
 2355460.4239571 6970224.2679699 2355705.2154622 6969308.0352223
 2355696.9690877 6969133.9899667 2356606.2966653 6968216.7076806
#Sta/Elev= 30
       0  567.19  163.41  561.15   280.8  536.28  329.12  536.01  397.01  517.52
  539.14  494.35  674.96  489.85  742.19   493.5  802.67  475.63  819.61  474.99
  924.84  500.89 1010.44  503.26 1646.52  499.12 2018.03  503.33 2307.97  495.53
 2401.24  503.71 2515.92  495.82 2661.76  501.36 2752.78  495.58 2966.05  499.94
    3400     492  4012.5  493.07 4076.07  467.73    4140   465.4 4202.74  467.51
 4230.74  476.24 4262.89  493.74 4340.25  499.23 4391.71  514.86  4481.3  495.89
#Mann= 4 ,-1,0
       0      .1       0    3400     .12       0  4012.5    .035       0
 4262.89     .06       0
#Block Obstruct= 2 ,-1
     476    1010     504    4391    4481     515
Bank Sta=4012.5,4262.89
XS Rating Curve= 0 ,0
Exp/Cntr=0.3,0.1

Type RM Length L Ch R = 1 ,186691  ,891,742,673
BEGIN DESCRIPTION:
This cross section corresponds to cross section 186691of the non-georeferenced CDC model which was the source of this model.
END DESCRIPTION:
XS GIS Cut Line= 6
   2355757.17558 6972283.8549662     2355775.952     6971293.699
     2355795.483     6970263.751     2356081.942     6969220.782
 2356631.1696476 6968453.2608311  2356904.680669 6968071.0413639
#Sta/Elev= 30
       0  574.35  201.97  566.71  566.98  493.44  708.77  488.29  797.94  492.16
  871.79  473.73  883.72  474.02  892.38  484.18  937.86  498.76 1110.26  504.27
 1612.38   501.5 1842.68   487.9 1969.13  496.94 2289.95  493.22 2454.63  501.09
 2706.86  494.21 2780.51  500.28 3076.98  494.46 3120.84  499.27 3268.03  490.67
 3903.97  493.35 3947.96  487.11 3988.07   468.2    4055   465.3 4100.25  467.97
 4173.45  493.38 4294.17  497.15 4393.54  514.67 4458.17  497.75 4515.85  497.08
#Mann= 4 ,-1,0
       0      .1       0 3268.03     .12       0 3903.97    .035       0
 4173.45    .065       0
#Block Obstruct= 2 ,-1
     497    1118     504    4393    4515     515
Bank Sta=3903.97,4173.45
XS Rating Curve= 0 ,0
Exp/Cntr=0.3,0.1

Type RM Length L Ch R = 1 ,185909  ,521,521,521
BEGIN DESCRIPTION:
This cross section corresponds to cross section 118732 of the non-georeferenced CDC model which was the source of this model.
END DESCRIPTION:
XS GIS Cut Line= 3
  2356668.949034 6974083.7043535 2356734.6034293 6970039.7026307
 2357403.7955759 6968451.8970062
#Sta/Elev= 30
       0  512.68    41.7  496.44  162.98  498.85  648.47  566.92 1395.66  582.99
 2044.07  562.24 2236.28  517.89 2405.72  494.78 2745.42  482.39 2918.87  493.18
 3210.55  488.67 3295.37  473.26 3326.57  492.91 3441.88  474.78 4070.08  472.47
 4207.08  495.74 4521.23  468.33 4568.79  471.36 4610.48  493.34 4778.03  470.64
 4994.26  471.77 5077.71  493.91 5192.58     493 5238.41   467.6 5292.67  464.68
 5388.76  472.25 5437.64  492.82 5698.67  495.61 5768.94  514.56 5887.35  494.64
#Mann= 6 ,-1,0
       0     .08       0 2405.72     .14       0 3441.88    .065       0
 4207.08     .08       0 5192.58    .035       0 5437.64     .05       0
#XS Ineff= 2 ,-1
    2400    4200     496    4610    5072     496
Permanent Ineff=
       T       T
#Block Obstruct= 3 ,-1
       0    1374     582    2340    5134     490    5769    5887     515
Bank Sta=5192.58,5437.64
XS Rating Curve= 0 ,0
Exp/Cntr=0.3,0.1