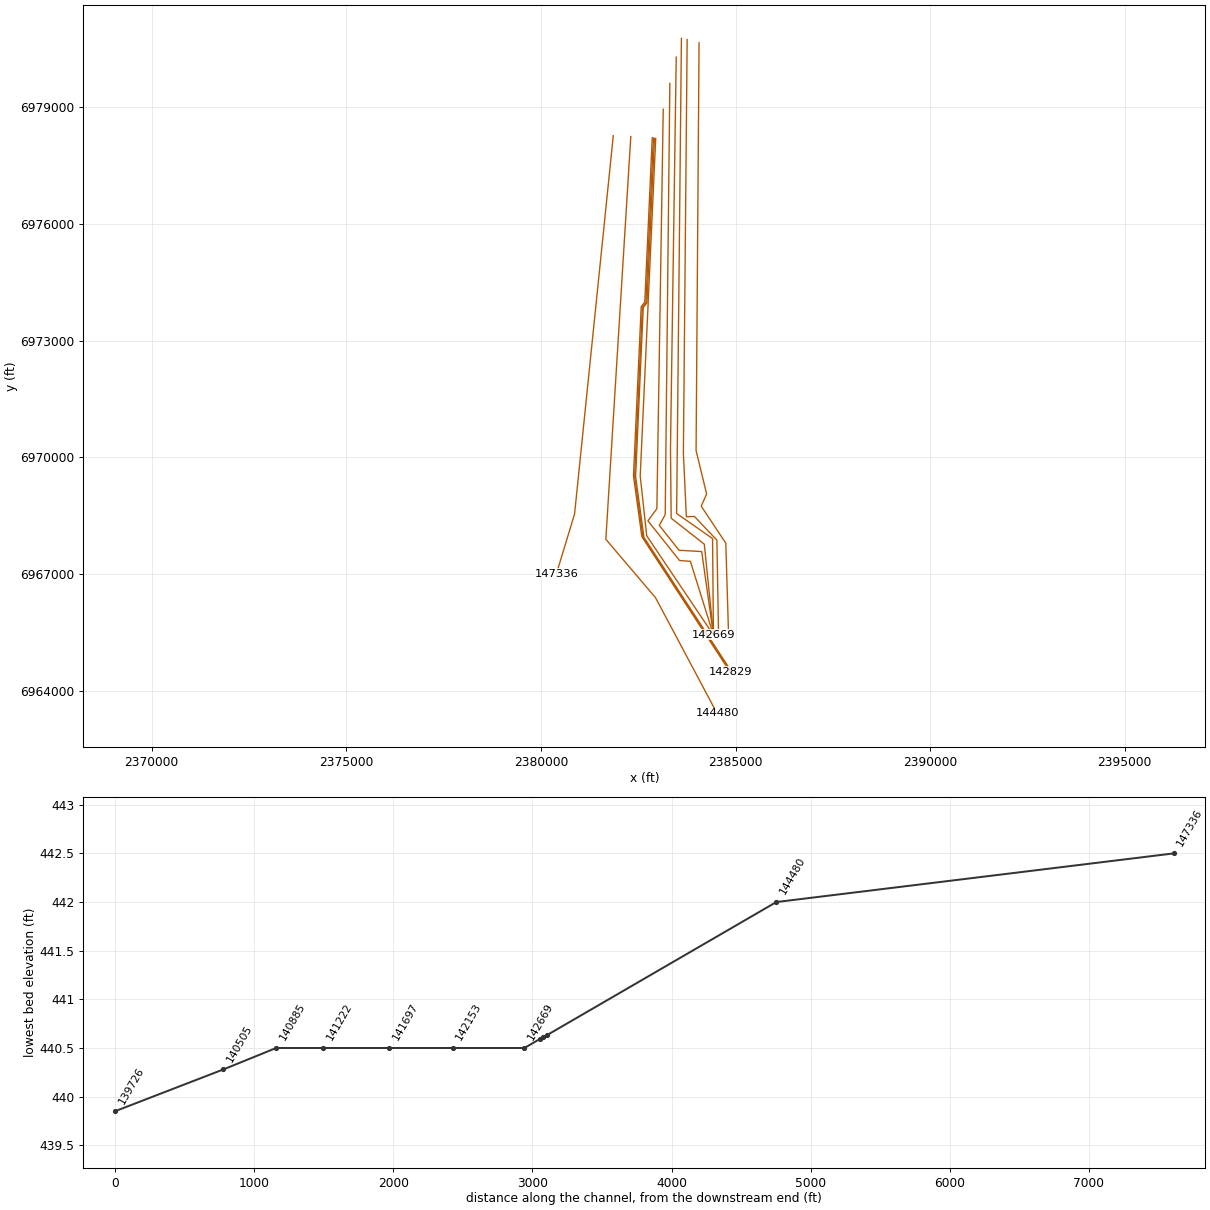
HEC-RAS study CDC_Consolidated_Model.prj: Upper Trinity CDC Consolidated Model

--- CDC_Consolidated_Model.g13 (geometry) --- (continued)

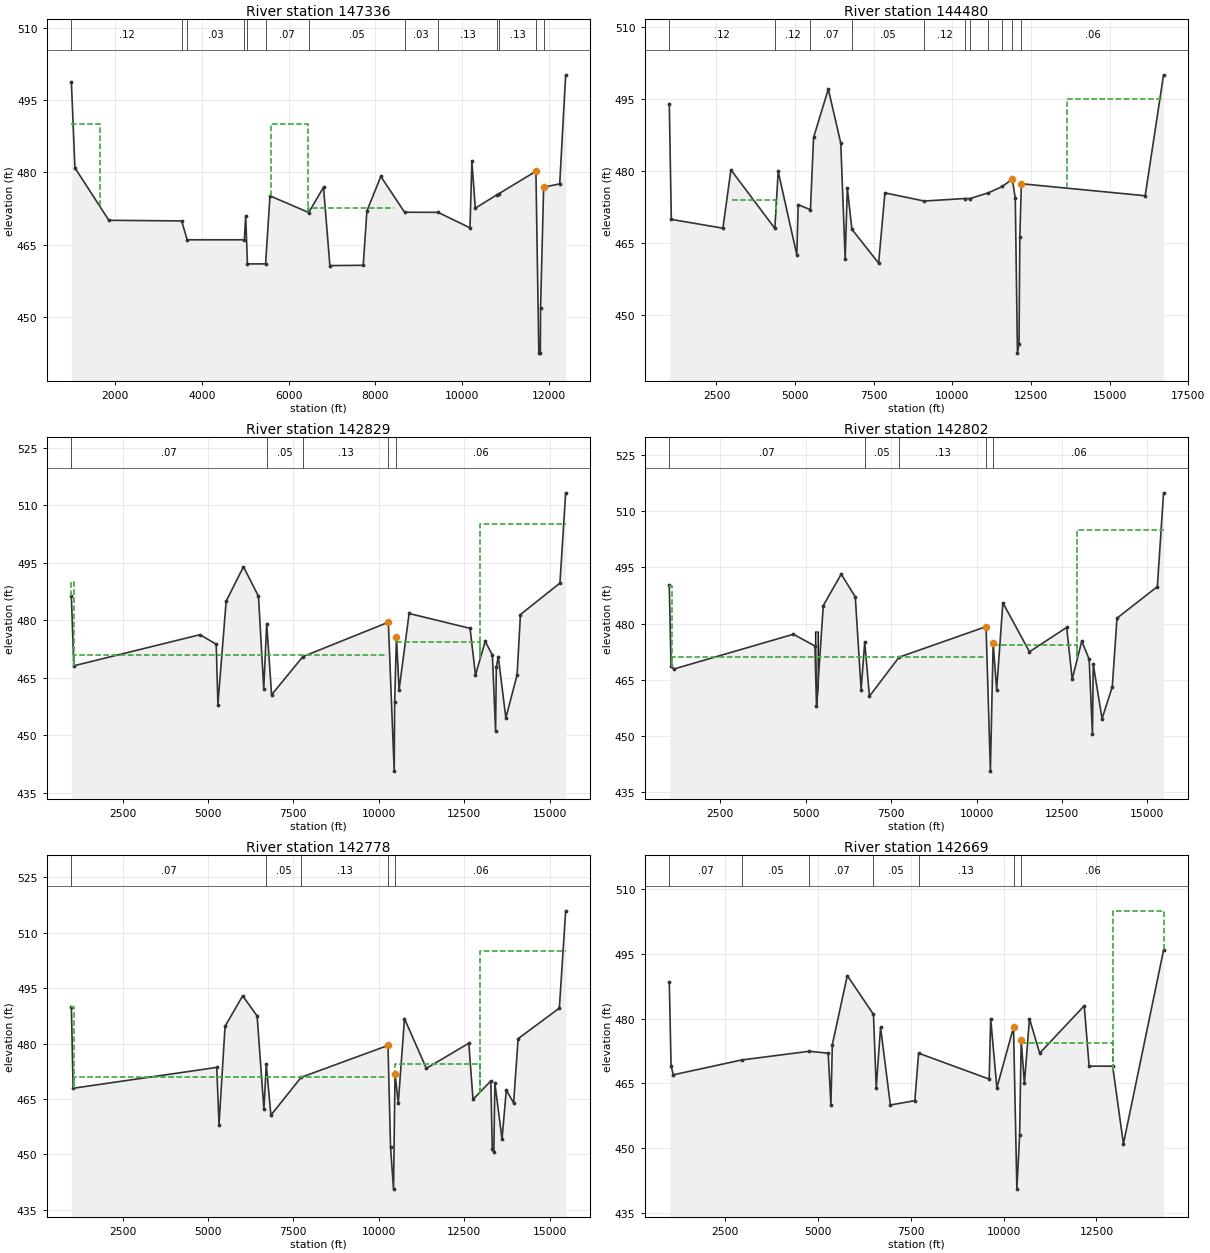
Type RM Length L Ch R = 1 ,147336  ,724,2856,2794
BEGIN DESCRIPTION:
147336 Revised w/ 2014 DAS, 2009 TNRIS, and Proposed Grading
THIS SECTION WAS COPIED FROM 1475+12 AND IT MODELS THE AREA 10'  DOWNSTREAM OF THE BLOCKED OBSTRUCTION
---------------------------------------------------------------------
CDC FW122804-01 Gas Well Duck Lake No.1
Located in LOB.
Cross-sections 147336 - 147496
---------------------------------------------------------------------
END DESCRIPTION:
XS GIS Cut Line= 3
       2381859.3      6978272.91       2380864.8      6968545.85
      2380399.76      6967012.49
#Sta/Elev= 30
    1000   498.7  1081.7  480.91 1862.86  470.04 3538.38  469.91 3665.17     466
 4981.78     466 5012.12     471 5052.58     461 5470.33     461 5571.45  475.11
 6463.29  471.65 6804.14  476.89 6950.59  460.65 7717.98  460.71 7802.81  471.99
 8123.19  479.14 8669.39  471.71 9439.14  471.6910175.42  468.4810219.33  482.24
10297.78  472.5510798.19  475.3510840.44  475.56   11693   480.2   11760   442.5
   11795   442.5   11800   451.8   11871   476.9   12241   477.6   12378   500.2
#Mann= 13 ,-1,0
    1000     .12       0 3538.38     .05       0 3665.17     .03       0
 4981.78     .08       0 5052.58     .03       0 5470.33     .07       0
 6463.29     .05       0 8669.39     .03       0 9439.14     .13       0
10798.19    .035       010840.44     .13       0   11693    .055       0
   11871     .13       0
#XS Ineff= 5 ,-1
    1000    1650     490    5600    6450     490    6450    8424   472.5
    842411695.79   472.5   11871   12378   476.9
Permanent Ineff=
       F       F       F       T       F
Bank Sta=11693,11871
XS Rating Curve= 0 ,0
Exp/Cntr=0.3,0.1

Type RM Length L Ch R = 1 ,144480  ,675,1651,590
BEGIN DESCRIPTION:
144480 Revised w/ 2014 DAS, 2009 TNRIS, and Proposed Grading
---------------------------------------------------------------------
CDC FW 040717-01 Trinity Lakes
Project in LOB.
Cross-section 144480 - 154445
---------------------------------------------------------------------
END DESCRIPTION:
XS GIS Cut Line= 5
   2382309.22295   6978250.58689   2381668.19011    6967894.5889
   2382944.88999   6966391.44886 2383077.2418921 6966142.4064883
2384525.465736686963417.32966443
#Sta/Elev= 30
    1000  493.93 1064.78  469.87 2705.14  468.04 2959.79   480.2 4356.04     468
 4462.57  479.87 5054.31   462.5 5098.81  472.93  5488.1  471.89 5587.84  486.94
 6056.02  497.02 6452.26  485.78 6592.65  461.64 6660.83  476.42 6806.72  467.81
 7656.64  460.76 7855.87   475.4 9104.78   473.710403.14  474.2210564.55  474.21
11140.39   475.411594.03  476.74   11906   478.3   12001   474.3   12070     442
   12120     444   12146   466.3   12195   477.3   16131   474.8   16716     500
#Mann= 11 ,-1,0
    1000     .12       0 4356.04     .12       0  5488.1     .07       0
 6806.72     .05       0 9104.78     .12       010403.14     .08       0
10564.55     .12       011140.39    .035       011594.03     .12       0
   11906     .05       0   12195     .06       0
#XS Ineff= 6 ,-1
    1000    3000   472.4    3000 4382.72     474    6500    7881   472.4
    7881   10260   472.4   12195   13630   475.3   13630   16716     495
Permanent Ineff=
       F       T       F       T       F       T
#Block Obstruct= 1 ,-1
 5015.26 5134.95   462.5
Bank Sta=11906,12195
XS Rating Curve= 0 ,0
Exp/Cntr=0.3,0.1

Type RM Length L Ch R = 1 ,142829  ,27,27,27
XS GIS Cut Line= 6
     2382860.835     6978223.473     2382668.216     6973992.727
      2382576.63     6973877.436      2382378.25     6969527.506
     2382593.053     6967962.481     2384861.041     6964481.326
#Sta/Elev= 30
    1003  486.16    1074  468.09 4767.74   476.2 5242.68  473.72 5292.19     458
 5533.21  484.92 6040.09  493.93 6479.99   486.2 6633.95  462.09 6719.93  479.11
  6863.9  460.52 7778.68  470.4810280.86  479.45 10452.7  440.6310466.69  458.77
10518.64  475.7110595.57  461.8210889.31  481.7312672.92  477.8612831.92  465.71
13116.92  474.4613326.92  470.8613419.92  451.0913441.92  467.6913498.92   470.5
13720.92   454.514049.92  465.7114147.92  481.4615303.92  489.6515471.92  513.19
#Mann= 5 ,-1,0
    1003     .07       0 6719.93     .05       0 7778.68     .13       0
10280.86    .055       010518.64     .06       0
#XS Ineff= 4 ,-1
    1003    1080     490    1080   10256     47110518.6412974.92   474.4
12974.92   15471     505
Permanent Ineff=
       F       F       F       T
Bank Sta=10280.86,10518.64
XS Rating Curve= 0 ,0
Exp/Cntr=0.3,0.1

Type RM Length L Ch R = 1 ,142802  ,24,24,24
BEGIN DESCRIPTION:
Created with Pecos 2019 LiDAR
CDC FW 053222-1 Trinity Trails East Phase 2
Added cross-section.
Project located in LOB.
Walker Branch culvert blocked obstruction.
END DESCRIPTION:
XS GIS Cut Line= 6
     2382890.127     6978210.016     2382697.215      6973976.85
     2382606.726     6973863.033     2382407.496     6969513.936
     2382622.406     6967946.886     2384890.304     6964467.632
#Sta/Elev= 30
    1003  490.15    1055  468.65 1132.99  467.85 4636.75  477.14 5266.37     474
 5312.28     458 5511.21  484.81 6036.09  493.18 6447.99  487.11 6617.95  462.39
 6723.93  474.99  6861.9   460.6 7728.69  471.0110275.86  479.1710402.77  440.61
10483.67  474.7710585.58  462.3710768.42  485.5311546.92  472.4612635.92  478.96
12796.92  465.1513076.92   475.313293.92  470.4613389.92   450.413412.92  469.13
13670.92  454.6113970.92  463.1214107.92  481.4215289.92  489.8515471.92  514.88
#Mann= 5 ,-1,0
    1003     .07       0 6723.93     .05       0 7728.69     .13       0
10275.86    .055       010483.67     .06       0
#XS Ineff= 4 ,-1
    1003    1080     490    1080   10256     47110483.67   12950   474.4
   12950   15471     505
Permanent Ineff=
       F       F       F       T
#Block Obstruct= 1 ,-1
 5264.79 5359.07   477.9
Bank Sta=10275.86,10483.67
XS Rating Curve= 0 ,0
Exp/Cntr=0.3,0.1

Type RM Length L Ch R = 1 ,142778  ,34,109,119
BEGIN DESCRIPTION:
Created with Pecos 2019 LiDAR
CDC FW 053222-1 Trinity Trails East Phase 2
Added cross-section.
Project located in LOB.
END DESCRIPTION:
XS GIS Cut Line= 6
     2382916.972     6978202.973     2382723.879     6973973.721
     2382629.756     6973858.683     2382432.919     6969508.515
     2382646.968     6967942.121     2384915.333     6964462.304
#Sta/Elev= 30
    1003  489.94    1054   467.9 5258.63  473.54 5324.73     458 5501.21  484.66
 6017.09  492.92    6440  487.48 6638.95  462.15 6707.93  474.38  6842.9   460.6
 7728.69  470.8610270.87  479.49 10345.8  451.8910432.72  440.5910476.68  471.75
10572.59  463.9310753.43  486.7511393.92  473.2912636.92  480.0912758.92  464.88
13280.92  469.8713323.92  451.3413369.92  450.6113398.92  469.3313608.92  454.13
13733.92  467.4113947.92  463.9314079.92  481.3215286.92  489.5915471.92  515.93
#Mann= 5 ,-1,0
    1003     .07       0 6707.93     .05       0 7728.69     .13       0
10270.87    .055       010476.68     .06       0
#XS Ineff= 4 ,-1
    1003    1080     490    1080   10256     47110483.67   12950   474.4
   12950   15471     505
Permanent Ineff=
       F       F       F       T
Bank Sta=10270.87,10476.68
XS Rating Curve= 0 ,0
Exp/Cntr=0.3,0.1

Type RM Length L Ch R = 1 ,142669  ,260,515,390
BEGIN DESCRIPTION:
Kimley-Horn updated cross section based on on-ground survey and proposed grading for Bell South Airfiled property and TNRIS 2009 LiDAR offsite. Channel flowline interpolated from effective model. (KH, 2017)
END DESCRIPTION:
XS GIS Cut Line= 4
  2382949.248654 6978203.3749724   2382551.17916   6969520.17915
   2382718.62994   6967983.55887 2384427.4746787  6965440.382665
#Sta/Elev= 30
    1000  488.45 1048.76     469 1111.52     467 2945.53  470.43 4767.68  472.45
 5278.52     472 5351.22     460 5389.59     474 5792.04     490 6496.68     481
 6570.56     464 6687.95     478  6951.7     460 7610.62     461 7712.13     472
 9612.55     466 9651.83     480 9819.04     46410267.05     47810357.44   440.5
10431.29     45310473.41     47510560.01     46510696.64     48010971.06     472
12170.83     483 12302.3     46912935.48     469 13225.2     45114306.44  495.89
#Mann= 7 ,-1,0
    1000     .07       0 2945.53     .05       0 4767.68     .07       0
 6496.68     .05       0 7712.13     .13       010267.05    .055       0
10473.41     .06       0
#XS Ineff= 3 ,-1
    1003   10256     471   10476   12950   474.4   12950   14305     505
Permanent Ineff=
       F       F       T
Bank Sta=10267.05,10473.41
XS Rating Curve= 0 ,0
Exp/Cntr=0.3,0.1

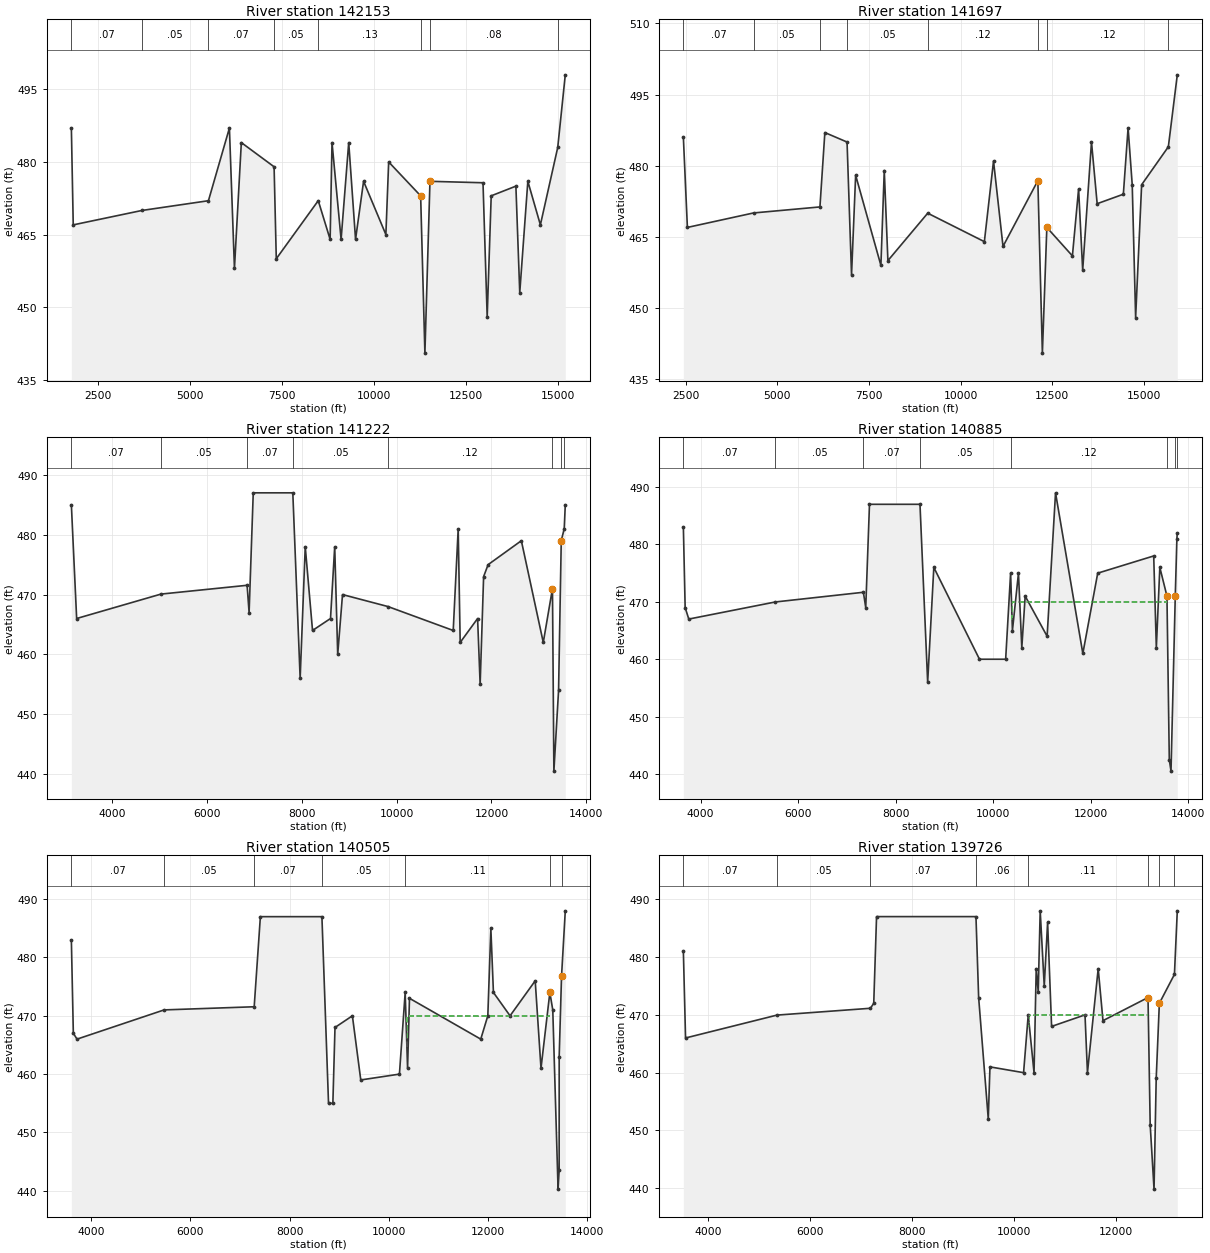
Type RM Length L Ch R = 1 ,142153  ,230,456,345
BEGIN DESCRIPTION:
Kimley-Horn added cross section based on on-ground survey and proposed grading for Bell South Airfiled property and TNRIS 2009 LiDAR offsite. Channel flowline interpolated from effective model. (KH, 2017)
END DESCRIPTION:
XS GIS Cut Line= 6
  2383142.643237 6978953.6116956 2382978.9424269 6968681.1869271
 2382749.7757602  6968368.686927 2383562.2757602 6967347.8535937
  2383840.053538 6967327.0202604  2384421.303538 6965467.2980382
#Sta/Elev= 30
 1770.48     487 1821.49     467 3690.09  469.98 5494.21  471.99 6063.64     487
 6200.66     458 6387.61     484 7277.65     479  7337.2     460 8477.28     472
 8799.83     464 8851.17     484 9097.85     464 9304.97     484 9490.45     464
 9708.37     47610314.04     46510390.07     48011258.63     47311374.28   440.5
11511.95     47612952.52   475.713066.21     44813175.38     47313846.03     475
13950.86     45314170.53     47614511.35     46714982.61     48315187.77     498
#Mann= 8 ,-1,0
 1770.48     .07       0 3690.09     .05       0 5494.21     .07       0
 7277.65     .05       0 8477.28     .13       011258.63    .055       0
11511.95     .08       014982.61     .03       0
#XS Ineff= 2 ,-1
 7277.65 8477.28     460 8477.2811258.63     470
Permanent Ineff=
       T       T
Bank Sta=11258.63,11511.95
XS Rating Curve= 0 ,0
Exp/Cntr=0.3,0.1

Type RM Length L Ch R = 1 ,141697  ,240,476,360
BEGIN DESCRIPTION:
Kimley-Horn added cross section based on on-ground survey and proposed grading for Bell South Airfiled property and TNRIS 2009 LiDAR offsite. Channel flowline interpolated from effective model. (KH, 2017)
END DESCRIPTION:
XS GIS Cut Line= 6
   2383312.15638 6979616.4345848 2383193.5221208 6968529.1950015
  2383040.744343 6968251.4172237 2383547.6887875 6967612.5283348
 2384131.0221208 6967577.8061126 2384423.8461949 6965498.4513672
#Sta/Elev= 30
 2436.18     486 2545.87     467 4349.06  470.05 6160.72  471.32 6294.96     487
 6900.34     485 7022.49     457 7134.56     478 7823.23     459 7915.36     479
  8014.3     460 9100.18     47010645.12     464 10894.9     48111153.71     463
12103.83  476.8612227.23   440.512348.91     46713046.18     46113214.91   475.1
13326.49     45813566.67     48513721.41     47214435.69     47414564.93     488
14677.57     47614770.51     44814934.16     47615662.78     48415906.67  499.17
#Mann= 8 ,-1,0
 2436.18     .07       0 4349.06     .05       0 6160.72     .07       0
 6900.34     .05       0 9100.18     .12       012103.83    .055       0
12348.91     .12       015662.78     .03       0
#XS Ineff= 2 ,-1
 6900.34 9100.18     460 9100.1812103.83     470
Permanent Ineff=
       T       T
Bank Sta=12103.83,12348.91
XS Rating Curve= 0 ,0
Exp/Cntr=0.3,0.1

Type RM Length L Ch R = 1 ,141222  ,170,337,255
BEGIN DESCRIPTION:
Kimley-Horn added cross section based on on-ground survey and proposed grading for Bell South Airfiled property and TNRIS 2009 LiDAR offsite. Channel flowline interpolated from effective model. (KH, 2017)
END DESCRIPTION:
XS GIS Cut Line= 5
  2383476.508231 6980294.8200015 2383328.9387875  6970225.375557
 2383346.2998986 6968437.1811126  2384196.994343 6967768.7783348
 2384422.3270977 6965566.7384043
#Sta/Elev= 30
 3145.85     485 3257.36     466  5034.6  470.08 6850.44  471.55 6892.37     467
 6979.92     487 7813.85     487 7968.58     456 8075.82     478 8229.43     464
 8608.65     466 8697.14     478 8760.27     460 8861.56     470 9819.54     468
11195.33     46411300.06     48111342.01     46211709.12     46611762.71     455
11835.99     47311930.81     47512631.34     47913093.61     46213287.23     471
13317.22   440.513416.01     45413472.58     47913535.13     481 13557.5     485
#Mann= 8 ,-1,0
 3145.85     .07       0  5034.6     .05       0 6850.44     .07       0
 7813.85     .05       0 9819.54     .12       013287.23    .055       0
13472.58     .12       013535.13     .03       0
#XS Ineff= 2 ,-1
 6979.92 8638.16     460 8638.1613287.23     470
Permanent Ineff=
       T       T
Bank Sta=13287.23,13472.58
XS Rating Curve= 0 ,0
Exp/Cntr=0.3,0.1

Type RM Length L Ch R = 1 ,140885  ,165,379,340
BEGIN DESCRIPTION:
Kimley-Horn updated cross section based on on-ground survey and proposed grading for Bell South Airfiled property and TNRIS 2009 LiDAR offsite. Channel flowline interpolated from effective model. (KH, 2017)
---------------------------------------------------------------------
CDC FW121505-1 Bell Station Tract
This project is located between cross-sections 140885 - 147512 and within ineffective flow area, therefore the model was not changed.
--------------------------------------------------------------
END DESCRIPTION:
XS GIS Cut Line= 4
  2383609.827097 6980776.8078487 2383486.5632088 6968558.0578487
 2384410.1743199 6967912.2245154 2384431.0944588 6965555.6272932
#Sta/Elev= 30
  3646.1     483 3682.73     469 3757.21     467 5532.29  469.98 7338.33  471.67
 7386.67     469 7463.42     487 8499.08     487 8656.65     456    8783     476
  9719.5     46010256.42     46010357.87     47510395.18     46510518.99     475
10587.28     46210656.76     47111106.81     46411279.43     48911839.29     461
12144.56     47513292.97     47813346.82     46213418.45     47613564.49     471
13612.74   442.513647.74   440.513735.16     47113768.16     48113776.58     482
#Mann= 8 ,-1,0
  3646.1     .07       0 5532.29     .05       0 7338.33     .07       0
 8499.08     .05       010357.87     .12       013564.49    .055       0
13735.16    .055       013768.16     .03       0
#XS Ineff= 2 ,-1
 8499.0810388.48     46010388.4813564.49     470
Permanent Ineff=
       T       T
Bank Sta=13564.49,13735.16
XS Rating Curve= 0 ,0
Exp/Cntr=0.3,0.1

Type RM Length L Ch R = 1 ,140505  ,338,779,698
BEGIN DESCRIPTION:
Kimley-Horn added cross section based on on-ground survey and proposed grading for Bell South Airfiled property and TNRIS 2009 LiDAR offsite. Channel flowline interpolated from effective model. (KH, 2017)
END DESCRIPTION:
XS GIS Cut Line= 6
  2383757.396542 6980745.5578487 2383660.1743199 6970099.7245154
 2383736.5632088 6968474.7245154 2383944.8965421 6968481.6689598
  2384521.285431 6967870.5578487 2384562.9520977 6965502.5022931
#Sta/Elev= 30
 3604.66     483 3644.51     467 3718.86     466 5473.15  471.01 7288.47  471.55
 7413.02     487 8653.04     487 8786.16     455 8873.63     455 8916.51     468
 9266.83     470 9435.89     45910214.73     46010330.63     47410378.93     461
10417.27     47311853.41     46611995.76     47012056.79     48512108.75     474
12443.69     47012950.43     47613067.23     46113245.69     47413304.59     471
13411.19  440.2813432.96  443.53 13433.7     46313480.81  476.7513556.58     488
#Mann= 7 ,-1,0
 3604.66     .07       0 5473.15     .05       0 7288.47     .07       0
 8653.04     .05       010330.63     .11       013245.69    .055       0
13480.81     .03       0
#XS Ineff= 2 ,-1
 8653.0410365.31     46010365.3113245.69     470
Permanent Ineff=
       T       T
Bank Sta=13245.69,13480.81
XS Rating Curve= 0 ,0
Exp/Cntr=0.3,0.1

Type RM Length L Ch R = 1 ,139726  ,191,439,394
BEGIN DESCRIPTION:
Kimley-Horn added cross section based on on-ground survey and proposed grading for Bell South Airfiled property and TNRIS 2009 LiDAR offsite. Channel flowline interpolated from effective model. (KH, 2017)
END DESCRIPTION:
XS GIS Cut Line= 6
  2384062.952097 6980662.2245154 2383986.5632088 6970176.1134042
 2384257.3965421 6969058.0578487 2384118.5076532 6968745.5578487
 2384750.4520977 6967794.1689598 2384819.8965422 6965467.7800709
#Sta/Elev= 30
 3522.11     481 3564.86     466  5355.7  469.96 7186.09  471.14 7250.99     472
 7305.96     487 9253.24     487 9305.59     473 9494.15     452 9527.23     461
10185.69     46010276.98     47010390.61     460 10433.3     47810472.51     474
10511.23     48810590.54     47510656.56     48610734.28     46811388.89     470
11436.83     46011647.32     47811740.91     46912623.15     47312665.43     451
12741.01  439.8512783.52     45912845.09     472 13140.6     47713196.49     488
#Mann= 8 ,-1,0
 3522.11     .07       0  5355.7     .05       0 7186.09     .07       0
 9253.24     .06       010276.98     .11       012623.15    .055       0
12845.09      .1       0 13140.6     .03       0
#XS Ineff= 2 ,-1
 9253.2410301.22     46010301.2212623.15     470
Permanent Ineff=
       T       T
Bank Sta=12623.15,12845.09
XS Rating Curve= 0 ,0
Exp/Cntr=0.3,0.1