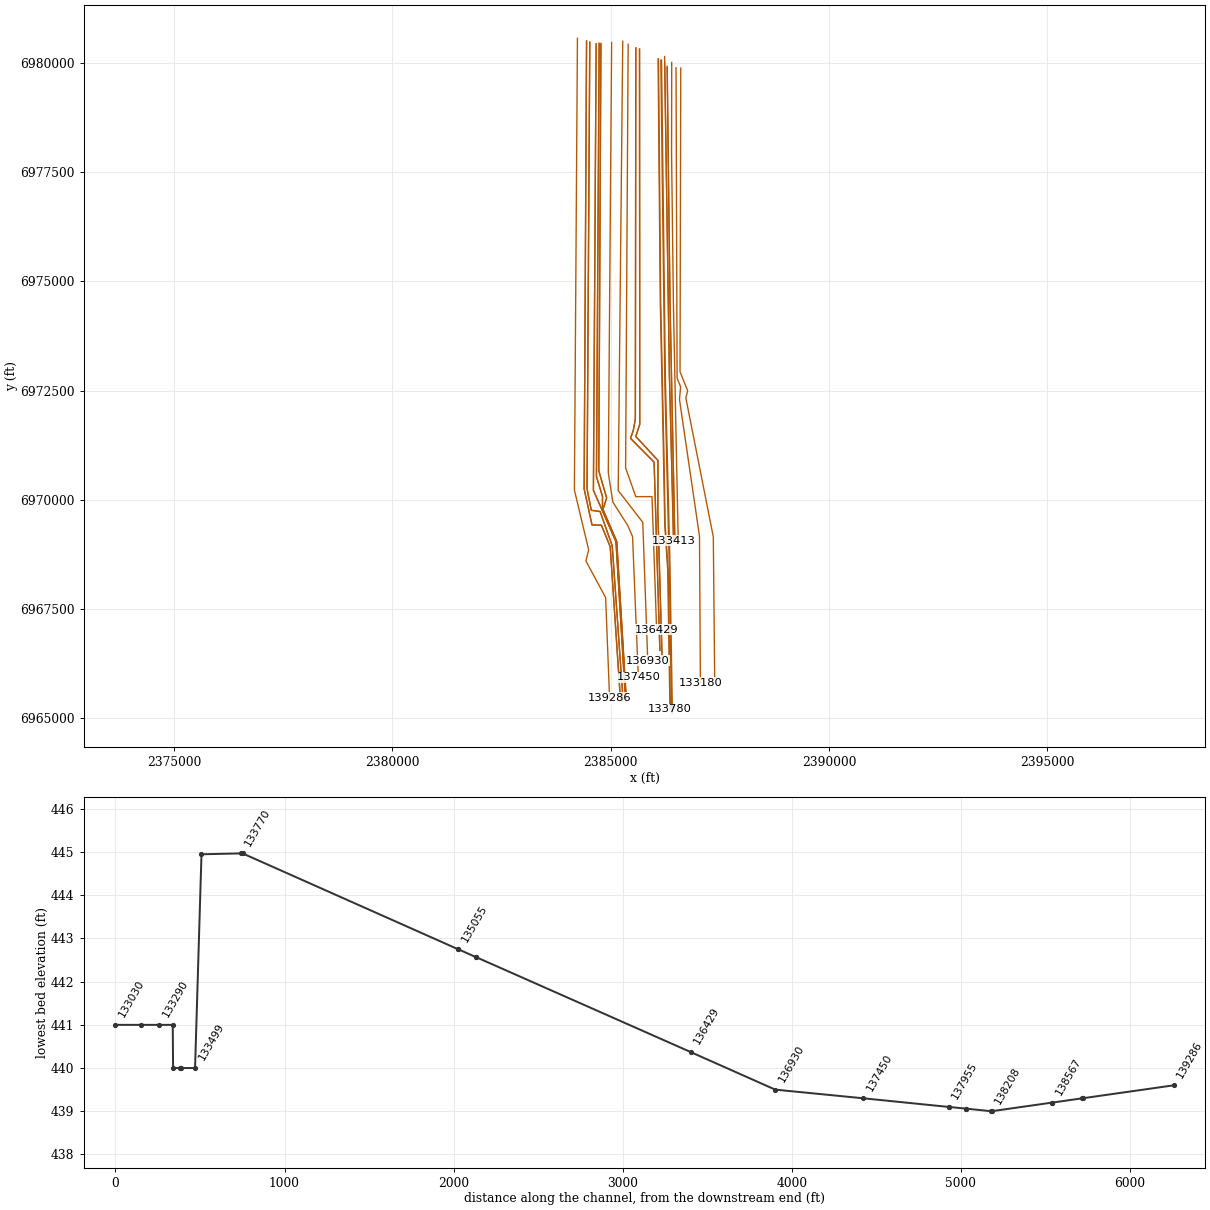
HEC-RAS study CDC_Consolidated_Model.prj: Upper Trinity CDC Consolidated Model

--- CDC_Consolidated_Model.g13 (geometry) --- (continued)

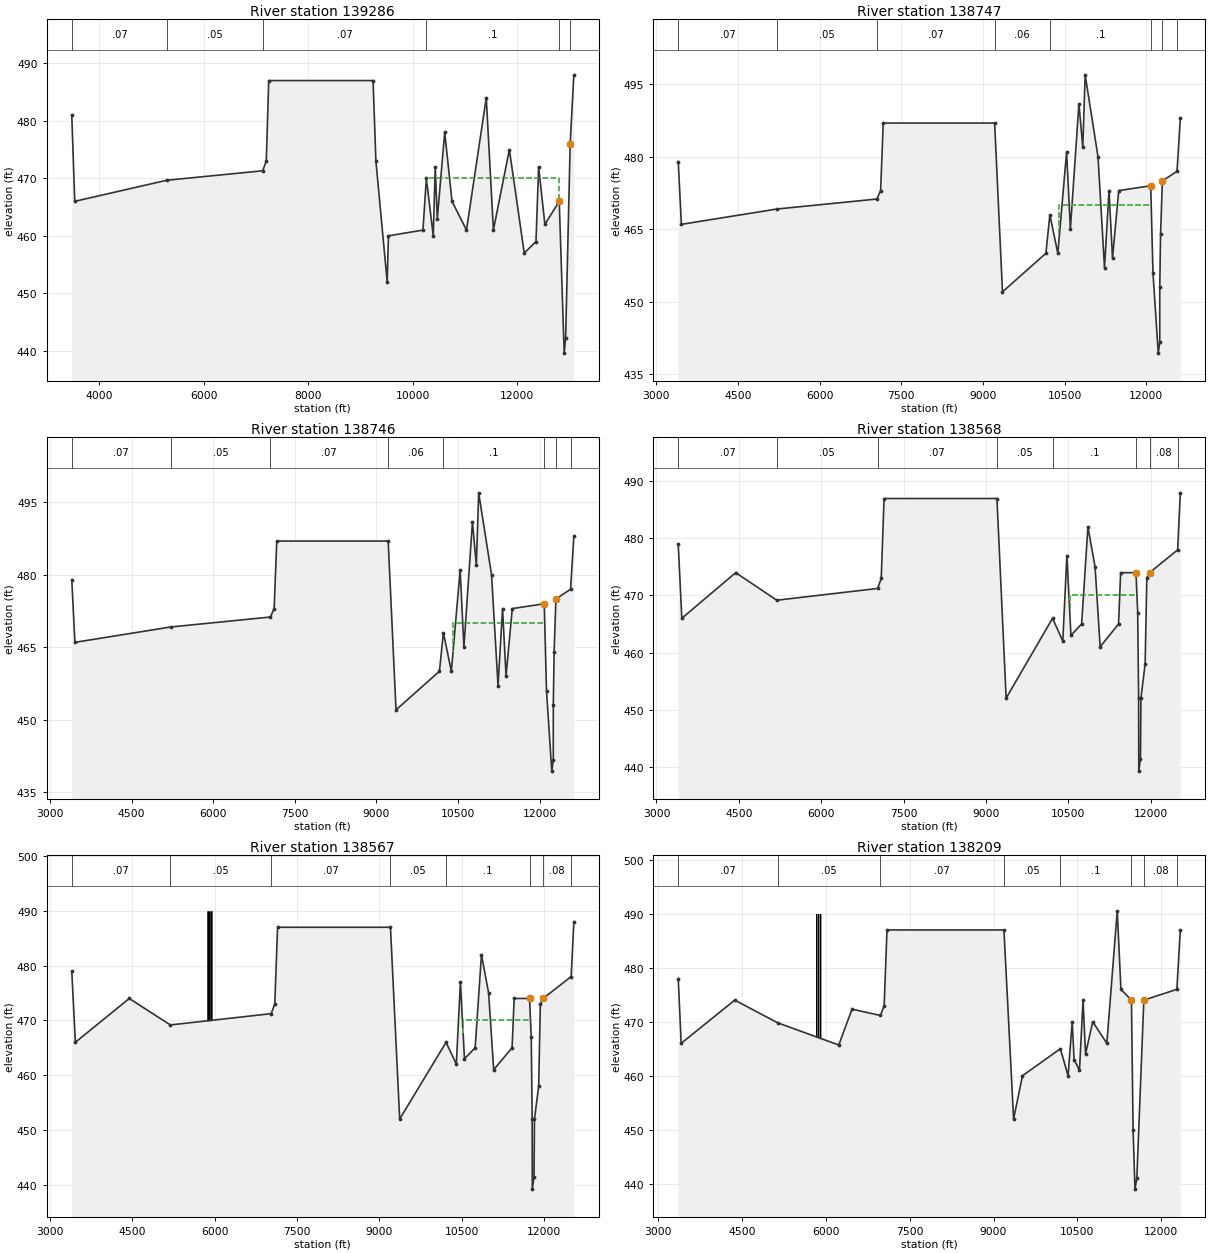
Type RM Length L Ch R = 1 ,139286  ,234,539,484
BEGIN DESCRIPTION:
Kimley-Horn added cross section based on on-ground survey and proposed grading for Bell South Airfiled property and TNRIS 2009 LiDAR offsite. Channel flowline interpolated from effective model. (KH, 2017)
END DESCRIPTION:
XS GIS Cut Line= 6
  2384236.563208 6980571.9467376 2384167.1187643 6970217.7800709
 2384493.5076532 6968849.7245154 2384431.0076532 6968592.7800709
 2384882.3965421 6967752.5022931 2384972.6743199 6965453.8911821
#Sta/Elev= 30
 3472.17     481 3528.98     466 5293.29  469.67 7125.94  471.31 7195.35     473
 7242.41     487  9239.6     487 9293.69     473 9509.59     452 9533.87     460
10194.37     46110259.26     47010391.36     46010429.32     47210468.64     463
10610.86     47810750.27     46611027.44     46111406.11     48411542.67     461
11848.17     47512132.98     45712357.74     45912408.23     47212528.35     462
12802.95     46612897.52   439.612925.23  442.1913012.37     47613082.44     488
#Mann= 6 ,-1,0
 3472.17     .07       0 5293.29     .05       0 7125.94     .07       0
10259.26      .1       012802.95     .05       013012.37     .03       0
#XS Ineff= 2 ,-1
  9239.610273.05     46010273.0512802.95     470
Permanent Ineff=
       T       T
Bank Sta=12802.95,13012.37
XS Rating Curve= 0 ,0
Exp/Cntr=0.3,0.1

Type RM Length L Ch R = 1 ,138747  ,1,1,1
BEGIN DESCRIPTION:
Kimley-Horn added cross section based on on-ground survey and proposed grading for Bell South Airfiled property and TNRIS 2009 LiDAR offsite. Channel flowline interpolated from effective model. (KH, 2017)
END DESCRIPTION:
XS GIS Cut Line= 6
  2384444.896542 6980509.4467376 2384389.3409866 6970245.5578487
 2384569.8965421 6969419.1689598 2384785.1743199 6969412.2245154
 2384986.5632088 6968919.1689598 2385222.6743199 6965384.4467376
#Sta/Elev= 30
 3402.01     479 3459.85     466 5216.54  469.18 7051.96  471.25 7120.64     473
 7168.91     487 9215.89     487  9359.9     45210157.72     46010230.48     468
10376.75     46010538.39     48110607.46     46510764.47     49110835.66     482
10879.12     497 11115.3     48011234.76     45711317.71     473 11381.6     459
11496.05     47312083.68     47412125.13     45612222.04   439.312249.75   441.6
12250.05     453 12264.9     46412298.26     47512567.19     47712627.56     488
#Mann= 8 ,-1,0
 3402.01     .07       0 5216.54     .05       0 7051.96     .07       0
 9215.89     .06       010230.48      .1       012083.68     .05       0
12298.26     .08       012567.19     .03       0
#XS Ineff= 2 ,-1
 9215.8910407.04     46010407.0412083.68     470
Permanent Ineff=
       T       T
Bank Sta=12083.68,12298.26
XS Rating Curve= 0 ,0
Exp/Cntr=0.3,0.1

Type RM Length L Ch R = 1 ,138746  ,76,178,159
BEGIN DESCRIPTION:
Kimley-Horn added cross section based on on-ground survey and proposed grading for Bell South Airfiled property and TNRIS 2009 LiDAR offsite. Channel flowline interpolated from effective model. (KH, 2017)
END DESCRIPTION:
XS GIS Cut Line= 6
  2384445.896527  6980509.441325 2384390.3415711 6970245.6631433
  2384570.707245 6969420.1433283 2384785.8548229 6969413.2030838
 2384987.5463398 6968919.4066113 2385223.6727639 6965384.5025018
#Sta/Elev= 30
 3402.01     479 3459.85     466 5216.54  469.18 7051.96  471.25 7120.64     473
 7168.91     487 9215.89     487  9359.9     45210157.72     46010230.48     468
10376.75     46010538.39     48110607.46     46510764.47     49110835.66     482
10879.12     497 11115.3     48011234.76     45711317.71     473 11381.6     459
11496.05     47312083.68     47412125.13     45612222.04   439.312249.75   441.6
12250.05     453 12264.9     46412298.26     47512567.19     47712627.56     488
#Mann= 8 ,-1,0
 3402.01     .07       0 5216.54     .05       0 7051.96     .07       0
 9215.89     .06       010230.48      .1       012083.68     .05       0
12298.26     .08       012567.19     .03       0
#XS Ineff= 2 ,-1
 9215.8910407.04     46010407.0412083.68     470
Permanent Ineff=
       T       T
Bank Sta=12083.68,12298.26
XS Rating Curve= 0 ,0
Exp/Cntr=0.3,0.1

Type RM Length L Ch R = 1 ,138568  ,1,1,1
BEGIN DESCRIPTION:
Kimley-Horn added cross section based on on-ground survey and proposed grading for Bell South Airfiled property and TNRIS 2009 LiDAR offsite. Channel flowline interpolated from effective model. (KH, 2017)
END DESCRIPTION:
XS GIS Cut Line= 6
  2384518.681264  6980483.405071 2384456.1812643 6970247.2939598
 2384553.4034866 6969754.2384043 2384754.7923755 6969726.4606265
 2385032.5701532 6968941.7384043 2385282.5701532 6965386.1828487
#Sta/Elev= 30
  3396.3     479 3461.59     466 4442.77     474 5191.23  469.17  7027.3  471.23
 7093.07     473 7144.61     487 9200.18     487 9367.88     45210212.97     466
10399.55     462 10473.7     47710547.74     46310742.46     46510857.05     482
10987.75     47511079.64     46111414.67     46511452.93     47411732.11     474
11763.82     46711780.34     45211782.94   439.211814.17   441.411822.45     452
 11899.2     45811929.47     47311979.87     47412490.97     47812539.61     488
#Mann= 8 ,-1,0
  3396.3     .07       0 5191.23     .05       0  7027.3     .07       0
 9200.18     .05       010212.97      .1       011732.11     .05       0
11979.87     .08       012490.97     .03       0
#XS Ineff= 2 ,-1
 9200.1810523.06     46010523.0611732.11     470
Permanent Ineff=
       T       T
Bank Sta=11732.11,11979.87
XS Rating Curve= 0 ,0
Exp/Cntr=0.3,0.1

Type RM Length L Ch R = 1 ,138567  ,155,358,321
BEGIN DESCRIPTION:
Kimley-Horn added cross section based on on-ground survey and proposed grading for Bell South Airfiled property and TNRIS 2009 LiDAR offsite. Channel flowline interpolated from effective model. (KH, 2017)
END DESCRIPTION:
XS GIS Cut Line= 6
  2384519.681245 6980483.3989652 2384457.1818607 6970247.3885866
 2384554.2466231 6969755.1315773 2384755.5319551 6969727.3680832
 2385033.5528226 6968941.9591323 2385283.5688739 6965386.2334168
#Sta/Elev= 30
  3396.3     479 3461.59     466 4442.77     474 5191.23  469.17  7027.3  471.23
 7093.07     473 7144.61     487 9200.18     487 9367.88     45210212.97     466
10399.55     462 10473.7     47710547.74     46310742.46     46510857.05     482
10987.75     47511079.64     46111414.67     46511452.93     47411732.11     474
11763.82     46711780.34     45211782.94   439.211814.17   441.411822.45     452
 11899.2     45811929.47     47311979.87     47412490.97     47812539.61     488
#Mann= 8 ,-1,0
  3396.3     .07       0 5191.23     .05       0  7027.3     .07       0
 9200.18     .05       010212.97      .1       011732.11     .05       0
11979.87     .08       012490.97     .03       0
#XS Ineff= 2 ,-1
 9200.1810523.06     46010523.0611732.11     470
Permanent Ineff=
       T       T
#Block Obstruct= 3 ,-1
    5869    5870     490    5903    5904     490    5938    5939     490
Bank Sta=11732.11,11979.87
XS Rating Curve= 0 ,0
Exp/Cntr=0.3,0.1

Type RM Length L Ch R = 1 ,138209  ,1,1,1
BEGIN DESCRIPTION:
Kimley-Horn added cross section based on on-ground survey and proposed grading for Bell South Airfiled property and TNRIS 2009 LiDAR offsite. Channel flowline interpolated from effective model. (KH, 2017)
END DESCRIPTION:
XS GIS Cut Line= 4
  2384664.514597 6980441.7384043 2384602.0145977 6970212.5717376
 2385118.7970051  6969036.067108  2385339.717144 6965369.9212747
#Sta/Elev= 30
 3358.27     478 3410.64     466 4369.34     474 5140.39  469.79 6231.23  465.69
 6467.82  472.33 6977.31  471.16 7043.47     473 7094.18     487 9186.53     487
  9359.8     452 9518.32     46010196.58     46510334.54     46010408.52     470
10442.26     46310538.47     46110602.55     474 10646.5     46410775.73     470
11028.36     46611214.24  490.5411280.18     47611468.38     47411497.89     450
11531.79     43911564.79     44111690.02     47412281.28     47612342.92     487
#Mann= 8 ,-1,0
 3358.27     .07       0 5140.39     .05       0 6977.31     .07       0
 9186.53     .05       010196.58      .1       011468.38     .05       0
11690.02     .08       012281.28     .03       0
#Block Obstruct= 3 ,-1
    5829    5830     490    5864    5865     490    5899    5900     490
Bank Sta=11468.38,11690.02
XS Rating Curve= 0 ,0
Exp/Cntr=0.3,0.1

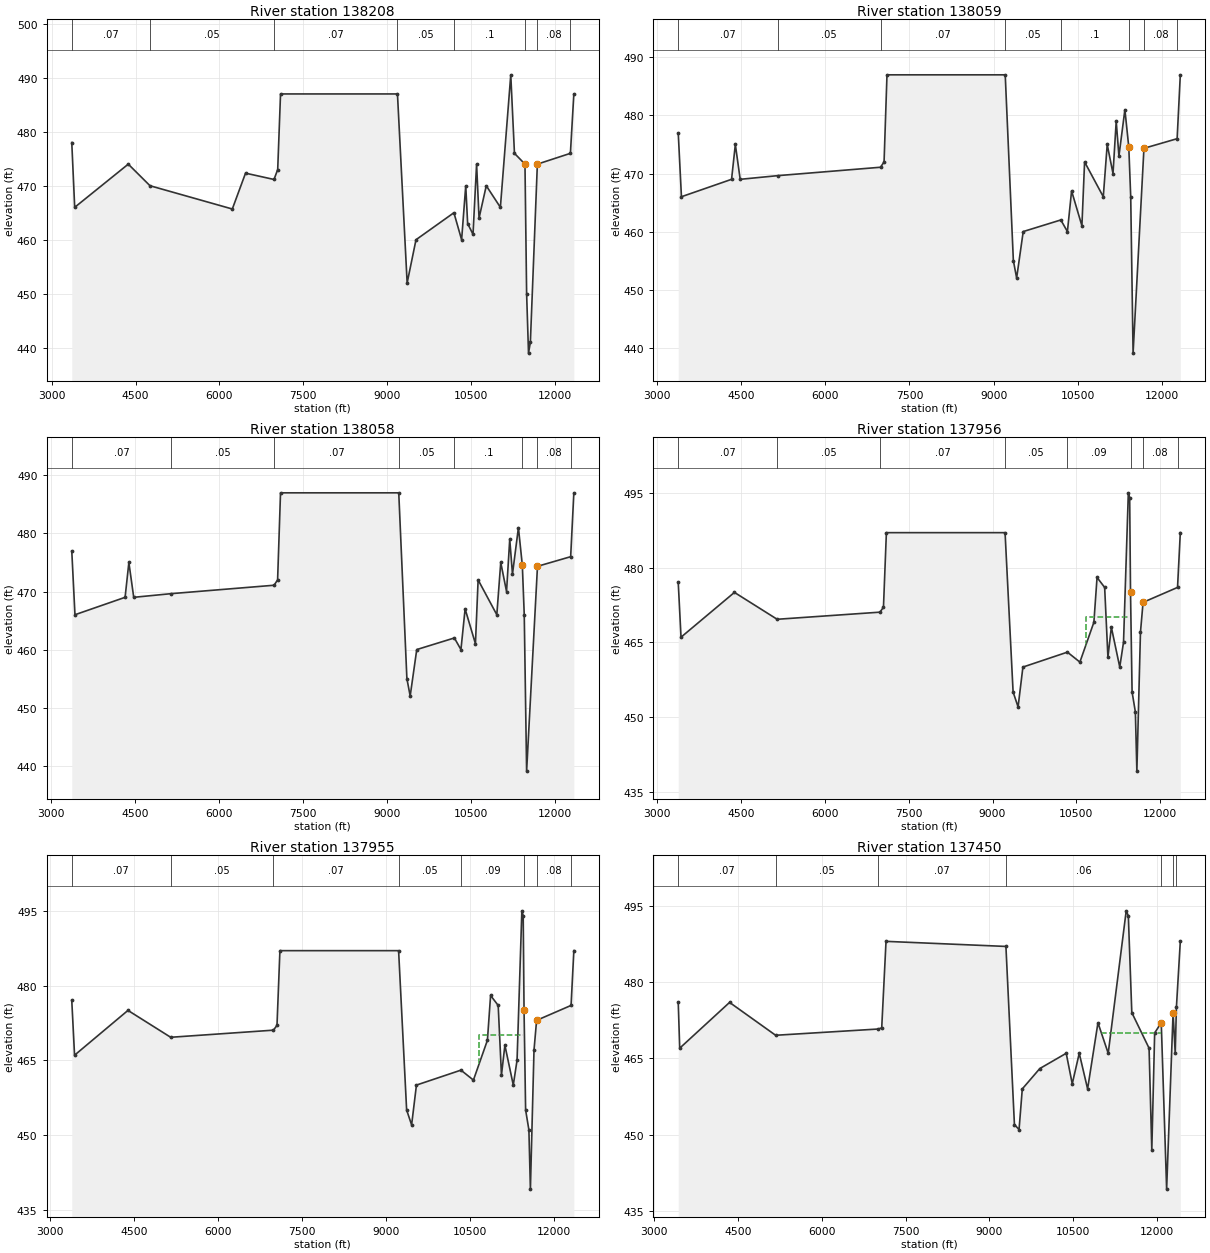
Type RM Length L Ch R = 1 ,138208  ,67,149,93
BEGIN DESCRIPTION:
Kimley-Horn updated cross section based on on-ground survey and proposed grading for Bell South Airfiled property and TNRIS 2009 LiDAR offsite. Channel flowline interpolated from effective model. (KH, 2017)
END DESCRIPTION:
XS GIS Cut Line= 4
  2384665.514579 6980441.7322944 2384603.0158813 6970212.7787611
 2385119.7844447 6969036.3056485 2385340.7153333 6965369.9814251
#Sta/Elev= 30
 3358.27     478 3410.64     466 4369.34     474 4758.11     470 6231.23  465.69
 6467.82  472.33 6977.31  471.16 7043.47     473 7094.18     487 9186.53     487
  9359.8     452 9518.32     46010196.58     46510334.54     46010408.52     470
10442.26     46310538.47     46110602.55     474 10646.5     46410775.73     470
11028.36     46611214.24  490.5411280.18     47611468.38     47411497.89     450
11531.79     43911564.79     44111690.02     47412281.28     47612342.92     487
#Mann= 8 ,-1,0
 3358.27     .07       0 4758.11     .05       0 6977.31     .07       0
 9186.53     .05       010196.58      .1       011468.38     .05       0
11690.02     .08       012281.28     .03       0
#XS Ineff= 2 ,-1
 9186.5310408.52     46010408.5211468.38     470
Permanent Ineff=
       T       T
Bank Sta=11468.38,11690.02
XS Rating Curve= 0 ,0
Exp/Cntr=0.3,0.1

Type RM Length L Ch R = 1 ,138059  ,1,1,1
BEGIN DESCRIPTION:
Kimley-Horn added cross section based on on-ground survey and proposed grading for Bell South Airfiled property and TNRIS 2009 LiDAR offsite. Channel flowline interpolated from effective model. (KH, 2017)
END DESCRIPTION:
XS GIS Cut Line= 6
  2384733.959042 6980455.6272932 2384671.4590421 6970525.0717376
  2384810.347931 6970073.6828487 2384809.7692273 6969766.9698858
 2385127.3039495 6969035.6330802 2385351.5053384 6965363.3240524
#Sta/Elev= 30
 3375.19     477 3432.23     466 4326.36     469 4393.69     475 4480.28     469
 5146.95  469.63 6983.45  471.08 7046.66     472 7098.73     487 9207.71     487
 9352.83     455 9411.32     452  9528.6     46010199.41     46210316.89     460
10391.36     46710575.49     46110623.29     47210956.82     46611026.87     475
11130.21     47011187.31     47911236.04     47311342.16     48111411.85  474.53
11446.06     46611488.41  439.0611682.12  474.3412274.02     47612330.75     487
#Mann= 8 ,-1,0
 3375.19     .07       0 5146.95     .05       0 6983.45     .07       0
 9207.71     .05       010199.41      .1       011411.85     .05       0
11682.12     .08       012274.02     .03       0
#XS Ineff= 2 ,-1
 9207.7110710.21     46010710.2111392.97     470
Permanent Ineff=
       T       T
Bank Sta=11411.85,11682.12
XS Rating Curve= 0 ,0
Exp/Cntr=0.3,0.1

Type RM Length L Ch R = 1 ,138058  ,1045,102,63
BEGIN DESCRIPTION:
Kimley-Horn added cross section based on on-ground survey and proposed grading for Bell South Airfiled property and TNRIS 2009 LiDAR offsite. Channel flowline interpolated from effective model. (KH, 2017)
END DESCRIPTION:
XS GIS Cut Line= 6
  2384734.959022 6980455.6209996 2384672.4599889 6970525.2190281
 2384811.3482148 6970073.8322942 2384810.7696193 6969767.1767075
 2385128.2913591 6969035.8698027   2385352.50348 6965363.3849908
#Sta/Elev= 30
 3375.19     477 3432.23     466 4326.36     469 4393.69     475 4480.28     469
 5146.95  469.63 6983.45  471.08 7046.66     472 7098.73     487 9207.71     487
 9352.83     455 9411.32     452  9528.6     46010199.41     46210316.89     460
10391.36     46710575.49     46110623.29     47210956.82     46611026.87     475
11130.21     47011187.31     47911236.04     47311342.16     48111411.85  474.53
11446.06     46611488.41  439.0611682.12  474.3412274.02     47612330.75     487
#Mann= 8 ,-1,0
 3375.19     .07       0 5146.95     .05       0 6983.45     .07       0
 9207.71     .05       010199.41      .1       011411.85     .05       0
11682.12     .08       012274.02     .03       0
#XS Ineff= 2 ,-1
 9207.7110710.21     46010710.2111392.97     470
Permanent Ineff=
       T       T
Bank Sta=11411.85,11682.12
XS Rating Curve= 0 ,0
Exp/Cntr=0.3,0.1

Type RM Length L Ch R = 1 ,137956  ,1,1,1
BEGIN DESCRIPTION:
Kimley-Horn added cross section based on on-ground survey and proposed grading for Bell South Airfiled property and TNRIS 2009 LiDAR offsite. Channel flowline interpolated from effective model. (KH, 2017)
END DESCRIPTION:
XS GIS Cut Line= 6
  2384773.310893 6980452.7337747 2384724.6997829  6970661.067108
 2384905.2553384  6970036.067108 2384820.2726995  6969774.348358
 2385136.1581162 6969040.5809969 2385358.3803384 6965365.2337747
#Sta/Elev= 30
 3383.76     477 3433.55     466 4388.02     475  5151.4   469.6 6987.76  471.03
 7051.31     472 7103.58     487 9224.56     487 9368.06     455 9457.13     452
 9543.36     46010338.82     46310561.69     46110811.78     46910868.34     478
11004.28     47611062.66     46211124.08     46811274.08     46011341.53     465
11427.38     49511451.37     49411466.45     47511494.48     45511553.07     451
11579.94   439.111644.22     46711690.76     47312306.72     47612356.34     487
#Mann= 8 ,-1,0
 3383.76     .07       0  5151.4     .05       0 6987.76     .07       0
 9224.56     .05       010338.82     .09       011466.45     .05       0
11690.76     .08       012306.72     .03       0
#XS Ineff= 2 ,-1
 9224.5610665.65     46010665.6511445.86     470
Permanent Ineff=
       T       T
Bank Sta=11466.45,11690.76
XS Rating Curve= 0 ,0
Exp/Cntr=0.3,0.1

Type RM Length L Ch R = 1 ,137955  ,229,505,316
BEGIN DESCRIPTION:
Kimley-Horn added cross section based on on-ground survey and proposed grading for Bell South Airfiled property and TNRIS 2009 LiDAR offsite. Channel flowline interpolated from effective model. (KH, 2017)
END DESCRIPTION:
XS GIS Cut Line= 6
  2384774.310881 6980452.7288102 2384725.7004858 6970661.2062249
 2384906.3011766 6970036.0499876 2384821.3401476 6969774.3977889
 2385137.1457429 6969040.8158442 2385359.3785155 6965365.2941274
#Sta/Elev= 30
 3383.76     477 3433.55     466 4388.02     475  5151.4   469.6 6987.76  471.03
 7051.31     472 7103.58     487 9224.56     487 9368.06     455 9457.13     452
 9543.36     46010338.82     46310561.69     46110811.78     46910868.34     478
11004.28     47611062.66     46211124.08     46811274.08     46011341.53     465
11427.38     49511451.37     49411466.45     47511494.48     45511553.07     451
11579.94   439.111644.22     46711690.76     47312306.72     47612356.34     487
#Mann= 8 ,-1,0
 3383.76     .07       0  5151.4     .05       0 6987.76     .07       0
 9224.56     .05       010338.82     .09       011466.45     .05       0
11690.76     .08       012306.72     .03       0
#XS Ineff= 2 ,-1
 9224.5610665.65     46010665.6511445.86     470
Permanent Ineff=
       T       T
Bank Sta=11466.45,11690.76
XS Rating Curve= 0 ,0
Exp/Cntr=0.3,0.1

Type RM Length L Ch R = 1 ,137450  ,236,520,326
BEGIN DESCRIPTION:
Kimley-Horn added cross section based on on-ground survey and proposed grading for Bell South Airfiled property and TNRIS 2009 LiDAR offsite. Channel flowline interpolated from effective model. (KH, 2017)
END DESCRIPTION:
XS GIS Cut Line= 6
  2385019.772188 6980477.9312432 2384943.3832992 6970609.8756876
 2385047.5499659  6969943.209021 2385387.8277437 6969408.4867987
 2385498.9388548 6969151.5423543 2385630.8832993 6965922.3756876
#Sta/Elev= 30
 3430.11     476 3456.49     467 4348.95     476 5173.34  469.54 7010.35  470.77
 7072.07     471 7149.17     488 9295.08     487 9447.35     452 9530.09     451
 9588.06     459 9901.66     46310374.05     46610482.16     460 10607.4     466
10757.09     45910942.34     47211125.86     46611448.01     49411485.99     493
 11548.2     47411857.13     467   11906     44711957.21     47012075.25     472
12171.53   439.3   12287     47412325.18     46612346.36     47512416.33     488
#Mann= 7 ,-1,0
 3430.11     .07       0 5173.34     .05       0 7010.35     .07       0
 9295.08     .06       012075.25    .055       0   12287    .075       0
12346.36     .03       0
#XS Ineff= 2 ,-1
 9295.0811004.64     46011004.6412075.25     470
Permanent Ineff=
       T       T
Bank Sta=12075.25,12287
XS Rating Curve= 0 ,0
Exp/Cntr=0.3,0.1

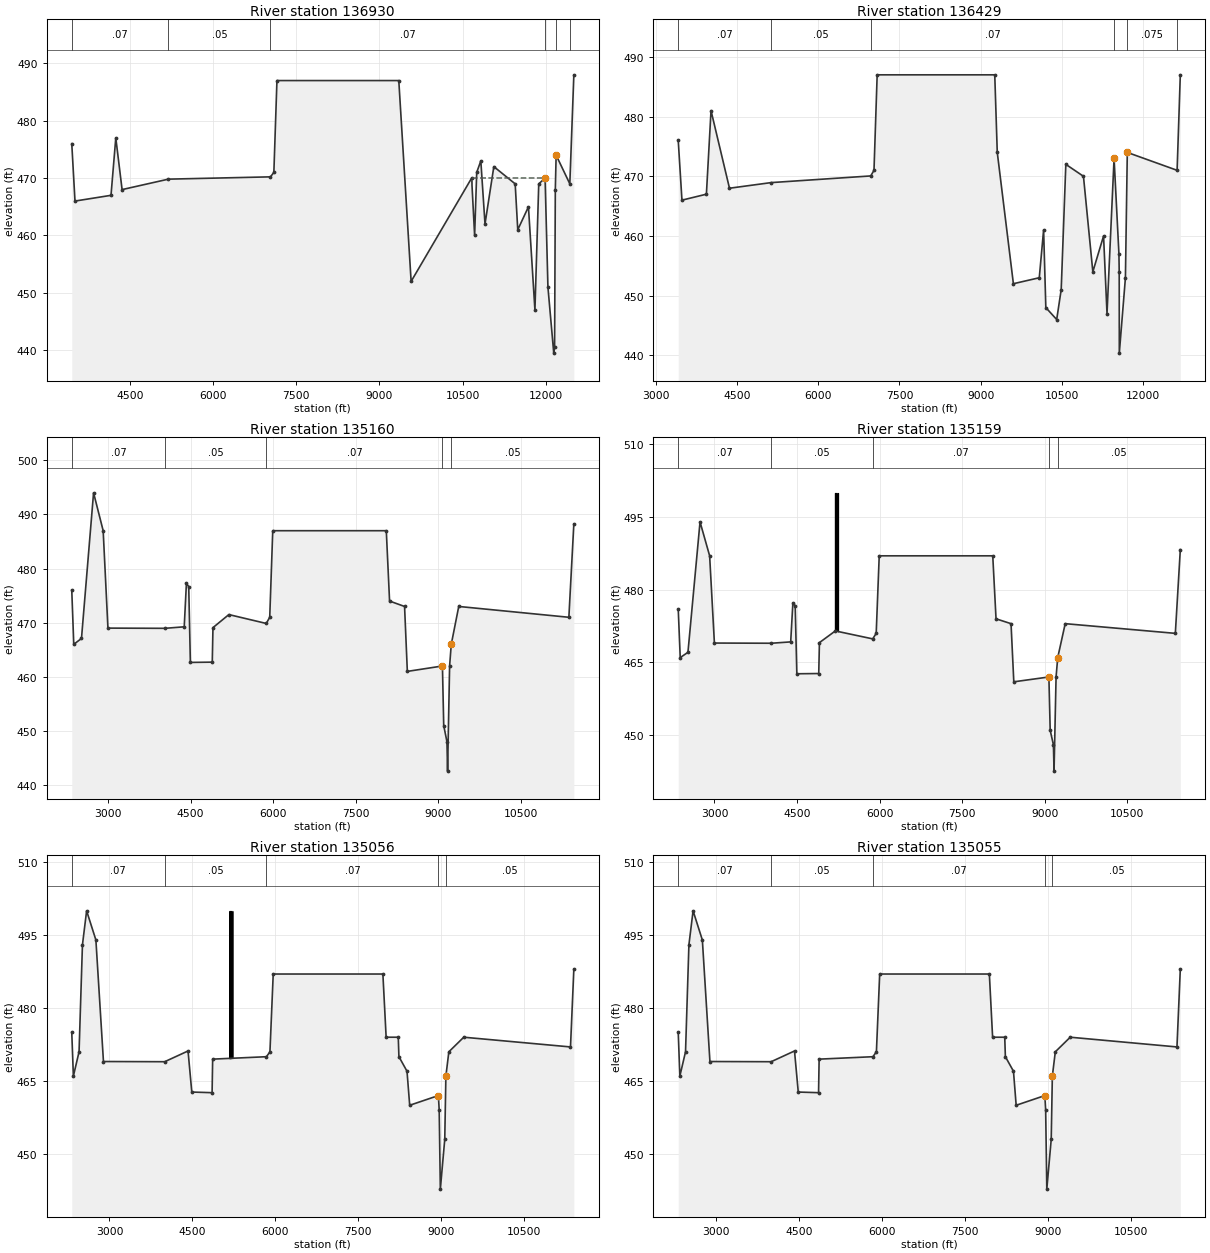
Type RM Length L Ch R = 1 ,136930  ,128,500,25
BEGIN DESCRIPTION:
Kimley-Horn updated cross section based on on-ground survey and proposed grading for Bell South Airfiled property and TNRIS 2009 LiDAR offsite. Channel flowline interpolated from effective model. (KH, 2017)
---------------------------------------------------------------------
CDC FW020400-01 Lakeview Addition
Cross-sections 136930 - 138208
---------------------------------------------------------------------
Project located in LOB outside of effective flow limits, therefore not included in model.
END DESCRIPTION:
XS GIS Cut Line= 4
  2385274.151885  6980505.250163 2385169.9852188  6970208.375163
 2385732.4852188 6969479.2084963 2385847.0685521  6966302.125163
#Sta/Elev= 30
 3453.53     476 3511.58     466 4160.97     467 4247.42     477 4360.94     468
    5196  469.82 7037.02  470.22 7097.86     471  7153.5     487 9350.65     487
 9573.04     45210664.03     47010718.13     46010755.91     47110829.96     473
10905.39     46211064.59     47211449.39     46911495.91     46111688.79     465
11805.59     44711874.49     46911988.92     47012040.11     45112145.12   439.5
12160.12   440.5 12173.4     46812188.06     47412434.82     46912507.39     488
#Mann= 6 ,-1,0
 3453.53     .07       0    5196     .05       0 7037.02     .07       0
11988.92    .055       012188.06    .075       012434.82     .03       0
#XS Ineff= 2 ,-1
 9350.6510671.24     46010671.2411988.92     470
Permanent Ineff=
       T       T
Bank Sta=11988.92,12188.06
XS Rating Curve= 0 ,0
Exp/Cntr=0.3,0.1

Type RM Length L Ch R = 1 ,136429  ,107,1270,41
BEGIN DESCRIPTION:
Kimley-Horn added cross section based on on-ground survey and proposed grading for Bell South Airfiled property and TNRIS 2009 LiDAR offsite. Channel flowline interpolated from effective model. (KH, 2017)
END DESCRIPTION:
XS GIS Cut Line= 5
  2385398.131878  6980435.895284 2385339.8246571 6970725.0926253
 2385573.0535419 6970067.8112226  2385944.099495 6970067.8112226
 2386050.1126244 6967014.6330941
#Sta/Elev= 30
 3414.23     476 3482.83     466 3934.35     467 4019.86     481 4360.62     468
 5128.53  468.94 6969.69  470.06 7029.78     471  7088.5     487 9260.27     487
 9306.61     474 9604.41     45210082.51     453 10162.5     46110203.58     448
10404.36     44610487.35     45110573.07     47210898.53     47011071.73     454
11269.83     46011333.48     44711464.11     47311553.72     45711558.95     454
11560.69  440.3711673.72     45311708.39     47412628.25     47112687.44     487
#Mann= 6 ,-1,0
 3414.23     .07       0 5128.53     .05       0 6969.69     .07       0
11464.11    .055       011708.39    .075       012628.25     .03       0
#XS Ineff= 2 ,-1
 9494.0110590.11     46010590.1111464.11     470
Permanent Ineff=
       T       T
Bank Sta=11464.11,11708.39
XS Rating Curve= 0 ,0
Exp/Cntr=0.3,0.1

Type RM Length L Ch R = 1 ,135160  ,1,1,1
BEGIN DESCRIPTION:
Kimley-Horn added cross section based on on-ground survey and proposed grading for Bell South Airfiled property and TNRIS 2009 LiDAR offsite. Channel flowline interpolated from effective model. (KH, 2017)
END DESCRIPTION:
XS GIS Cut Line= 6
  2385573.053541 6980351.0847804 2385562.4522289 6971848.8317976
 2385514.7463207 6971583.7989739  2385451.138443 6971403.5766538
 2385991.8054032 6970857.6090371 2386124.3218151  6966542.874668
#Sta/Elev= 30
 2342.22     476 2378.44     466 2518.71  467.09 2738.25     494 2912.57     487
 2999.21     469 4034.38  468.96 4385.14  469.24 4424.74  477.27 4466.93  476.67
 4496.73  462.66 4894.57  462.71 4907.21  469.09 5196.27   471.5  5875.2  469.86
 5938.45     471 5993.34     487 8055.84     487 8115.35     474 8387.82     473
 8438.14     461 9075.66     462 9099.12     451 9157.72     448 9169.18  442.57
 9206.05     462 9236.15     466 9372.03     47311372.58     47111462.94  488.27
#Mann= 5 ,-1,0
 2342.22     .07       0 4034.38     .05       0  5875.2     .07       0
 9075.66    .055       0 9236.15     .05       0
#XS Ineff= 1 ,-1
    4470    4910     468
Permanent Ineff=
       T
Bank Sta=9075.66,9236.15
XS Rating Curve= 0 ,0
Exp/Cntr=0.3,0.1

Type RM Length L Ch R = 1 ,135159  ,93,103,54
BEGIN DESCRIPTION:
Kimley-Horn added cross section based on on-ground survey and proposed grading for Bell South Airfiled property and TNRIS 2009 LiDAR offsite. Channel flowline interpolated from effective model. (KH, 2017)
END DESCRIPTION:
XS GIS Cut Line= 6
  2385574.053541 6980351.0835335 2385563.4521176 6971848.7418966
 2385515.7161945 6971583.5423237 2385452.2900513 6971403.8349181
 2385992.7928516 6970858.0330708 2386125.3213438 6966542.9053661
#Sta/Elev= 30
 2342.22     476 2378.44     466 2518.71  467.09 2738.25     494 2912.57     487
 2999.21     469 4034.38  468.96 4385.14  469.24 4424.74  477.27 4466.93  476.67
 4496.73  462.66 4894.57  462.71 4907.21  469.09 5196.27   471.5  5875.2  469.86
 5938.45     471 5993.34     487 8055.84     487 8115.35     474 8387.82     473
 8438.14     461 9075.66     462 9099.12     451 9157.72     448 9169.18  442.57
 9206.05     462 9236.15     466 9372.03     47311372.58     47111462.94  488.27
#Mann= 5 ,-1,0
 2342.22     .07       0 4034.38     .05       0  5875.2     .07       0
 9075.66    .055       0 9236.15     .05       0
#XS Ineff= 1 ,-1
    4470    4910     468
Permanent Ineff=
       T
#Block Obstruct= 5 ,-1
    5187    5188     500    5197    5198     500    5207    5208     500
    5220    5221     500    5246    5247     500
Bank Sta=9075.66,9236.15
XS Rating Curve= 0 ,0
Exp/Cntr=0.3,0.1

Type RM Length L Ch R = 1 ,135056  ,1,1,1
BEGIN DESCRIPTION:
Kimley-Horn added cross section based on on-ground survey and proposed grading for Bell South Airfiled property and TNRIS 2009 LiDAR offsite. Channel flowline interpolated from effective model. (KH, 2017)
END DESCRIPTION:
XS GIS Cut Line= 6
  2385657.864045  6980324.581498 2385663.1647019 6971726.9166987
 2385573.0535419 6971445.9819056 2386081.9165633 6970894.7136324
 2386076.6159068 6969744.4711778 2386175.0401956 6966356.7027095
#Sta/Elev= 30
 2318.63     475 2347.74     466 2450.46     471 2511.69     493 2587.14     500
 2754.83     494  2891.7     469 3999.11  468.96 4421.39  471.17 4489.17  462.72
 4856.27  462.59 4866.59  469.49 5839.42  469.99 5902.44     471 5961.76     487
 7944.99     487 8003.79     474 8223.19     474 8234.81     470 8381.23     467
 8429.76     460  8948.8     462 8963.36     459    8984  442.75 9063.86     453
 9084.21     466 9137.85     471  9407.4     47411337.74     47211398.36     488
#Mann= 5 ,-1,0
 2318.63     .07       0 3999.11     .05       0 5839.42     .07       0
  8948.8    .055       0 9084.21     .05       0
#XS Ineff= 1 ,-1
    4420    4870     468
Permanent Ineff=
       T
#Block Obstruct= 5 ,-1
    5168    5169     500    5178    5179     500    5188    5189     500
    5201    5202     500    5223    5224     500
Bank Sta=8948.8,9084.21
XS Rating Curve= 0 ,0
Exp/Cntr=0.3,0.1

Type RM Length L Ch R = 1 ,135055  ,476,1275,38
BEGIN DESCRIPTION:
Kimley-Horn added cross section based on on-ground survey and proposed grading for Bell South Airfiled property and TNRIS 2009 LiDAR offsite. Channel flowline interpolated from effective model. (KH, 2017)
END DESCRIPTION:
XS GIS Cut Line= 6
  2385658.864045 6980324.5821146 2385664.1647984 6971726.7605477
 2385574.1838533 6971446.2317188 2386082.9183667 6970895.1026626
 2386077.6159737 6969744.4833974 2386176.0397739 6966356.7317501
#Sta/Elev= 30
 2318.63     475 2347.74     466 2450.46     471 2511.69     493 2587.14     500
 2754.83     494  2891.7     469 3999.11  468.96 4421.39  471.17 4489.17  462.72
 4856.27  462.59 4866.59  469.49 5839.42  469.99 5902.44     471 5961.76     487
 7944.99     487 8003.79     474 8223.19     474 8234.81     470 8381.23     467
 8429.76     460  8948.8     462 8963.36     459    8984  442.75 9063.86     453
 9084.21     466 9137.85     471  9407.4     47411337.74     47211398.36     488
#Mann= 5 ,-1,0
 2318.63     .07       0 3999.11     .05       0 5839.42     .07       0
  8948.8    .055       0 9084.21     .05       0
#XS Ineff= 1 ,-1
    4420    4870     468
Permanent Ineff=
       T
Bank Sta=8948.8,9084.21
XS Rating Curve= 0 ,0
Exp/Cntr=0.3,0.1

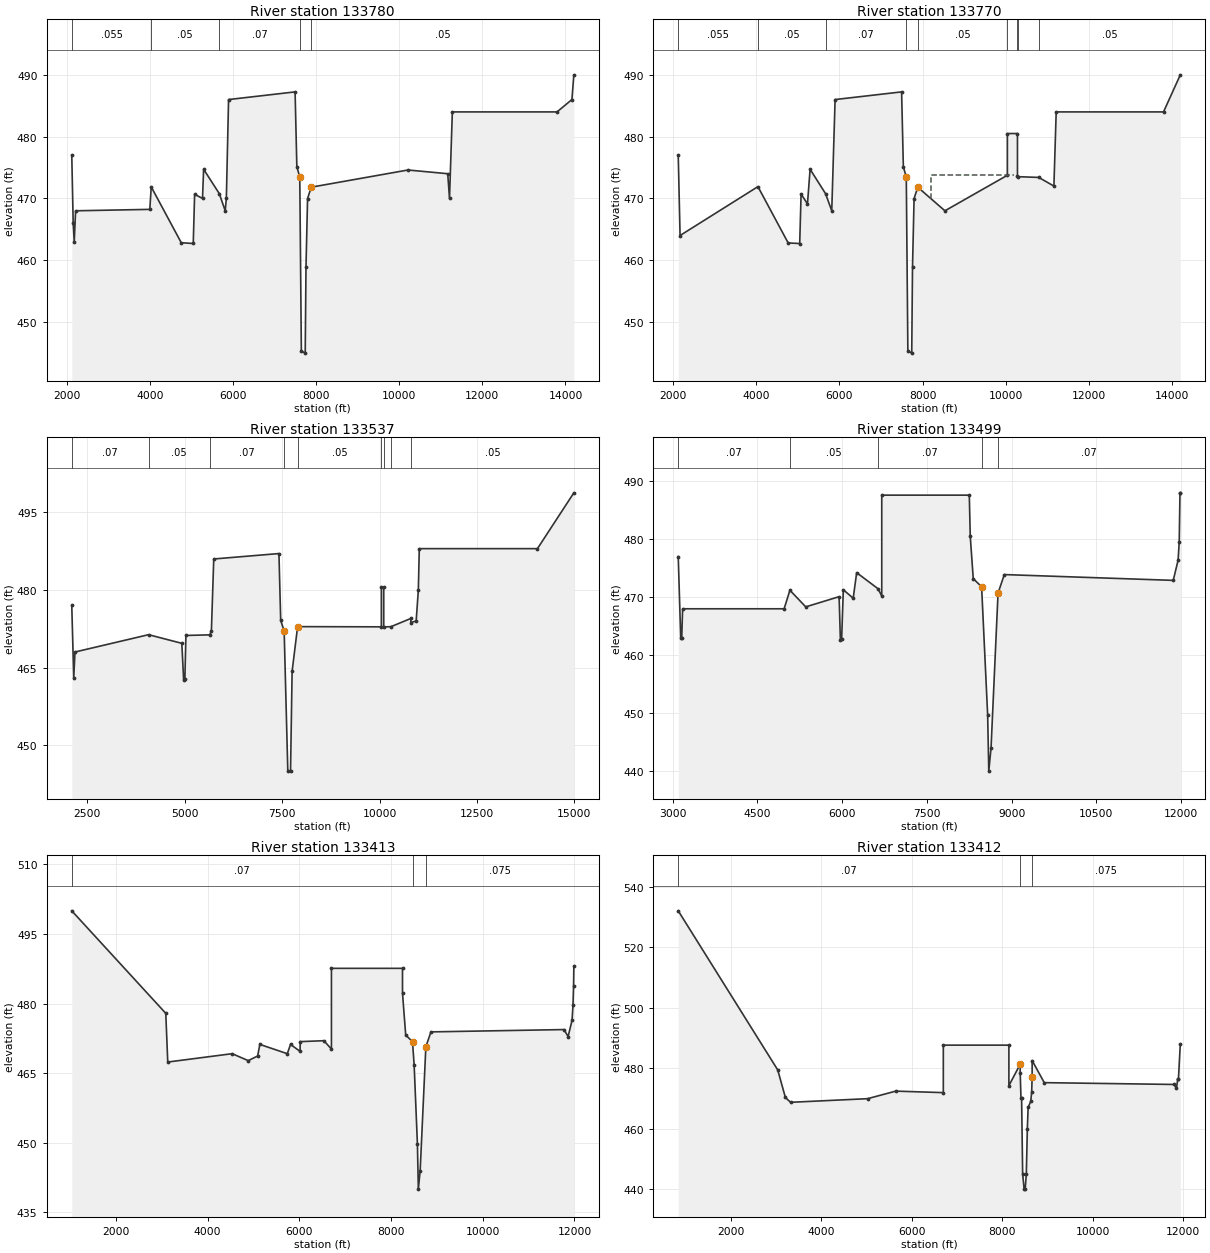
Type RM Length L Ch R = 1 ,133780  ,10,10,40
BEGIN DESCRIPTION:
Kimley-Horn updated cross section based on on-ground survey and proposed grading for Bell South Airfiled property and TNRIS 2009 LiDAR offsite. Channel flowline interpolated from effective model. (KH, 2017)
*CDC Approximated Cross Section*
END DESCRIPTION:
XS GIS Cut Line= 6
   2386083.24332 6980099.9752789 2386133.5905429 6974532.7009734
 2386204.9881123  6971138.820765 2386236.2381123 6969414.8624317
 2386303.9464456 6968383.6124317 2386355.5089456 6965190.6436817
#Sta/Elev= 30
 2123.13     477 2157.19     466 2182.57     463 2215.18     468 4000.58  468.23
 4034.65  471.87 4757.32  462.83 5045.44  462.71 5078.61  470.67 5268.14     470
 5294.95  474.72 5671.72  470.78 5814.55     468 5841.65     470 5895.14     486
 7495.41  487.24 7537.46  475.13 7607.93  473.45 7645.97  445.31 7739.03  444.97
 7757.61  458.89 7795.31  469.98 7883.29  471.82 10210.8   474.6 11167.2     474
11209.74     470 11278.1     48413796.99     48414154.72     48614200.95     490
#Mann= 5 ,-1,0
 2123.13    .055       0 4034.65     .05       0 5671.72     .07       0
 7607.93     .05       0 7883.29     .05       0
#XS Ineff= 1 ,-1
    4300    5100     468
Permanent Ineff=
       T
Bank Sta=7607.93,7883.29
XS Rating Curve= 0 ,0
Exp/Cntr=0.3,0.1

Type RM Length L Ch R = 1 ,133770  ,223,233,366
BEGIN DESCRIPTION:
Kimley-Horn updated cross section based on on-ground survey and proposed grading for Bell South Airfiled property and TNRIS 2009 LiDAR offsite. Channel flowline interpolated from effective model. (KH, 2017) *CDC Approximated Cross Section*
--------------------------------------------------------
CDC FW121713-1 Revised West Village Creek Quicksilver Pad Site. Cross-section 133537 - 133770.  Modification of CDC FW022811-1
Proposed raised storage pad with As-built gas pad and floodplain storage site on ROB.
END DESCRIPTION:
XS GIS Cut Line= 6
  2386093.242911 6980100.0657095 2386143.5895918 6974532.8513565
 2386214.9862062 6971139.0165475 2386246.2321702 6969415.2808641
 2386313.9411517 6968384.0209919  2386365.507642 6965190.8051483
#Sta/Elev= 30
 2121.03     477 2165.14     464  4038.3  471.91 4765.89   462.8 5043.55   462.7
 5076.88   470.7 5230.58  469.12  5293.6  474.72 5666.69  470.76 5814.55     468
 5895.14     486 7495.41  487.24 7537.46  475.13 7607.93  473.45 7645.97  445.31
 7739.03  444.97 7757.61  458.89 7795.31  469.98 7883.29  471.82 8537.75     468
10040.44  473.7510040.45   480.510282.75   480.510282.76  473.56   10297  473.52
   10795   473.411159.66     47211214.69     48413796.99     48414200.95     490
#Mann= 9 ,-1,0
 2121.03    .055       0  4038.3     .05       0 5666.69     .07       0
7607.931     .05       0 7883.29     .05       010040.44    .023       0
10282.76    .045       0   10297    .023       0   10795     .05       0
#XS Ineff= 2 ,-1
    4300    5100     468    8210 10210.9  473.75
Permanent Ineff=
       T       T
Bank Sta=7607.93,7883.29
XS Rating Curve= 0 ,0
Exp/Cntr=0.3,0.1

Type RM Length L Ch R = 1 ,133537  ,261,38,24
BEGIN DESCRIPTION:
Kimley-Horn updated cross section based on on-ground survey and proposed grading for Bell South Airfiled property and TNRIS 2009 LiDAR offsite. Channel flowline interpolated from effective model. (KH, 2017)
*CDC Approximated Cross Section*
----------------------------
CDC FW121713-1 Revised West Village Creek Quicksilver Pad Site. Located in ROB. Cross-section 133537 - 133770
Modification of CDC FW022811-1
Proposed raised storage pad with as-built gas pad on ROB.
------------------------------------
END DESCRIPTION:
XS GIS Cut Line= 4
  2386145.723066 6980069.9637047  2386239.473066 6972601.4307186
 2386341.4695938  6968393.531413 2386393.5529271 6965107.9411353
#Sta/Elev= 30
 2098.35     477 2148.92     463 2180.87     468  4069.8  471.35 4923.96  469.68
 4970.97  462.59 5002.53  462.77 5029.26   471.2 5639.77  471.32 5682.87     472
 5744.07     486 7417.95  487.05 7462.83  474.12 7551.79  472.05 7645.48  444.97
 7715.47  444.95 7756.01  464.27 7897.13  472.91 10048.5  472.8710048.51   480.5
 10108.5   480.510108.51  472.85   10293   472.9   10805  474.49   10805   473.7
10941.07     47410997.15     48011021.15     48814055.12     48814989.83   498.8
#Mann= 9 ,-1,0
 2098.35     .07       0  4069.8     .05       0 5639.77     .07       0
 7551.79     .05       0 7897.13     .05       0 10048.5    .023       0
10108.51    .045       0   10293    .023       0   10805     .05       0
#XS Ineff= 1 ,-1
    4900    5050     468
Permanent Ineff=
       T
Bank Sta=7551.79,7897.13
XS Rating Curve= 0 ,0
Exp/Cntr=0.3,0.1

Type RM Length L Ch R = 1 ,133499  ,86,86,86
BEGIN DESCRIPTION:
Kimley-Horn updated cross section based on on-ground survey and proposed grading for Bell South Airfiled property and TNRIS 2009 LiDAR offsite. Channel flowline interpolated from effective model. (KH, 2017)
---------------------------------------------------------------------
CDC FW080317-1 Bell South Airfield
Cross-sections 133499 - 142669
---------------------------------------------------------------------
END DESCRIPTION:
XS GIS Cut Line= 4
  2386162.529044 6980068.8666784 2386251.1221572 6972726.1526477
 2386352.4676433 6968683.2273005 2386411.4954211 6965099.8939671
#Sta/Elev= 30
 3096.82     477 3140.73     463 3158.79     463 3174.46     468 4971.79     468
 5073.75   471.2 5354.44  468.33  5945.2  470.09 5967.64  462.64 5989.61  462.72
 6019.76  471.28 6194.57  469.82 6255.82  474.23 6634.09  471.46    6700   470.2
    6700   487.6    8250   487.6    8267   480.5    8320   473.2    8468   471.8
    8575   449.7    8595     440    8635     444    8759   470.7    8870   473.9
   11861   472.9   11947   476.4   11967   479.6   11980     488   11986     488
#Mann= 5 ,-1,0
 3096.82     .07       0 5073.75     .05       0 6634.09     .07       0
    8468     .05       0    8759     .07       0
#XS Ineff= 1 ,-1
    5950    6015     468
Permanent Ineff=
       T
Bank Sta=8468,8759
XS Rating Curve= 0 ,0
Exp/Cntr=0.3,0.1

Type RM Length L Ch R = 1 ,133413  ,1,1,1
BEGIN DESCRIPTION:
This cross section corresponds to cross section 133413 of the non-georeferenced CDC model which was the source of this model.
END DESCRIPTION:
XS GIS Cut Line= 6
 2386234.19991786980007.39418702 2386317.1890151 6974496.9877709
 2386342.4432297 6972847.0117402 2386367.6981004 6971887.3309167
 2386435.0440943 6969151.4006931 2386436.5245987 6969061.3855018
#Sta/Elev= 30
    1038     500    3088   477.9    3131   467.4    4536   469.2    4886   467.7
    5091   468.7    5139   471.2    5738   469.2    5808   471.2    6016   469.7
    6020   471.8    6535     472    6700   470.2    6700   487.6    8250   487.6
    8250   482.2    8320   473.2    8468   471.8    8504   466.7    8575   449.7
    8595     440    8635     444    8759   470.7    8870   473.9   11770   474.4
   11861   472.9   11947   476.4   11967   479.6   11980   483.8   11986     488
#Mann= 3 ,0,0
    1038     .07       0    8468    .055       0    8759    .075       0
Bank Sta=8468,8759
XS Rating Curve= 0 ,0
Exp/Cntr=0.3,0.1

Type RM Length L Ch R = 1 ,133412  ,43,43,43
BEGIN DESCRIPTION:
This cross section corresponds to cross section 133412 of the non-georeferenced CDC model which was the source of this model.
END DESCRIPTION:
XS GIS Cut Line= 6
 2386232.96956946980154.93454859 2386318.1798267 6974497.0448574
 2386343.4340413 6972847.0688267 2386368.6889121 6971887.3880032
  2386436.034906 6969151.4577796 2386437.6058582  6969055.943332
#Sta/Elev= 30
     839     532    3039   479.4    3208   470.3    3323   468.7    5026   469.9
    5649   472.4    6700   471.9    6700   487.6    8150   487.6    8150   474.2
    8400   481.3    8400   478.5    8417     470    8431     470    8454     445
    8487     440    8510     440    8535     445    8558     460    8575     467
    8633     469    8653     472    8664     477    8664   482.5    8932   475.2
   11802   474.6   11855   473.3   11883   476.4   11898   476.3   11940     488
#Mann= 3 ,0,0
     839     .07       0    8400    .055       0    8664    .075       0
Bank Sta=8400,8664
XS Rating Curve= 0 ,0
Exp/Cntr=0.3,0.1

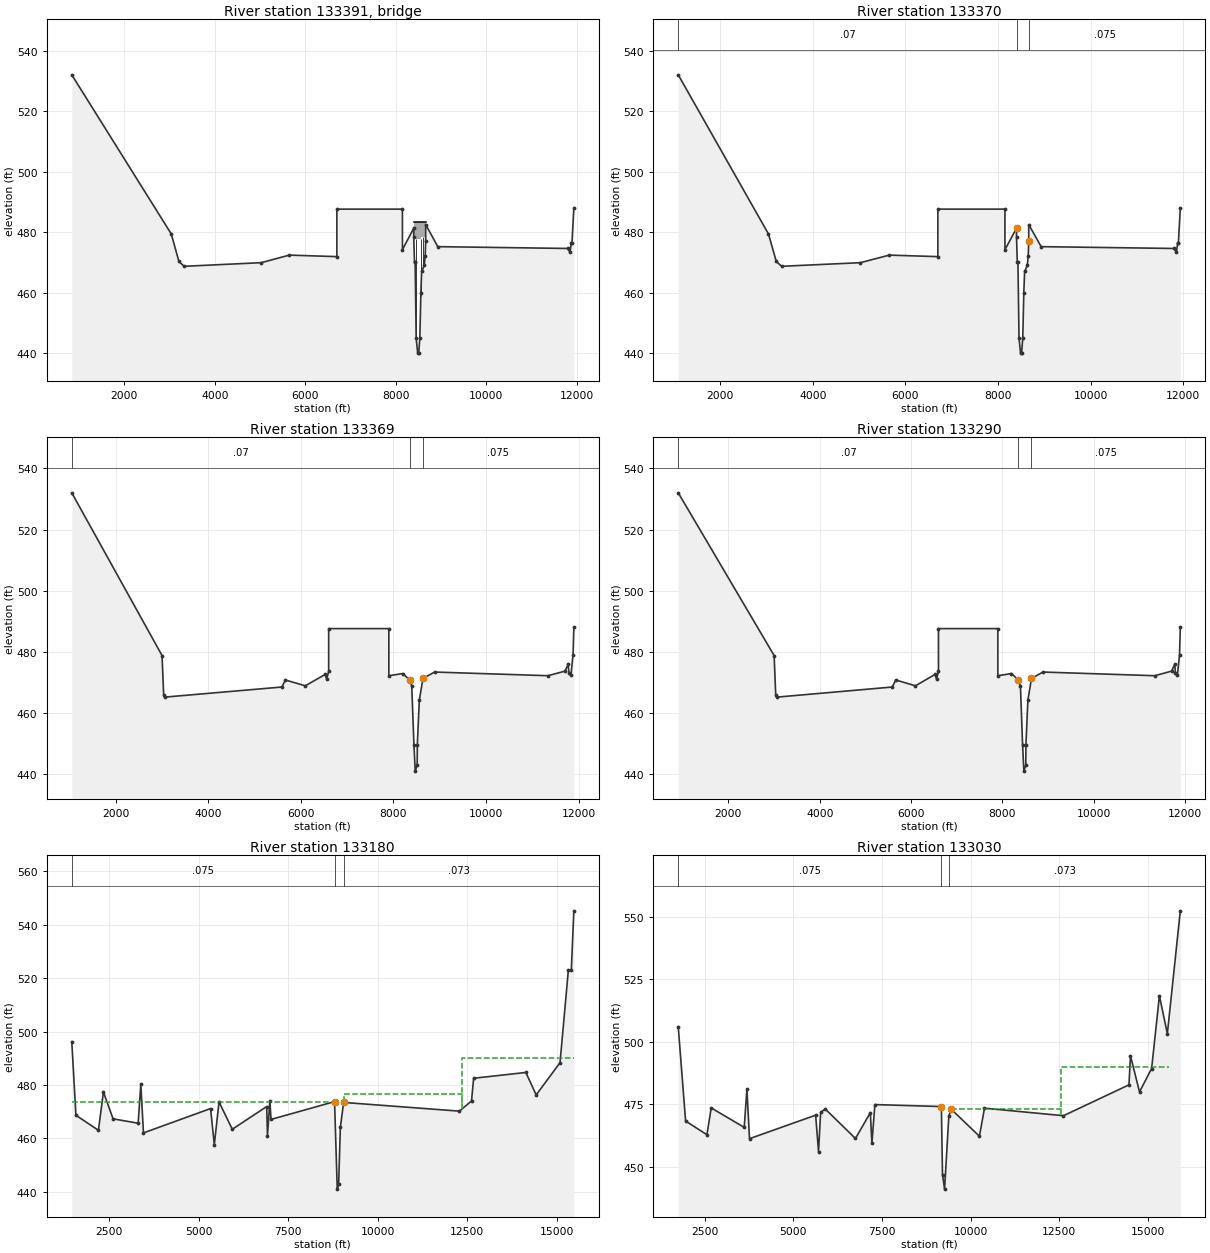
Type RM Length L Ch R = 3 ,133391  ,,,
BEGIN DESCRIPTION:
Arlington-Bedford Road
END DESCRIPTION:
Node Name=Arl. Bedford Roa
Bridge Culvert--1,0,-1,-1, 0
Deck Dist Width WeirC Skew NumUp NumDn MinLoCord MaxHiCord MaxSubmerge Is_Ogee
1,40,2.6,0, 11, 11, , , 0.95, 0, ,,,
    8400    8454    8454    8457    8487    8535    8555    8558    8558    8610
    8664
   483.3   483.3   483.3   483.3   483.3   483.3   483.3   483.3   483.3   483.3
   483.3
   478.5   478.5   477.6   477.6   477.6   477.6   477.6   477.6   478.5   478.5
   478.5
    8400    8454    8454    8457    8487    8535    8555    8558    8558    8610
    8664
   483.3   483.3   483.3   483.3   483.3   483.3   483.3   483.3   483.3   483.3
   483.3
   478.5   478.5   477.6   477.6   477.6   477.6   477.6   477.6   478.5   478.5
   478.5
Pier Skew, UpSta & Num, DnSta & Num=  ,8456.5, 2 ,8456.5, 2 , 0 , 0 , 0 ,,
       3       3
     440     480
       3       3
     440     480
Pier Skew, UpSta & Num, DnSta & Num=  ,8556.5, 2 ,8556.5, 2 , 0 , 0 , 0 ,,
       3       3
     440     480
       3       3
     440     480
Pier Skew, UpSta & Num, DnSta & Num=  ,8612.5, 2 ,8612.5, 2 , 0 , 0 , 0 ,,
       3       3
     440     480
       3       3
     440     480
BR Coef= 1 , 0 , 0 ,1.05, 0 ,,,0.8,-1,0.5,1,
WSPro=,,,, 1 ,,,, 0 ,,,, 0 ,,,,-1 ,-1 ,-1 , 0 , 0 , 0 , 0 , 0
BC Design=,, 0 ,, 0 ,,,,,,
BC HTab HWMax=488
BC Use User HTab Curves=0
BC User HTab FreeFlow(D)= 0

Type RM Length L Ch R = 1 ,133370  ,2,2,2
BEGIN DESCRIPTION:
This cross section corresponds to cross section 133370 of the non-georeferenced CDC model which was the source of this model.
END DESCRIPTION:
XS GIS Cut Line= 6
2386290.552566956979930.75752952 2386321.7441241 6977273.9897628
 2386355.4159727 6974529.6409208 2386389.0891337 6972845.9907448
 2386405.9260423 6971962.0748617 2386466.3023447  6969081.276845
#Sta/Elev= 30
    1089     532    3039   479.4    3208   470.3    3323   468.7    5026   469.9
    5649   472.4    6700   471.9    6700   487.6    8150   487.6    8150   474.2
    8400   481.3    8400   478.5    8417     470    8431     470    8454     445
    8487     440    8510     440    8535     445    8558     460    8575     467
    8633     469    8653     472    8664     477    8664   482.5    8932   475.2
   11802   474.6   11855   473.3   11883   476.4   11898   476.3   11940     488
#Mann= 3 ,0,0
    1089     .07       0    8400    .055       0    8664    .075       0
Bank Sta=8400,8664
XS Rating Curve= 0 ,0
Exp/Cntr=0.3,0.1

Type RM Length L Ch R = 1 ,133369  ,79,79,79
BEGIN DESCRIPTION:
This cross section corresponds to cross section 133369 of the non-georeferenced CDC model which was the source of this model.
END DESCRIPTION:
XS GIS Cut Line= 6
     2386292.894     6979908.412     2386323.827     6977273.643
     2386357.499     6974529.294     2386391.172     6972845.644
     2386408.009     6971961.728     2386468.556      6969064.93
#Sta/Elev= 30
    1051     532    3001   478.8    3036   465.9    3060   465.2    5588   468.5
    5666   470.8    6096   468.9    6522   472.6    6557   471.1    6600   473.6
    6600   487.6    7900   487.6    7900   472.2    8199   472.9    8351   470.8
    8395   468.8    8442   449.6    8470     441    8512     443    8515   449.6
    8558   464.2    8637   471.3    8888   473.4   11338   472.2   11704   473.7
   11773   475.9   11790   473.2   11833   472.4   11879   479.1   11896     488
#Mann= 3 ,0,0
    1051     .07       0    8351    .055       0    8637    .075       0
Bank Sta=8351,8637
XS Rating Curve= 0 ,0
Exp/Cntr=0.3,0.1

Type RM Length L Ch R = 1 ,133290  ,100,110,361.7
BEGIN DESCRIPTION:
This cross section corresponds to cross section 133290 of the non-georeferenced CDC model which was the source of this model.
END DESCRIPTION:
XS GIS Cut Line= 6
      2386395.58        6980019.   2386392.53101  6977917.407739
   2386433.70387   6974534.15207   2386467.37703   6972850.50189
   2386484.21394   6971966.58601 2386545.6356243 6969023.7965306
#Sta/Elev= 30
     901     532    3001   478.8    3036   465.9    3060   465.2    5588   468.5
    5666   470.8    6096   468.9    6522   472.6    6557   471.1    6600   473.6
    6600   487.6    7900   487.6    7900   472.2    8199   472.9    8351   470.8
    8395   468.8    8442   449.6    8470     441    8512     443    8515   449.6
    8558   464.2    8637   471.3    8888   473.4   11338   472.2   11704   473.7
   11773   475.9   11790   473.2   11833   472.4   11879   479.1   11896     488
#Mann= 3 ,0,0
     901     .07       0    8351    .055       0    8637    .075       0
Bank Sta=8351,8637
XS Rating Curve= 0 ,0
Exp/Cntr=0.3,0.1

Type RM Length L Ch R = 1 ,133180  ,73.6,150,227.3
BEGIN DESCRIPTION:
Additional XS1 (2009 TNRIS Lidar and Dec 2013
END DESCRIPTION:
XS GIS Cut Line= 6
     2386494.623     6979895.895     2386519.257     6972784.035
     2386599.345     6972583.816     2386573.316     6972295.501
     2387031.779     6969158.968      2387052.46     6965806.077
#Sta/Elev= 30
    1455496.22121570.995468.6576 2198.97463.02072338.965 477.3492608.954467.3122
3308.927 465.6713382.924480.26463456.921462.04365330.847 471.1615434.842457.6559
5566.837 473.6545936.823 463.4116898.785471.91896918.784460.95246986.781474.0285
 7018.78467.0904 8792.74473.7635 8868.33     441 8906.99   442.88954.529464.1352
 9046.44473.450812278.03470.192612617.13     47412676.62   482.5 14134.2  484.67
14422.98476.275315088.63488.336415320.51522.871715404.47523.107115474.43545.1738
#Mann= 3 ,-1,0
    1455    .075       0 8792.74    .053       0 9046.44    .073       0
#XS Ineff= 3 ,-1
    1455    8757  473.77 9046.4412361.54  476.4512361.5415474.43     490
Permanent Ineff=
       F       F       F
Bank Sta=8792.74,9046.44
XS Rating Curve= 0 ,0
Exp/Cntr=0.3,0.1

Type RM Length L Ch R = 1 ,133030  ,76.4,1563,651
BEGIN DESCRIPTION:
Additional XS2 (2009 TNRIS Lidar and Dec 2013
CDC ARL 092221-01 Childress South Addition
Cross-section 1333030 - 133180
Project in ROB.
END DESCRIPTION:
XS GIS Cut Line= 6
     2386603.019     6979891.107     2386586.083     6972928.174
     2386760.874     6972495.701     2386719.428      6972329.92
     2387348.324     6969144.851     2387379.622     6965908.011
#Sta/Elev= 30
    1750505.9627    1958468.2269    2560 462.763    2680473.4837    3612465.7028
    3688480.9151    3762461.1743 5627.99470.5717 5709.99455.9846 5767.99471.6585
 5897.99473.0647 6751.99461.2542 7171.99   471.6 7215.99459.3342 7299.99474.8077
 9176.57474.0221 9208.47446.8228 9266.67     441 9387.94470.3887 9457.93472.9053
10249.75462.162710393.72473.368312623.24470.364414471.07   482.714513.76  494.36
14768.63479.875415110.53 489.23515330.46518.307515554.39503.155515920.28552.2887
#Mann= 3 ,-1,0
    1750    .075       0 9176.57    .053       0 9387.94    .073       0
#XS Ineff= 3 ,-1
    1750 9176.57  474.02 9457.9312563.93  472.9112563.9315597.55     490
Permanent Ineff=
       F       F       F
Bank Sta=9176.57,9457.93
XS Rating Curve= 0 ,0
Exp/Cntr=0.3,0.1