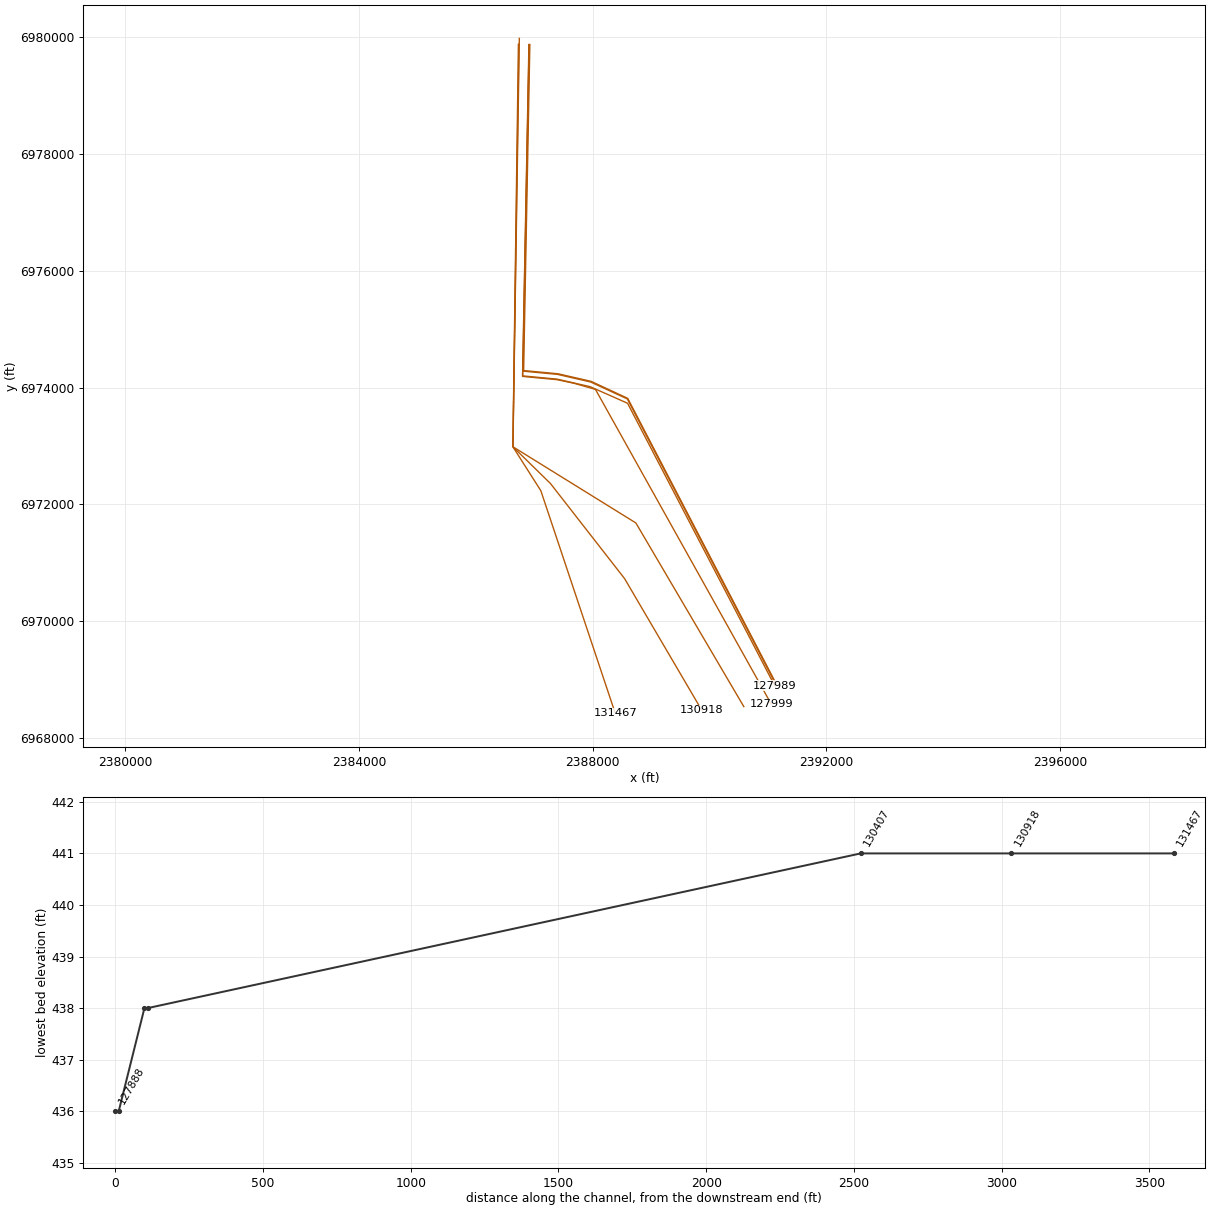
HEC-RAS study CDC_Consolidated_Model.prj: Upper Trinity CDC Consolidated Model

--- CDC_Consolidated_Model.g13 (geometry) --- (continued)

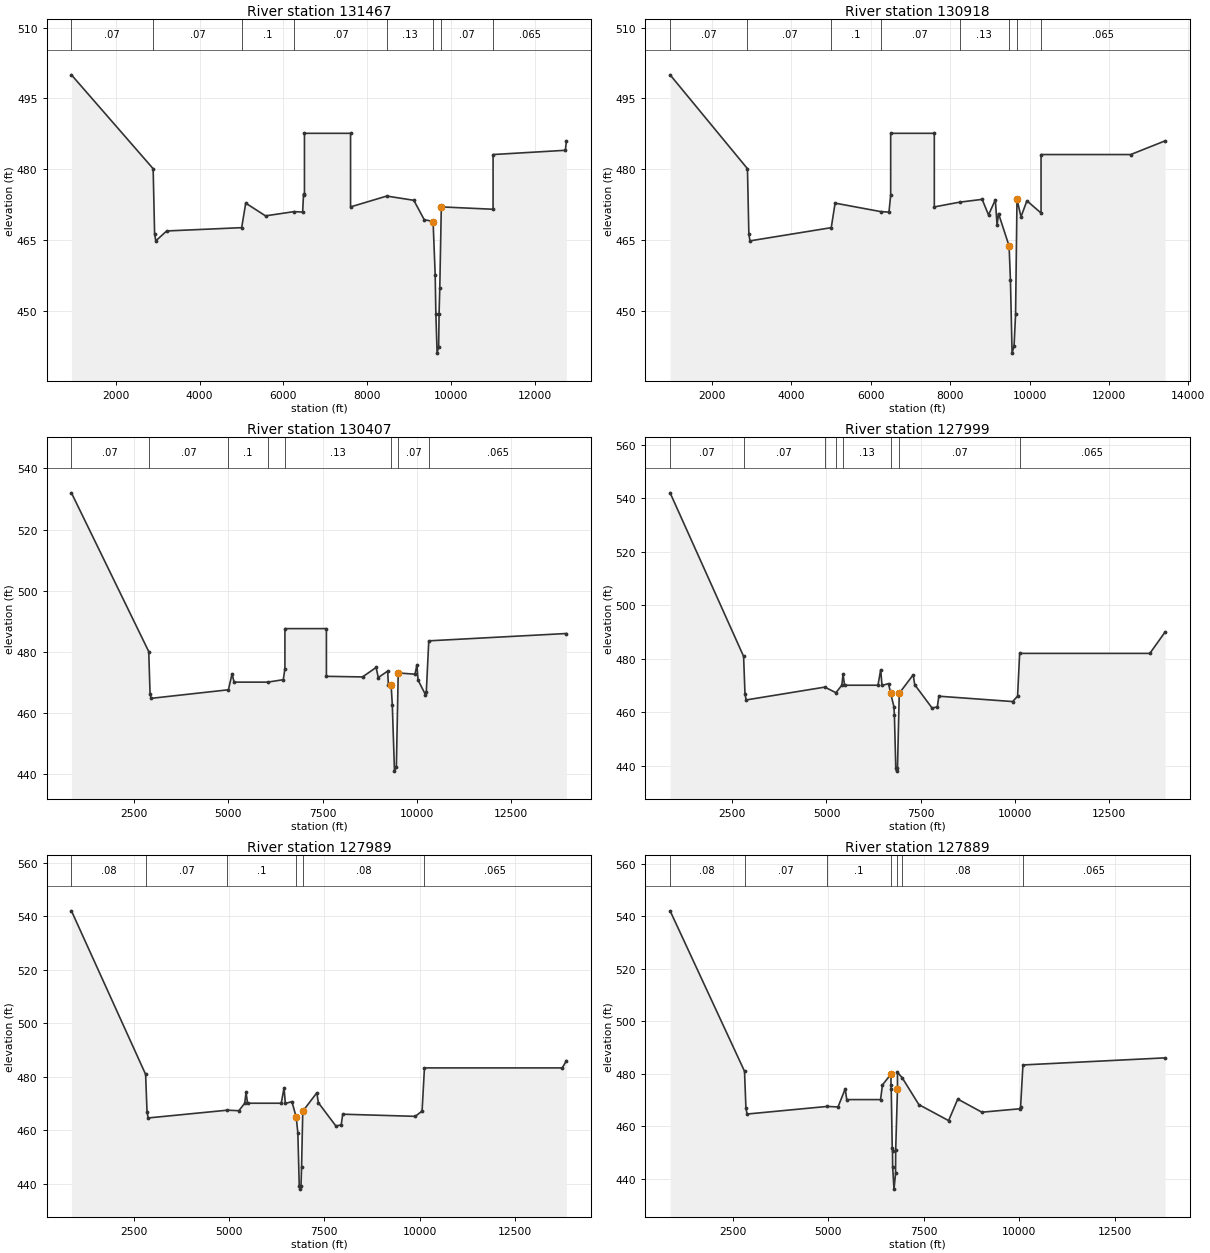
Type RM Length L Ch R = 1 ,131467  ,1,549,721
BEGIN DESCRIPTION:
This cross section corresponds to cross section 131467 of the non-georeferenced CDC model which was the source of this model.
---------------------------------------------------------------------
CDC ARL021511-1 GREENMAN GAS WELL SITE
LOCATED ADJACENT TO VILLAGE CREEK STP IN INEFFECTIVE FLOW AREA.  SITE LOCATED BETWEEN
CROSS-SECTION 131467 AND 133290.
----------------------
CDC ARL071405-1 SVC Park Highlands, LTD.
In ROB beyond eff. flow line - storage mitigation area d/s SH 360 d/s cross-sect 78083.
END DESCRIPTION:
XS GIS Cut Line= 6
2386728.967360536979883.18641281      2386702.21      6977933.37
   2386634.33897   6972987.58889   2387112.96203   6972235.61303
 2388136.8534676 6969169.68392532388387.094605446968420.36465227
#Sta/Elev= 30
     940     500    2890   480.1    2925   466.3    2953   464.8    3213   466.9
    5002   467.6    5099   472.8    5571   470.1    6252     471    6457   470.9
    6478   474.7    6500   474.5    6500   487.6    7600   487.6    7600     472
    8464   474.3    9109   473.4    9357   469.3    9569   468.9    9619   457.6
    9635   449.4    9665     441    9702   442.4    9712   449.4    9729   454.9
    9765     472   11000   471.5   11000   483.1   12725     484   12750     486
#Mann= 8 ,-1,0
     940     .07       0    2890     .07       0    5002      .1       0
    6252     .07       0    8464     .13       0    9569     .05       0
    9765     .07       0   11000    .065       0
#XS Ineff= 2 , 0
                           12725
Permanent Ineff=
       F       F
Bank Sta=9569,9765
XS Rating Curve= 0 ,0
Exp/Cntr=0.3,0.1

Type RM Length L Ch R = 1 ,130918  ,1,510,699
BEGIN DESCRIPTION:
This cross section corresponds to cross section 130918 of the non-georeferenced CDC model which was the source of this model.
END DESCRIPTION:
XS GIS Cut Line= 6
2386737.563770176979884.22088967      2386634.99      6972987.54
   2387277.15396   6972359.02584    2388545.9339   6970729.97595
   2389430.32091   6969220.875952389868.684603556968472.86106233
#Sta/Elev= 30
     940     500    2890   480.1    2925   466.3    2953   464.8    5002   467.6
    5099   472.8    6252     471    6457   470.9    6500   474.5    6500   487.6
    7600   487.6    7600     472    8235     473    8806   473.6    8966   470.3
    9138   473.5    9182   468.1    9218   470.6    9485   463.7    9519   456.4
    9560     441    9610   442.5    9648   449.2    9684   473.6    9785   469.9
    9934   473.3   10290   470.7   10290   483.1   12550   483.1   13417     486
#Mann= 8 ,-1,0
     940     .07       0    2890     .07       0    5002      .1       0
    6252     .07       0    8235     .13       0    9485     .05       0
    9684     .07       0   10290    .065       0
#XS Ineff= 2 , 0
                           12550
Permanent Ineff=
       F       F
Bank Sta=9485,9684
XS Rating Curve= 0 ,0
Exp/Cntr=0.3,0.1

Type RM Length L Ch R = 1 ,130407  ,170,2413,1045
BEGIN DESCRIPTION:
This cross section corresponds to cross section 130407 of the non-georeferenced CDC model which was the source of this model.
END DESCRIPTION:
XS GIS Cut Line= 6
2386745.252862386979985.05101815  2386713.211418 6977935.3014369
      2386635.87      6972987.63    2388739.7511   6971682.79392
   2390208.02999   6969181.893092390587.243143516968535.98413031
#Sta/Elev= 30
     840     532    2890   480.1    2925   466.3    2953   464.8    5002   467.6
    5099   472.8    5153   470.1    6047   470.1    6457   470.9    6500   474.5
    6500   487.6    7600   487.6    7600     472    8558   471.8    8918   474.9
    8975   471.6    9223   473.7    9245     469    9315   469.3    9347   462.7
    9405     441    9455   442.5    9504   473.1    9949   472.7   10000   475.8
   10029   470.8   10226     466   10249     467   10314   483.6   13963     486
#Mann= 8 ,-1,0
     840     .07       0    2890     .07       0    5002      .1       0
    6047     .07       0    6500     .13       0    9315    .055       0
    9504     .07       0   10314    .065       0
#XS Ineff= 2 , 0
                           13214
Permanent Ineff=
       F       F
Bank Sta=9315,9504
XS Rating Curve= 0 ,0
Exp/Cntr=0.3,0.1

Type RM Length L Ch R = 1 ,127999  ,11,11,384
BEGIN DESCRIPTION:
This cross section corresponds to cross section 127999 of the non-georeferenced CDC model which was the source of this model.
END DESCRIPTION:
XS GIS Cut Line= 6
2386908.972737256979877.95741094   2386799.79894   6974193.06089
   2387388.91489   6974137.69387   2387682.10492   6974075.23107
      2388048.19      6973970.41 2391057.2090427 6968578.4097208
#Sta/Elev= 30
     852     542    2802   480.9    2839   466.9    2869   464.6    4958   469.4
    5252   467.3    5407   470.1    5441   474.2    5481   470.1    6367   470.1
    6440   475.9    6474     470    6647   470.7    6702   467.2    6790   462.1
    6803     459    6840     439    6860     438    6885     439    6932   467.1
    7302     474    7342   470.3    7802   461.6    7942     462    7982     466
    9940     464   10071     466   10126     482 13580.5     482   13985     490
#Mann= 8 ,-1,0
     852     .07       0    2802     .07       0    4958      .1       0
    5252     .07       0    5441     .13       0    6702    .055       0
    6932     .07       0   10126    .065       0
Bank Sta=6702,6932
XS Rating Curve= 0 ,0
Exp/Cntr=0.3,0.1

Type RM Length L Ch R = 1 ,127989  ,1,87,87
BEGIN DESCRIPTION:
This cross section corresponds to cross section 127989 of the non-georeferenced CDC model which was the source of this model.
END DESCRIPTION:
XS GIS Cut Line= 6
2386912.371899496979877.78530247 2386803.0685215  6974202.068684
 2387392.1844715  6974146.701664 2387957.8024315  6974016.957834
 2388597.7926215  6973733.1178442391117.582931756968891.08217855
#Sta/Elev= 30
     852     542    2802   480.9    2839   466.9    2869   464.6    4950   467.5
    5252   467.3    5407   470.1    5441   474.2    5481   470.1    6367   470.1
    6440   475.9    6474     470    6647   470.7    6760   464.9    6803     459
    6840     439    6860     438    6885     439    6901   446.3    6932   467.1
    7302     474    7342   470.3    7802   461.6    7942     462    7982     466
    9890   465.2   10068   467.2   10130   483.3   13752   483.3   13861     486
#Mann= 6 ,-1,0
     852     .08       0    2802     .07       0    4950      .1       0
    6760     .05       0    6932     .08       0   10130    .065       0
#XS Ineff= 2 , 0
                           13752
Permanent Ineff=
       F       F
Bank Sta=6760,6932
XS Rating Curve= 0 ,0
Exp/Cntr=0.3,0.1

Type RM Length L Ch R = 1 ,127889  ,12,12,12
BEGIN DESCRIPTION:
This cross section corresponds to cross section 127889 of the non-georeferenced CDC model which was the source of this model.
END DESCRIPTION:
XS GIS Cut Line= 6
2386915.380638786979877.47995426 2386808.3232034 6974283.3612296
 2387397.4391512 6974227.9942144 2387963.0571144 6974098.2503794
      2388593.48      6973807.732391132.398256476968920.98900988
#Sta/Elev= 30
     852     542    2802   480.9    2839   466.9    2869   464.6    4970   467.5
    5252   467.3    5441   474.2    5481   470.1    6367   470.1    6417   475.7
    6640   479.8    6640   475.5    6647     474    6673   451.5    6680   450.5
  6683.5   444.5    6719     436    6760     442  6763.5     451    6810     474
    6810   480.5    6935   478.4    7370   468.2    8150   462.1    8390   470.3
    9022   465.3   10011   466.6   10036   467.2   10098   483.3   13823     486
#Mann= 7 ,-1,0
     852     .08       0    2802     .07       0    4970      .1       0
    6640    .055       0    6810     .13       0    6935     .08       0
   10098    .065       0
#XS Ineff= 2 , 0
                           13720
Permanent Ineff=
       F       F
Bank Sta=6640,6810
XS Rating Curve= 0 ,0
Exp/Cntr=0.3,0.1

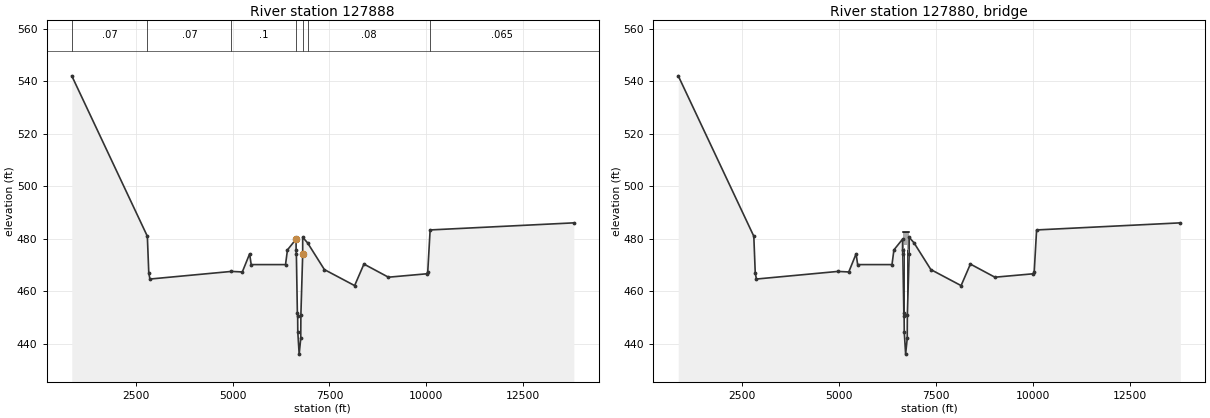
Type RM Length L Ch R = 1 ,127888  ,1,14,14
BEGIN DESCRIPTION:
This cross section corresponds to cross section 127888 of the non-georeferenced CDC model which was the source of this model.
END DESCRIPTION:
XS GIS Cut Line= 6
2386925.189568136979877.72399945 2386818.9094683 6974293.7191486
 2387408.0254161 6974238.3521333 2387973.6433793 6974108.6082983
      2388600.73      6973817.032391137.621004666968934.45215315
#Sta/Elev= 30
     852     542    2802   480.9    2839   466.9    2869   464.6    4970   467.5
    5252   467.3    5441   474.2    5481   470.1    6367   470.1    6417   475.7
    6640   479.8    6640   475.5    6647     474    6673   451.5    6680   450.5
  6683.5   444.5    6719     436    6760     442  6763.5     451    6810     474
    6810   480.5    6935   478.4    7370   468.2    8150   462.1    8390   470.3
    9022   465.3   10011   466.6   10036   467.2   10098   483.3   13806     486
#Mann= 7 ,-1,0
     852     .07       0    2802     .07       0    4970      .1       0
    6640    .055       0    6810     .13       0    6935     .08       0
   10098    .065       0
#XS Ineff= 2 , 0
                           13720
Permanent Ineff=
       F       F
Bank Sta=6640,6810
XS Rating Curve= 0 ,0
Exp/Cntr=0.3,0.1

Type RM Length L Ch R = 3 ,127880  ,,,
BEGIN DESCRIPTION:
Trammel-Davis Road
END DESCRIPTION:
Node Name=Trammel-Davis Ro
Bridge Culvert--1,0,-1,-1, 0
Deck Dist Width WeirC Skew NumUp NumDn MinLoCord MaxHiCord MaxSubmerge Is_Ogee
0.5,13,2.6,0, 8, 8, , , 0.95, 0, ,,,
    6640    6680  6683.5  6683.5    6760    6760  6763.5    6810
   482.7   482.7   482.7   482.7   482.7   482.7   482.7   482.7
   476.4   476.4   476.4   477.5   477.5   476.1   476.1   476.1
    6640    6680  6683.5  6683.5    6760    6760  6763.5    6810
   482.7   482.7   482.7   482.7   482.7   482.7   482.7   482.7
   476.4   476.4   476.4   477.5   477.5   476.1   476.1   476.1
Pier Skew, UpSta & Num, DnSta & Num=  ,6681.75, 2 ,6681.75, 2 , 0 , 0 , 0 ,,
     3.5     3.5
     440     480
     3.5     3.5
     440     480
Pier Skew, UpSta & Num, DnSta & Num=  ,6761.75, 2 ,6761.75, 2 , 0 , 0 , 0 ,,
     3.5     3.5
     440     480
     3.5     3.5
     440     480
BR Coef= 1 , 0 , 0 ,1.05, 0 ,,,0.8,-1,0.5,1,
WSPro=,,,, 1 ,,,, 0 ,,,, 0 ,,,,-1 ,-1 ,-1 , 0 , 0 , 0 , 0 , 0
BC Design=,, 0 ,, 0 ,,,,,,
BC HTab HWMax=483.3
BC Use User HTab Curves=0
BC User HTab FreeFlow(D)= 0