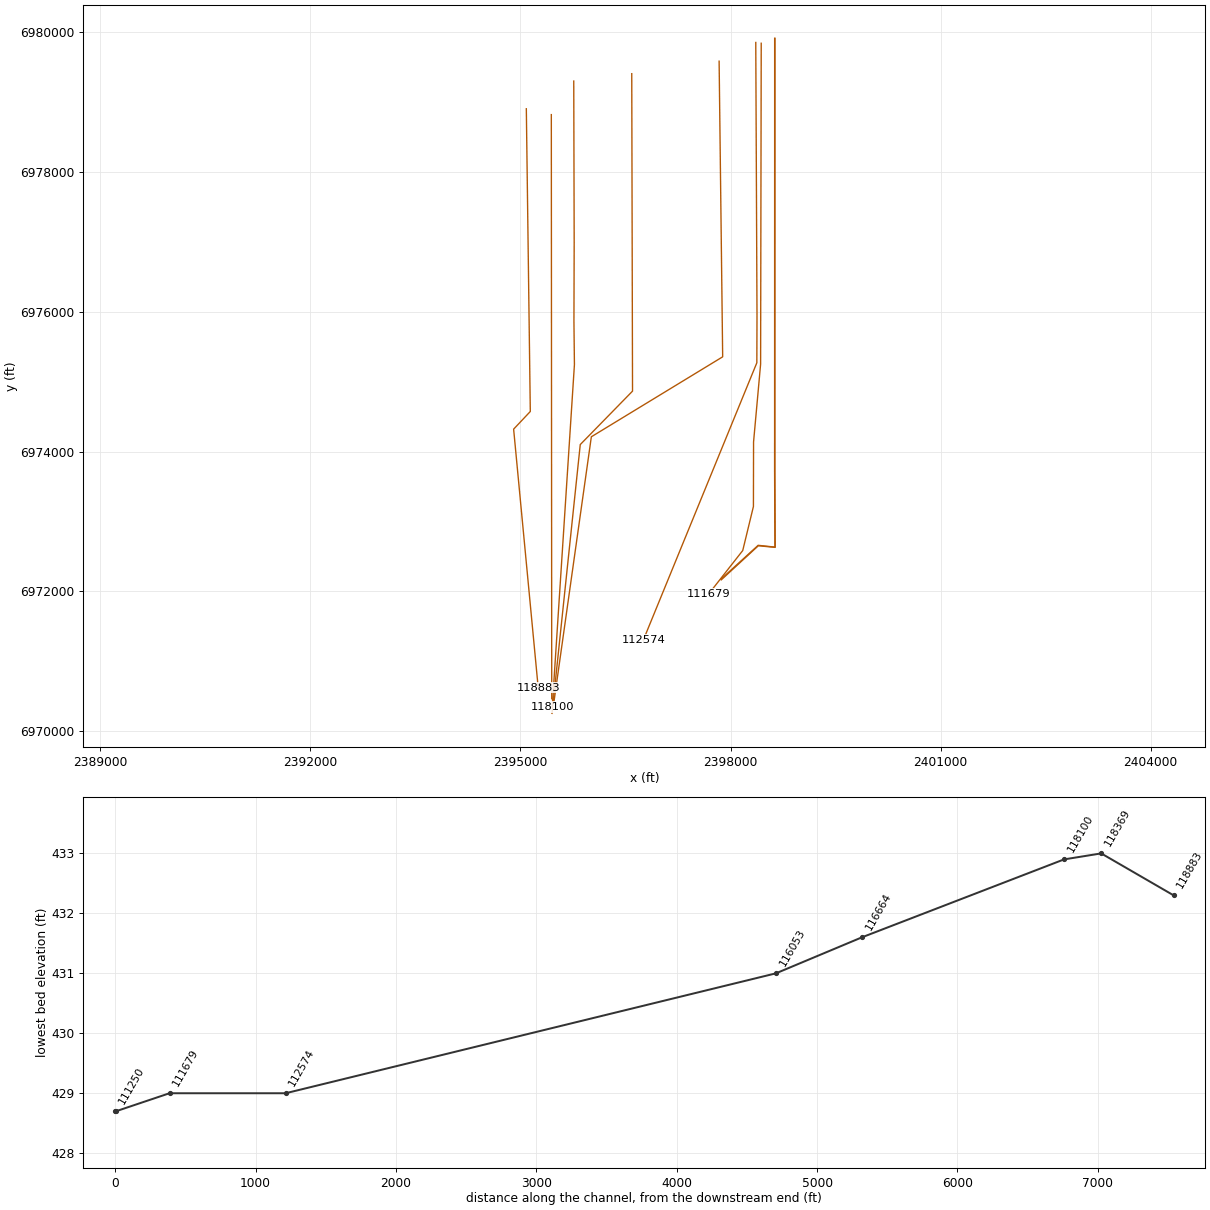
HEC-RAS study CDC_Consolidated_Model.prj: Upper Trinity CDC Consolidated Model

--- CDC_Consolidated_Model.g13 (geometry) --- (continued)

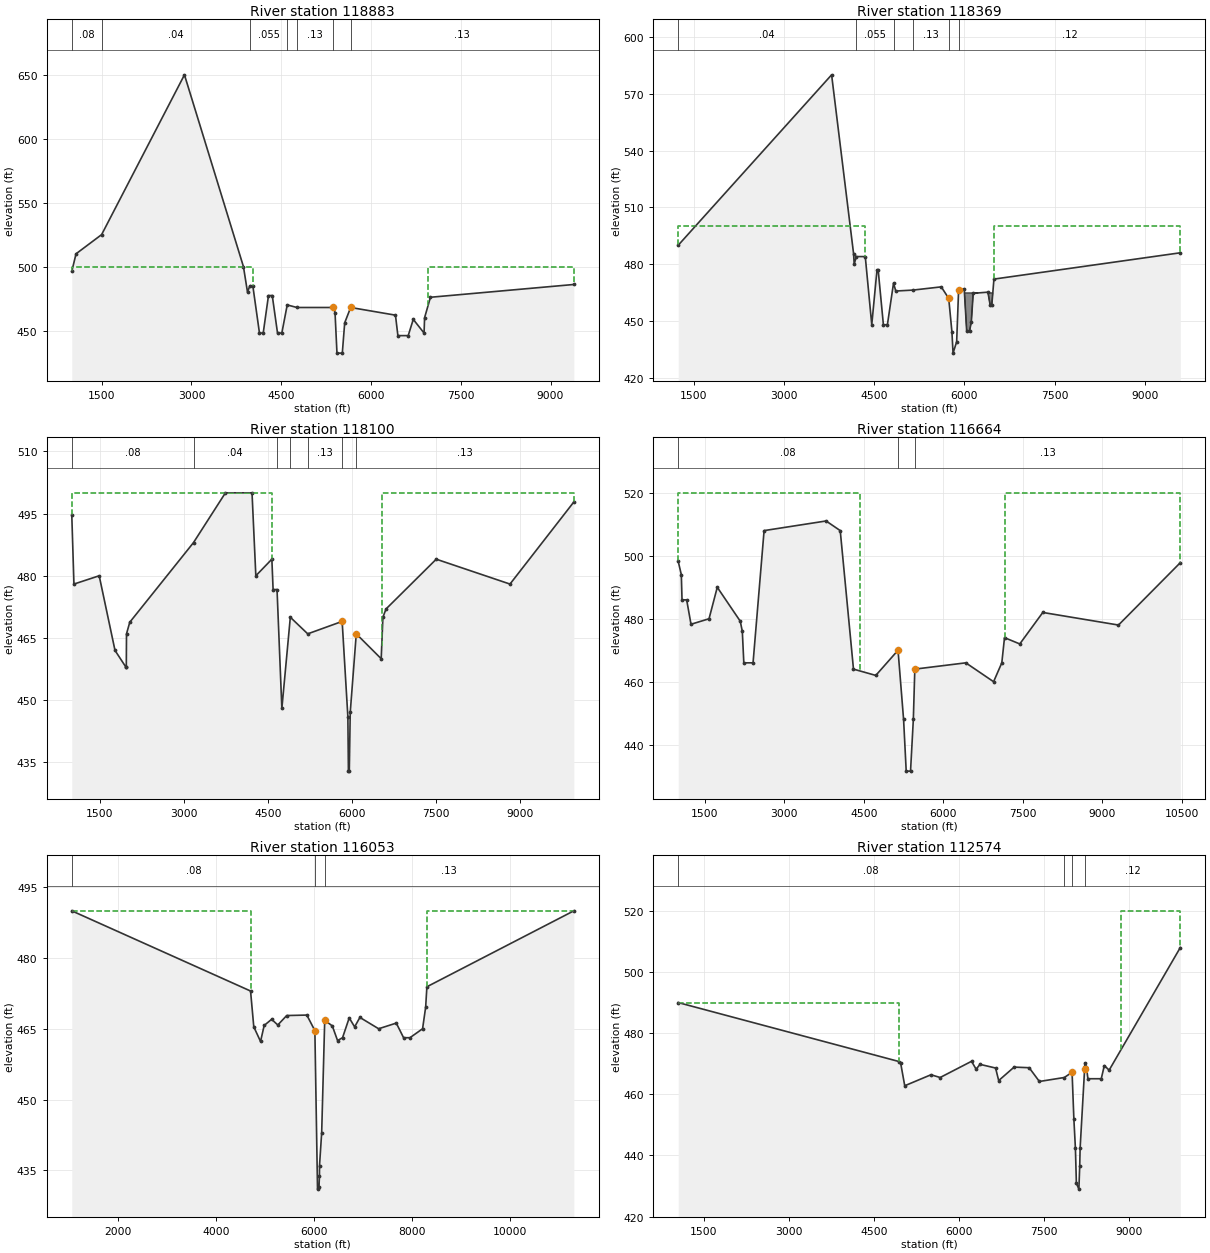
Type RM Length L Ch R = 1 ,118883  ,338,516,320
BEGIN DESCRIPTION:
This cross section corresponds to cross section 118883 of the non-georeferenced CDC model which was the source of this model.
END DESCRIPTION:
XS GIS Cut Line= 5
  2395083.250572  6978901.396929  2395083.604225 6978874.4376774
 2395140.0276686 6974573.2221985 2394901.8765701  6974320.704987
 2395252.8748838 6970623.5696647
#Sta/Elev= 30
    1000  496.19 1071.41     510 1498.73     525  2882.8     650  3868.4     500
  3936.4     480  3975.6     485 4025.26     485 4136.26     448    4199     448
    4287  477.34    4350  477.34    4438     448    4510     448    4600     470
 4763.26     468    5370     468    5399     464 5431.33   432.3 5520.52   432.3
 5560.42     456 5660.13     468 6408.77     462 6449.24     446 6621.78     446
 6706.18   458.7 6886.76     448 6895.43     460 6993.17     476 9389.41     486
#Mann= 7 ,-1,0
    1000     .08       0 1498.73     .04       0  3975.6    .055       0
    4600     .08       0 4763.26     .13       0    5370     .06       0
 5660.13     .13       0
#XS Ineff= 2 , 0
         4025.26     500    6951             500
Permanent Ineff=
       F       T
#Block Obstruct= 2 , 0
                            6000           464.8
Bank Sta=5370,5660.13
XS Rating Curve= 0 ,0
Exp/Cntr=0.3,0.1

Type RM Length L Ch R = 1 ,118369  ,257,265,61
BEGIN DESCRIPTION:
This cross section corresponds to cross section 118369 of the non-georeferenced CDC model which was the source of this model.
END DESCRIPTION:
XS GIS Cut Line= 6
  2395440.313041 6978817.8179206 2395443.7717583 6973819.8191173
 2395443.8824815 6973659.8191556 2395443.8963219 6973639.8191604
 2395443.9032421 6973629.81916282395446.092103376970466.81992018
#Sta/Elev= 30
    1239     490    3790     580  4155.6   485.5  4165.6     480 4200.75     484
 4349.89     484 4457.89     448 4544.62  476.91 4564.62  476.91  4651.4     448
    4718     448    4820     470    4857   465.8    5144   466.3    5614     468
    5738   461.9    5791   444.3    5810     433    5870     439    5902   466.1
    5996   466.9    6037   444.6    6085   444.7    6114   449.6    6145   464.6
    6390   465.2    6428   458.2    6454   458.2    6490   472.1    9590     486
#Mann= 6 ,-1,0
    1239     .04       0 4200.75    .055       0    4820     .08       0
    5144     .13       0    5738     .06       0    5902     .12       0
#XS Ineff= 2 , 0
         4349.89     500    6490             500
Permanent Ineff=
       T       F
#Block Obstruct= 1 ,-1
    5996 6489.99   464.8
Bank Sta=5738,5902
XS Rating Curve= 0 ,0
Exp/Cntr=0.3,0.1

Type RM Length L Ch R = 1 ,118100  ,1399,1440,330
BEGIN DESCRIPTION:
This cross section corresponds to cross section 118100 of the non-georeferenced CDC model which was the source of this model.
END DESCRIPTION:
XS GIS Cut Line= 6
  2395760.713111 6979297.4298475 2395766.7639479 6976982.2934958
 2395763.2915139 6975860.7658832 2395770.2360538 6975242.7103608
 2395463.3783998 6970504.2119638      2395452.19      6970348.02
#Sta/Elev= 30
    1000  494.75 1038.75     478 1489.33     480 1771.69     462 1965.04     458
 1973.14     458 1976.69     466 2035.09   468.8  3172.3     488  3742.2     500
  4216.6     500  4284.6     480  4570.7     484 4592.66  476.68  4662.9  476.68
    4749     448    4900     470    5211     466    5825     469 5927.01     446
 5936.54   432.9 5952.36   432.9 5969.27  447.08 6076.95     466  6521.7     460
 6552.17     470 6608.18     472    7504     484 8820.07     478 9959.48   497.8
#Mann= 7 ,-1,0
    1000     .08       0  3172.3     .04       0  4662.9    .055       0
    4900     .08       0    5211     .13       0    5825     .06       0
 6076.95     .13       0
#XS Ineff= 2 , 0
            4565     500    6531             500
Permanent Ineff=
       T       T
Bank Sta=5825,6076.95
XS Rating Curve= 0 ,0
Exp/Cntr=0.3,0.1

Type RM Length L Ch R = 1 ,116664  ,595,612,140
BEGIN DESCRIPTION:
This cross section corresponds to cross section 116664 of the non-georeferenced CDC model which was the source of this model.
END DESCRIPTION:
XS GIS Cut Line= 5
  2396589.089219 6979403.0000038  2396589.255085  6979334.663463
 2396600.1057852 6974864.1773252 2395853.5780788 6974100.2884331
 2395449.8452904 6970257.0592429
#Sta/Elev= 30
    1000  498.22 1058.29     494 1071.33     486 1159.07     486 1240.91  478.25
 1581.06     480  1736.4     490 2170.07  479.22 2208.81     476 2237.19     466
 2411.38     466 2619.58     508 3789.23  511.06 4055.85     508 4305.89     464
 4726.63     462 5146.23     470 5251.18     448 5300.52   431.6 5382.09   431.6
    5435     448    5463     464    6425     466    6949     460 7104.06     466
 7154.89     474 7443.08     472 7877.16     482 9305.03     47810471.31  497.81
#Mann= 3 ,-1,0
    1000     .08       0 5146.23     .06       0    5463     .13       0
#XS Ineff= 2 , 0
            4430     520    7163             520
Permanent Ineff=
       T       T
Bank Sta=5146.23,5463
XS Rating Curve= 0 ,0
Exp/Cntr=0.3,0.1

Type RM Length L Ch R = 1 ,116053  ,1064,3493,1757
BEGIN DESCRIPTION:
This cross section corresponds to cross section 116053 of the non-georeferenced CDC model which was the source of this model.
---------------------------------------------------------------------
CDC ARL021910-1 ARLINGTON LANDFILL
CROSS-SECTION 116053-125562
DOWNSTREAM END
---------------------------------------------------------------------
END DESCRIPTION:
XS GIS Cut Line= 6
2397836.890235056979581.69371645  2397880.702198 6975931.9566695
   2397887.63011   6975354.82989   2396011.94784   6974211.57791
 2395930.1309836  6973631.1198982395477.915836636970422.83352345
#Sta/Elev= 30
    1050     490    4700     473    4766   465.4    4904   462.3    4978   465.7
    5130     467    5256   465.8    5438   467.8    5849   467.9    6013   464.6
    6067     431    6097   431.4    6106   433.7    6108     436    6152     443
    6214   466.8    6369   465.6    6476   462.5    6578   463.1    6714   467.3
    6825   465.4    6932   467.4    7315     465    7675   466.2    7824   463.1
    7954   463.1    8212     465    8275   469.6    8300   473.9   11300     490
#Mann= 3 ,0,0
    1050     .08       0    6013    .055       0    6214     .13       0
#XS Ineff= 2 , 0
            4700     490    8300             490
Permanent Ineff=
       F       F
Bank Sta=6013,6214
XS Rating Curve= 0 ,0
Exp/Cntr=0.3,0.1

Type RM Length L Ch R = 1 ,112574  ,139,827,888
BEGIN DESCRIPTION:
This cross section corresponds to cross section 112574 of the non-georeferenced CDC model which was the source of this model.
Cross Section Truncated due to Ineffective Flow Areas
END DESCRIPTION:
XS GIS Cut Line= 6
      2398360.36      6979849.11      2398377.95      6975948.18
     2398375.625     6975269.703 2397355.0711938 6972774.1297082
 2397228.1415286 6972463.7469723  2396754.994459 6971306.7543835
#Sta/Elev= 30
    1050     490    4950   470.7    4976   470.1    5047   462.8    5510   466.4
    5672   465.5    6226   470.8    6307   468.2    6375   469.8    6650   468.6
    6705   464.5    6977   468.9    7243   468.7    7423   464.2    7863   465.5
    8000   467.2    8032   451.8    8059   442.3    8076   430.9    8120     429
    8135   436.6    8142   442.4    8221   468.2    8225   470.3    8253   468.9
    8280   465.1    8515   465.1    8569   469.4    8654   467.9    9910     508
#Mann= 4 ,-1,0
    1050     .08       0    7863     .12       0    8000     .05       0
    8221     .12       0
#XS Ineff= 2 , 0
            4950     490    8860             520
Permanent Ineff=
       F       F
Bank Sta=8000,8221
XS Rating Curve= 0 ,0
Exp/Cntr=0.3,0.1

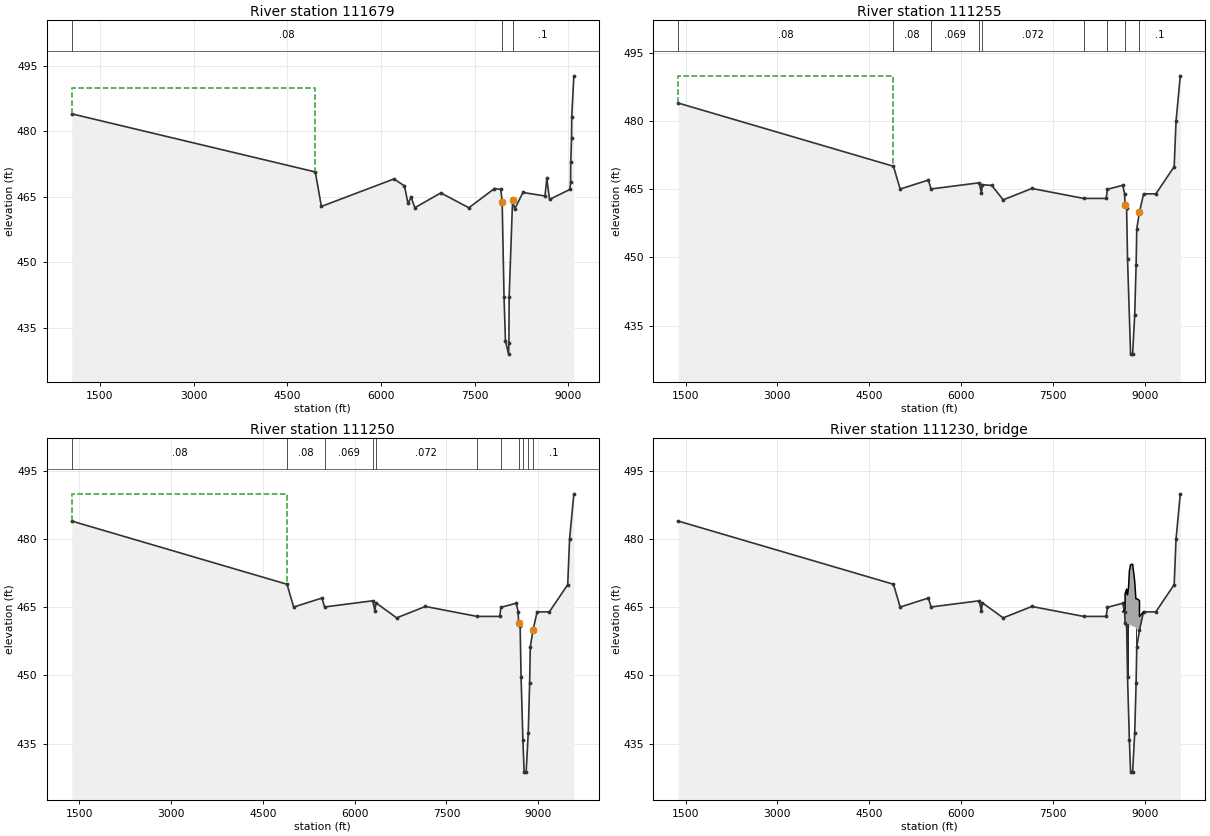
Type RM Length L Ch R = 1 ,111679  ,118,381,189
BEGIN DESCRIPTION:
This cross section corresponds to cross section 111679 of the non-georeferenced CDC model which was the source of this model.
END DESCRIPTION:
XS GIS Cut Line= 6
     2398438.216     6979837.937     2398429.536     6975250.264
     2398328.751     6974137.508     2398326.893     6973214.789
     2398174.252     6972585.482      2397691.47     6971969.229
#Sta/Elev= 30
    1050     484    4950   470.7    5047   462.8    6210   469.1    6378   467.5
    6434   463.5    6485   464.9    6543   462.5    6960   465.9    7409   462.5
    7819   466.9    7920   466.7    7942   463.9    7972   442.1    7995     432
    8045     429    8050   431.5    8054   442.1    8109   464.3    8143   462.2
    8275     466    8628   465.2    8657   469.2    8701   464.4    9026   466.7
    9038   468.3    9040   472.9    9053   478.4    9056   483.2    9090   492.7
#Mann= 3 ,0,0
    1050     .08       0    7942     .05       0    8109      .1       0
#XS Ineff= 2 , 0
            4950     490
Permanent Ineff=
       F       F
Bank Sta=7942,8109
XS Rating Curve= 0 ,0
Exp/Cntr=0.3,0.1

Type RM Length L Ch R = 1 ,111255  ,6,6,6
BEGIN DESCRIPTION:
This cross section corresponds to cross section 111255 of the non-georeferenced CDC model which was the source of this model.
END DESCRIPTION:
XS GIS Cut Line= 5
     2398630.233      6979908.03     2398629.332     6973733.511
     2398633.939     6972634.264      2398394.66     6972660.029
     2397863.089     6972175.199
#Sta/Elev= 30
 1380.36     484 4895.36  470.08 5004.44  465.06 5465.21  467.04 5509.63  465.08
 6294.85  466.44 6332.56  464.16 6345.13  466.02 6501.21  465.86 6686.76  462.68
  7155.7  465.19    8000     463    8369     463    8390     465    8640   465.9
    8670     464    8678   461.5    8703   460.9    8718   449.7    8768   428.7
    8801   428.7    8835   437.3    8858   448.3    8869   456.3    8913     460
    8980     464    9180     464    9480     470    9510     480    9580     490
#Mann= 9 ,-1,0
 1380.36     .08       0 4895.36     .08       0 5509.63    .069       0
 6294.85    .063       0 6345.13    .072       0    8000     .08       0
    8390     .08       0    8678     .05       0    8913      .1       0
#XS Ineff= 2 , 0
         4895.36     490
Permanent Ineff=
       F       F
Bank Sta=8678,8913
XS Rating Curve= 0 ,0
Exp/Cntr=0.3,0.1

Type RM Length L Ch R = 1 ,111250  ,14,14,14
BEGIN DESCRIPTION:
This cross section corresponds to cross section 111250 of the non-georeferenced CDC model which was the source of this model.
END DESCRIPTION:
XS GIS Cut Line= 5
     2398634.507     6979908.253     2398633.369     6973729.605
     2398637.975     6972630.358     2398397.013     6972653.605
     2397867.326     6972166.018
#Sta/Elev= 30
 1380.36     484 4895.36  470.08 5004.44  465.06 5465.21  467.04 5509.63  465.08
 6294.85  466.44 6332.56  464.16 6345.13  466.02 6686.76  462.68  7155.7  465.19
    8000     463    8369     463    8390     465    8640   465.9    8670     464
    8678   461.5    8703   460.9    8718   449.7    8748   435.8    8768   428.7
    8801   428.7    8835   437.3    8858   448.3    8869   456.3    8913     460
    8980     464    9180     464    9480     470    9510     480    9580     490
#Mann= 11 ,-1,0
 1380.36     .08       0 4895.36     .08       0 5509.63    .069       0
 6294.85    .063       0 6345.13    .072       0    8000     .08       0
    8390     .08       0    8678     .03       0    8748     .05       0
    8835     .03       0    8913      .1       0
#XS Ineff= 2 , 0
         4895.36     490
Permanent Ineff=
       F       F
Bank Sta=8678,8913
XS Rating Curve= 0 ,0
Exp/Cntr=0.3,0.1

Type RM Length L Ch R = 3 ,111230  ,,,
BEGIN DESCRIPTION:
River Legacy Parks Pedestrian Bridge
END DESCRIPTION:
Node Name=River Legacy Par
Bridge Culvert--1,0,-1,-1, 0
Deck Dist Width WeirC Skew NumUp NumDn MinLoCord MaxHiCord MaxSubmerge Is_Ogee
0.5,12,2.6,0, 16, 16, , , 0.95, 0, 0,0,,
    8640    8678  8678.1    8703    8712    8718    8735    8748    8768    8801
    8835    8854    8869    8913    8913    8980
     464   464.6     468     469   467.8  467.75   469.5     473   474.4   474.5
   470.8   466.9   466.9   466.5     463     464
     464   461.6   461.6   461.5   461.4   461.4  461.25  461.15   461.1   460.8
   460.7   460.5   460.4   460.1   460.1     464
    8640    8678  8678.1    8703    8712    8718    8735    8748    8768    8801
    8835    8854    8869    8913    8913    8980
     464   464.6     468     469   467.8  467.75   469.5     473   474.4   474.5
   470.8   466.9   466.9   466.5     463     464
     464   461.6   461.6   461.5   461.4   461.4  461.25  461.15   461.1   460.8
   460.7   460.5   460.4   460.1   460.1     464
Pier Skew, UpSta & Num, DnSta & Num=  ,8718, 2 ,8718, 2 , 0 , 0 , 0 ,,
       5       5
     454   461.4
       5       5
     454   461.4
Pier Skew, UpSta & Num, DnSta & Num=  ,8858, 2 ,8858, 2 , 0 , 0 , 0 ,,
       5       5
   448.3   463.4
       5       5
   448.3   463.4
BR Coef=-1 , 0 , 0 ,, 0 ,,,0.8,-1,,0,
WSPro=,,,, 1 ,,,, 0 ,,,, 0 ,,,,-1 ,-1 ,-1 , 0 , 0 , 0 , 0 , 0
BC Design=,, 0 ,, 0 ,,,,,,
BC Use User HTab Curves=0
BC User HTab FreeFlow(D)= 0