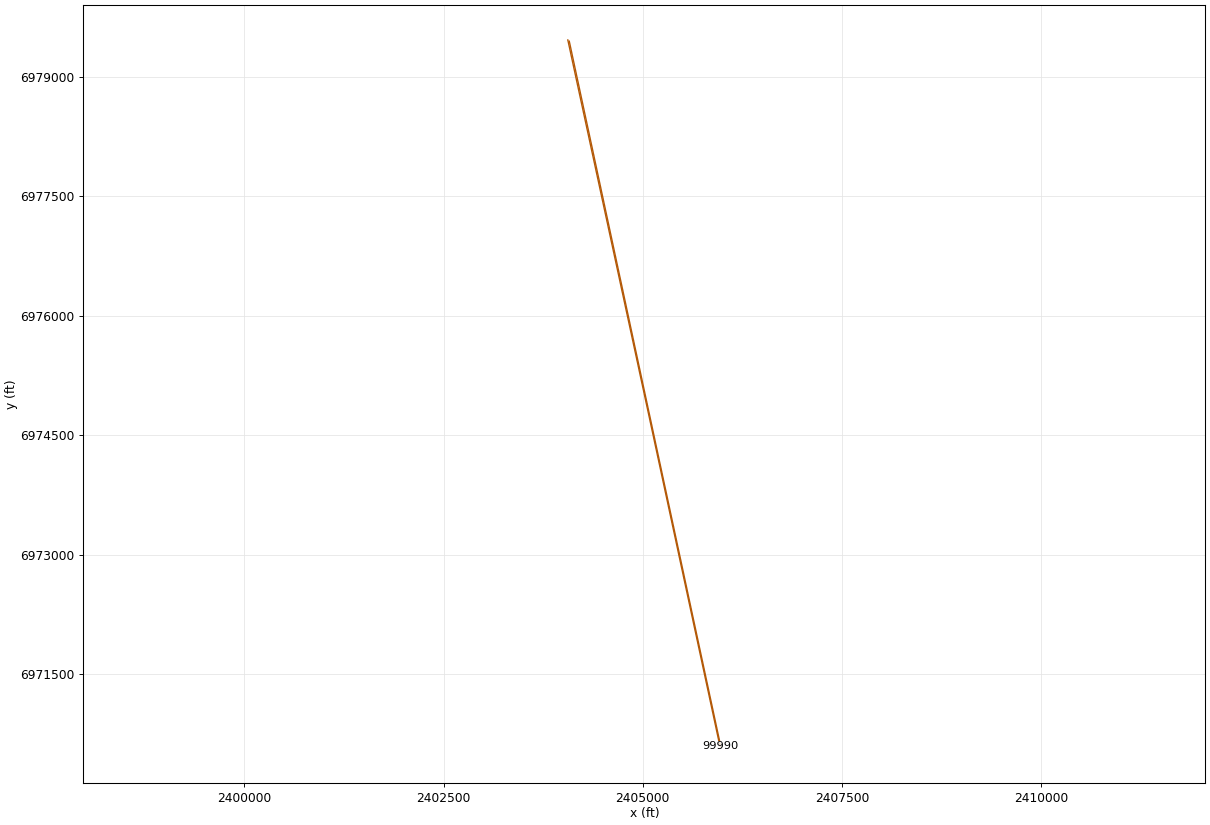
HEC-RAS study CDC_Consolidated_Model.prj: Upper Trinity CDC Consolidated Model

--- CDC_Consolidated_Model.g13 (geometry) --- (continued)

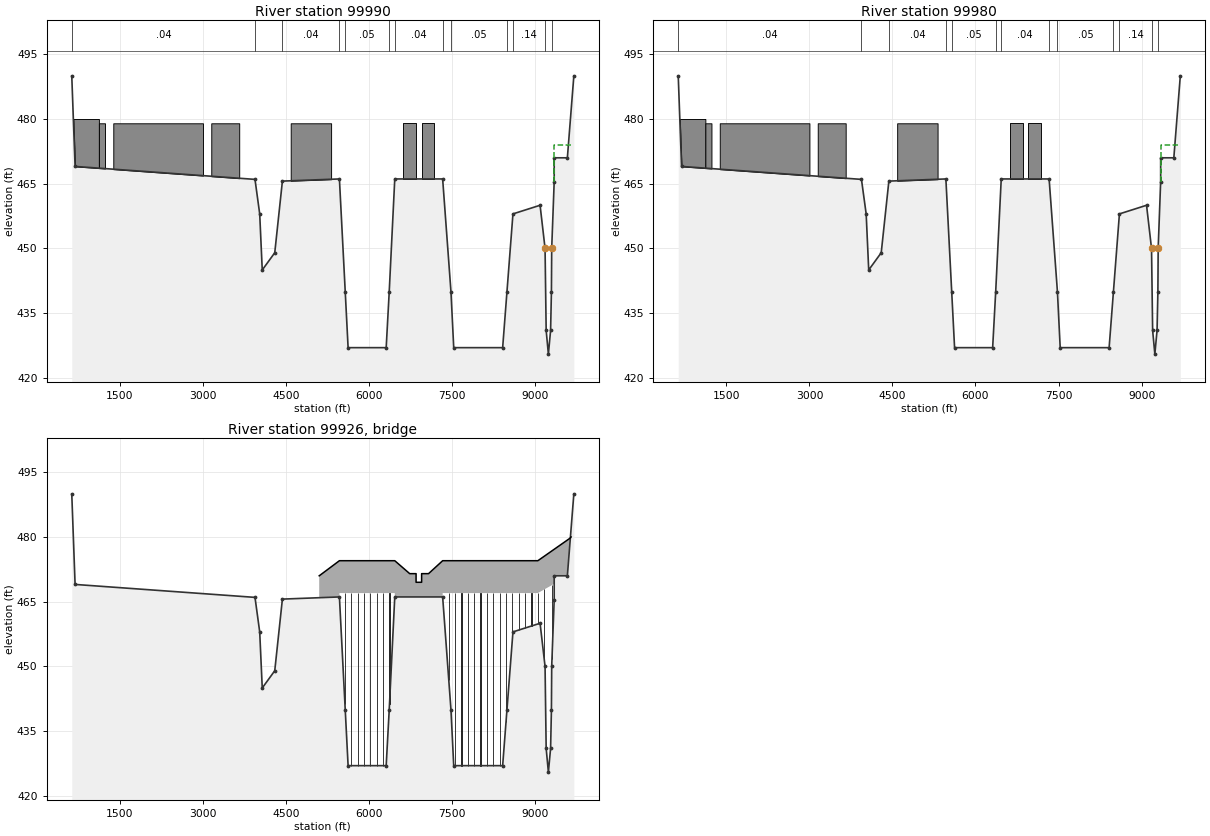
Type RM Length L Ch R = 1 ,99990   ,10,10,10
BEGIN DESCRIPTION:
This cross section corresponds to cross section 99990 of the non-georeferenced CDC model which was the source of this model.
U/S of Bridge #1 & #2.  Proposed fill & lake on LOB.  Flow limit 1120  Repeat of 99980.  X-SECTION BASED ON 1991 AND 2001 SURVEY DATA.
END DESCRIPTION:
XS GIS Cut Line= 3
     2404059.717     6979460.783     2405081.398     6974727.361
     2405969.484     6970594.128
#Sta/Elev= 30
     630     490     690     469    3940     466    4025     458    4071     445
    4297     449    4435   465.6    5465   466.1    5570     440    5622     427
    6310     427    6365     440    6465   466.1    7330   466.1    7480     440
    7530     427    8414     427    8492     440    8600     458    9090     460
    9180     450    9200     431    9240   425.5    9280     431    9295     440
    9300     450    9345   465.5    9345     471    9583     471    9700     490
#Mann= 13 ,-1,0
     630     .04       0    3940     .07       0    4435     .04       0
    5465     .08       0    5570     .05       0    6365     .08       0
    6465     .04       0    7330     .08       0    7480     .05       0
    8492     .08       0    8600     .14       0    9180    .055       0
    9300     .14       0
#XS Ineff= 4 ,-1
    3900    4400   455.5    5200    6800     449    7200    8800     447
    9345    9650     474
Permanent Ineff=
       T       T       T       T
#Block Obstruct= 7 ,-1
     630    1120     480    1120    1230     479    1380    3000     479
    3150    3655     479    4585    5315     479    6615    6850     479
    6950    7180     479
Bank Sta=9180,9300
XS Rating Curve= 0 ,0
Exp/Cntr=0.4,0.2

Type RM Length L Ch R = 1 ,99980   ,61,61,61
BEGIN DESCRIPTION:
This cross section corresponds to cross section 99980 of the non-georeferenced CDC model which was the source of this model.
U/S face of Bridge #1 & #2.  Proposed fill & lake on LOB.  Flow limit 1120  Repeat of 99980.  X-SECTION BASED ON 1991 AND 2001 SURVEY DATA.
END DESCRIPTION:
XS GIS Cut Line= 4
   2404078.04193  6979445.353264     2404113.807     6979278.856
      2405947.14     6970744.134 2405982.9050698 6970577.6367361
#Sta/Elev= 30
     630     490     690     469    3940     466    4025     458    4071     445
    4297     449    4435   465.6    5465   466.1    5570     440    5622     427
    6310     427    6365     440    6465   466.1    7330   466.1    7480     440
    7530     427    8414     427    8492     440    8600     458    9090     460
    9180     450    9200     431    9240   425.5    9280     431    9295     440
    9300     450    9345   465.5    9345     471    9583     471    9700     490
#Mann= 13 ,-1,0
     630     .04       0    3940     .07       0    4435     .04       0
    5465     .08       0    5570     .05       0    6365     .08       0
    6465     .04       0    7330     .08       0    7480     .05       0
    8492     .08       0    8600     .14       0    9180    .055       0
    9300     .14       0
#XS Ineff= 4 ,-1
    3900    4400   455.5    5200    6800     449    7200    8800     447
    9345    9650     474
Permanent Ineff=
       T       T       T       T
#Block Obstruct= 7 ,-1
     630    1120     480    1120    1230     479    1380    3000     479
    3150    3655     479    4585    5315     479    6615    6850     479
    6950    7180     479
Bank Sta=9180,9300
XS Rating Curve= 0 ,0
Exp/Cntr=0.4,0.2

Type RM Length L Ch R = 3 ,99926   ,,,
BEGIN DESCRIPTION:
Ballpark Way
Proposed - 6' low beam to top of curb + 2.5' (30") for barrier
END DESCRIPTION:
Node Name=Ballpark Way
Bridge Culvert--1,0,-1,-1, 0
Deck Dist Width WeirC Skew NumUp NumDn MinLoCord MaxHiCord MaxSubmerge Is_Ogee
0.5,60,2.6,0, 16, 16, 480, , 0.95, 0, 0,0,,
    5100    5465    5465    6465    6465    6735    6850    6850    6950    6950
    7075    7330    7330    9050    9629    9650
     471   474.5   474.5   474.5   474.5   471.5   471.5   469.5   469.5   471.5
   471.5   474.5   474.5   474.5   479.7     480
     466     466     467     467     466     466     466     466     466     466
     466     466     467     467   471.2     474
    5100    5465    5465    6465    6465    6735    6850    6850    6950    6950
    7075    7330    7330    9050    9629    9650
     471   474.5   474.5   474.5   474.5   471.5   471.5   469.5   469.5   471.5
   471.5   474.5   474.5   474.5   479.7     480
     466     466     467     467     466     466     466     466     466     466
     466     466     467     467   471.2     474
Pier Skew, UpSta & Num, DnSta & Num=  ,5565, 2 ,5565, 2 , 0 , 0 , 0 ,,
       3       3
     437     474
       3       3
     437     474
Pier Skew, UpSta & Num, DnSta & Num=  ,5680, 2 ,5680, 2 , 0 , 0 , 0 ,,
       3       3
     437     474
       3       3
     437     474
Pier Skew, UpSta & Num, DnSta & Num=  ,5795, 2 ,5795, 2 , 0 , 0 , 0 ,,
       3       3
     437     474
       3       3
     437     474
Pier Skew, UpSta & Num, DnSta & Num=  ,5910, 2 ,5910, 2 , 0 , 0 , 0 ,,
       3       3
     437     474
       3       3
     437     474
Pier Skew, UpSta & Num, DnSta & Num=  ,6025, 2 ,6025, 2 , 0 , 0 , 0 ,,
       3       3
     437     474
       3       3
     437     474
Pier Skew, UpSta & Num, DnSta & Num=  ,6140, 2 ,6140, 2 , 0 , 0 , 0 ,,
       3       3
     437     474
       3       3
     437     474
Pier Skew, UpSta & Num, DnSta & Num=  ,6255, 2 ,6255, 2 , 0 , 0 , 0 ,,
       3       3
     437     474
       3       3
     437     474
Pier Skew, UpSta & Num, DnSta & Num=  ,6370, 2 ,6370, 2 , 0 , 0 , 0 ,,
       3       3
     437     474
       3       3
     437     474
Pier Skew, UpSta & Num, DnSta & Num=  ,7440, 2 ,7440, 2 , 0 , 0 , 0 ,,
       3       3
     437     474
       3       3
     437     474
Pier Skew, UpSta & Num, DnSta & Num=  ,7555, 2 ,7555, 2 , 0 , 0 , 0 ,,
       3       3
     437     474
       3       3
     437     474
Pier Skew, UpSta & Num, DnSta & Num=  ,7670, 2 ,7670, 2 , 0 , 0 , 0 ,,
       3       3
     437     474
       3       3
     437     474
Pier Skew, UpSta & Num, DnSta & Num=  ,7785, 2 ,7785, 2 , 0 , 0 , 0 ,,
       3       3
     437     474
       3       3
     437     474
Pier Skew, UpSta & Num, DnSta & Num=  ,7900, 2 ,7900, 2 , 0 , 0 , 0 ,,
       3       3
     437     474
       3       3
     437     474
Pier Skew, UpSta & Num, DnSta & Num=  ,8015, 2 ,8015, 2 , 0 , 0 , 0 ,,
       3       3
     437     474
       3       3
     437     474
Pier Skew, UpSta & Num, DnSta & Num=  ,8130, 2 ,8130, 2 , 0 , 0 , 0 ,,
       3       3
     437     474
       3       3
     437     474
Pier Skew, UpSta & Num, DnSta & Num=  ,8245, 2 ,8245, 2 , 0 , 0 , 0 ,,
       3       3
     437     474
       3       3
     437     474
Pier Skew, UpSta & Num, DnSta & Num=  ,8360, 2 ,8360, 2 , 0 , 0 , 0 ,,
       3       3
     437     474
       3       3
     437     474
Pier Skew, UpSta & Num, DnSta & Num=  ,8475, 2 ,8475, 2 , 0 , 0 , 0 ,,
       3       3
     437     474
       3       3
     437     474
Pier Skew, UpSta & Num, DnSta & Num=  ,8590, 2 ,8590, 2 , 0 , 0 , 0 ,,
       3       3
     437     474
       3       3
     437     474
Pier Skew, UpSta & Num, DnSta & Num=  ,8705, 2 ,8705, 2 , 0 , 0 , 0 ,,
       3       3
     437     474
       3       3
     437     474
Pier Skew, UpSta & Num, DnSta & Num=  ,8820, 2 ,8820, 2 , 0 , 0 , 0 ,,
       3       3
     437     474
       3       3
     437     474
Pier Skew, UpSta & Num, DnSta & Num=  ,8935, 2 ,8935, 2 , 0 , 0 , 0 ,,
       3       3
     437     474
       3       3
     437     474
Pier Skew, UpSta & Num, DnSta & Num=  ,9050, 2 ,9050, 2 , 0 , 0 , 0 ,,
       3       3
     437     474
       3       3
     437     474
Pier Skew, UpSta & Num, DnSta & Num=  ,9165, 2 ,9165, 2 , 0 , 0 , 0 ,,
       3       3
     437     474
       3       3
     437     474
Pier Skew, UpSta & Num, DnSta & Num=  ,9305, 2 ,9305, 2 , 0 , 0 , 0 ,,
       3       3
     437     474
       3       3
     437     474
BR Coef=-1 , 0 , 0 ,1.05, 0 ,,,0.8,-1,1.2,0,474
WSPro=,,,, 1 ,,,, 0 ,,,, 0 ,,,,-1 ,-1 ,-1 , 0 , 0 , 0 , 0 , 0
BC Design=,, 0 ,, 0 ,,,,,,
BC Use User HTab Curves=0
BC User HTab FreeFlow(D)= 0