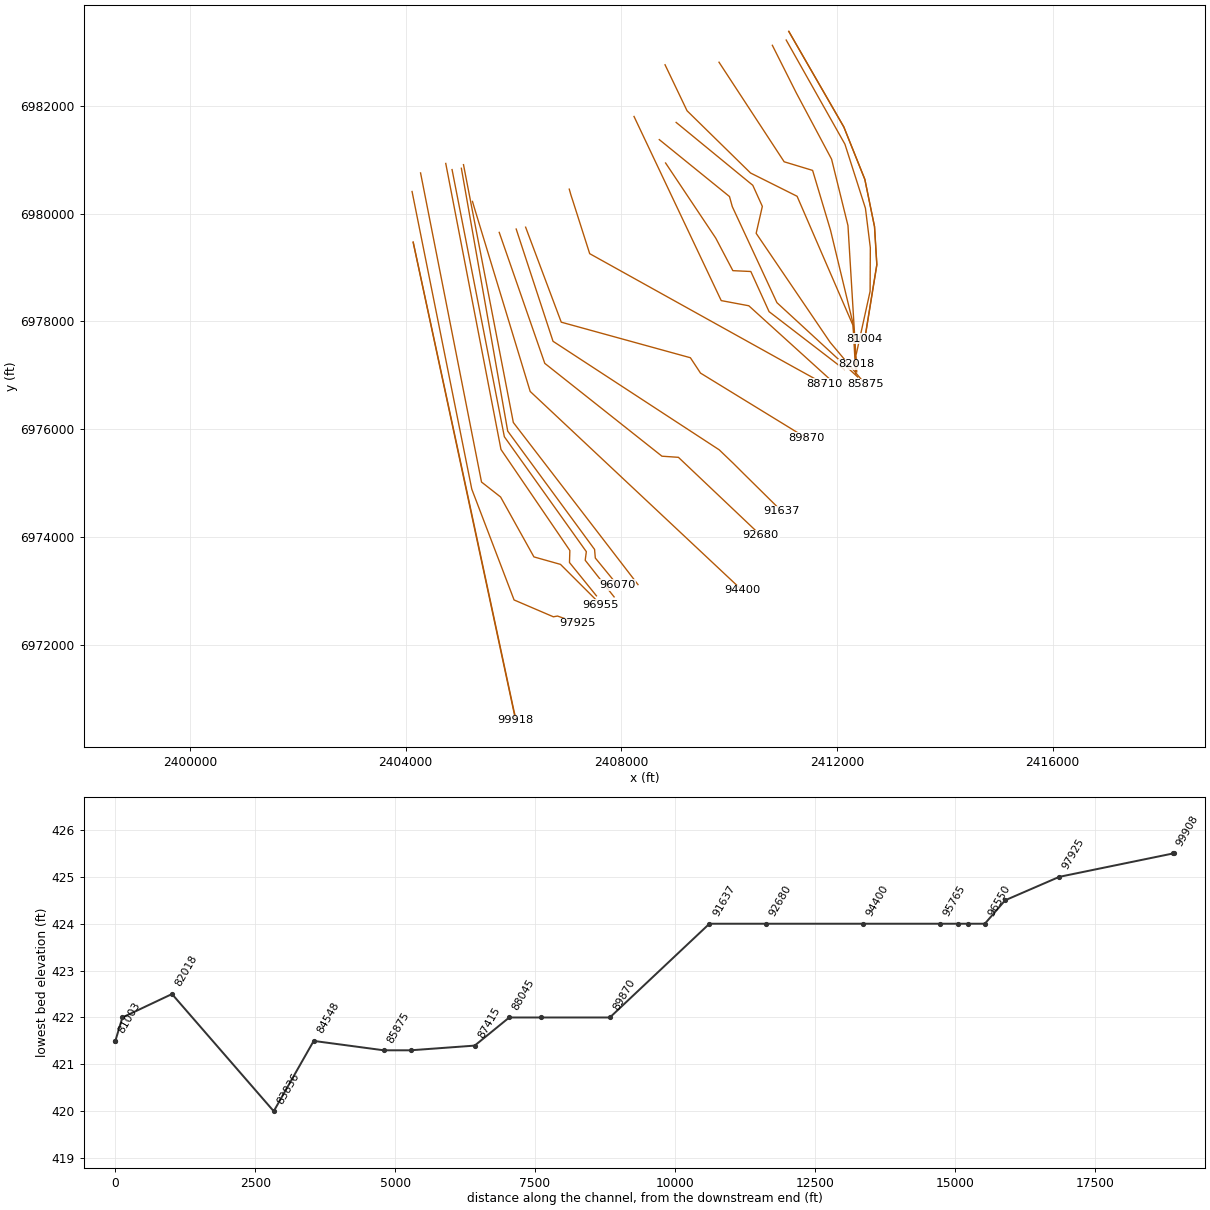
HEC-RAS study CDC_Consolidated_Model.prj: Upper Trinity CDC Consolidated Model

--- CDC_Consolidated_Model.g13 (geometry) --- (continued)

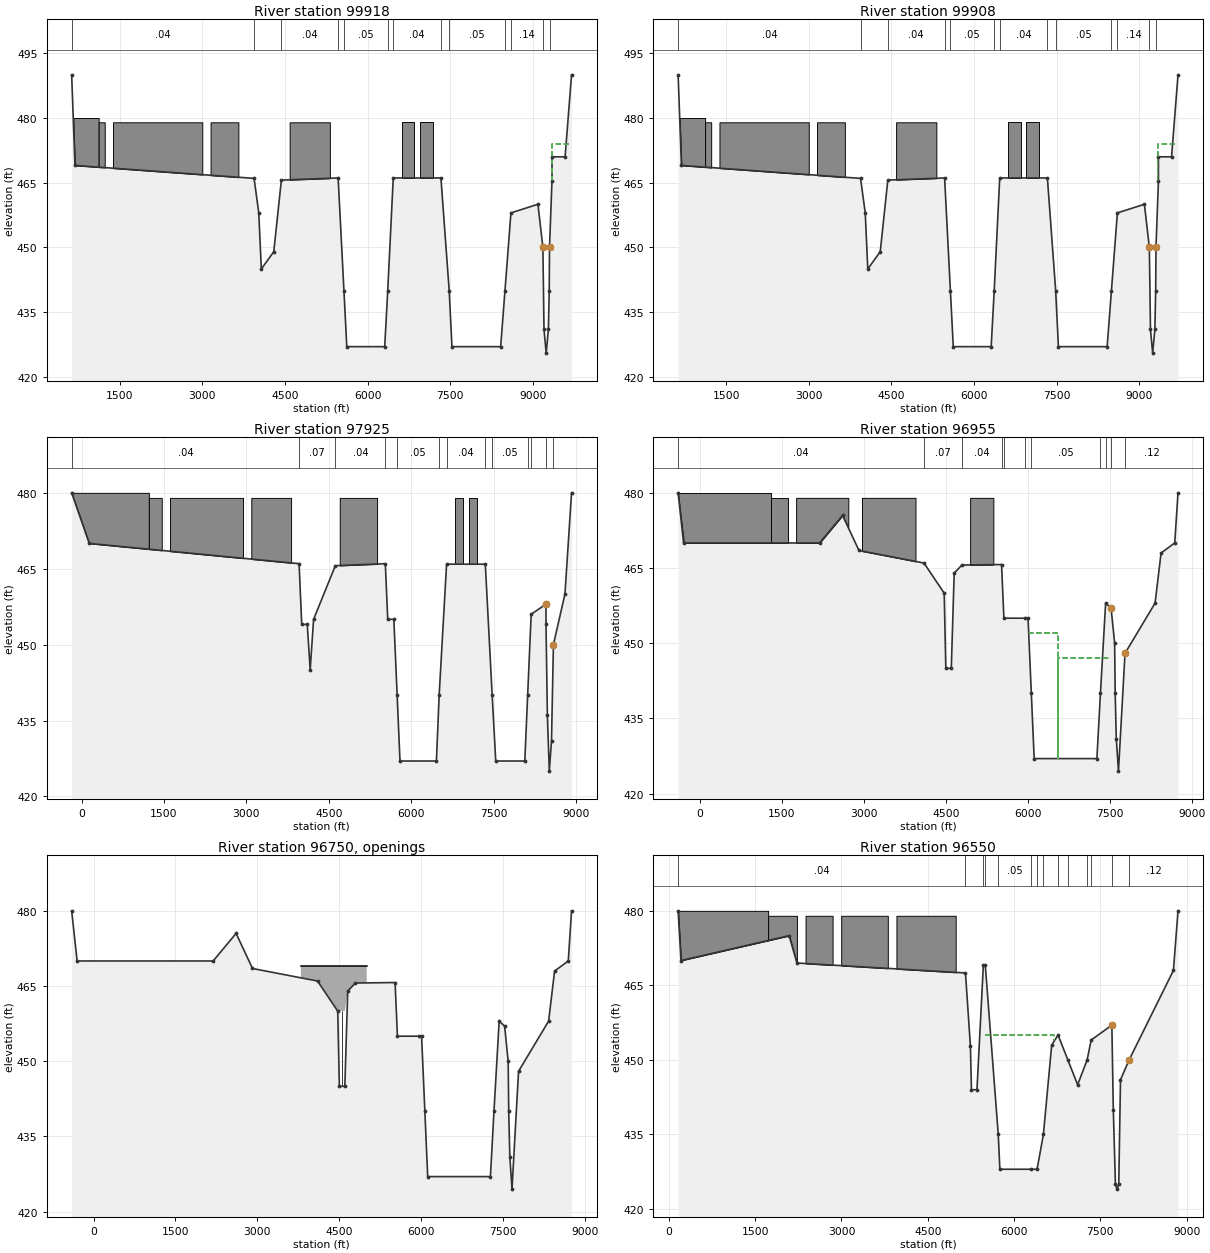
Type RM Length L Ch R = 1 ,99918   ,6,6,6
BEGIN DESCRIPTION:
This cross section corresponds to cross section 99918 of the non-georeferenced CDC model which was the source of this model.
D/S face of Bridge #1 & #2.  Proposed fill & lake on LOB.  Flow limit 1120  Repeat of 99980
END DESCRIPTION:
XS GIS Cut Line= 4
  2404136.934075 6979468.0216169     2404174.942     6979290.844
     2406001.331     6970776.955 2406039.3389245 6970599.7773831
#Sta/Elev= 30
     630     490     690     469    3940     466    4025     458    4071     445
    4297     449    4435   465.6    5465   466.1    5570     440    5622     427
    6310     427    6365     440    6465   466.1    7330   466.1    7480     440
    7530     427    8414     427    8492     440    8600     458    9090     460
    9180     450    9200     431    9240   425.5    9280     431    9295     440
    9300     450    9345   465.5    9345     471    9583     471    9700     490
#Mann= 13 ,-1,0
     630     .04       0    3940     .07       0    4435     .04       0
    5465     .08       0    5570     .05       0    6365     .08       0
    6465     .04       0    7330     .08       0    7480     .05       0
    8492     .08       0    8600     .14       0    9180    .055       0
    9300     .14       0
#XS Ineff= 4 ,-1
    3900    4400   455.5    5200    6800     449    7200    8800     447
    9345    9650     474
Permanent Ineff=
       T       T       T       T
#Block Obstruct= 7 ,-1
     630    1120     480    1120    1230     479    1380    3000     479
    3150    3655     479    4585    5315     479    6615    6850     479
    6950    7180     479
Bank Sta=9180,9300
XS Rating Curve= 0 ,0
Exp/Cntr=0.4,0.2

Type RM Length L Ch R = 1 ,99908   ,257,2038,2145
BEGIN DESCRIPTION:
This cross section corresponds to cross section 99908 of the non-georeferenced CDC model which was the source of this model.
D/S of Bridge #1 & #2.  Proposed fill & lake on LOB.  Flow limit 1120  Repeat of 99980
END DESCRIPTION:
XS GIS Cut Line= 4
      2404138.47     6979473.908     2405155.749     6974749.724
     2406008.784     6970770.542     2406048.819     6970605.992
#Sta/Elev= 30
     630     490     690     469    3940     466    4025     458    4071     445
    4297     449    4435   465.6    5465   466.1    5570     440    5622     427
    6310     427    6365     440    6465   466.1    7330   466.1    7480     440
    7530     427    8414     427    8492     440    8600     458    9090     460
    9180     450    9200     431    9240   425.5    9280     431    9295     440
    9300     450    9345   465.5    9345     471    9583     471    9700     490
#Mann= 13 ,-1,0
     630     .04       0    3940     .07       0    4435     .04       0
    5465     .08       0    5570     .05       0    6365     .08       0
    6465     .04       0    7330     .08       0    7480     .05       0
    8492     .08       0    8600     .14       0    9180    .055       0
    9300     .14       0
#XS Ineff= 4 ,-1
    3900    4400   455.5    5200    6800     449    7200    8800     447
    9345    9650     474
Permanent Ineff=
       T       T       T       T
#Block Obstruct= 7 ,-1
     630    1120     480    1120    1230     479    1380    3000     479
    3150    3655     479    4585    5315     479    6615    6850     479
    6950    7180     479
Bank Sta=9180,9300
XS Rating Curve= 0 ,0
Exp/Cntr=0.4,0.2

Type RM Length L Ch R = 1 ,97925   ,688,967,818
BEGIN DESCRIPTION:
This cross section corresponds to cross section of 97925 the non-georeferenced CDC model which was the source of this model.
Proposed fill & lake on LOB.  Flow limit 1225  452.9 for continuity around island.  LOB from 2001 aerial topo.  ROB OF X-SECTION BASED ON 1991 AND 2001 SURVEY DATA
END DESCRIPTION:
XS GIS Cut Line= 6
  2404117.181044  6980411.203205     2405224.918     6974889.967
      2406009.64     6972834.411     2406738.807     6972521.911
     2406815.196       6972535.8     2407190.196     6972403.856
#Sta/Elev= 30
    -180     480     140     470    3960     466    4008     454    4109     454
    4162     445    4224     455    4620   465.6    5530     466    5574     455
    5685     455    5745     440    5797     427    6460     427    6510     440
    6645   465.9    7350   465.9    7475     440    7540     427    8069     427
    8121     440    8185     456    8455     458    8455     454    8480     436
    8515     425    8555     431    8590     450    8800     460    8920     480
#Mann= 13 ,-1,0
    -180     .04       0    3960     .07       0    4620     .04       0
    5530     .08       0    5745     .05       0    6510     .08       0
    6645     .04       0    7350     .08       0    7475     .05       0
    8121     .08       0    8185     .14       0    8455     .06       0
    8590     .12       0
#XS Ineff= 3 ,-1
    3900    4500   459.8    5500    6700   452.3    7200    8200     446
Permanent Ineff=
       T       T       T
#Block Obstruct= 7 ,-1
    -180    1225     480    1225    1460     479    1610    2940     479
    3090    3815     479    4700    5380     479    6795    6950     479
    7050    7200     479
Bank Sta=8455,8590
XS Rating Curve= 0 ,0
Exp/Cntr=0.3,0.1

Type RM Length L Ch R = 1 ,96955   ,538,363,108
BEGIN DESCRIPTION:
This cross section corresponds to cross section 96955 of the non-georeferenced CDC model which was the source of this model.
Proposed fill & lake on LOB.  U/S face of bridge #3.  Flow limit 1300  Far LOB realigned for hydraulics.  LOB from 2001 aerial topo.  ROB OF X-SECTION BASED ON 1991 AND 2001 SURVEY DATA
END DESCRIPTION:
XS GIS Cut Line= 6
  2404274.836498 6980755.8538621 2405405.4730169 6975021.9109336
 2405759.6399595 6974744.1339302 2406377.6961381 6973633.0229634
 2406870.7509263 6973494.1341336 2407617.8842745 6972748.3311632
#Sta/Elev= 30
    -400     480    -300     470    2190     470    2610   475.5    2910   468.5
    4100     466    4470     460    4500     445    4600     445    4653     464
    4795   465.6    5520   465.7    5563     455    5950     455    6005     455
    6065     440    6117     427    7265     427    7330     440    7425     458
    7525     457    7590     450    7600     440    7620     431    7660   424.5
    7780     448    8330     458    8440     468    8690     470    8750     480
#Mann= 11 ,-1,0
    -400     .04       0    4100     .07       0    4795     .04       0
    5520     .09       0    5563     .12       0    5950     .09       0
    6065     .05       0    7330     .09       0    7425     .14       0
    7525     .06       0    7780     .12       0
#XS Ineff= 2 ,-1
    6000    6550     452    6550    7500     447
Permanent Ineff=
       T       T
#Block Obstruct= 5 ,-1
    -400    1300     480    1300    1610     479    1760    2715     479
    2965    3945     479    4945    5370     479
Bank Sta=7525,7780
XS Rating Curve= 0 ,0
Exp/Cntr=0.3,0.1

Type RM Length L Ch R = 4 ,96750   ,,,
BEGIN DESCRIPTION:
Bridge over Hurricane Creek
2-80' spans
END DESCRIPTION:
Node Name=Bridge over Hurr
Bridge Culvert--1,0,-1,-1, 0
Deck Dist Width WeirC Skew NumUp NumDn MinLoCord MaxHiCord MaxSubmerge Is_Ogee
150,62,2.6,0, 2, 3, 469, , 0.95, 0, 2,2,,
    3796    5000
     469     469
     460     460
    5080    5155    5466
   467.5     469     469
     460     460     460
Pier Skew, UpSta & Num, DnSta & Num=  ,4550, 2 ,5307, 2 , 0 , 0 , 0 ,,
       3       3
     444     460
       3       3
     444     460
Abutment Skew #Up #Dn= , 3 , 3
    4460    4470    4500
     460     460     445
    5180    5227    5259
     460     460     444
Abutment Skew #Up #Dn= , 3 , 3
    4600    4630    4640
     445     460     460
    5355    5387    5430
     444     460     460
BR Coef=-1 , 0 , 0 ,1.05, 0 ,,,0.8,-1,1.2,0,
WSPro=,,,, 1 ,,,, 0 ,,,, 0 ,,,,-1 ,-1 ,-1 , 0 , 0 , 0 , 0 , 0
BC Mult= 1 ,-400,3780,160,4800
BC Mult= 3 ,3780,5150,4800,5485
BC Mult= 1 ,5150,8750,5485,8850
BC Design=,, 0 ,, 0 ,,,,,,
BC Use User HTab Curves=0
BC User HTab FreeFlow(D)= 0

Type RM Length L Ch R = 1 ,96550   ,199,301,272
BEGIN DESCRIPTION:
This cross section corresponds to cross section 96550 of the non-georeferenced CDC model which was the source of this model.
Proposed fill & lake overflow structure on LOB.  D/S face of bridge #3.  Flow limit 1725  Flow limited in LOB due to sewer ridge.  LOB from 2001 aerial topo.  ROB OF X-SECTION BASED ON 1991 AND 2001 SURVEY DATA
END DESCRIPTION:
XS GIS Cut Line= 6
  2404742.167568 6980931.7807449     2405030.473     6979438.578
     2405766.585     6975626.078     2407044.362     6973751.078
     2407037.418     6973528.856     2407537.418       6972910.8
#Sta/Elev= 30
     160     480     210     470    2090     475    2225   469.5    5155   467.5
    5241   452.8    5259     444    5355     444    5466     469    5500     469
    5725     435    5753     428    6300     428    6400     428    6510     435
    6654     453    6765     455    6935     450    7105     445    7270     450
    7340     454    7700     457    7725     440    7762     425    7790     424
    7820     425    7850     446    8000     450    8770     468    8850     480
#Mann= 14 ,-1,0
     160     .04       0    5155     .07       0    5466     .04       0
    5500     .09       0    5725     .05       0    6300     .12       0
    6400     .05       0    6510     .09       0    6765     .08       0
    6935    .025       0    7270     .08       0    7340     .14       0
    7700     .06       0    8000     .12       0
#XS Ineff= 1 ,-1
    5500    6700     455
Permanent Ineff=
       T
#Block Obstruct= 5 ,-1
     160    1725     480    1725    2225     479    2375    2845     479
    2995    3805     479    3955    4985     479
Bank Sta=7700,8000
XS Rating Curve= 0 ,0
Exp/Cntr=0.3,0.1

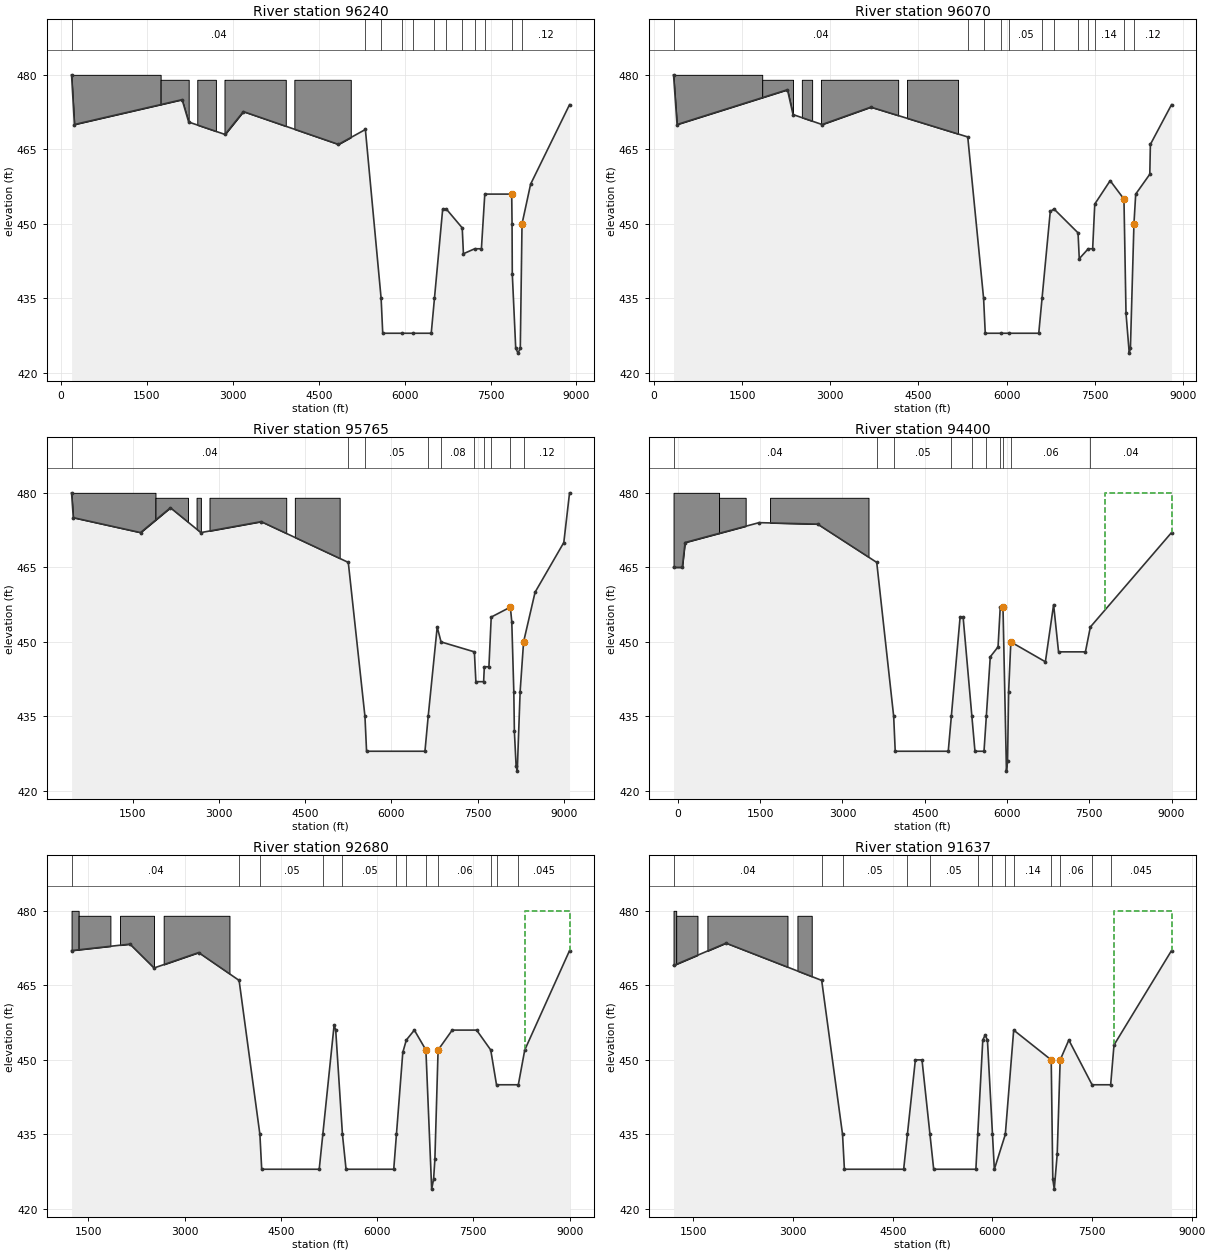
Type RM Length L Ch R = 1 ,96240   ,166,176,166
BEGIN DESCRIPTION:
This cross section corresponds to cross section 96240 of the non-georeferenced CDC model which was the source of this model.
Proposed fill, lake, & lake ooutfall on LOB.  Flow limit 1740  Flow limited in LOB due to sewer ridge.  LOB from 2001 aerial topo.  ROB OF X-SECTION BASED ON 1991 AND 2001 SURVEY DATA
END DESCRIPTION:
XS GIS Cut Line= 6
  2404859.079752 6980817.8589874 2405829.0850306 6975862.1891087
 2407349.9179469 6973730.2452099 2407329.0849833 6973570.5230884
 2407766.5850926 6973014.9671129 2407865.2499215 6972891.2121111
#Sta/Elev= 30
     185     480     235     470    2115     475    2230   470.5    2865     468
    3185   472.6    4845     466    5315     469    5590     435    5618     428
    5950     428    6150     428    6465     428    6521     435    6665     453
    6728     453    7006   449.2    7027     444    7224     445    7341     445
    7400     456    7870     456    7876     450    7880     440    7940     425
    7980     424    8020     425    8050     450    8200     458    8880     474
#Mann= 12 ,-1,0
     185     .04       0    5315     .09       0    5590     .05       0
    5950     .12       0    6150     .05       0    6521     .09       0
    6728     .08       0    7006     .06       0    7224     .08       0
    7400     .14       0    7870     .06       0    8050     .12       0
#XS Ineff= 1 ,-1
    5400    6700   452.5
Permanent Ineff=
       T
#Block Obstruct= 5 ,-1
     185    1740     480    1740    2230     479    2380    2705     479
    2855    3925     479    4075    5060     479
Bank Sta=7870,8050
XS Rating Curve= 0 ,0
Exp/Cntr=0.3,0.1

Type RM Length L Ch R = 1 ,96070   ,213,317,333
BEGIN DESCRIPTION:
This cross section corresponds to cross section 96070 of the non-georeferenced CDC model which was the source of this model.
Proposed fill, lake, & lake ooutfall on LOB.  Flow limit 1840  Flow limited in LOB due to sewer ridge.  LOB from 2001 aerial topo.  ROB OF X-SECTION BASED ON 1991 AND 2001 SURVEY DATA
END DESCRIPTION:
XS GIS Cut Line= 6
  2405031.750795 6980841.9999936     2405280.473     6979431.634
     2405891.585     6975966.356     2407502.696     6973771.911
     2407516.585     6973612.189     2407926.307     6973112.189
#Sta/Elev= 30
     330     480     390     470    2270     477    2365     472    2860     470
    3690   473.5    5340   467.5    5610     435    5638     428    5900     428
    6050     428    6549     428    6605     435    6745   452.5    6809     453
    7218   448.2    7239     443    7392     445    7467     445    7503     454
    7765   458.7    8000     455    8035     432    8090     424    8110     425
    8170     450    8200     456    8440     460    8450     466    8810     474
#Mann= 12 ,-1,0
     330     .04       0    5340     .09       0    5610     .05       0
    5900     .12       0    6050     .05       0    6605     .09       0
    6809     .08       0    7218     .06       0    7392     .08       0
    7503     .14       0    8000     .06       0    8170     .12       0
#XS Ineff= 1 ,-1
    5400    6800   452.5
Permanent Ineff=
       T
#Block Obstruct= 5 ,-1
     330    1840     480    1840    2365     479    2515    2690     479
    2840    4155     479    4305    5175     479
Bank Sta=8000,8170
XS Rating Curve= 0 ,0
Exp/Cntr=0.3,0.1

Type RM Length L Ch R = 1 ,95765   ,883,1377,1200
BEGIN DESCRIPTION:
This cross section corresponds to cross section 95765 of the non-georeferenced CDC model which was the source of this model.
Proposed fill, lake, & lake ooutfall on LOB.  Flow limit 1895  Flow limited in LOB due to sewer ridge.  LOB from 2001 aerial topo.  ROB OF X-SECTION BASED ON 1991 AND 2001
END DESCRIPTION:
XS GIS Cut Line= 4
  2405071.277154 6980909.2250994     2405356.862     6979431.634
     2405995.751     6976126.078     2408308.251     6973119.134
#Sta/Elev= 30
     435     480     465     475    1635     472    2155     477    2685     472
    3735   474.2    5250     466    5540     435    5568     428    6584     428
    6640     435    6797     453    6864     450    7444     448    7470     442
    7605     442    7617     445    7697     445    7737     455    8070     457
    8095     454    8130     440    8140     432    8170     425    8190     424
    8240     440    8300     450    8500     460    9000     470    9100     480
#Mann= 10 ,-1,0
     435     .04       0    5250     .09       0    5540     .05       0
    6640     .09       0    6864     .08       0    7444     .06       0
    7617     .08       0    7737     .14       0    8070     .06       0
    8300     .12       0
#XS Ineff= 1 ,-1
    5300    6800     452
Permanent Ineff=
       T
#Block Obstruct= 5 ,-1
     435    1895     480    1895    2460     479    2610    2685     479
    2835    4170     479    4320    5100     479
Bank Sta=8070,8300
XS Rating Curve= 0 ,0
Exp/Cntr=0.3,0.1

Type RM Length L Ch R = 1 ,94400   ,681,1734,1008
BEGIN DESCRIPTION:
This cross section corresponds to cross section 94400 of the non-georeferenced CDC model which was the source of this model.
Proposed fill & lakes (2) on LOB.  Flow limit 750  Flow limited in LOB due to sewer ridge.  LOB from 2001 aerial topo.  ROB OF X-SECTION BASED ON 1991 AND 2001 SURVEY DATA  SET COE NON-EFFECTIVE FLOW LIMIT AT FILL LINE IN ROB
END DESCRIPTION:
XS GIS Cut Line= 6
  2405237.782735 6980227.1465862 2405275.2327918 6980100.3282702
 2405467.9728919  6979466.356113  2406308.251067 6976702.4669557
 2409357.6514643 6973841.55108962410243.73420308 6973010.2374424
#Sta/Elev= 30
     -80     465      80     465     130     470    1480     474    2548   473.7
    3625     466    3934     435    3962     428    4929     428    4985     435
    5145     455    5200     455    5360     435    5416     428    5581     428
    5623     435    5695     447    5837     449    5877     457    5927     457
    5990     424    6010     426    6030     440    6070     450    6700     446
    6850   457.5    6940     448    7430     448    7520     453    9000     472
#Mann= 10 ,-1,0
     -80     .04       0    3625     .09       0    3934     .05       0
    4985     .09       0    5360     .05       0    5623     .09       0
    5877     .14       0    5927    .055       0    6070     .06       0
    7520     .04       0
#XS Ineff= 2 ,-1
    3700    5800   447.5    7785    9000     480
Permanent Ineff=
       T       F
#Block Obstruct= 3 ,-1
     -80     750     480     750    1235     479    1680    3475     479
Bank Sta=5927,6070
XS Rating Curve= 0 ,0
Exp/Cntr=0.3,0.1

Type RM Length L Ch R = 1 ,92680   ,555,1016,585
BEGIN DESCRIPTION:
This cross section corresponds to cross section 92680 of the non-georeferenced CDC model which was the source of this model.
Proposed fill & lakes (2) on LOB.  Flow limit 1350  Flow limited in LOB due to sewer ridge.  LOB from 2001 aerial topo.  ROB OF X-SECTION BASED ON 1991 AND 2001 SURVEY DATA  SET COE NON-EFFECTIVE FLOW LIMIT AT FILL LINE IN ROB
END DESCRIPTION:
XS GIS Cut Line= 6
  2405734.098521 6979652.6362441     2406579.085       6977223.3
     2408752.696     6975501.078     2409058.251     6975480.245
     2410080.402      6974511.272410586.963189156974031.06196004
#Sta/Elev= 30
    1240     472    2150   473.3    2525   468.5    3220   471.6    3850     466
    4174     435    4202     428    5098     428    5154     435    5330     457
    5355     456    5460     435    5516     428    6259     428    6301     435
    6400   451.5    6455     454    6580     456    6760     452    6850     424
    6880     426    6900     430    6950     452    7170     456    7550     456
    7770     452    7860     445    8200     445    8300     452    8998     472
#Mann= 12 ,-1,0
    1240     .04       0    3850     .09       0    4174     .05       0
    5154     .09       0    5460     .05       0    6301     .09       0
    6455     .14       0    6760    .055       0    6950     .06       0
    7770    .055       0    7860    .035       0    8200    .045       0
#XS Ineff= 2 ,-1
    4000    6500     449    8300    8998     480
Permanent Ineff=
       T       F
#Block Obstruct= 4 ,-1
    1240    1350     480    1350    1845     479    1995    2525     479
    2675    3700     479
Bank Sta=6760,6950
XS Rating Curve= 0 ,0
Exp/Cntr=0.3,0.1

Type RM Length L Ch R = 1 ,91637   ,856,1779,1148
BEGIN DESCRIPTION:
This cross section corresponds to cross section 91637 of the non-georeferenced CDC model which was the source of this model.
Proposed fill & lakes (3) on LOB.  Flow limit 1240  Flow limited in LOB due to sewer ridge.  LOB from 2001 aerial topo.  ROB OF X-SECTION BASED ON 1991 AND 2001 SURVEY DATA  SET COE NON-EFFECTIVE FLOW LIMIT AT FILL LINE IN ROB
END DESCRIPTION:
XS GIS Cut Line= 6
  2406048.778816 6979715.1134895 2406731.8620964 6977633.0231655
 2409815.1961528 6975619.1341486 2410079.0358482 6975366.1579486
 2410266.5617199 6975179.07695792410972.212002316974482.48745869
#Sta/Elev= 30
    1200     469    1990   473.5    3430     466    3744     435    3772     428
    4664     428    4720     435    4840     450    4940     450    5060     435
    5116     428    5751     428    5779     435    5855     454    5890     455
    5925     454    6001     435    6029     428    6194     435    6320     456
    6885     450    6909     426    6931     424    6975     431    7020     450
    7150     454    7500     445    7780     445    7830     453    8696     472
#Mann= 13 ,-1,0
    1200     .04       0    3430     .09       0    3744     .05       0
    4720     .09       0    5060     .05       0    5779     .09       0
    6001     .05       0    6194     .09       0    6320     .14       0
    6885    .055       0    7020     .06       0    7500    .035       0
    7780    .045       0
#XS Ineff= 2 ,-1
    3500    6300     452    7830    8696     480
Permanent Ineff=
       T       F
#Block Obstruct= 4 ,-1
    1200    1240     480    1240    1560     479    1710    2915     479
    3065    3280     479
Bank Sta=6885,7020
XS Rating Curve= 0 ,0
Exp/Cntr=0.3,0.1

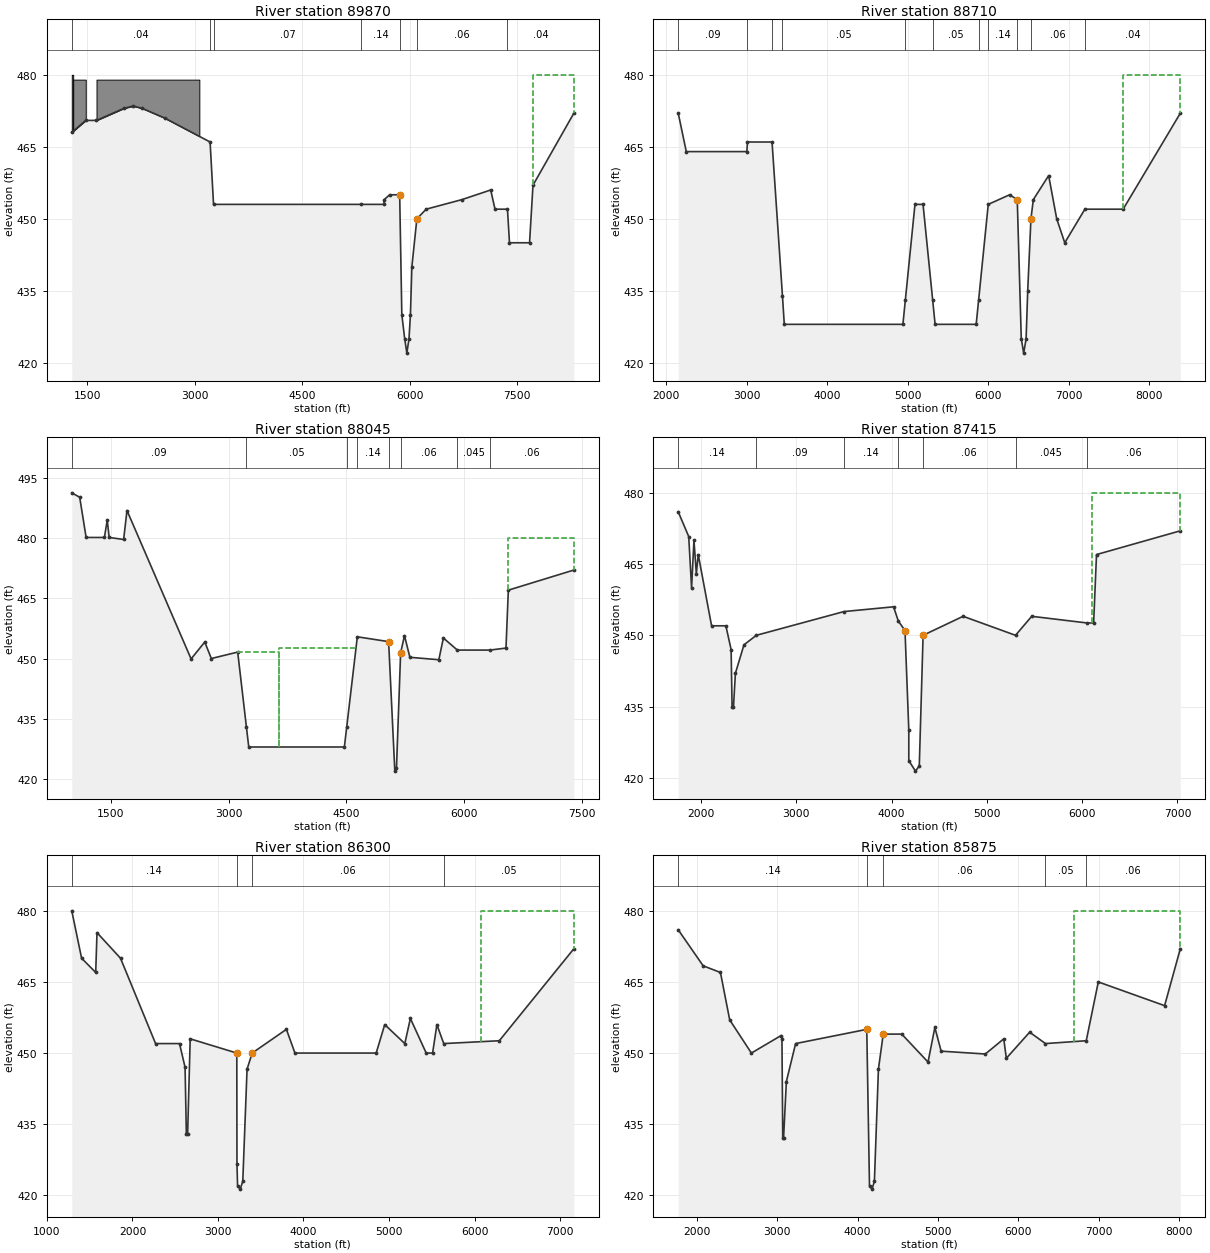
Type RM Length L Ch R = 1 ,89870   ,1028,1230,1023
BEGIN DESCRIPTION:
This cross section corresponds to cross section 89870 of the non-georeferenced CDC model which was the source of this model.
Proposed fill on LOB.  Flow limit 1305  LOB ground lowered to 457 and 453  LOB along sewer ridge.  Existing pond added to ROB.  LOB from 2001 aerial topo.  ROB OF X-SECTION BASED ON 1991 AND 2001 SURVEY DATA  SET COE NON-EFFECTIVE FLOW LIMIT AT FILL LINE IN ROB
END DESCRIPTION:
XS GIS Cut Line= 6
  2406223.789271 6979749.4576084      2406884.64     6977987.189
     2409280.473     6977327.467     2409467.973     6977042.745
     2410940.196     6976139.9672411426.112855726975841.99920085
#Sta/Elev= 30
    1285     468    1480   470.5    1630   470.5    2010     473    2140   473.5
    2270     473    2580     471    3215     466    3263     453    5325     453
    5640     453    5645     454    5720     455    5860     455    5890     430
    5930     425    5960     422    5990     425    6010     430    6030     440
    6100     450    6230     452    6730     454    7130     456    7190     452
    7364     452    7392     445    7672     445    7720     457    8290     472
#Mann= 7 ,-1,0
    1285     .04       0    3215     .09       0    3263     .07       0
    5325     .14       0    5860    .055       0    6100     .06       0
    7364     .04       0
#XS Ineff= 2 , 0
                            7720             480
Permanent Ineff=
       F       F
#Block Obstruct= 3 ,-1
    1285    1305     480    1305    1480     479    1630    3065     479
Bank Sta=5860,6100
XS Rating Curve= 0 ,0
Exp/Cntr=0.3,0.1

Type RM Length L Ch R = 1 ,88710   ,1110,568,444
BEGIN DESCRIPTION:
This cross section corresponds to cross section 88710 of the non-georeferenced CDC model which was the source of this model.
Proposed fill and lakes (2) in LOB.  Flow limited in LOB due to sewer ridge and D/S high ground.  LOB from 2001 aerial topo. - realigned for hydraulics - ROB OF X-SECTION BASED ON 1991 AND 2001 SURVEY DATA  SET COE NON-EFFECTIVE FLOW LIMIT AT FILL LINE IN ROB
END DESCRIPTION:
XS GIS Cut Line= 6
2407033.356106516980454.86166243  2407066.078149 6980339.7788345
     2407099.918     6980237.189     2407412.418     6979258.023
     2411174.952     6977166.217      2411765.65      6976840.42
#Sta/Elev= 30
    2150     472    2250     464    3002     464    3010     466    3315     466
    3444     434    3467     428    4940     428    4970     433    5090     453
    5190     453    5310     433    5340     428    5850     428    5880     433
    6000     453    6265     455    6360     454    6410     425    6440     422
    6470     425    6490     435    6530     450    6560     454    6750     459
    6850     450    6950     445    7200     452    7675     452    8385     472
#Mann= 11 ,-1,0
    2150     .09       0    3010     .04       0    3315     .09       0
    3444     .05       0    4970     .09       0    5310     .05       0
    5880     .09       0    6000     .14       0    6360    .055       0
    6530     .06       0    7200     .04       0
#XS Ineff= 3 ,-1
    3315    5100     453    5190    6000     453    7675    8385     480
Permanent Ineff=
       T       T       F
#Block Obstruct= 2 , 0
            2435     480
Bank Sta=6360,6530
XS Rating Curve= 0 ,0
Exp/Cntr=0.3,0.1

Type RM Length L Ch R = 1 ,88045   ,377,617,157
BEGIN DESCRIPTION:
This cross section corresponds to cross section 88045 of the non-georeferenced CDC model which was the source of this model.
Proposed lake in LOB.  Flow limited in LOB due to sewer ridge and D/S high ground.  CHANNEL BASED ON 1991 SURVEY DATA  SET COE NON-EFFECTIVE FLOW LIMIT AT FILL LINE IN ROB
END DESCRIPTION:
XS GIS Cut Line= 6
  2408234.632056 6981803.1598383 2409022.6114519 6980139.1474183
 2409395.8925295 6979350.9380367 2409852.1491629 6978387.5771026
 2410363.9699897 6978291.61108712411920.070240386976881.40353538
#Sta/Elev= 30
    1000   491.2    1101   490.1    1183   480.1    1416   480.1    1452   484.4
    1477   480.1    1661   479.6    1704   486.8    2521   449.9    2695   454.1
    2779     450    3115   451.6    3226     433    3256     428    4475     428
    4505     433    4640   455.4    5039   454.2    5118     422    5139   422.7
    5192   451.4    5241   455.7    5310   450.3    5679   449.7    5737   455.1
    5915   452.1    6332   452.1    6535   452.6    6565     467    7400     472
#Mann= 8 ,-1,0
    1000     .09       0    3226     .05       0    4505     .09       0
    4640     .14       0    5039    .055       0    5192     .06       0
    5915    .045       0    6332     .06       0
#XS Ineff= 3 ,-1
    3100    3640   451.5    3640    4650   452.5    6565    7400     480
Permanent Ineff=
       T       T       F
Bank Sta=5039,5192
XS Rating Curve= 0 ,0
Exp/Cntr=0.3,0.1

Type RM Length L Ch R = 1 ,87415   ,688,1145,205
BEGIN DESCRIPTION:
This cross section corresponds to cross section 87415 of the non-georeferenced CDC model which was the source of this model.
LOB from 2001 aerial topo. Far ROB from 2001 aerial topo - realigned for hydraulics -  ROB OF X-SECTION BASED ON 1991 AND 2001 SURVEY DATA  SET COE NON-EFFECTIVE FLOW LIMIT AT FILL LINE IN ROB  Added 2001 survey information for flood plain
END DESCRIPTION:
XS GIS Cut Line= 6
  2408820.035717 6980940.3439224 2409750.3609807 6979547.1033268
 2410068.0693348 6978942.9368842 2410401.4026576 6978927.3119155
 2410739.9443033  6978182.5200982412135.246462176977110.01177108
#Sta/Elev= 30
    1760     476    1870   470.8    1900     460    1925     470    1950     463
    1970     467    2110     452    2260     452    2315     447    2325     435
    2340     435    2360     442    2450     448    2580     450    3500     455
    4020     456    4070     453    4140     451    4180     430    4180   423.6
    4250   421.4    4290   422.5    4330     450    4750     454    5300     450
    5470     454    6050   452.6    6120   452.6    6150     467  7029.6     472
#Mann= 7 ,-1,0
    1760     .14       0    2580     .09       0    3500     .14       0
    4070    .055       0    4330     .06       0    5300    .045       0
    6050     .06       0
#XS Ineff= 2 , 0
                            6100             480
Permanent Ineff=
       F       F
Bank Sta=4140,4330
XS Rating Curve= 0 ,0
Exp/Cntr=0.3,0.1

Type RM Length L Ch R = 1 ,86300   ,394,480,411
BEGIN DESCRIPTION:
This cross section corresponds to cross section 86300 of the non-georeferenced CDC model which was the source of this model.
LOB from 2001 aerial topo. - realigned for hydraulics -  ROB OF X-SECTION BASED ON 1991 AND 2001 SURVEY DATA  SET COE NON-EFFECTIVE FLOW LIMIT AT FILL LINE IN ROB  Added 2001 survey information for flood plain
END DESCRIPTION:
XS GIS Cut Line= 6
  2408703.405812 6981373.7449416 2408849.3191476 6981255.4368524
 2410005.5694597 6980317.9367589 2410057.6526889 6980130.4368058
 2410885.7776731 6978349.18675942412384.155768146976970.24438076
#Sta/Elev= 30
    1290     480    1405     470    1570     467    1585   475.4    1860     470
    2270     452    2550     452    2615     447    2630     433    2645     433
    2675     453    3220     450    3222   426.7    3229     422    3261   421.3
    3290     423    3340   446.6    3400     450    3800     455    3900     450
    4850     450    4950     456    5185     452    5250   457.3    5435     450
    5510     450    5560     456    5640     452    6290   452.6 7161.68     472
#Mann= 4 ,-1,0
    1290     .14       0    3220    .055       0    3400     .06       0
    5640     .05       0
#XS Ineff= 2 , 0
                            6080             480
Permanent Ineff=
       F       F
Bank Sta=3220,3400
XS Rating Curve= 0 ,0
Exp/Cntr=0.3,0.1

Type RM Length L Ch R = 1 ,85875   ,264,1252,793
BEGIN DESCRIPTION:
This cross section corresponds to cross section 85875 of the non-georeferenced CDC model which was the source of this model.
LOB from 2001 aerial topo.-realigned for hydraulics - ROB from COE section 86951.  CHANNEL BASED ON 1991 AND 2001 SURVEY DATA  SET COE NON-EFFECTIVE FLOW LIMIT AT FILL LINE IN ROB  Added 2001 survey information for flood plain
CDC GP041795-1 Riverside Development
Cross-section 85875 - 94400
Located in ROB.
END DESCRIPTION:
XS GIS Cut Line= 6
     2409015.986     6981692.937     2410437.861      6980526.27
     2410614.944     6980135.645     2410500.361     6979635.645
     2411872.557     6977613.7562412527.285983586976834.47057364
#Sta/Elev= 30
    1770     476    2080   468.4    2295     467    2410     457    2680     450
    3050   453.7    3060     453    3070     432    3080     432    3115     444
    3230     452    4115     455    4149     422    4181   421.3    4210     423
    4260   446.6    4320     454    4550     454    4877   448.1    4962   455.4
    5040   450.4    5590   449.8    5819     453    5851   448.9    6141   454.4
    6338     452    6845   452.6    6995     465 7819.67     460    8015     472
#Mann= 5 ,-1,0
    1770     .14       0    4115    .055       0    4320     .06       0
    6338     .05       0    6845     .06       0
#XS Ineff= 2 , 0
                            6690             480
Permanent Ineff=
       F       F
Bank Sta=4115,4320
XS Rating Curve= 0 ,0
Exp/Cntr=0.3,0.1

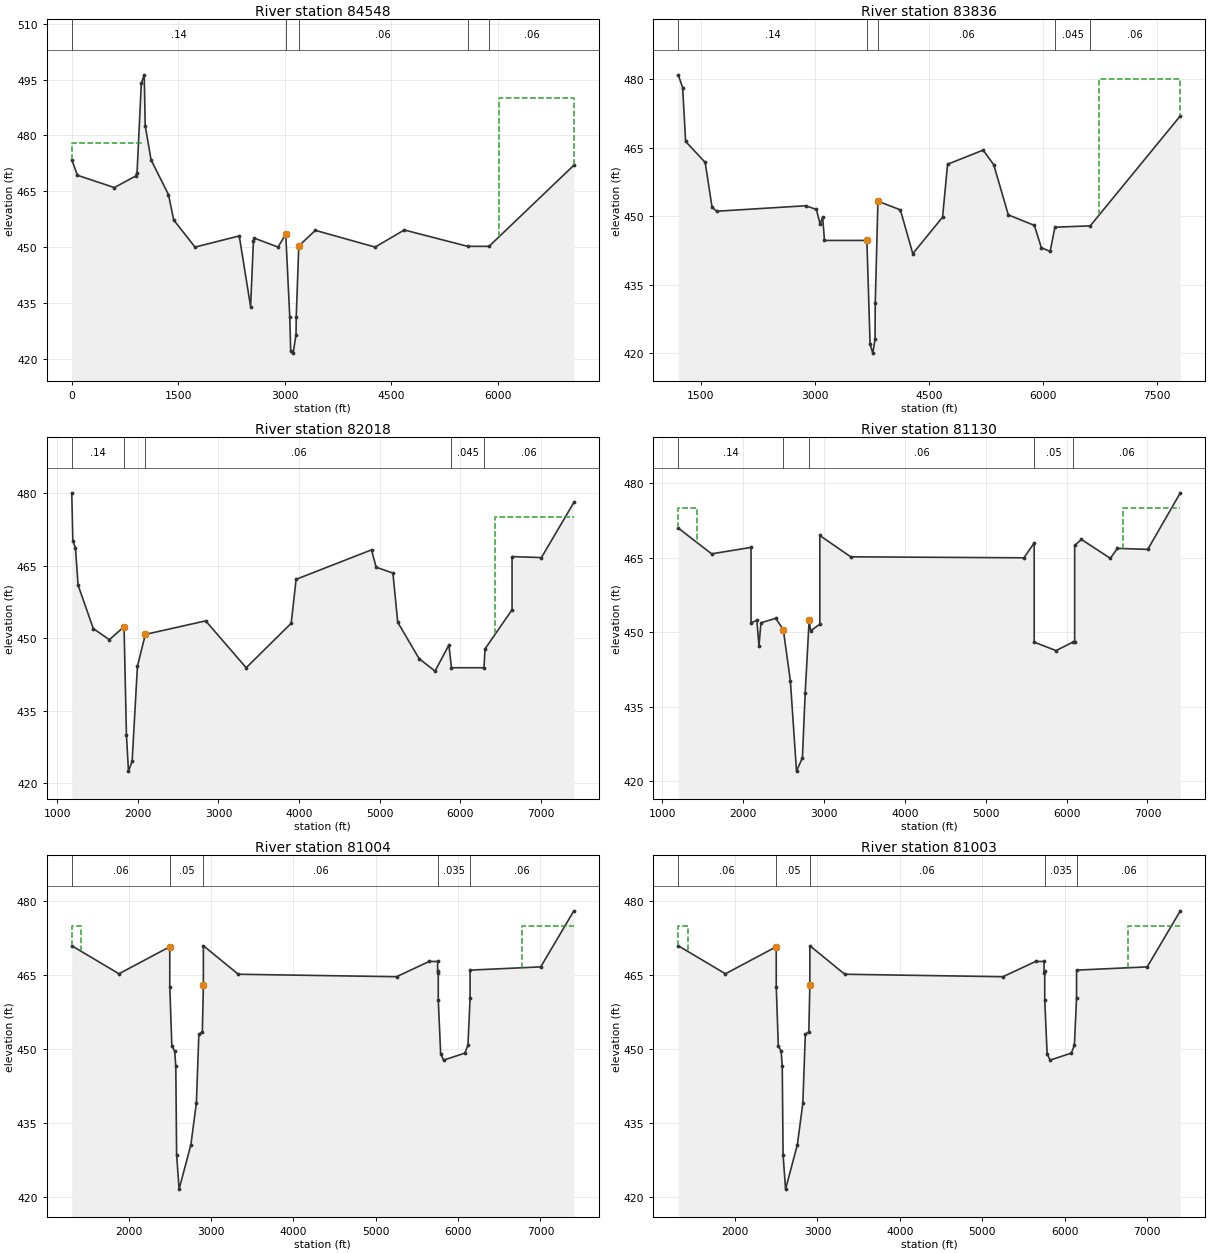
Type RM Length L Ch R = 1 ,84548   ,902,714,211
BEGIN DESCRIPTION:
This cross section corresponds to cross section 84548 of the non-georeferenced CDC model which was the source of this model.
Flow limit moved for SPF conditions.  GRs added from storage model.  Boyd Br added.
END DESCRIPTION:
XS GIS Cut Line= 6
     2408810.039     6982762.393     2409218.499     6981908.865
     2410395.959      6980754.75     2411259.658     6980322.901
     2412297.668     6977925.6072412347.992532436977025.01205531
#Sta/Elev= 30
       0   473.5      80   469.3     600     466     900   469.1     920     470
     980     494    1021   496.3    1035   482.6    1118   473.4    1363   464.1
    1436   457.3    1737     450    2360     453    2520     434    2560   451.7
    2573   452.4    2907     450    3015   453.5    3072   431.2    3085     422
    3120   421.5    3160   426.5    3163   431.2    3199   450.3    3432   454.5
    4275     450    4685   454.6    5580   450.2    5880   450.2    7075     472
#Mann= 5 ,-1,0
       0     .14       0    3015    .055       0    3199     .06       0
    5580    .045       0    5880     .06       0
#XS Ineff= 2 , 0
            1000     478    6015             490
Permanent Ineff=
       F       F
Bank Sta=3015,3199
XS Rating Curve= 0 ,0
Exp/Cntr=0.3,0.1

Type RM Length L Ch R = 1 ,83836   ,950,1818,200
BEGIN DESCRIPTION:
This cross section corresponds to cross section 83836 of the non-georeferenced CDC model which was the source of this model.
Flow limit moved for SPF conditions.  GRs added from storage model and 1991 topo.  Section modified for continuity.  See 100 yr model for modifications.
END DESCRIPTION:
XS GIS Cut Line= 6
     2409811.199     6982809.534     2411019.741     6980962.678
     2411547.557     6980802.734     2411878.949     6979696.036
     2412299.304     6977953.9412412366.388365966977067.47714849
#Sta/Elev= 30
    1207     481    1265   478.2    1304   466.4    1561   461.8    1651     452
    1711   451.1    2880   452.3    3021   451.5    3071   448.3    3104   449.8
    3128   444.7    3685   444.7    3727     422    3762     420    3792     423
    3795     431    3830   453.3    4125   451.4    4288   441.8    4679   449.8
    4745   461.4    5212   464.5    5351   461.3    5543   450.3    5885     448
    5977   443.1    6092   442.3    6155   447.6    6619   447.9    7802     472
#Mann= 5 ,-1,0
    1207     .14       0    3685    .055       0    3830     .06       0
    6155    .045       0    6619     .06       0
#XS Ineff= 2 , 0
                            6735             480
Permanent Ineff=
       F       F
Bank Sta=3685,3830
XS Rating Curve= 0 ,0
Exp/Cntr=0.5,0.3

Type RM Length L Ch R = 1 ,82018   ,309,886,399
BEGIN DESCRIPTION:
This cross section corresponds to cross section 82018 of the non-georeferenced CDC model which was the source of this model.
Flow limit moved for SPF conditions.  Data added to relief from CORPS data.  See 100 yr model for modifications.
END DESCRIPTION:
XS GIS Cut Line= 6
     2410800.738     6983123.357     2411243.663     6982242.231
     2411899.434     6981010.661     2412203.328     6979779.091
     2412351.956     6977334.862     2412358.376     6977209.727
#Sta/Elev= 30
    1182   480.1    1195   470.2    1228   468.7    1260     461    1449     452
    1648   449.7    1830   452.4    1860   429.9    1885   422.5    1930   424.5
    1996   444.2    2094   450.8    2842   453.6    3344   443.9    3902   453.1
    3963   462.2    4898   468.3    4955   464.7    5163   463.5    5223   453.3
    5487   445.8    5685   443.2    5857   448.6    5889   443.9    6292   443.9
    6305   447.8    6640   455.9    6640   466.9    7004   466.7    7406   478.1
#Mann= 5 ,-1,0
    1182     .14       0    1830    .055       0    2094     .06       0
    5889    .045       0    6292     .06       0
#XS Ineff= 2 , 0
                            6430             475
Permanent Ineff=
       F       F
Bank Sta=1830,2094
XS Rating Curve= 0 ,0
Exp/Cntr=0.5,0.3

Type RM Length L Ch R = 1 ,81130   ,126,126,126
BEGIN DESCRIPTION:
This cross section corresponds to cross section 81130 of the non-georeferenced CDC model which was the source of this model.
Left flow limit due to u/s high ground.  Right flow limit due to d/s high ground.  Data added to relief from CORPS data.  Cont/Exp raised due to influences from SH 360.  'n' value lowered to reflect irregular pavement section and short vegetation. CDC ARL062007-1 Viridian Project
Cross-section 81131 - 109405
Located in LOB.
END DESCRIPTION:
XS GIS Cut Line= 6
   2411057.64181 6983220.6152984 2412147.2449664 6981288.3380333
 2412527.5119224 6980100.0031396  2412618.258132  6979367.557098
 2412613.9359622 6978559.4901446 2412358.3597017 6977398.0984385
#Sta/Elev= 30
    1200     471    1613   465.8    2100   467.1    2100   451.9    2172   452.4
    2198   447.2    2222   451.9    2405   452.8    2499   450.5    2586   440.2
    2662     422    2735   424.7    2769   437.7    2818   452.4    2837   450.3
    2950   451.6    2950   469.5    3332   465.2    5473     465    5600     468
    5600     448    5870   446.3    6077     448    6100     448    6100   467.5
    6184   468.7    6541   464.9    6629   466.9    7004   466.7    7406   478.1
#Mann= 5 ,-1,0
    1200     .14       0    2499    .055       0    2818     .06       0
    5600     .05       0    6077     .06       0
#XS Ineff= 2 , 0
            1435     475    6700             475
Permanent Ineff=
       F       F
Bank Sta=2499,2818
XS Rating Curve= 0 ,0
Exp/Cntr=0.5,0.3

Type RM Length L Ch R = 1 ,81004   ,1,1,1
BEGIN DESCRIPTION:
This cross section corresponds to cross section 81004 of the non-georeferenced CDC model which was the source of this model.
Left flow limit due to u/s high ground.  Right flow limit due to d/s high ground.  'n' value lowered through relief bridge to reflect normal high grass and regular pavement section.  Relief bridge surveyed 10-06.
END DESCRIPTION:
XS GIS Cut Line= 6
  2411103.941935 6983383.1987873 2412126.6193515 6981607.3331302
 2412515.5283506 6980637.2202411 2412694.8593567 6979762.1740909
 2412738.0715407 6979055.6551627 2412514.6582736 6977680.4269421
#Sta/Elev= 30
    1310     471    1883   465.3    2500   470.8    2500   462.7    2525   450.7
    2560   449.5    2573   446.5    2583   428.5    2613   421.5    2756   430.5
    2823     439    2853     453  2895.5   453.5    2908     463    2908     471
    3332   465.2    5253   464.7    5649   467.8    5752   467.8    5752  465.51
    5760  465.88    5760  459.92    5789  449.02    5825  447.74    6082  449.16
    6120  450.76    6146  460.29    6146  466.04    7004   466.7    7406   478.1
#Mann= 5 ,-1,0
    1310     .06       0    2500     .05       0    2908     .06       0
    5760    .035       0    6146     .06       0
#XS Ineff= 2 , 0
            1425     475    6775             475
Permanent Ineff=
       F       F
Bank Sta=2500,2908
XS Rating Curve= 0 ,0
Exp/Cntr=0.5,0.3

Type RM Length L Ch R = 1 ,81003   ,90,90,90
BEGIN DESCRIPTION:
This cross section corresponds to cross section 81003 of the non-georeferenced CDC model which was the source of this model.
Left flow limit due to u/s high ground.  Right flow limit due to d/s high ground.  'n' value lowered through relief bridge to reflect normal high grass and regular pavement section.  Relief bridge surveyed 10-06.
END DESCRIPTION:
XS GIS Cut Line= 6
  2411108.350972 6983377.5437578 2412127.4631818 6981607.7986805
 2412517.0785443 6980635.8980652 2412696.7199173 6979759.3079549
 2412740.0065762 6979051.5711814 2412516.3026272 6977674.0076636
#Sta/Elev= 30
    1310     471    1883   465.3    2500   470.8    2500   462.7    2525   450.7
    2560   449.5    2573   446.5    2583   428.5    2613   421.5    2756   430.5
    2823     439    2853     453  2895.5   453.5    2908     463    2908     471
    3332   465.2    5253   464.7    5649   467.8    5752   467.8    5752  465.51
    5760  465.88    5760  459.92    5789  449.02    5825  447.74    6082  449.16
    6120  450.76    6146  460.29    6146  466.04    7004   466.7    7406   478.1
#Mann= 5 ,-1,0
    1310     .06       0    2500     .05       0    2908     .06       0
    5760    .035       0    6146     .06       0
#XS Ineff= 2 , 0
            1425     475    6775             475
Permanent Ineff=
       F       F
Bank Sta=2500,2908
XS Rating Curve= 0 ,0
Exp/Cntr=0.5,0.3