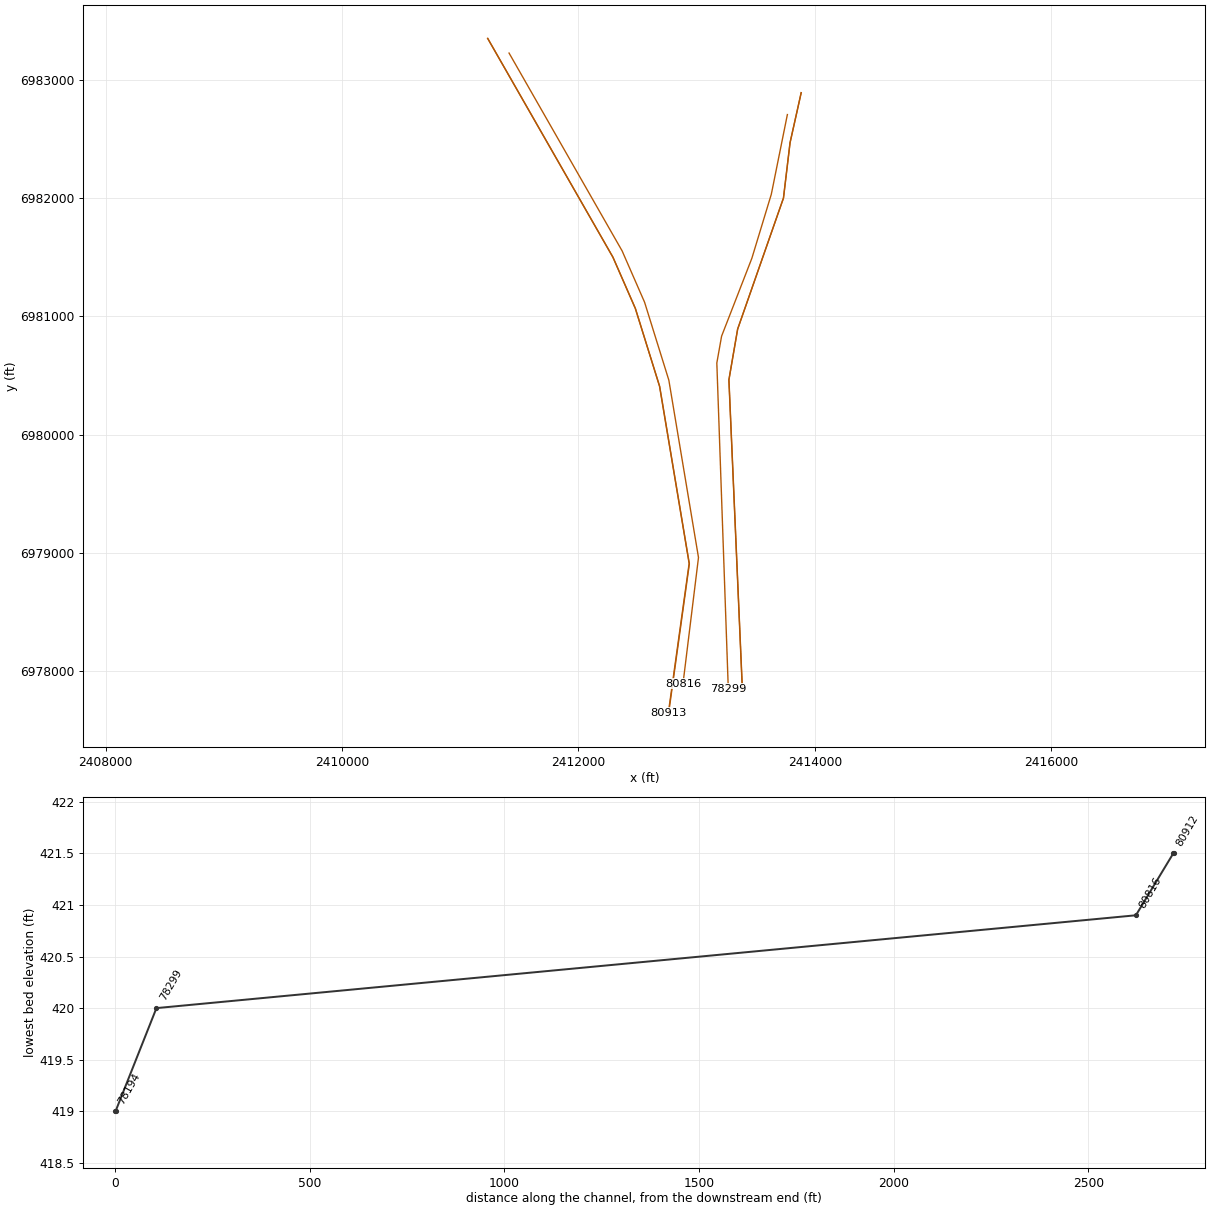
HEC-RAS study CDC_Consolidated_Model.prj: Upper Trinity CDC Consolidated Model

--- CDC_Consolidated_Model.g13 (geometry) --- (continued)

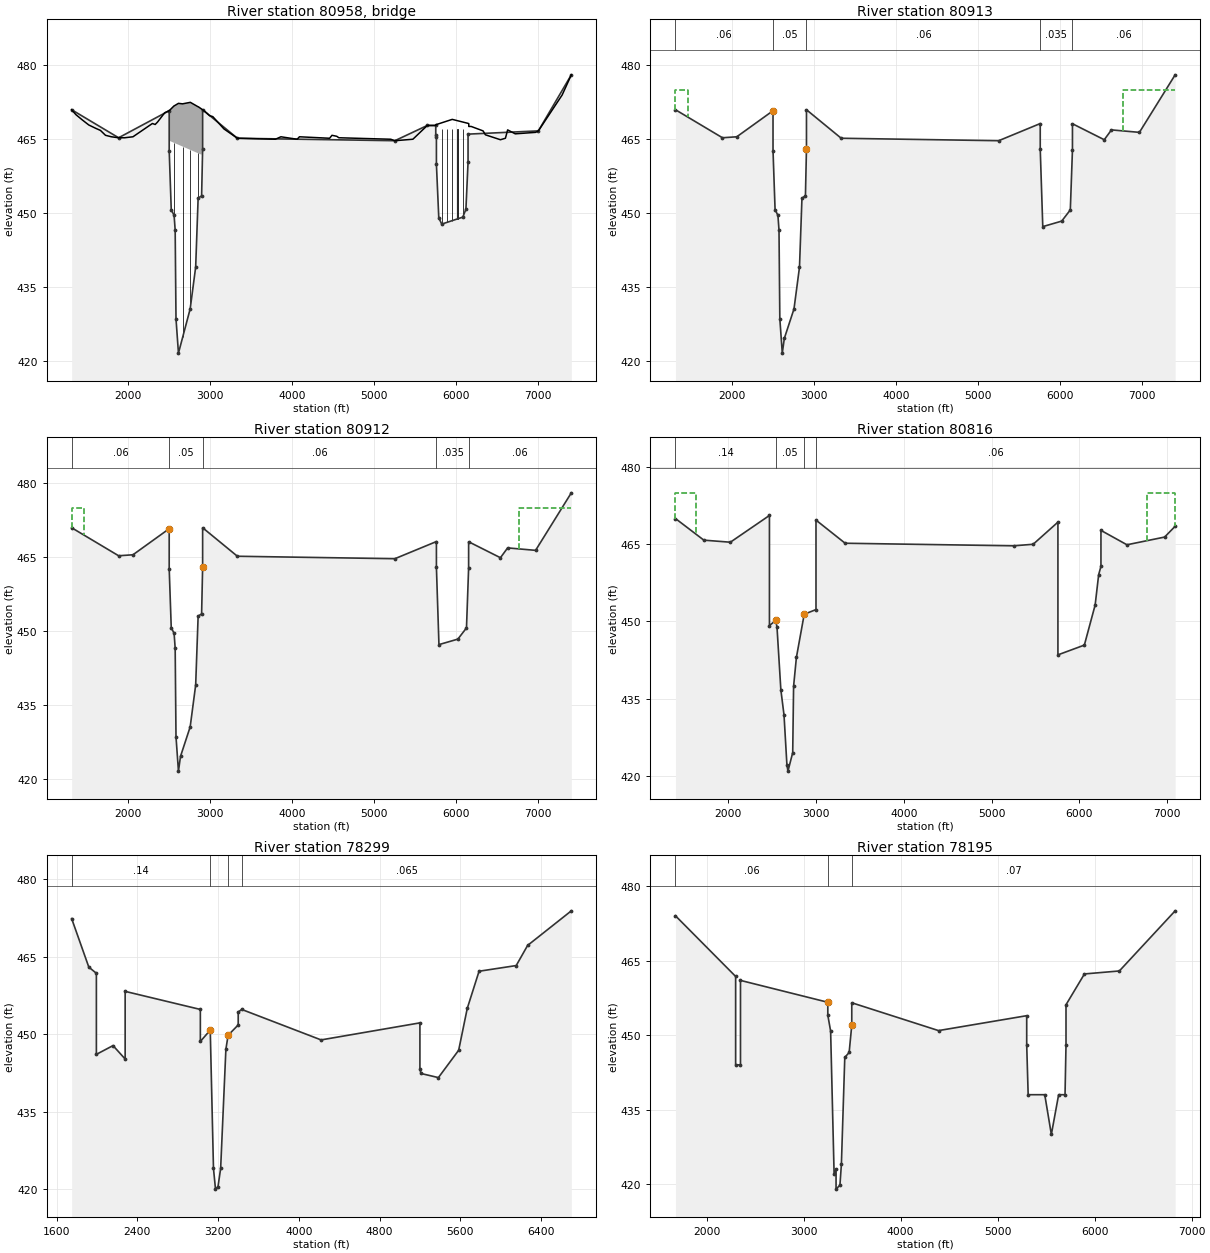
Type RM Length L Ch R = 3 ,80958   ,,,
BEGIN DESCRIPTION:
S.H. 360
Relief bridge superelevated.  D/S sided higher.  Relief bridge surveyed 10-06.
END DESCRIPTION:
Node Name=S.H. 360
Bridge Culvert--1,0,-1,-1, 0
Deck Dist Width WeirC Skew NumUp NumDn MinLoCord MaxHiCord MaxSubmerge Is_Ogee
1,88,2.6,0, 62, 62, , , 0.95, 0, ,,,
    1310    1362    1442    1519    1606    1661    1723    1795    1883    1956
    2058    2295    2329    2358    2446    2500    2500    2560  2562.5    2613
    2663    2756  2758.5    2853  2855.5    2908    2908    2952    2992    3032
    3168    3332    3796    3863    4061    4089    4457    4486    4544    4570
    5203    5253    5473    5649    5752    5752    5760    5953    6146    6155
    6155    6184    6329    6358    6541    6602    6629    6722    6970    7004
    7294    7406
     471     470   468.9   467.9   467.2   466.8   465.8   465.5   465.3   465.3
   465.5   468.2     468   468.5   470.4   470.8   470.8   471.8   471.8   472.3
   472.2   472.5   472.5   471.6   471.6     471     471   470.4   469.8   469.6
   467.1   465.2     465   465.5     465   465.5   465.2   465.8   465.6   465.3
     465   464.7     465   467.8   467.8  467.89  467.99  469.04  468.23  468.17
   467.6   467.6   466.7   465.9   464.9   465.2   466.9   466.1   466.4   466.7
     474   478.1
                                                   464.6     465   464.1   464.1
   464.1   464.1   464.1   464.1   465.1   464.7
                                                  461.75  462.86  461.93
    1310    1362    1442    1519    1606    1661    1723    1795    1883    1956
    2058    2295    2329    2358    2446    2500    2500    2560  2562.5    2613
    2663    2756  2758.5    2853  2855.5    2908    2908    2952    2992    3032
    3168    3332    3796    3863    4061    4089    4457    4486    4544    4570
    5203    5253    5473    5649    5751    5751    5760    5956    6153    6161
    6161    6184    6329    6358    6541    6602    6629    6722    6970    7004
    7294    7406
     471     470   468.9   467.9   467.2   466.8   465.8   465.5   465.3   465.3
   465.5   468.2     468   468.5   470.4   470.8   470.8   471.8   471.8   472.3
   472.2   472.5   472.5   471.6   471.6     471     471   470.4   469.8   469.6
   467.1   465.2     465   465.5     465   465.5   465.2   465.8   465.6   465.3
     465   464.7     465     468   468.9  470.78  470.89  472.11  470.89  470.79
     469   468.7   466.7   465.9   464.9   465.2   466.9   466.1   466.4   466.7
     474   478.1
                                                   464.6     465   464.1   464.1
   464.1   464.1   464.1   464.1   465.1   464.7
                                                  464.04  465.24  464.06
Pier Skew, UpSta & Num, DnSta & Num=  ,2561.25, 2 ,2561.25, 2 , 0 , 0 , 0 ,,
     2.5     2.5
     420     467
     2.5     2.5
     420     467
Pier Skew, UpSta & Num, DnSta & Num=  ,2664.25, 2 ,2664.25, 2 , 0 , 0 , 0 ,,
     2.5     2.5
     420     467
     2.5     2.5
     420     467
Pier Skew, UpSta & Num, DnSta & Num=  ,2758.25, 2 ,2758.25, 2 , 0 , 0 , 0 ,,
     2.5     2.5
     420     467
     2.5     2.5
     420     467
Pier Skew, UpSta & Num, DnSta & Num=  ,2854.25, 2 ,2854.25, 2 , 0 , 0 , 0 ,,
     2.5     2.5
     420     467
     2.5     2.5
     420     467
Pier Skew, UpSta & Num, DnSta & Num=  ,5825, 2 ,5825, 2 , 0 , 0 , 0 ,,
       3       3
     420     467
       3       3
     420     467
Pier Skew, UpSta & Num, DnSta & Num=  ,5889, 2 ,5891, 2 , 0 , 0 , 0 ,,
       3       3
     420     467
       3       3
     420     467
Pier Skew, UpSta & Num, DnSta & Num=  ,5953, 2 ,5956, 2 , 0 , 0 , 0 ,,
       3       3
     420     467
       3       3
     420     467
Pier Skew, UpSta & Num, DnSta & Num=  ,6017, 2 ,6022, 2 , 0 , 0 , 0 ,,
       3       3
     420     467
       3       3
     420     467
Pier Skew, UpSta & Num, DnSta & Num=  ,6082, 2 ,6087, 2 , 0 , 0 , 0 ,,
       3       3
     420     467
       3       3
     420     467
BR Coef= 1 , 0 , 0 ,1.05, 0 ,,,0.8,-1,0.5,1,
WSPro=,,,, 1 ,,,, 0 ,,,, 0 ,,,,-1 ,-1 ,-1 , 0 , 0 , 0 , 0 , 0
BC Design=,, 0 ,, 0 ,,,,,,
BC HTab HWMax=478.1
BC Use User HTab Curves=0
BC User HTab FreeFlow(D)= 0

Type RM Length L Ch R = 1 ,80913   ,1,1,1
BEGIN DESCRIPTION:
This cross section corresponds to cross section 80913 of the non-georeferenced CDC model which was the source of this model.
Flow limits due to d/s high ground.  'n' value lowered through relief bridge to reflect normal high grass and regular pavement section.  Relief bridge surveyed 10-06.
END DESCRIPTION:
XS GIS Cut Line= 6
  2411231.377001 6983351.3869289 2412291.5563576 6981500.4291446
 2412481.2931828 6981067.0664942 2412686.2429042 6980409.0701068
 2412936.8290172 6978910.7876703 2412760.6915345 6977645.8100276
#Sta/Elev= 30
    1310     471    1883   465.3    2058   465.5    2500   470.8    2500   462.7
    2525   450.7    2560   449.5    2573   446.5    2583   428.5    2613   421.5
    2638   424.5    2756   430.5    2823     439    2853     453  2895.5   453.5
    2908     463    2908     471    3332   465.2    5253   464.7    5760  468.19
    5760  462.97    5791  447.23    6022  448.35    6127  450.63    6153  462.81
    6153  468.15    6541   464.9    6629   466.9    6970   466.4    7406   478.1
#Mann= 5 ,-1,0
    1310     .06       0    2500     .05       0    2908     .06       0
    5760    .035       0    6153     .06       0
#XS Ineff= 2 , 0
            1465     475    6770             475
Permanent Ineff=
       F       F
Bank Sta=2500,2908
XS Rating Curve= 0 ,0
Exp/Cntr=0.5,0.3

Type RM Length L Ch R = 1 ,80912   ,96,96,96
BEGIN DESCRIPTION:
This cross section corresponds to cross section 80912 of the non-georeferenced CDC model which was the source of this model.
Flow limits due to d/s high ground.  'n' value lowered through relief bridge to reflect normal high grass and regular pavement section.  Relief bridge surveyed 10-06.
END DESCRIPTION:
XS GIS Cut Line= 6
  2411234.004349 6983348.8685622 2412292.6410011 6981500.5239607
 2412482.7738229 6981066.2410366 2412688.0319426  6980407.255806
 2412938.9389211 6978907.3877427 2412763.3695778 6977642.9633245
#Sta/Elev= 30
    1310     471    1883   465.3    2058   465.5    2500   470.8    2500   462.7
    2525   450.7    2560   449.5    2573   446.5    2583   428.5    2613   421.5
    2638   424.5    2756   430.5    2823     439    2853     453  2895.5   453.5
    2908     463    2908     471    3332   465.2    5253   464.7    5760  468.19
    5760  462.97    5791  447.23    6022  448.35    6127  450.63    6153  462.81
    6153  468.15    6541   464.9    6629   466.9    6970   466.4    7406   478.1
#Mann= 5 ,-1,0
    1310     .06       0    2500     .05       0    2908     .06       0
    5760    .035       0    6153     .06       0
#XS Ineff= 2 , 0
            1465     475    6770             475
Permanent Ineff=
       F       F
Bank Sta=2500,2908
XS Rating Curve= 0 ,0
Exp/Cntr=0.5,0.3

Type RM Length L Ch R = 1 ,80816   ,2199,2516,280
BEGIN DESCRIPTION:
This cross section corresponds to cross section 80816 of the non-georeferenced CDC model which was the source of this model.
Flow limits due to d/s high ground.  Left 'n' value corrected from 0.014 to 0.14.  Data added to relief from CORPS data.
END DESCRIPTION:
XS GIS Cut Line= 6
  2411413.125112 6983226.9088134 2412369.7881565 6981554.0930792
 2412559.9209783 6981119.8101552  2412765.179098 6980460.8249246
 2413016.0860765 6978960.9568613 2412884.9808202 6977894.6029986
#Sta/Elev= 30
    1400     470    1723   465.8    2025   465.4    2470   470.6    2470   449.2
    2542   450.2    2556   448.9    2600   436.7    2636   431.8    2669   422.1
    2681   420.9    2735   424.5    2745   437.4    2777     443    2866   451.4
    3000   452.3    3000   469.7    3332   465.2    5253   464.7    5473     465
    5755   469.3    5755   443.5    6056   445.4    6179   453.2    6219   459.1
    6245   460.7    6245   467.7    6541   464.9    6970   466.4    7090   468.5
#Mann= 4 ,-1,0
    1400     .14       0    2542     .05       0    2866     .09       0
    3000     .06       0
#XS Ineff= 2 , 0
            1635     475    6770             475
Permanent Ineff=
       F       F
Bank Sta=2542,2866
XS Rating Curve= 0 ,0
Exp/Cntr=0.5,0.3

Type RM Length L Ch R = 1 ,78299   ,105,105,105
BEGIN DESCRIPTION:
This cross section corresponds to cross section 78299 of the non-georeferenced CDC model which was the source of this model.
Railroad lowered 2' below rails.  Left 'n' value corrected from 0.014 to 0.14.  Data added to LOB from CORPS data.  'n' value changed in ROB  to transition from RR to 360 'n' value.
END DESCRIPTION:
XS GIS Cut Line= 6
  2413768.241068 6982706.7886085 2413632.3000672 6982032.7138412
 2413467.6439004 6981491.1801473 2413211.5141633 6980832.5590892
    2413171.2649 6980605.6999629  2413268.339753 6977849.5186728
#Sta/Elev= 30
    1750   472.4    1920     463    1995   461.8    1995   446.1    2160   447.8
    2280   445.2    2280   458.3    3025   454.8    3025   448.6    3123   450.8
    3155     424    3175     420    3200   420.5    3226     424    3278   447.1
    3300   449.8    3400   451.8    3400   454.3    3435   454.8    4221   448.9
    5200   452.2    5200   443.3    5210   442.4    5383   441.6    5584   446.9
    5669     455    5786   462.2    6154   463.3    6267   467.2    6700   473.9
#Mann= 4 ,-1,0
    1750     .14       0    3123     .05       0    3300     .09       0
    3435    .065       0
Bank Sta=3123,3300
XS Rating Curve= 0 ,0
Exp/Cntr=0.5,0.3

Type RM Length L Ch R = 1 ,78195   ,1,1,1
BEGIN DESCRIPTION:
This cross section corresponds to cross section 78195 of the non-georeferenced CDC model which was the source of this model.
Far LOB extended with 1991 topo.  High ground from u/s added to ROB.  'n' value raised in ROB  to be consistent.
END DESCRIPTION:
XS GIS Cut Line= 6
  2413884.730336  6982892.148474 2413790.3046724 6982468.5171034
 2413734.5738128 6982000.4803098 2413346.8859398 6980892.4546387
 2413272.9149592 6980463.4548406 2413387.0961613 6977837.8193438
#Sta/Elev= 30
    1680     474    2300   461.8    2300     444    2350     444    2350     461
    3250   456.6    3250     454    3279   450.8    3315     422    3335     423
    3335     419    3375   419.8    3390     424    3425   445.5    3470   446.5
    3497     452    3497   456.5    4391   450.9    5300   453.9    5300     448
    5315     438    5486     438    5554     430    5629     438    5695     438
    5705     448    5705   456.1    5895   462.3    6255   462.9    6830     475
#Mann= 3 ,0,0
    1680     .06       0    3250     .05       0    3497     .07       0
Bank Sta=3250,3497
XS Rating Curve= 0 ,0
Exp/Cntr=0.5,0.3

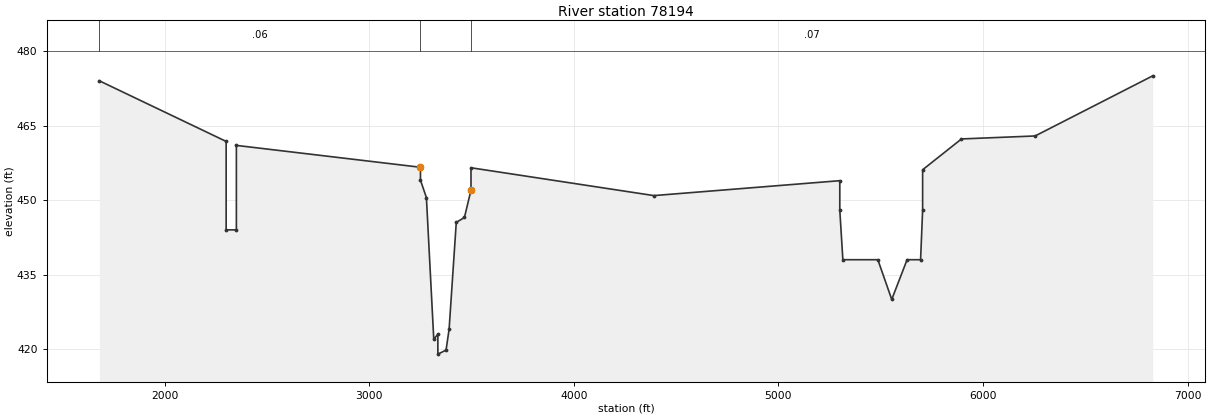
Type RM Length L Ch R = 1 ,78194   ,10,10,10
BEGIN DESCRIPTION:
This cross section corresponds to cross section 78194 of the non-georeferenced CDC model which was the source of this model.
Far LOB extended with 1991 topo.  High ground from u/s added to ROB.  'n' value raised in ROB  to be consistent.
END DESCRIPTION:
XS GIS Cut Line= 6
  2413885.692276 6982891.6369921 2413791.4414812  6982468.980029
 2413735.6144931 6982000.5170552 2413347.9069352 6980892.4146126
 2413274.0288021 6980463.9505745 2413388.2470776 6977837.5526121
#Sta/Elev= 30
    1680     474    2300   461.8    2300     444    2350     444    2350     461
    3250   456.6    3250     454    3279   450.5    3315     422    3335     423
    3335     419    3375   419.8    3390     424    3425   445.5    3465   446.5
    3497     452    3497   456.5    4391   450.9    5300   453.9    5300     448
    5315     438    5486     438    5554     430    5629     438    5695     438
    5705     448    5705   456.1    5895   462.3    6255   462.9    6830     475
#Mann= 3 ,0,0
    1680     .06       0    3250     .05       0    3497     .07       0
Bank Sta=3250,3497
XS Rating Curve= 0 ,0
Exp/Cntr=0.5,0.3