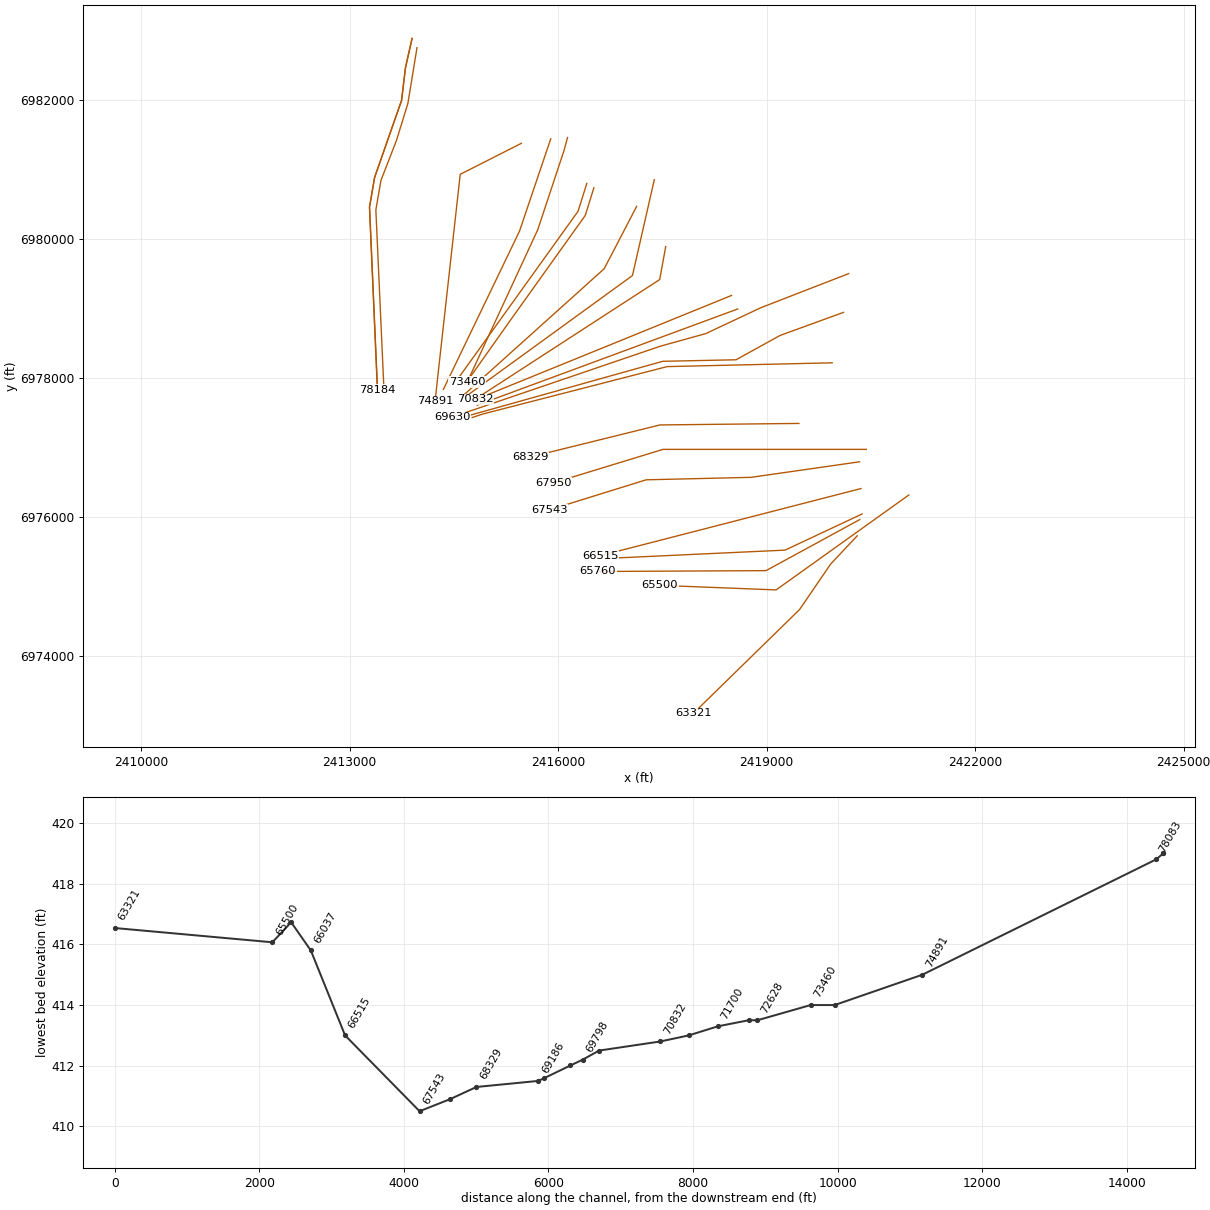
HEC-RAS study CDC_Consolidated_Model.prj: Upper Trinity CDC Consolidated Model

--- CDC_Consolidated_Model.g13 (geometry) --- (continued)

Type RM Length L Ch R = 3 ,78189   ,,,
BEGIN DESCRIPTION:
Union Pacific Railroad
END DESCRIPTION:
Node Name=Union Pacific Ra
Bridge Culvert--1,0,-1,-1, 0
Deck Dist Width WeirC Skew NumUp NumDn MinLoCord MaxHiCord MaxSubmerge Is_Ogee
1,8,2.6,0, 68, 73, , , 0.95, 0, 0,0,,
    1680    1900    2080    2112    2142    2224    2246    2300    2300    2350
    2350    2408    3250    3250    3265    3266    3275    3275    3279    3437
    3441    3441    3465    3470    3497    3497    3529    3552    3605    3911
    3986    4066    4138    4198    4226    4311    4391    4462    4507    5266
    5300    5300    5400    5404    5482    5482    5486    5526    5530    5577
    5583    5629    5633    5633    5668    5673    5705    5705    5805    5895
    6208    6255    6423    6431    6570    6605    6732    6830
     474     469     465   464.9   464.1   463.1   462.5   461.8   461.8     461
     461   460.5   456.6   456.6   456.5   456.5   456.5   456.5   456.5   456.5
   456.5   456.5   456.5   456.5   456.5   456.5   456.3   456.2   456.8   454.7
   453.6   453.4   452.8   452.5   451.9   451.2   450.9   451.2     451   453.4
   453.9   453.9   454.4   454.4   454.9   454.9   454.9   455.2   455.2   455.5
   455.5   455.7   455.7   455.7     456     456   456.1   456.1   457.4   462.3
   462.3   462.9   466.5   467.4   470.4   471.7   474.3     475
                                                                   459.8   459.8
                           455.8   455.8   455.8   455.8     453     453     453
     453   454.6   454.6   454.6   454.6
           452.5   452.5   452.5   452.5   448.9   448.9   449.2   449.2   449.5
   449.5   449.7   449.7   453.7     454     454   454.1
    1680    1900    2080    2112    2142    2224    2246    2300    2300    2350
    2350    2408    3250    3250    3265    3266    3275    3275    3279    3437
    3441    3441    3465    3470    3497    3497    3529    3552    3605    3911
    3986    4066    4138    4198    4226    4311    4391    4462    4507    5266
    5300    5300    5400    5404    5482    5482    5486    5526    5530    5577
    5583    5629    5633    5633    5668    5673    5705    5705    5745    5755
    5770    5900    5960    6010    6100    6150    6255    6423    6431    6570
    6605    6732    6830
     474     469     465   464.9   464.1   463.1   462.5   461.8   461.8     461
     461   460.5   456.6   456.6   456.5   456.5   456.5   456.5   456.5   456.5
   456.5   456.5   456.5   456.5   456.5   456.5   456.3   456.2   456.8   454.7
   453.6   453.4   452.8   452.5   451.9   451.2   450.9   451.2     451   453.4
   453.9   453.9   454.4   454.4   454.9   454.9   454.9   455.2   455.2   455.5
   455.5   455.7   455.7   455.7     456     456   456.1   456.1   456.6   460.8
     461     461     462     462   461.5   461.5   462.9   466.5   467.4   470.4
   471.7   474.3     475
                                                                   459.8   459.8
                           455.8   455.8   455.8   455.8     453     453     453
     453   454.6   454.6   454.6   454.6
           452.5   452.5   452.5   452.5   448.9   448.9   449.2   449.2   449.5
   449.5   449.7   449.7   453.7     454     454   454.1
Pier Skew, UpSta & Num, DnSta & Num=  ,3265.5, 2 ,3265.5, 2 , 0 , 0 , 0 ,,
       1       1
     450     456
       1       1
     450     456
Pier Skew, UpSta & Num, DnSta & Num=  ,3277, 2 ,3277, 2 , 0 , 0 , 0 ,,
       4       4
     450     456
       4       4
     450     456
Pier Skew, UpSta & Num, DnSta & Num=  ,3439, 2 ,3439, 2 , 0 , 0 , 0 ,,
       4       4
     450     456
       4       4
     450     456
Pier Skew, UpSta & Num, DnSta & Num=  ,3467.5, 2 ,3467.5, 2 , 0 , 0 , 0 ,,
       5       5
     450     456
       5       5
     450     456
Pier Skew, UpSta & Num, DnSta & Num=  ,5317, 2 ,5317, 2 , 0 , 0 , 0 ,,
       4       4
     430     453
       4       4
     430     453
Pier Skew, UpSta & Num, DnSta & Num=  ,5382, 2 ,5382, 2 , 0 , 0 , 0 ,,
       4       4
     430     453
       4       4
     430     453
Pier Skew, UpSta & Num, DnSta & Num=  ,5402, 2 ,5402, 2 , 0 , 0 , 0 ,,
       4       4
     430     453
       4       4
     430     453
Pier Skew, UpSta & Num, DnSta & Num=  ,5484, 2 ,5484, 2 , 0 , 0 , 0 ,,
       4       4
     430     453
       4       4
     430     453
Pier Skew, UpSta & Num, DnSta & Num=  ,5528, 2 ,5528, 2 , 0 , 0 , 0 ,,
       4       4
     430     453
       4       4
     430     453
Pier Skew, UpSta & Num, DnSta & Num=  ,5579, 2 ,5579, 2 , 0 , 0 , 0 ,,
       4       4
     430     453
       4       4
     430     453
Pier Skew, UpSta & Num, DnSta & Num=  ,5631, 2 ,5631, 2 , 0 , 0 , 0 ,,
       4       4
     430     453
       4       4
     430     453
Pier Skew, UpSta & Num, DnSta & Num=  ,5670.5, 2 ,5670.5, 2 , 0 , 0 , 0 ,,
       4       4
     430     455
       4       4
     430     455
BR Coef=-1 , 0 , 0 ,, 0 ,,,0.8,-1,,1,
WSPro=,,,, 1 ,,,, 0 ,,,, 0 ,,,,-1 ,-1 ,-1 , 0 , 0 , 0 , 0 , 0
BC Design=,, 0 ,, 0 ,,,,,,
BC HTab HWMax=475
BC Use User HTab Curves=0
BC User HTab FreeFlow(D)= 0

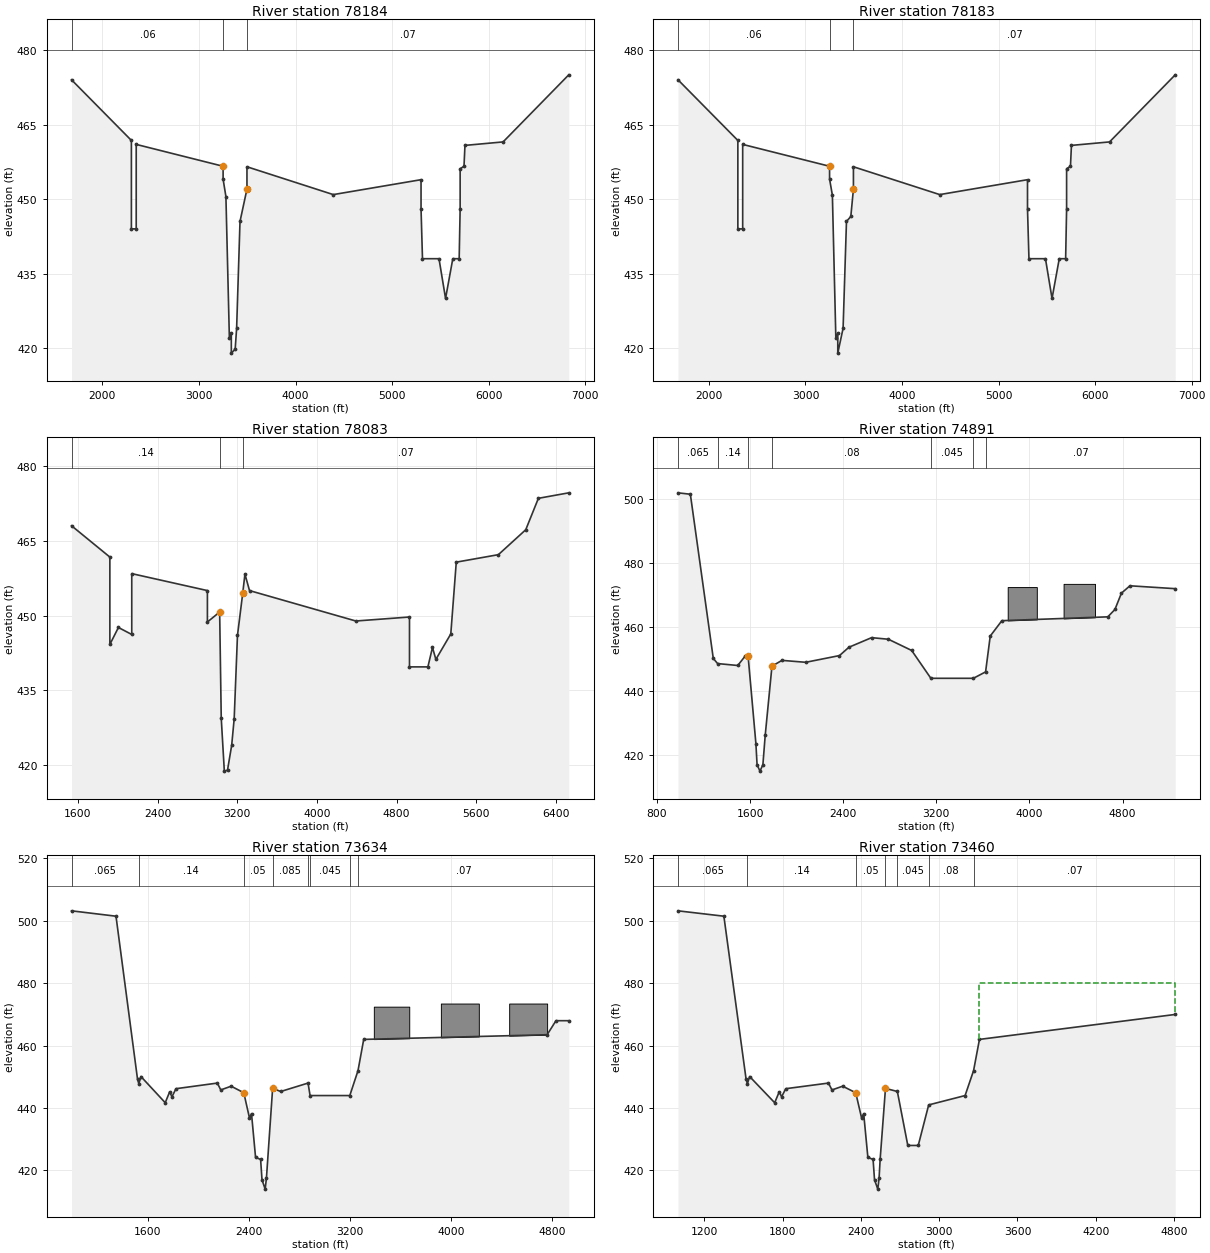
Type RM Length L Ch R = 1 ,78184   ,1,1,1
BEGIN DESCRIPTION:
This cross section corresponds to cross section 78184 of the non-georeferenced CDC model which was the source of this model.
Far LOB extended with 1991 topo.  Cont/Exp raised due to railroad.   High ground from d/s added to ROB.  'n' value raised in ROB  to be consistent.
END DESCRIPTION:
XS GIS Cut Line= 6
  2413895.712598 6982889.0162624 2413801.1278135 6982466.7277369
 2413745.0603403 6981997.1998046  2413357.303898 6980888.9047771
  2413283.658376 6980461.7806313 2413398.0075567 6977832.6179107
#Sta/Elev= 30
    1680     474    2300   461.8    2300     444    2350     444    2350     461
    3250   456.6    3250     454    3279   450.5    3315     422    3335     423
    3335     419    3375   419.8    3390     424    3425   445.5    3497     452
    3497   456.5    4391   450.9    5300   453.9    5300     448    5315     438
    5486     438    5554     430    5629     438    5695     438    5705     448
    5705   456.1    5745   456.6    5755   460.8    6150   461.5    6830     475
#Mann= 3 ,0,0
    1680     .06       0    3250     .05       0    3497     .07       0
Bank Sta=3250,3497
XS Rating Curve= 0 ,0
Exp/Cntr=0.5,0.3

Type RM Length L Ch R = 1 ,78183   ,100,100,100
BEGIN DESCRIPTION:
This cross section corresponds to cross section 78183 of the non-georeferenced CDC model which was the source of this model.
LOB 'n' value lowered to 0.06.  Far LOB extended with 1991 topo.  Cont/Exp raised due to railroad.   High ground from d/s added to ROB.
END DESCRIPTION:
XS GIS Cut Line= 6
    2413898.2267 6982891.6724251 2413803.3873234  6982470.609947
 2413746.8392082 6981998.9511134 2413358.9843408 6980890.2719003
 2413285.8043691 6980465.8268831 2413400.2562399 6977834.6457937
#Sta/Elev= 30
    1680     474    2300   461.8    2300     444    2350     444    2350     461
    3250   456.6    3250     454    3279   450.8    3315     422    3335     423
    3335     419    3390     424    3425   445.5    3470   446.5    3497     452
    3497   456.5    4391   450.9    5300   453.9    5300     448    5315     438
    5486     438    5554     430    5629     438    5695     438    5705     448
    5705   456.1    5745   456.6    5755   460.8    6150   461.5    6830     475
#Mann= 3 ,0,0
    1680     .06       0    3250     .05       0    3497     .07       0
Bank Sta=3250,3497
XS Rating Curve= 0 ,0
Exp/Cntr=0.5,0.3

Type RM Length L Ch R = 1 ,78083   ,1773,3234,942
BEGIN DESCRIPTION:
This cross section corresponds to cross section 78083 of the non-georeferenced CDC model which was the source of this model.
Flow limit due to railroad.  Railroad lowered 2' below rails.  Cont/Exp raised due to railroad.  'n' value lowered in ROB  to be consistent.
-------------------------------------------------------------------
CDC ARL071405-1 SVC Park Highlands, LTD.
In ROB beyond eff. flow line - storage mitigation area d/s SH 360 d/s cross-sect 78083.
------------------------------------------
END DESCRIPTION:
XS GIS Cut Line= 6
  2413968.174395 6982757.5342419 2413837.2038568 6981955.8740998
 2413672.5490024 6981421.6589609 2413449.3489895 6980847.1948867
 2413376.1690177 6980422.74986952413491.596804136977856.21586878
#Sta/Elev= 30
    1535     468    1920  461.72    1920   444.2    2006   447.6    2140   446.2
    2140   458.4    2900     455    2900   448.7    3023   450.7    3039   429.4
    3070   418.8    3102     419    3144     424    3169   429.3    3202     446
    3255   454.5    3277   458.3    3323     455    4391   448.9    4930   449.7
    4930   439.7    5115   439.7    5161   443.6    5195   441.2    5345   446.3
    5400   460.7    5823   462.2    6098   467.2    6225   473.5    6530   474.6
#Mann= 3 ,0,0
    1535     .14       0    3023     .05       0    3255     .07       0
Bank Sta=3023,3255
XS Rating Curve= 0 ,0
Exp/Cntr=0.5,0.3

Type RM Length L Ch R = 1 ,74891   ,869,1214,1352
BEGIN DESCRIPTION:
This cross section corresponds to cross section 74891 of the non-georeferenced CDC model which was the source of this model.
END DESCRIPTION:
XS GIS Cut Line= 6
  2415471.004723 6981381.1974277 2414978.3492123 6981131.3980585
 2414590.3768912 6980934.6858535 2414446.0609068 6979635.9505901
 2414301.7314711 6978337.2163109 2414228.4960533 6977670.7035363
#Sta/Elev= 30
 980.741501.94171086.999   501.51283.878450.2066    1321   448.6    1494     448
    1557   450.9    1583   450.9    1650   423.6    1660     417    1685     415
    1710     417    1730   426.2    1788   447.8    1874   449.6    2078     449
    2368   451.1    2449   453.7    2644   456.7    2788   456.2    2988   452.7
    3153     444    3518     444    3623     446    3663   457.2    3763     462
    4673   463.2    4734   465.5    4790   470.6    4863   472.9    5252     472
#Mann= 7 ,-1,0
 980.741    .065       0    1321     .14       0    1583    .055       0
    1788     .08       0    3153    .045       0    3518     .08       0
    3623     .07       0
#Block Obstruct= 2 ,-1
    3813    4063   472.5    4293    4563   473.5
Bank Sta=1583,1788
XS Rating Curve= 0 ,0
Exp/Cntr=0.3,0.1

Type RM Length L Ch R = 1 ,73634   ,332,332,332
BEGIN DESCRIPTION:
This cross section corresponds to cross section 73634 of the non-georeferenced CDC model which was the source of this model.
END DESCRIPTION:
XS GIS Cut Line= 6
  2415893.225007 6981445.9968387 2415683.3592852 6980825.8635646
 2415443.5021534 6980117.1418849 2414906.6088702 6979000.7527135
 2414617.4969157 6978399.6239945 2414347.8555254 6977839.0005659
#Sta/Elev= 30
  999.19503.22311350.739   501.51520.912 449.257    1531   447.8    1548   450.1
    1740   441.7    1775   445.2    1793   443.6    1825   446.2    2152     448
    2179   445.8    2261     447    2361   444.9    2406   436.8    2422   438.2
    2454   424.2    2494   423.5    2505     417    2530     414    2540   417.5
    2589   446.3    2653   445.3    2869     448    2885     444    3199     444
    3264     452    3309     462    4759   463.5    4829     468    4930     468
#Mann= 8 ,-1,0
  999.19    .065       0    1531     .14       0    2361     .05       0
    2589    .085       0    2869     .08       0    2885    .045       0
    3199     .08       0    3264     .07       0
#Block Obstruct= 3 ,-1
    3389    3669   472.5    3919    4219   473.5    4459    4759   473.5
Bank Sta=2361,2589
XS Rating Curve= 0 ,0
Exp/Cntr=0.3,0.1

Type RM Length L Ch R = 1 ,73460   ,735,735,735
BEGIN DESCRIPTION:
This cross section corresponds to cross section 73460 of the non-georeferenced CDC model which was the source of this model.
Copy of 73634
END DESCRIPTION:
XS GIS Cut Line= 6
  2416134.643815 6981463.9469341 2416109.5634853  6981371.966475
 2416083.0920816 6981274.3898985 2415706.7854195 6980139.3275361
 2415321.4941953 6979306.59068452414691.625355876977945.24383483
#Sta/Elev= 30
  999.19503.22311350.739   501.51520.912 449.257    1531   447.8    1548   450.1
    1740   441.7    1775   445.2    1793   443.6    1825   446.2    2152     448
    2179   445.8    2261     447    2361   444.9    2406   436.8    2422   438.2
    2454   424.2    2494   423.5    2505     417    2530     414    2540   417.5
    2548   423.5    2589   446.3    2680   445.3    2760     428    2840     428
    2920     441    3199     444    3264     452    3309     462    4809     470
#Mann= 7 ,-1,0
  999.19    .065       0    1531     .14       0    2361     .05       0
    2589    .085       0    2680    .045       0    2920     .08       0
    3264     .07       0
#XS Ineff= 2 , 0
                            3309             480
Permanent Ineff=
       F       F
Bank Sta=2361,2589
XS Rating Curve= 0 ,0
Exp/Cntr=0.3,0.1

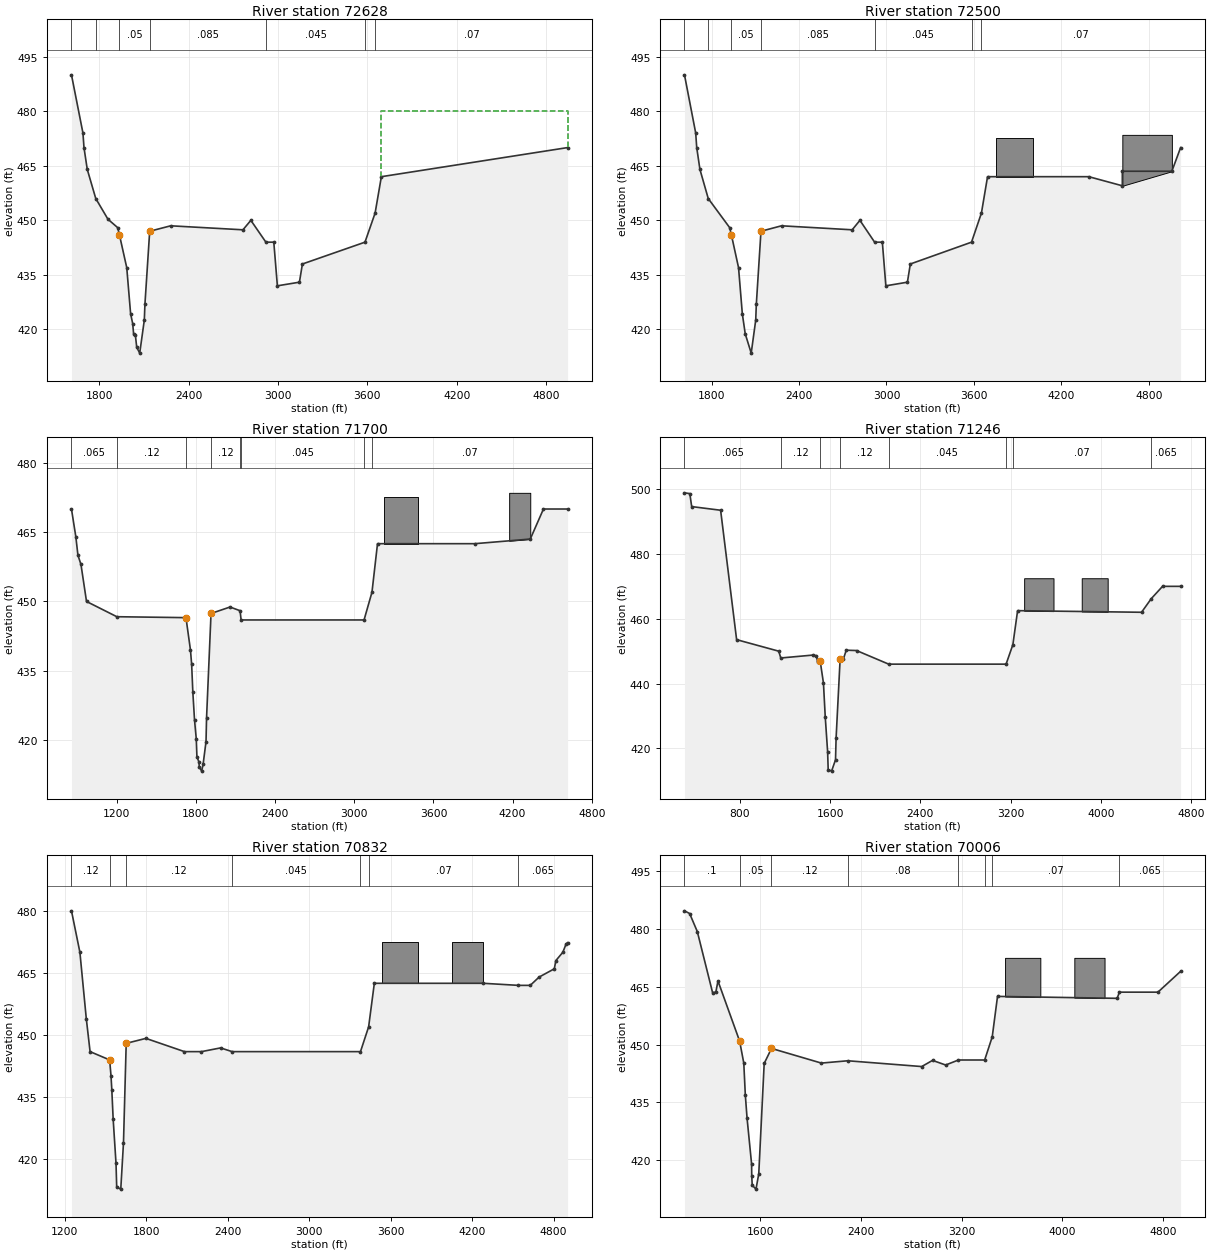
Type RM Length L Ch R = 1 ,72628   ,121,121,121
BEGIN DESCRIPTION:
This cross section corresponds to cross section 72628 of the non-georeferenced CDC model which was the source of this model.
Copy of 72500
END DESCRIPTION:
XS GIS Cut Line= 4
  2416411.804022 6980803.2500927 2416286.0418069 6980402.6304871
 2415316.5450583 6979051.08036872414587.956632566978035.37425674
#Sta/Elev= 30
    1614     490    1691     474    1698     470    1720     464    1777     456
    1859   450.3    1924     448    1936     446    1985     437    2011   424.3
    2025   421.6    2031   418.8    2043   418.4    2052   415.1    2072   413.5
    2103   422.6    2107   426.9    2139     447    2280   448.5    2765   447.4
    2818     450    2919     444    2972     444    2996     432    3144     433
    3164     438    3584     444    3652     452    3694     462    4944     470
#Mann= 7 ,-1,0
    1614    .065       0    1777     .12       0    1936     .05       0
    2139    .085       0    2919    .045       0    3584     .08       0
    3652     .07       0
#XS Ineff= 2 , 0
                            3694             480
Permanent Ineff=
       F       F
Bank Sta=1936,2139
XS Rating Curve= 0 ,0
Exp/Cntr=0.3,0.1

Type RM Length L Ch R = 1 ,72500   ,363,427,277
BEGIN DESCRIPTION:
This cross section corresponds to cross section 72500 of the non-georeferenced CDC model which was the source of this model.
END DESCRIPTION:
XS GIS Cut Line= 4
  2416513.265761 6980739.9887363 2416390.0452078 6980343.0594121
 2415317.8967616 6978842.4525052 2414656.4571396 6977906.9881687
#Sta/Elev= 30
    1614     490    1691     474    1698     470    1720     464    1777     456
    1924     448    1936     446    1985     437    2011   424.3    2031   418.8
    2072   413.5    2103   422.6    2107   426.9    2139     447    2280   448.5
    2765   447.4    2818     450    2919     444    2972     444    2996     432
    3144     433    3164     438    3584     444    3652     452    3694     462
    4389     462    4619   459.5    4619   463.5    4959   463.5    5019     470
#Mann= 7 ,-1,0
    1614    .065       0    1777     .12       0    1936     .05       0
    2139    .085       0    2919    .045       0    3584     .08       0
    3652     .07       0
#Block Obstruct= 2 ,-1
    3749    4009   472.5    4619    4959   473.5
Bank Sta=1936,2139
XS Rating Curve= 0 ,0
Exp/Cntr=0.3,0.1

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
Type RM Length L Ch R = 1 ,71700   ,301,403,284
BEGIN DESCRIPTION:
This cross section corresponds to cross section 71700 of the non-georeferenced CDC model which was the source of this model.
END DESCRIPTION:
XS GIS Cut Line= 4
  2417130.693476  6980475.338131 2417130.6934765  6980475.338131
 2416662.2543091 6979575.7860122 2414619.8986056 6977739.0447145
#Sta/Elev= 30
     856     470     889     464     905     460     928     458     970     450
    1200   446.7    1724   446.5    1758   439.5    1767   436.4    1776   430.4
    1789   424.3    1802   420.3    1807   416.4    1822   415.3    1825   414.2
    1843   413.3    1854   414.8    1876   419.7    1880   424.8    1914   447.4
    2058   448.8    2134     448    2142     446    3074     446    3134     452
    3176   462.5    3914   462.5    4334   463.5    4434     470    4617     470
#Mann= 8 ,-1,0
     856    .065       0    1200     .12       0    1724     .05       0
    1914     .12       0    2134     .08       0    2142    .045       0
    3074     .08       0    3134     .07       0
#Block Obstruct= 2 ,-1
    3224    3484   472.5    4174    4334   473.5
Bank Sta=1724,1914
XS Rating Curve= 0 ,0
Exp/Cntr=0.3,0.1

Type RM Length L Ch R = 1 ,71246   ,380,393,241
BEGIN DESCRIPTION:
This cross section corresponds to cross section 71246 of the non-georeferenced CDC model which was the source of this model.
---------------------------------------------------------------------
CDC FW020105-01 Riverpark Addition
Cross-section 71246 - 74891
Located in LOB.
---------------------------------------------------------------------
END DESCRIPTION:
XS GIS Cut Line= 3
     2417383.365     6980857.409     2417068.926     6979477.766
     2414657.399     6977727.086
#Sta/Elev= 30
 309.988498.8458357.3073   498.6 373.718   494.6630.1356493.4716771.8537453.5542
1144.922     450    1163   447.9    1449   448.8    1479   448.6    1489   446.7
    1512     447    1541   440.2    1557   429.7    1578     419    1583   413.5
    1613     413    1648   416.5    1653   423.1    1689   447.7    1717   447.5
    1743   450.3    1834   450.2    2119     446    3159     446    3219     452
    3261   462.5    4359     462    4445   466.2    4545     470    4705     470
#Mann= 8 ,-1,0
 309.988    .065       0    1163     .12       0    1512     .05       0
    1689     .12       0    2119    .045       0    3159     .08       0
    3219     .07       0    4445    .065       0
#Block Obstruct= 2 ,-1
    3319    3579   472.5    3829    4059   472.5
Bank Sta=1512,1689
XS Rating Curve= 0 ,0
Exp/Cntr=0.3,0.1

Type RM Length L Ch R = 1 ,70832   ,1077,847,406
BEGIN DESCRIPTION:
This cross section corresponds to cross section 70832 of the non-georeferenced CDC model which was the source of this model.
END DESCRIPTION:
XS GIS Cut Line= 3
  2417547.578325 6979894.0199558 2417460.8819769 6979419.8174921
 2414801.2832935 6977694.6723204
#Sta/Elev= 30
    1250     480    1312     470    1359     454    1387     446    1531     444
    1541   440.2    1547   436.8    1557   429.7    1578     419    1583   413.3
    1613   412.8    1633     424    1653     448    1798   449.2    2082     446
    2207     446    2348   446.9    2433     446    3378     446    3438     452
    3480   462.5    4283   462.5    4541     462    4628     462    4693     464
    4805     466    4817     468    4868     470    4892     472    4903   472.3
#Mann= 7 ,-1,0
    1250     .12       0    1531     .05       0    1653     .12       0
    2433    .045       0    3378     .08       0    3438     .07       0
    4541    .065       0
#Block Obstruct= 2 ,-1
    3533    3803   472.5    4053    4283   472.5
Bank Sta=1531,1653
XS Rating Curve= 0 ,0
Exp/Cntr=0.3,0.1

Type RM Length L Ch R = 1 ,70006   ,228,228,228
BEGIN DESCRIPTION:
This cross section corresponds to cross section 70006 of the non-georeferenced CDC model which was the source of this model.
END DESCRIPTION:
XS GIS Cut Line= 6
  2418494.785092 6979191.3750356  2417625.039457 6978837.3659011
 2417150.6247234 6978644.2800012 2416676.2044124 6978451.2009911
 2415806.4194066 6978097.24106912414857.488231366977711.10457569
#Sta/Elev= 30
    1000   484.7    1041     484    1102   479.3    1223   463.5    1249   463.6
    1266   466.5    1438   450.9    1471   445.2    1483     437    1497   430.9
    1533     419    1534     416    1538   413.5    1568   412.5    1590   416.5
    1633   445.1    1691     449    2087   445.2    2297   445.8    2884   444.3
    2970   445.9    3074   444.7    3176     446    3384     446    3444     452
    3486   462.5    4436     462    4454   463.6    4760   463.6    4940     469
#Mann= 8 ,-1,0
    1000      .1       0    1438     .05       0    1691     .12       0
    2297     .08       0    3176    .045       0    3384     .08       0
    3444     .07       0    4454    .065       0
#Block Obstruct= 2 ,-1
    3546    3826   472.5    4096    4336   472.5
Bank Sta=1438,1691
XS Rating Curve= 0 ,0
Exp/Cntr=0.3,0.1

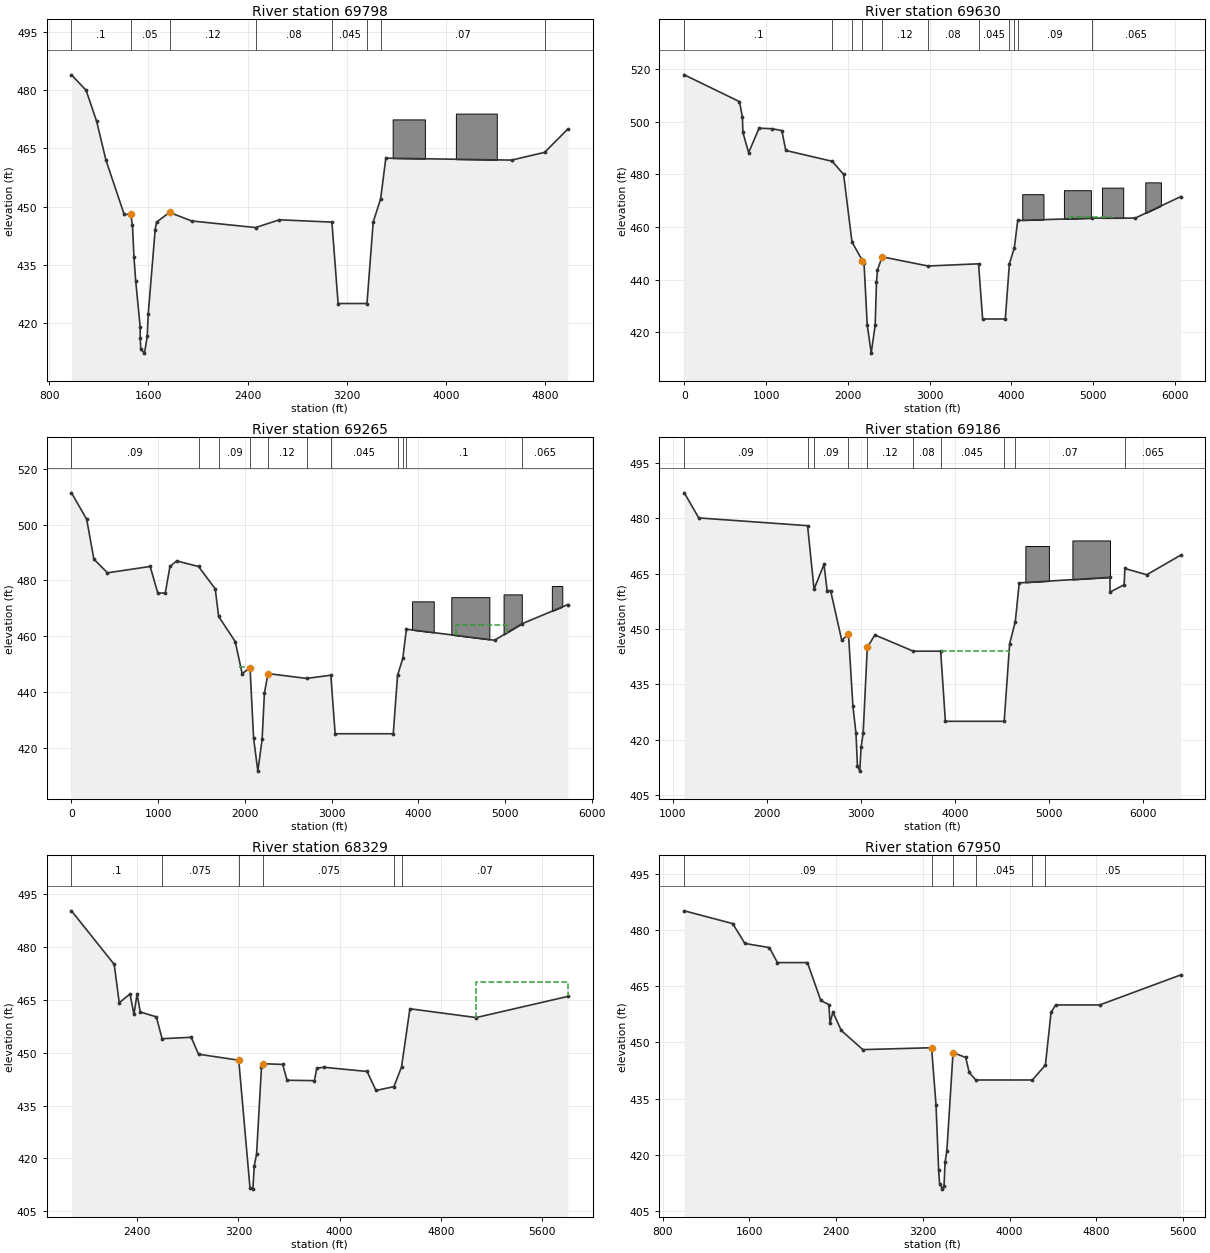
Type RM Length L Ch R = 1 ,69798   ,166,168,109
BEGIN DESCRIPTION:
69798
END DESCRIPTION:
XS GIS Cut Line= 2
  2418583.8709296978996.755135862414833.43700001     6977612.207
#Sta/Elev= 30
     979     484    1097     480    1182     472    1257     462    1404     448
    1457     448    1471   445.2    1483     437    1497   430.9    1533     419
    1534     416    1538   413.2    1568   412.2    1590   416.5    1598   422.2
    1654     444    1665     446    1770   448.5    1948   446.3    2464   444.6
    2657   446.6    3080     446    3130     425    3363     425    3413     446
    3473     452    3515   462.5    4530     462    4796     464    4983     470
#Mann= 8 ,-1,0
     979      .1       0    1457     .05       0    1770     .12       0
    2464     .08       0    3080    .045       0    3363     .08       0
    3473     .07       0    4796    .065       0
#XS Ineff= 1 ,-1
    3080    3413     446
Permanent Ineff=
       T
#Block Obstruct= 2 ,-1
    3570    3830   472.5    4080    4410     474
Bank Sta=1457,1770
XS Rating Curve= 0 ,0
Exp/Cntr=0.3,0.1

Type RM Length L Ch R = 1 ,69630   ,425,365,210
BEGIN DESCRIPTION:
69630
2009 LiDAR - LOB Includes Pettigrew Fill
END DESCRIPTION:
XS GIS Cut Line= 5
  2420181.3521216979505.819805952418915.727122046979014.50036153
2418125.796566436978642.972583742417472.071161366978461.55258952
2414474.024286366977440.01034415
#Sta/Elev= 30
       0  517.92  675.07  507.72  711.01  501.76  716.97  496.01  786.99  488.32
  915.19  497.62 1077.64   497.4 1193.47  496.71 1241.54  489.14 1810.87     485
 1948.99     480 2051.75  454.31 2179.17  447.24 2198.94  446.23 2237.89   422.9
    2287  412.01 2335.36  422.68  2351.1  438.91 2363.59  443.69 2421.06  448.66
  2981.7  445.17    3600     446    3650     425 3927.34     425 3977.34     446
 4037.34     452 4079.34   462.5 4986.41  463.37 5517.64  463.41    6072  471.55
#Mann= 11 ,-1,0
       0      .1       0 1810.87     .07       0 2051.75      .1       0
 2179.17     .05       0 2421.06     .12       0  2981.7     .08       0
    3600    .045       0 3977.34     .08       0 4037.34     .07       0
 4079.34     .09       0 4986.41    .065       0
#XS Ineff= 2 ,-1
    3600 3977.34     446 4715.94 5235.39  463.64
Permanent Ineff=
       T       F
#Block Obstruct= 4 ,-1
 4134.34 4394.34   472.5 4644.34 4974.34     474    5110    5370     475
    5640    5831     477
Bank Sta=2179.17,2421.06
XS Rating Curve= 0 ,0
Exp/Cntr=0.3,0.1

Type RM Length L Ch R = 1 ,69265   ,78,79,80
BEGIN DESCRIPTION:
69265
2009 LiDAR - LOB Includes Pettigrew Fill
END DESCRIPTION:
XS GIS Cut Line= 5
  2420106.5098186978947.835141612419193.749402116978615.80389161
2418559.634818736978265.543474962417505.815374346978243.69741014
2414644.270000046977443.35000001
#Sta/Elev= 30
       0  511.43  175.08  501.97  258.55  487.63   415.5  482.73  907.77  485.02
  996.08  475.43 1082.03  475.51    1136     485    1214     487 1465.46     485
 1658.23     477 1697.95  467.07 1889.67  458.03 1969.17  446.55 2060.18  448.66
    2101  423.46    2150  411.59 2199.25  422.95 2225.88  439.59 2267.44  446.58
 2712.06  444.85 2992.02     446 3042.02     425 3712.25     425 3762.25     446
 3822.25     452 3864.25   462.5 4880.77  458.55 5192.84  464.39    5726  471.34
#Mann= 11 ,-1,0
       0     .09       0 1465.46     .07       0 1697.95     .09       0
 2060.18     .05       0 2267.44     .12       0 2712.06     .08       0
 2992.02    .045       0 3762.25     .08       0 3822.25     .07       0
 3864.25      .1       0 5192.84    .065       0
#XS Ineff= 4 ,-1
  164.38    1214     487  1934.3 2055.48     449 2992.02 3762.25     446
 4437.25 5027.87  463.98
Permanent Ineff=
       F       F       T       F
#Block Obstruct= 4 ,-1
 3929.25 4179.25   472.5    4382    4821     474    4985    5195     475
  5541.8  5662.6     478
Bank Sta=2060.18,2267.44
XS Rating Curve= 0 ,0
Exp/Cntr=0.3,0.1

Type RM Length L Ch R = 1 ,69186   ,850,857,800
BEGIN DESCRIPTION:
69186
---------------------------------------------------------------------
LOMR#17-06-0659P & CDC FW050115-01 Pettigrew Development
Cross-sections 69186 - 69630
---------------------------------------------------------------------
LOB includes Pettigrew Fill.
END DESCRIPTION:
XS GIS Cut Line= 6
  2419943.983309 6978221.9225782  2418749.186815 6978194.4262421
 2417568.4959349 6978167.2980156 2416327.9416575 6977848.2471445
  2414910.690555 6977483.8148025 2414762.2476104 6977434.2709383
#Sta/Elev= 30
    1121   486.9    1275   480.1 2431.28     478    2500  460.82    2606   467.5
    2639   460.4    2676   460.4    2795   446.9    2866   448.7    2913   429.2
    2946   421.7    2961     413    2986   411.5    3000     418    3022   421.7
    3066     445    3146   448.4    3555     444    3846     444    3896     425
    4521     425    4579     446    4639     452    4681   462.5    5646     464
    5646     460    5796     462    5804   466.4    6036   464.7    6396     470
#Mann= 10 ,-1,0
    1121     .09       0 2431.28     .07       0    2500     .09       0
    2866     .05       0    3066     .12       0    3555     .08       0
    3846    .045       0    4521     .08       0    4639     .07       0
    5804    .065       0
#XS Ineff= 1 ,-1
    3846    4571     444
Permanent Ineff=
       T
#Block Obstruct= 2 ,-1
    4746    4996   472.5    5246    5646     474
Bank Sta=2866,3066
XS Rating Curve= 0 ,0
Exp/Cntr=0.3,0.1

Type RM Length L Ch R = 1 ,68329   ,339,364,334
BEGIN DESCRIPTION:
This cross section corresponds to cross section 68329 of the non-georeferenced CDC model which was the source of this model.
END DESCRIPTION:
XS GIS Cut Line= 6
  2419464.020533 6977349.6039763 2418555.6301155 6977339.7366786
 2417968.6099641 6977333.3741585 2417465.4498812 6977327.9289594
 2416631.7796325 6977121.72530362415594.513645666976865.18881984
#Sta/Elev= 30
    1879   490.3    2217   475.1    2257   464.2    2342   466.7    2373   460.9
    2398   466.7    2423   461.6    2550   460.2    2596     454    2826   454.4
    2884   449.6    3202   447.9    3291   411.7    3314   411.3    3325     418
    3343   421.2    3382   445.9    3395   446.9    3550   446.7    3584   442.2
    3801   442.1    3819   445.6    3873   445.9    4217   444.7    4288   439.3
    4430   440.4    4490     446    4556   462.5    5080     460    5805     466
#Mann= 6 ,-1,0
    1879      .1       0    2596    .075       0    3202     .05       0
    3395    .075       0    4430     .08       0    4490     .07       0
#XS Ineff= 2 , 0
                            5080             470
Permanent Ineff=
       F       F
Bank Sta=3202,3395
XS Rating Curve= 0 ,0
Exp/Cntr=0.3,0.1

Type RM Length L Ch R = 1 ,67950   ,454,423,449
BEGIN DESCRIPTION:
This cross section corresponds to cross section 67950 of the non-georeferenced CDC model which was the source of this model.
END DESCRIPTION:
XS GIS Cut Line= 3
  2420433.972159 6976976.2410145 2417508.6249917 6976976.2410145
 2415928.2474444 6976492.8486351
#Sta/Elev= 30
    1000   485.1    1446   481.7    1559   476.4    1785   475.3    1859   471.3
    2136   471.3    2259   461.2    2334   460.1    2344   455.2    2371   458.1
    2448   453.2    2647   448.1    3281   448.6    3322   433.3    3346   416.1
    3355   412.4    3380   410.9    3396   411.7    3405     418    3422   421.1
    3479   447.3    3596     446    3628     442    3689     440    4211     440
    4331     444    4383     458    4425     460    4831     460    5578     468
#Mann= 6 ,-1,0
    1000     .09       0    3281    .055       0    3479     .07       0
    3689    .045       0    4211     .07       0    4331     .05       0
Bank Sta=3281,3479
XS Rating Curve= 0 ,0
Exp/Cntr=0.3,0.1

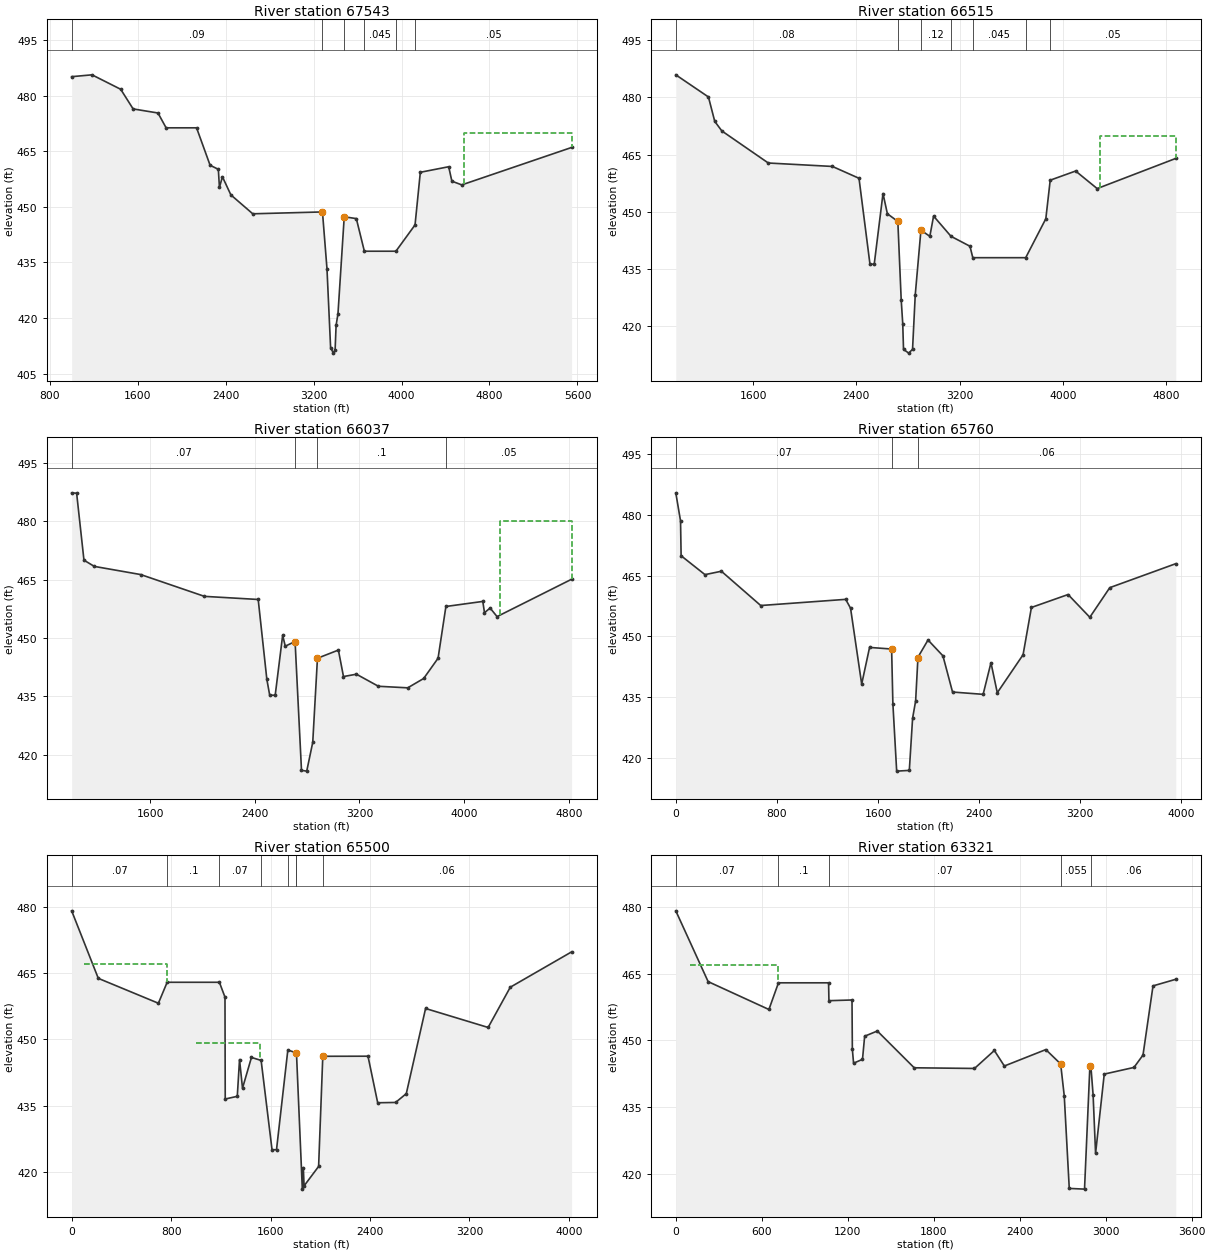
Type RM Length L Ch R = 1 ,67543   ,522,1031,853
BEGIN DESCRIPTION:
This cross section corresponds to cross section 67543 of the non-georeferenced CDC model which was the source of this model.
END DESCRIPTION:
XS GIS Cut Line= 6
    2420337.2381 6976797.2948501 2419597.4981105 6976691.3432903
 2418775.5591376 6976573.6391294 2417937.7222306 6976554.0158091
 2417267.4519176 6976538.33309772415872.391759036976105.24664666
#Sta/Elev= 30
    1000   485.1    1185   485.6    1446   481.7    1559   476.4    1785   475.3
    1859   471.3    2136   471.3    2259   461.2    2334   460.1    2344   455.2
    2371   458.1    2448   453.2    2647   448.1    3281   448.6    3322   433.3
    3355     412    3380   410.5    3396   411.3    3405     418    3422   421.1
    3479   447.3    3589   446.8    3662     438    3949     438    4123   445.1
    4171   459.3    4429   460.8    4458   456.9    4548   455.9    5547     466
#Mann= 6 ,-1,0
    1000     .09       0    3281    .055       0    3479     .07       0
    3662    .045       0    3949     .07       0    4123     .05       0
#XS Ineff= 2 , 0
                            4567             470
Permanent Ineff=
       F       F
Bank Sta=3281,3479
XS Rating Curve= 0 ,0
Exp/Cntr=0.3,0.1

Type RM Length L Ch R = 1 ,66515   ,526,474,298
BEGIN DESCRIPTION:
This cross section corresponds to cross section 66515 of the non-georeferenced CDC model which was the source of this model.
END DESCRIPTION:
XS GIS Cut Line= 6
  2420357.846983 6976412.1230482 2419529.0172763 6976198.6093677
 2418948.8301165 6976049.1624881 2418534.4073889 6975942.4212317
 2417705.5540597 6975728.95446712416605.313413346975445.62587406
#Sta/Elev= 30
    1000   485.9    1253   480.1    1302   473.7    1357   471.2    1717   462.8
    2214   461.9    2420   458.8    2505   436.3    2538   436.3    2606   454.8
    2640   449.5    2721   447.5    2747     427    2759   420.7    2765     414
    2805     413    2835     414    2856   428.3    2900   445.2    2969   443.6
    2998   448.9    3133   443.6    3280     441    3302     438    3712     438
    3868   448.2    3902   458.3    4099   460.7    4266   456.1    4875     464
#Mann= 7 ,-1,0
    1000     .08       0    2721     .05       0    2900     .12       0
    3133     .07       0    3302    .045       0    3712     .07       0
    3902     .05       0
#XS Ineff= 2 , 0
                            4285             470
Permanent Ineff=
       F       F
#Block Obstruct= 2 , 0
            2606   454.8
Bank Sta=2721,2900
XS Rating Curve= 0 ,0
Exp/Cntr=0.3,0.1

Type RM Length L Ch R = 1 ,66037   ,265,272,243
XS GIS Cut Line= 6
  2420373.650101 6976046.3809976 2419819.9149885 6975786.3592079
 2419266.1710172 6975526.3469327 2418596.2547062 6975495.1635961
 2417926.3370827  6975463.9940392416670.475325896975405.59604374
#Sta/Elev= 30
    1000   487.3    1038   487.2    1094     470    1173   468.4    1528   466.3
    2015   460.7    2426   459.9    2492   439.4    2514   435.3    2556   435.3
    2613   450.7    2633   447.9    2708   449.1    2757     416    2797   415.8
    2843   423.2    2879   444.8    3039   446.9    3078   440.1    3177   440.7
    3345   437.6    3569   437.2    3691   439.6    3801   444.8    3861   458.1
    4143   459.4    4156   456.5    4199   457.7    4252   455.5    4822   465.1
#Mann= 4 ,-1,0
    1000     .07       0    2708    .055       0    2879      .1       0
    3861     .05       0
#XS Ineff= 3 ,-1
    2426    2708   449.1    2879    4271   444.8    4271    4822     480
Permanent Ineff=
       T       F       F
Bank Sta=2708,2879
XS Rating Curve= 0 ,0
Exp/Cntr=0.3,0.1

Type RM Length L Ch R = 1 ,65760   ,302,260.4,218
XS GIS Cut Line= 4
      2420340.23     6975965.957     2418991.532     6975231.001
      2416572.87     6975218.711      2416572.87     6975218.711
#Sta/Elev= 30
       0  485.41   37.53  478.47   42.08  469.88  231.01  465.22  360.65  466.06
   671.9   457.6  1344.1  459.12 1382.65  456.93 1470.61  438.21 1533.03  447.26
 1707.45  446.86 1717.45  433.38 1747.45  416.73 1847.45  416.91 1873.45  429.79
 1897.45  434.05 1915.45   444.6 1917.45  444.93 1995.45  449.09 2113.45  445.18
 2189.46  436.25 2431.46  435.68 2493.46  443.48 2543.46  436.07 2747.46  445.45
 2813.46  457.12 3103.47  460.31 3275.47   454.7 3433.47  462.01 3955.31  467.92
#Mann= 3 ,-1,0
       0     .07       0 1707.45    .055       0 1917.45     .06       0
Bank Sta=1707.45,1915.45
XS Rating Curve= 0 ,0
Exp/Cntr=0.3,0.1

Type RM Length L Ch R = 1 ,65500   ,511.3,2179,1785
BEGIN DESCRIPTION:
LOB updated using 2016 LIDAR
END DESCRIPTION:
XS GIS Cut Line= 5
2421045.677612326976319.19124747  2420232.389229 6975737.3304346
 2419637.9261792 6975312.0264951  2419136.229348 6974953.6715688
2417464.841823746975019.11162293
#Sta/Elev= 30
       0  479.13  214.32  463.83  697.85  458.19  768.29  462.94 1188.67  462.94
 1233.67  459.57 1235.67  436.49 1332.67   437.1 1350.67  445.43 1374.67  438.94
 1446.67  445.91  1524.5  445.23 1612.25     425 1648.27     425 1739.41  447.59
  1807.9  446.94 1808.91  446.88 1855.94  416.07 1863.95  420.95 1869.95   416.8
 1987.04  421.21 2020.71  446.17 2384.34  446.19 2462.41  435.64 2606.52  435.71
 2692.58  437.71  2847.7     457 3351.09   452.7 3529.22  461.82  4022.8  469.83
#Mann= 8 ,-1,0
       0     .07       0  768.29      .1       0 1188.67     .07       0
  1524.5    .045       0 1739.41     .07       0  1807.9     .07       0
 1808.91    .055       0 2020.71     .06       0
#XS Ineff= 4 ,-1
     100  768.29   467.1    1000    1515   449.1    1515    1800   444.5
 2020.34    3500   444.8
Permanent Ineff=
       F       F       T       F
Bank Sta=1808.91,2020.71
XS Rating Curve= 0 ,0
Exp/Cntr=0.3,0.1

Type RM Length L Ch R = 1 ,63321   ,559,1845.5,1805
XS GIS Cut Line= 5
     2420303.952      6975732.37     2419920.675     6975324.966
     2419474.108     6974671.059     2417945.272     6973176.737
     2417945.272     6973176.737
#Sta/Elev= 30
       0  479.13  225.58  463.21  649.89  456.94  716.47  462.94  1066.3  462.94
 1068.72  458.92 1229.72  459.08 1232.14  448.02 1240.61  444.86  1302.9  445.73
 1318.01  450.93 1406.42   452.1 1663.72  443.83 2084.56  443.68 2223.15  447.72
  2292.9  444.23 2582.33  447.92  2685.8   444.7 2710.97   437.5 2745.92   416.7
 2852.43  416.54 2889.88  444.23 2896.98  444.09 2912.31  437.73 2929.51  424.59
 2990.03  442.41 3197.52  443.91 3260.48  446.69 3330.39  462.25 3489.03  463.73
#Mann= 5 ,-1,0
       0     .07       0  716.47      .1       0  1066.3     .07       0
  2685.8    .055       0 2896.98     .06       0
#XS Ineff= 1 ,-1
     100 716.469     467
Permanent Ineff=
       F
Bank Sta=2685.8,2889.88
XS Rating Curve= 0 ,0
Exp/Cntr=0.3,0.1