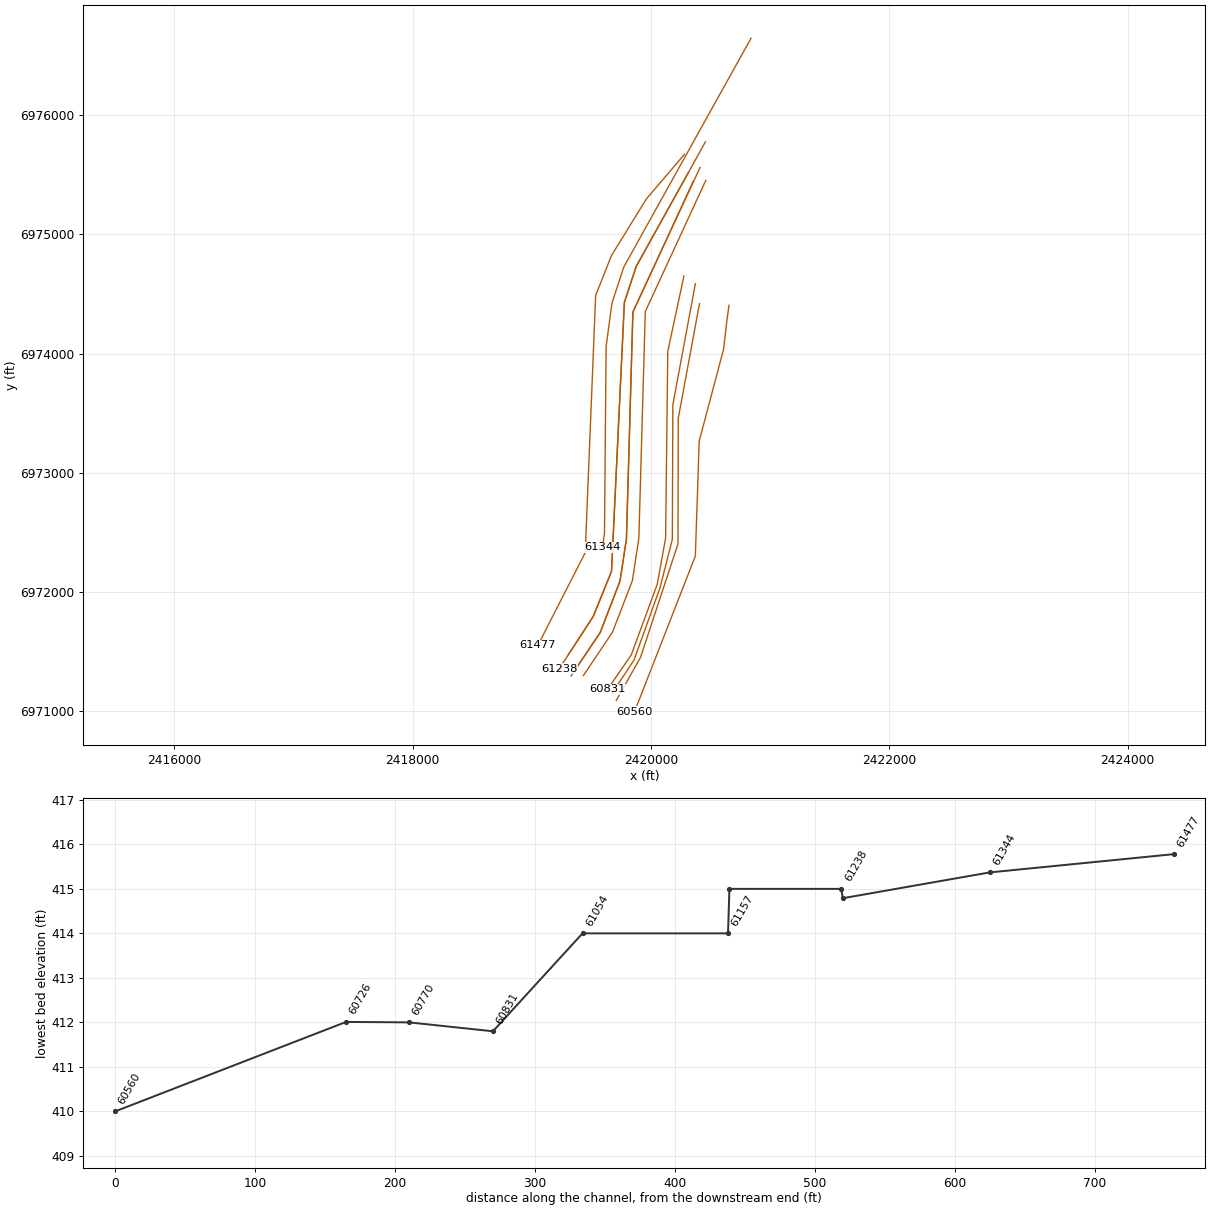
HEC-RAS study CDC_Consolidated_Model.prj: Upper Trinity CDC Consolidated Model

--- CDC_Consolidated_Model.g13 (geometry) --- (continued)

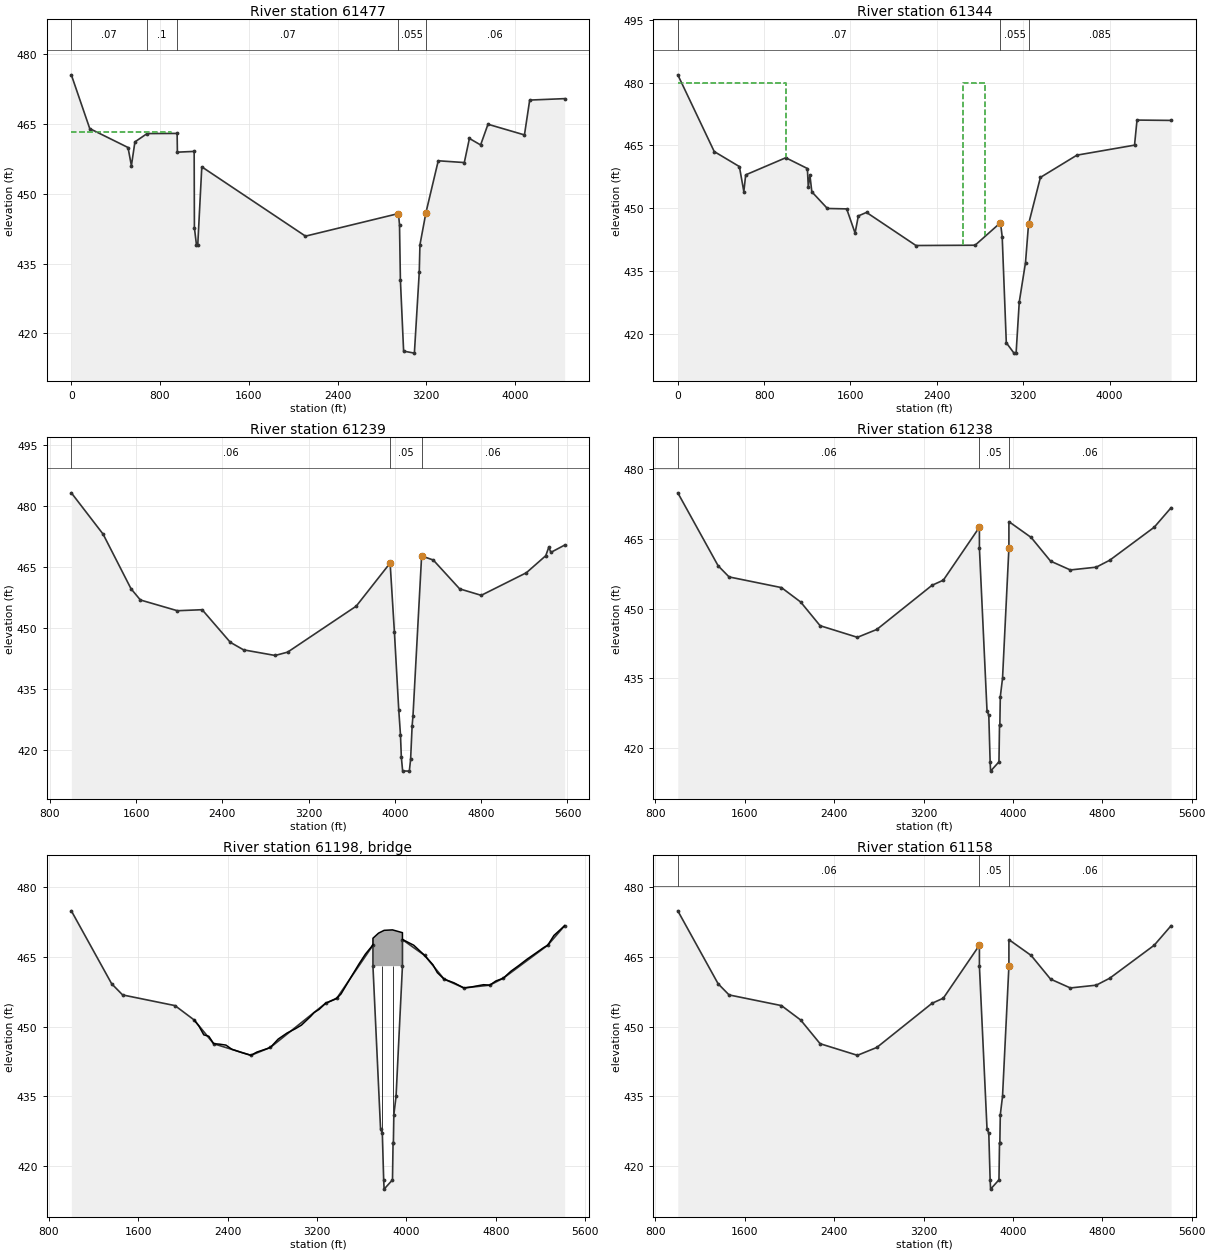
Type RM Length L Ch R = 1 ,61477   ,255,131.5,359
XS GIS Cut Line= 6
     2420281.179      6975672.93     2419961.206     6975297.601
     2419668.601     6974822.975     2419535.963     6974488.464
     2419448.391     6972329.063     2419050.487     6971550.205
#Sta/Elev= 30
       0  475.52  166.08  463.98  511.09  459.92  541.64  456.01  573.35  461.12
  682.97  462.91  953.94  462.94  956.29  458.92 1107.55  459.08  1109.7   442.7
 1128.57  438.94 1139.79  438.94 1176.33  455.77 2111.34  440.89 2949.23  445.74
 2959.03  443.34 2967.04  431.48 2996.06  416.21 3093.15  415.78  3137.2  433.18
  3143.2  439.02 3197.46  445.95 3308.35  457.07 3543.25  456.69  3589.3  461.86
 3690.36  460.47 3756.75  464.91 4085.61  462.62 4132.84   470.1 4447.94  470.41
#Mann= 5 ,-1,0
       0     .07       0  682.97      .1       0  953.94     .07       0
 2949.23    .055       0 3197.46     .06       0
#XS Ineff= 2 , 0
          899.26  463.35
Permanent Ineff=
       F       F
Bank Sta=2949.23,3197.46
XS Rating Curve= 0 ,0
Exp/Cntr=0.3,0.1

Type RM Length L Ch R = 1 ,61344   ,105,105,105
BEGIN DESCRIPTION:
sta 0 to 2232 updated based on LIDAR
END DESCRIPTION:
XS GIS Cut Line= 6
2420839.714722836976647.07913802     2419772.294     6974727.113
     2419673.129     6974425.111     2419623.547     6974060.004
     2419610.024     6972491.3952419593.645665196972373.46640566
#Sta/Elev= 30
       0  481.86   337.6  463.53  570.68  459.94  611.87  453.96  629.03  457.96
 1000.65  462.05 1200.76  459.48 1209.18  455.02 1223.91  457.94 1241.83  453.91
    1386  449.93 1564.87  449.83 1642.58  444.06 1672.85  448.15 1748.54  448.99
 2206.72  441.08 2754.79  441.15  2989.8  446.53  3005.8  443.17  3043.8  417.86
 3114.81  415.37 3134.81  415.46 3163.81  427.58 3221.81  437.02 3249.81  446.18
 3359.82  457.35 3698.16  462.67 4231.96  465.06 4254.94  471.05 4570.79  470.97
#Mann= 3 ,0,0
       0     .07       0  2989.8    .055       0 3249.81    .085       0
#XS Ineff= 3 ,-1
       0    1000     480    1000    2640     441    2640    2850     480
Permanent Ineff=
       T       F       T
Bank Sta=2989.8,3249.81
XS Rating Curve= 0 ,0
Exp/Cntr=0.3,0.1

Type RM Length L Ch R = 1 ,61239   ,1,1,1
BEGIN DESCRIPTION:
Cross-section recut part of:
CDC GP092922-1 Roy Orr LGD Holdings Industrial Development
Cross-sections 61239 - 65760
Project located in LOB.
END DESCRIPTION:
XS GIS Cut Line= 6
     2420457.214     6975777.636     2419875.645     6974731.711
     2419776.479     6974429.709       2419668.3     6972171.453
     2419515.046     6971792.824     2419305.893     6971471.801
#Sta/Elev= 30
    1000  483.15 1294.56     473 1553.54  459.58 1640.11  456.83 1983.14  454.19
    2213  454.44 2474.02  446.43 2596.88  444.58  2889.5   443.2  3005.5  444.02
 3641.53  455.32 3955.54   465.9 3995.54  448.85 4035.54  429.86 4051.54  423.71
 4059.54  418.25 4071.54  414.84 4133.54  414.79 4145.55  417.67 4159.59  425.94
 4167.55  428.36 4247.55  467.64 4355.55  466.65 4600.25  459.56 4800.25  457.97
 5218.83  463.52 5398.36   467.7 5426.96  469.81 5446.06  468.52 5573.56  470.31
#Mann= 3 ,0,0
    1000     .06       0 3955.54     .05       0 4247.55     .06       0
Bank Sta=3955.54,4247.55
XS Rating Curve= 0 ,0
Exp/Cntr=0.5,0.3

Type RM Length L Ch R = 1 ,61238   ,80,80,80
BEGIN DESCRIPTION:
This cross section corresponds to cross section 61238 of the non-georeferenced CDC model which was the source of this model.
END DESCRIPTION:
XS GIS Cut Line= 6
     2420314.954     6975521.336     2419876.525     6974731.399
     2419777.477     6974429.754     2419669.298     6972171.498
     2419516.044     6971792.868     2419231.253     6971355.756
#Sta/Elev= 30
    1000   474.9    1361   459.2    1459   456.8    1928   454.5    2100   451.4
    2274   446.3    2608   443.8    2782   445.5    3276     455    3377   456.1
    3700   467.5    3700     463    3768     428    3784     427    3796     417
    3800     415    3875     417    3880     425    3883     425    3887     431
    3907     435    3964     463    3964   468.7    4163   465.3    4337   460.2
    4514   458.3    4746   458.9    4867   460.4    5265   467.5    5416   471.7
#Mann= 3 ,0,0
    1000     .06       0    3700     .05       0    3964     .06       0
Bank Sta=3700,3964
XS Rating Curve= 0 ,0
Exp/Cntr=0.3,0.1

Type RM Length L Ch R = 3 ,61198   ,,,
BEGIN DESCRIPTION:
Roy Orr Boulevard/N.W. 19th Street
END DESCRIPTION:
Node Name=NW 19th Street
Bridge Culvert--1,0,-1,-1, 0
Deck Dist Width WeirC Skew NumUp NumDn MinLoCord MaxHiCord MaxSubmerge Is_Ogee
1,78,2.6,0, 57, 57, , , 0.95, 0, ,,,
    2100    2142    2186    2231    2274    2328    2384    2437    2524    2608
    2661    2749    2782    2852    2931    3004    3060    3143    3173    3219
    3276    3354    3377    3414    3503    3576    3633    3698    3700    3700
    3750    3800    3875    3964    3964    3967    4065    4163    4237    4276
    4337    4426    4514    4578    4645    4690    4746    4800    4867    4935
    5004    5080    5158    5229    5265    5320    5416
   451.4   450.1   448.2   447.9   446.3   446.2     446   445.1   444.4   443.8
   444.5   445.2   445.5   447.3   448.6   449.5   450.3   452.2     453   453.7
     455   455.8   456.1     457   460.6   463.5   465.6   467.5   467.5     469
   470.1   470.7   470.8   470.2   468.7   468.7   467.5   465.3   463.3   461.6
   460.2   459.4   458.3   458.5   458.8     459   458.9   459.8   460.4   461.9
   463.1   464.5   465.8     467   467.5   469.6   471.7
   451.4   450.1   448.2   447.9   446.3   446.2     446   445.1   444.4   443.8
   444.5   445.2   445.5   447.3   448.6   449.5   450.3   452.2     453   453.7
     455   455.8   456.1     457   460.6   463.5   465.6   467.5   467.5     463
     463     463     463     463   468.7   468.7   467.5   465.3   463.3   461.6
   460.2   459.4   458.3   458.5   458.8     459   458.9   459.8   460.4   461.9
   463.1   464.5   465.8     467   467.5   469.6   471.7
    2100    2142    2186    2231    2274    2328    2384    2437    2524    2608
    2661    2749    2782    2852    2931    3004    3060    3143    3173    3219
    3276    3354    3377    3414    3503    3576    3633    3698    3700    3700
    3750    3800    3875    3964    3964    3967    4065    4163    4237    4276
    4337    4426    4514    4578    4645    4690    4746    4800    4867    4935
    5004    5080    5158    5229    5265    5320    5416
   451.4   450.1   448.2   447.9   446.3   446.2     446   445.1   444.4   443.8
   444.5   445.2   445.5   447.3   448.6   449.5   450.3   452.2     453   453.7
     455   455.8   456.1     457   460.6   463.5   465.6   467.5   467.5     469
   470.1   470.7   470.8   470.2   468.7   468.7   467.5   465.3   463.3   461.6
   460.2   459.4   458.3   458.5   458.8     459   458.9   459.8   460.4   461.9
   463.1   464.5   465.8     467   467.5   469.6   471.7
   451.4   450.1   448.2   447.9   446.3   446.2     446   445.1   444.4   443.8
   444.5   445.2   445.5   447.3   448.6   449.5   450.3   452.2     453   453.7
     455   455.8   456.1     457   460.6   463.5   465.6   467.5   467.5     463
     463     463     463     463   468.7   468.7   467.5   465.3   463.3   461.6
   460.2   459.4   458.3   458.5   458.8     459   458.9   459.8   460.4   461.9
   463.1   464.5   465.8     467   467.5   469.6   471.7
Pier Skew, UpSta & Num, DnSta & Num=  ,3782.5, 2 ,3782.5, 2 , 0 , 0 , 0 ,,
       3       3
     400     464
       3       3
     400     464
Pier Skew, UpSta & Num, DnSta & Num=  ,3881.5, 2 ,3881.5, 2 , 0 , 0 , 0 ,,
       3       3
     400     464
       3       3
     400     464
BR Coef= 1 , 0 , 0 ,1.05, 0 ,,,0.8,-1,0.5,1,
WSPro=,,,, 1 ,,,, 0 ,,,, 0 ,,,,-1 ,-1 ,-1 , 0 , 0 , 0 , 0 , 0
BC Design=,, 0 ,, 0 ,,,,,,
BC HTab HWMax=471.7
BC Use User HTab Curves=0
BC User HTab FreeFlow(D)= 0

Type RM Length L Ch R = 1 ,61158   ,1,1,1
BEGIN DESCRIPTION:
This cross section corresponds to cross section 61158 of the non-georeferenced CDC model which was the source of this model.
END DESCRIPTION:
XS GIS Cut Line= 6
     2420411.952     6975562.168     2419847.886     6974348.333
     2419793.796     6972446.168     2419739.706     6972090.077
     2419573.081     6971657.752     2419379.336     6971369.819
#Sta/Elev= 30
    1000   474.9    1361   459.2    1459   456.8    1928   454.5    2100   451.4
    2274   446.3    2608   443.8    2782   445.5    3276     455    3377   456.1
    3700   467.5    3700     463    3768     428    3784     427    3796     417
    3800     415    3875     417    3880     425    3883     425    3887     431
    3907     435    3964     463    3964   468.7    4163   465.3    4337   460.2
    4514   458.3    4746   458.9    4867   460.4    5265   467.5    5416   471.7
#Mann= 3 ,0,0
    1000     .06       0    3700     .05       0    3964     .06       0
Bank Sta=3700,3964
XS Rating Curve= 0 ,0
Exp/Cntr=0.3,0.1

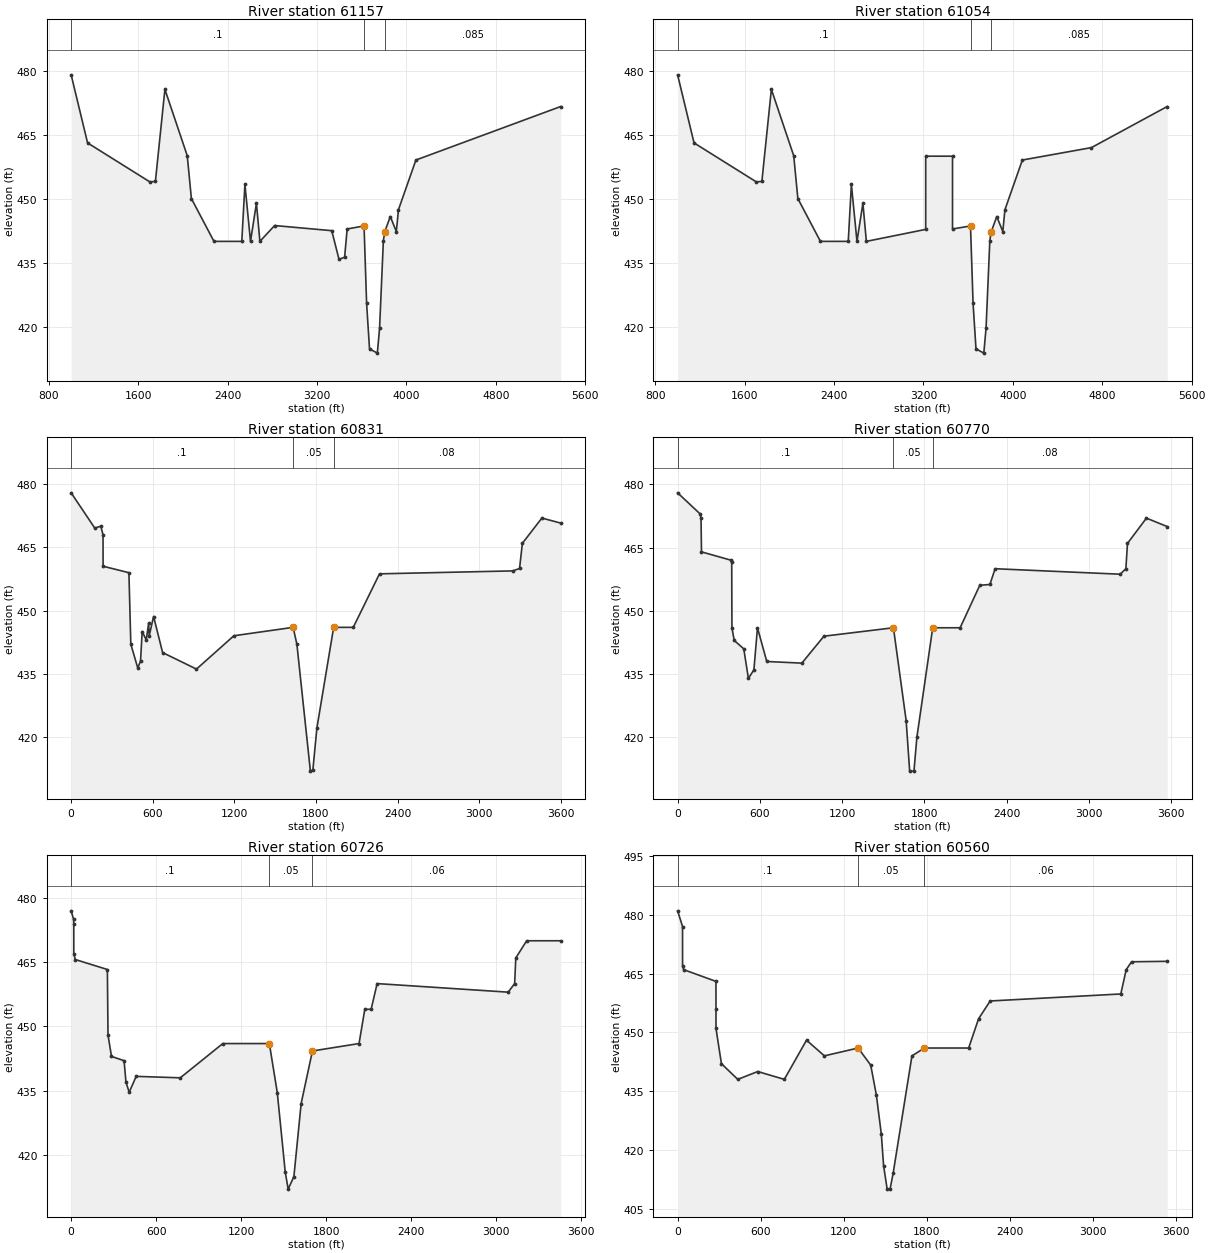
Type RM Length L Ch R = 1 ,61157   ,104,104,104
BEGIN DESCRIPTION:
This cross section corresponds to cross section 61157 of the non-georeferenced CDC model which was the source of this model.
END DESCRIPTION:
XS GIS Cut Line= 6
     2420356.356     6975448.961     2419848.884     6974348.377
     2419794.794     6972446.213     2419740.704     6972090.121
     2419573.927     6971657.4022419329.73591478  6971293.508873
#Sta/Elev= 30
    1000     479    1147   463.1    1704     454    1754   454.1    1839   475.6
    2039   460.1    2076   450.1    2278   440.1    2527   440.1    2555   453.4
    2605   440.1    2658     449    2689   440.1    2821   443.8    3332   442.6
    3397   435.9    3447   436.4    3470     443    3621   443.7    3644   425.6
    3670     415    3740     414    3760   419.8    3794   440.3    3807   442.4
    3856   445.9    3910   442.4    3929   447.5    4085   459.1    5381   471.6
#Mann= 3 ,0,0
    1000      .1       0    3621     .05       0    3807    .085       0
#XS Ineff= 2 , 0
            3621   443.7    3807           442.4
Permanent Ineff=
       F       F
Bank Sta=3621,3807
XS Rating Curve= 0 ,0
Exp/Cntr=0.3,0.1

Type RM Length L Ch R = 1 ,61054   ,174,64,145
BEGIN DESCRIPTION:
This cross section corresponds to cross section 61054 of the non-georeferenced CDC model which was the source of this model.
END DESCRIPTION:
XS GIS Cut Line= 6
     2420460.066     6975453.575     2419952.594     6974352.991
     2419898.504     6972450.827     2419844.414     6972094.735
     2419677.637     6971662.016     2419433.446     6971298.123
#Sta/Elev= 30
    1000     479    1147   463.1    1704     454    1754   454.1    1839   475.6
    2039   460.1    2076   450.1    2278   440.1    2527   440.1    2555   453.4
    2605   440.1    2658     449    2689   440.1    3220   442.9    3220     460
    3460     460    3460     443    3621   443.7    3644   425.6    3670     415
    3740     414    3760   419.8    3794   440.3    3807   442.4    3856   445.9
    3910   442.4    3929   447.5    4085   459.1    4703     462    5381   471.6
#Mann= 3 ,0,0
    1000      .1       0    3621     .05       0    3807    .085       0
Bank Sta=3621,3807
XS Rating Curve= 0 ,0
Exp/Cntr=0.3,0.1

Type RM Length L Ch R = 1 ,60831   ,88,60,45
XS GIS Cut Line= 6
  2420276.5518396974651.243947642420141.135172816974018.43144765
 2420122.90600616972450.72311433 2420052.59350616972062.70228098
2419834.277533926971469.38630877 2419634.62475616971180.75783654
#Sta/Elev= 30
       0     478  173.65  469.62  218.23  470.06  234.62     468   234.8  460.54
  424.75     459   438.8     442  489.84  436.33  510.21     438  522.32     445
   552.4     443  569.77     447  573.98     444  606.09  448.58  672.52     440
  921.53  436.07 1196.42     444 1632.08     446 1659.78     442 1759.11   411.8
 1777.41  412.08 1806.67     422  1930.2     446 2074.33     446 2267.28  458.73
 3247.35  459.43 3296.92     460 3317.83     466 3461.29     472 3599.73   470.8
#Mann= 3 ,0,0
       0      .1       0 1632.08     .05       0  1930.2     .08       0
Bank Sta=1632.08,1930.2
XS Rating Curve= 0 ,0
Exp/Cntr=0.3,0.1

Type RM Length L Ch R = 1 ,60770   ,53,45,36
XS GIS Cut Line= 6
  2420372.4719786974585.705753192420183.669894996973570.08075319
2420179.32961726 6972439.43839212420075.16295055  6972031.452281
2419858.149061656971428.153669862419669.346978346971141.69533655
#Sta/Elev= 30
       0     478  164.16     473  170.76     472  174.08     464  391.84     462
  394.52  461.51  396.17     446   412.7     443  482.42     441  516.14     434
  556.25     436  582.37     446  650.14     438  906.05  437.61 1067.03     444
 1573.82     446 1666.53     424 1692.23     412 1723.56     412 1744.73     420
 1860.34     446  2060.3     446 2203.57  456.07 2277.17  456.26 2315.41     460
 3227.46   458.7  3268.9     460 3280.51     466 3418.75     472 3570.18     470
#Mann= 3 ,0,0
       0      .1       0 1573.82     .05       0 1860.34     .08       0
Bank Sta=1573.82,1860.34
XS Rating Curve= 0 ,0
Exp/Cntr=0.3,0.1

Type RM Length L Ch R = 1 ,60726   ,213,165,125
XS GIS Cut Line= 5
    2420407.19426974418.605058762420229.242811686973457.23353098
2420227.07267281  6972402.5460312419912.402533896971449.85505877
2419708.409478376971087.44186433
#Sta/Elev= 30
       0  476.99    17.3     475   18.61     474   18.79     467    29.1  465.62
  255.82  463.29  260.28     448   284.9     443  373.65     442   387.2     437
   409.9  434.63  459.22  438.34  770.72     438 1070.87     446 1399.62     446
 1455.66  434.54 1511.77     416  1532.5  412.01 1572.96  414.95 1624.22     432
 1703.91  444.27 2033.04     446 2073.65     454 2118.35     454 2160.61     460
 3086.09     458 3131.74     460 3140.01     466 3216.87     470 3457.15     470
#Mann= 3 ,0,0
       0      .1       0 1399.62     .05       0 1703.91     .06       0
Bank Sta=1399.62,1703.91
XS Rating Curve= 0 ,0
Exp/Cntr=0.3,0.1

Type RM Length L Ch R = 1 ,60560   ,20,19,16
BEGIN DESCRIPTION:
---------------------------------------------------------------------
CDC GP020915-1 Elmore Drill Site
Cross-section 6056 - 60831.  Project in LOB.
---------------------------------------------------------------------
END DESCRIPTION:
XS GIS Cut Line= 6
  2420654.5900336974405.584225432420635.058783926974258.01478098
 2420609.01711726974034.490475432420405.024061686973266.26130876
2420372.471978376972300.549503192419862.48933944 6970994.1258921
#Sta/Elev= 30
       0     481   35.62     477   35.84     467   43.36     466  277.09     463
  277.23     456  277.24     451  316.47     442  434.77     438   578.8     440
  770.88     438  931.21     448 1060.47     444 1303.94     446 1394.97  441.65
 1435.86     434 1471.75     424 1487.89     416 1513.83     410 1534.67     410
 1556.88     414 1692.94     444 1783.37     446 2102.54     446  2174.3  453.47
 2258.18     458 3201.62  459.79 3240.83     466 3279.35     468 3536.81  468.12
#Mann= 3 ,0,0
       0      .1       0 1303.94     .05       0 1783.37     .06       0
Bank Sta=1303.94,1783.37
XS Rating Curve= 0 ,0
Exp/Cntr=0.3,0.1