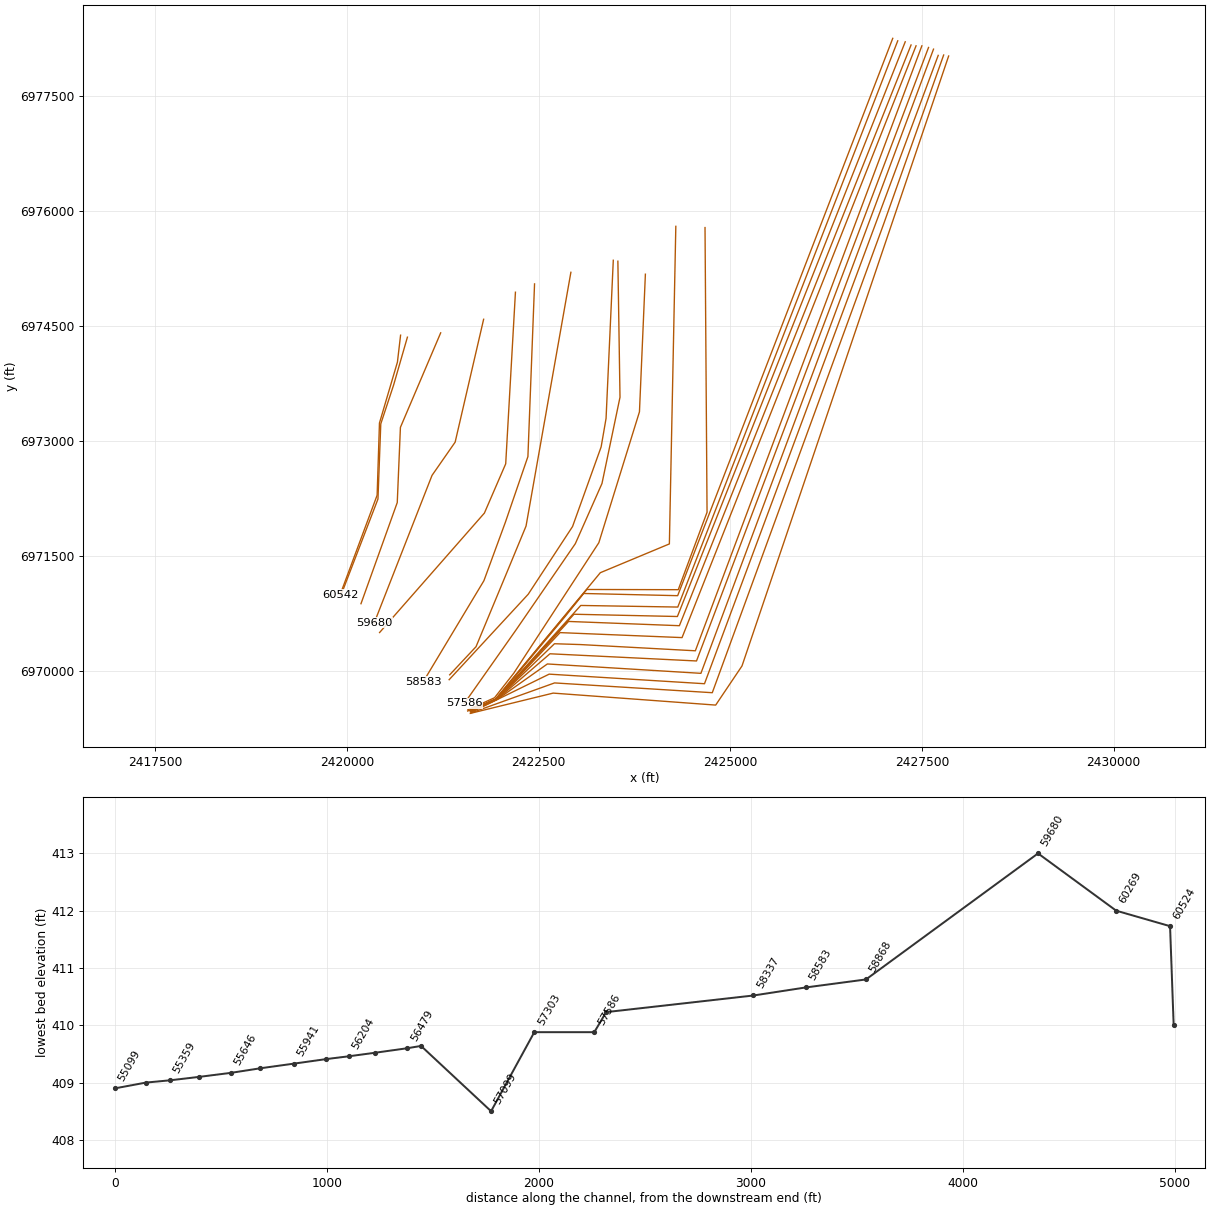
HEC-RAS study CDC_Consolidated_Model.prj: Upper Trinity CDC Consolidated Model

--- CDC_Consolidated_Model.g13 (geometry) --- (continued)

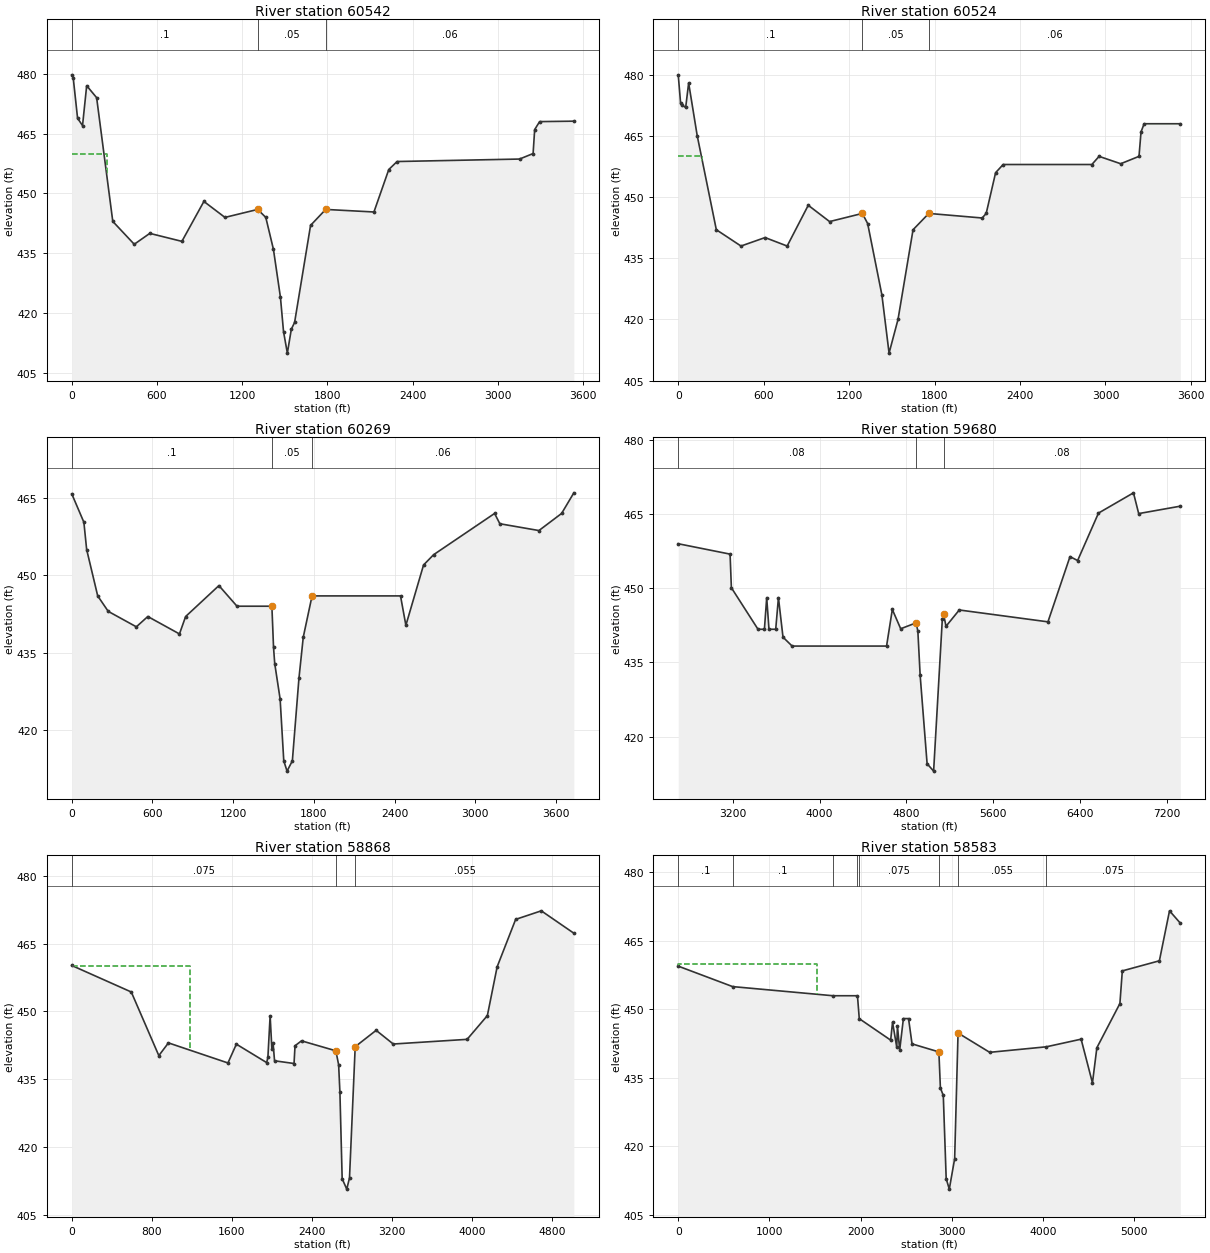
Type RM Length L Ch R = 1 ,60542   ,20,17,13
XS GIS Cut Line= 5
  2420697.9928116974375.202280982420656.76017281  6974023.639781
2420422.385172816973229.368947652420392.003228376972287.52866986
2419910.232395056970991.95575321
#Sta/Elev= 30
       0  479.72   10.11     479   40.85  468.85   75.73     467  104.96     477
     175     474  288.73     443   439.8  437.27   549.3     440  775.25     438
  930.15     448 1078.37     444 1308.86     446  1365.9     444 1419.71     436
 1469.02     424 1490.76  415.39 1517.69     410 1545.74     416 1568.77   417.7
 1681.09     442 1787.63     446  2127.3  445.36 2231.82     456 2290.31     458
 3152.41  458.62 3247.73     460 3258.78     466 3293.69     468 3534.58  468.11
#Mann= 3 ,0,0
       0      .1       0 1308.86     .05       0 1787.63     .06       0
#XS Ineff= 2 , 0
           245.7     460
Permanent Ineff=
       F       F
Bank Sta=1308.86,1787.63
XS Rating Curve= 0 ,0
Exp/Cntr=0.3,0.1

Type RM Length L Ch R = 1 ,60524   ,267,254,195
XS GIS Cut Line= 5
  2420786.9685066974349.160614312420606.846978346973724.16061433
2420439.746283926973218.518253192420402.853922816972237.61547543
2419918.912950556970978.93491988
#Sta/Elev= 30
       0     480    16.7     473    24.1  472.62   52.28     472   73.12     478
  133.09   465.1  267.49     442  440.71     438  609.94  440.08  764.92     438
  913.07     448 1062.89     444 1292.82     446 1330.19  443.52 1430.22     426
 1480.62  411.73 1543.42     420    1649     442 1759.69     446 2134.45  444.88
 2162.69     446 2228.79     456 2281.76     458 2904.78     458  2955.4     460
 3107.27  458.19 3235.82     460 3250.02     466  3271.8     468 3525.87     468
#Mann= 3 ,0,0
       0      .1       0 1292.82     .05       0 1759.69     .06       0
#XS Ineff= 2 , 0
           168.8     460
Permanent Ineff=
       F       F
Bank Sta=1292.82,1759.69
XS Rating Curve= 0 ,0
Exp/Cntr=0.3,0.1

Type RM Length L Ch R = 1 ,60269   ,425,369,245
XS GIS Cut Line= 4
  2421220.9962836974405.584225432420695.822672786973172.94533654
2420654.590033896972192.042558772420181.499756136970872.59811433
#Sta/Elev= 30
       0   465.8   90.04  460.29  110.66     455  192.82     446   271.1     443
  480.15     440  565.36     442  800.66  438.62  846.61     442 1094.09     448
 1228.47     444 1487.88     444 1500.14     436 1508.98  432.88 1549.08     426
 1576.25     414 1600.67     412 1640.12     414 1689.05     430 1721.23     438
 1786.51     446 2444.25     446 2484.14   440.3 2615.56     452 2690.61     454
 3143.78     462 3182.84     460 3473.32  458.68 3642.03     462    3733     466
#Mann= 3 ,0,0
       0      .1       0 1487.88     .05       0 1786.51     .06       0
Bank Sta=1487.88,1786.51
XS Rating Curve= 0 ,0
Exp/Cntr=0.3,0.1

Type RM Length L Ch R = 1 ,59680   ,419,812,882
BEGIN DESCRIPTION:
This cross section corresponds to cross section 59680 of the non-georeferenced CDC model which was the source of this model.
END DESCRIPTION:
XS GIS Cut Line= 4
   2421781.16304 6974582.5035938 2421409.6450831  6972979.853912
 2421108.0761325  6972546.346905 2420353.9240975 6970621.9219481
#Sta/Elev= 30
    2700     459    3177   456.9    3189   450.1    3434   441.7    3493   441.7
    3514   448.1    3535   441.7    3597   441.7    3622   448.1    3664   440.1
    3748   438.3    4617   438.3    4670   445.7    4747   441.8    4889     443
    4905   441.3    4926   432.4    4990   414.5    5050     413    5130   443.7
    5142   444.7    5164   442.3    5286   445.6    6102   443.2    6305   456.4
    6375   455.6    6567   465.2    6889   469.3    6937   465.1    7320   466.6
#Mann= 3 ,0,0
    2700     .08       0    4889     .05       0    5142     .08       0
#XS Ineff= 3 ,-1
    2700    3622   448.1    3622    4659   440.1    5142    7320   444.7
Permanent Ineff=
       T       T       F
Bank Sta=4889,5142
XS Rating Curve= 0 ,0
Exp/Cntr=0.3,0.1

Type RM Length L Ch R = 1 ,58868   ,267,285,457
BEGIN DESCRIPTION:
XS added for transition to natural ground.
2009 lidar
END DESCRIPTION:
XS GIS Cut Line= 5
  2422196.122184 6974935.7709319 2422173.2751176 6974533.0919472
 2422069.1083311 6972697.1543461 2421791.3306715 6972054.7930981
 2420424.1431171 6970496.6334847
#Sta/Elev= 30
       0  460.15  594.41   454.3  869.61  440.26  965.45  443.07 1559.99  438.64
 1644.05  442.79 1946.76  438.72 1958.98  439.87 1981.33  449.06 1998.55  441.82
 2010.85  443.02 2025.36  439.12 2220.15  438.52 2230.02  442.44 2294.81  443.52
 2637.96  441.32 2665.58  438.24 2678.28  432.23 2700.86  413.09 2746.74   410.8
 2774.16  413.28 2831.06  442.23 3040.34  445.84 3211.19  442.82 3948.86  443.85
 4151.14  449.09 4248.83  459.85 4433.67  470.32 4689.82  472.21    5015  467.27
#Mann= 3 ,-1,0
       0    .075       0 2637.96     .05       0 2831.06    .055       0
#XS Ineff= 2 , 0
            1183     460
Permanent Ineff=
       F       F
Bank Sta=2637.96,2831.06
XS Rating Curve= 0 ,0
Exp/Cntr=0.3,0.1

Type RM Length L Ch R = 1 ,58583   ,264,246,261
BEGIN DESCRIPTION:
XS 57642 - 58583 represent Oakdale.
XS 58583 added to represent Oakdale.
2009 lidar with 2001 in LOB STA 0 to 2153
Fill from STA 581 - 1924
END DESCRIPTION:
XS GIS Cut Line= 5
  2422445.340846   6975043.90687  2422358.898762  6972791.866427
  2422065.496134   6971936.83172  2421784.974057  6971172.670847
   2420995.04355  6969857.566849
#Sta/Elev= 30
       0  459.48   596.5     455  1697.1     453  1965.4     453  1985.2  447.98
 2329.53  443.28 2350.14   447.2 2396.13  441.75 2403.82  446.38 2428.59  441.13
 2469.19     448 2525.51     448 2563.86  442.46 2858.32   440.7 2874.83  432.82
 2906.61  431.16 2938.39  412.94 2972.48  410.66 3031.16  417.32 3068.52  444.84
 3415.29  440.61 4036.73  441.82 4418.04  443.49 4542.33  433.92  4590.7  441.61
 4843.36  451.29 4869.79  458.44  5276.2  460.65 5387.42  471.59  5505.8  468.89
#Mann= 8 ,-1,0
       0      .1       0   596.5      .1       0  1697.1    .055       0
  1965.4     .06       0  1985.2    .075       0 2858.32     .05       0
 3068.52    .055       0 4036.73    .075       0
#XS Ineff= 2 , 0
            1525     460
Permanent Ineff=
       F       F
Bank Sta=2858.32,3068.52
XS Rating Curve= 0 ,0
Exp/Cntr=0.3,0.1

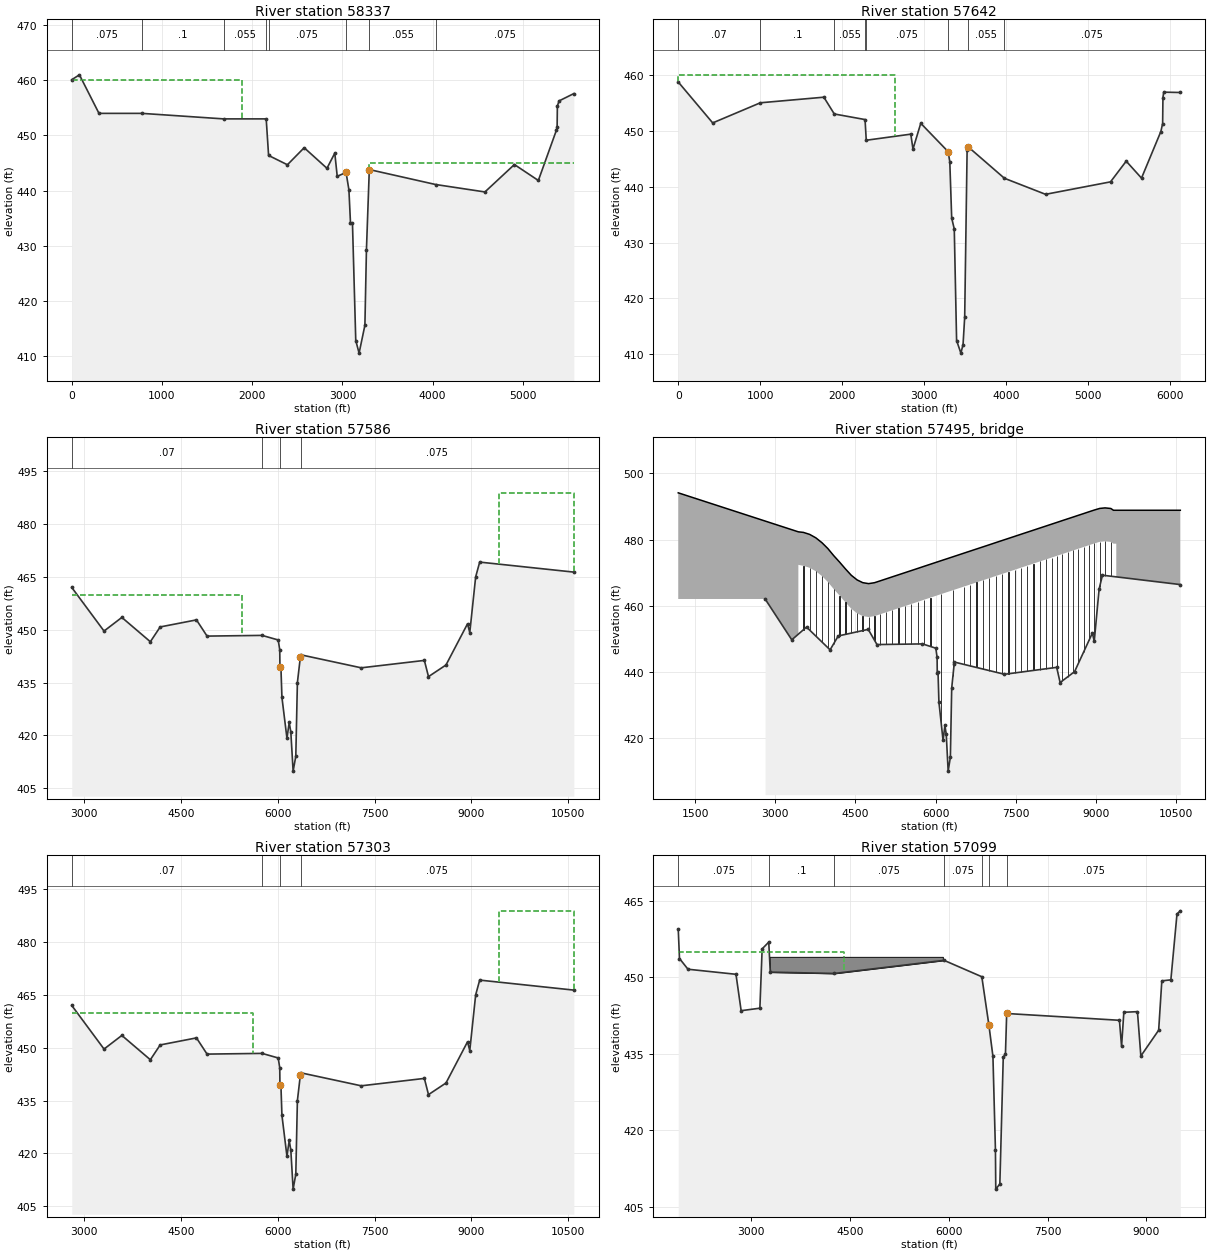
Type RM Length L Ch R = 1 ,58337   ,635,695,520
BEGIN DESCRIPTION:
XS 57642 - 58583 represent Oakdale.
XS 58337 present in effective.
2009 lidar with 2001 in LOB STA 2062 to 4401
Fill from STA 2828 - 4169
END DESCRIPTION:
XS GIS Cut Line= 5
  2422919.422247  6975195.555189  2422334.451961  6971885.196981
  2422075.859302  6971259.801578  2421682.070719  6970311.927161
  2421338.760054  6969945.227107
#Sta/Elev= 30
       0  460.11   84.92  460.99  301.66     454  778.34     454 1682.49     453
 2154.99     453 2181.57  446.37 2390.08  444.68 2575.94  447.77 2828.52  444.04
  2915.4  446.79 2942.19  442.59 3040.19  443.28 3071.72  440.15 3089.22  434.15
 3111.23  434.09  3147.7  412.81 3184.61  410.52 3249.04  415.58 3266.07  429.26
 3297.86  443.81 4032.69   441.1 4579.31  439.75 4906.05  444.72 5171.51  441.83
 5372.08  450.96 5379.48  451.47  5382.4  455.34 5401.19  456.26 5564.93  457.59
#Mann= 8 ,-1,0
       0    .075       0  778.34      .1       0 1682.49    .055       0
 2154.99     .06       0 2181.57    .075       0 3040.19     .05       0
 3297.86    .055       0 4032.69    .075       0
#XS Ineff= 2 , 0
         1890.79     460 3297.86             445
Permanent Ineff=
       F       F
Bank Sta=3040.19,3297.86
XS Rating Curve= 0 ,0
Exp/Cntr=0.3,0.1

Type RM Length L Ch R = 1 ,57642   ,79,56,219
BEGIN DESCRIPTION:
XS 57642 - 58583 represent Oakdale.
XS 57642 added to represent Oakdale.
2009 lidar with 2001 in LOB STA 0 to 2436
Fill from STA 998 - 2234
END DESCRIPTION:
XS GIS Cut Line= 6
  2423472.470026   6975352.26813  2423378.200201  6973289.557361
  2423313.964109  6972918.029561  2422941.061968  6971878.967006
  2422362.719949  6970995.937604  2421331.469715  6969881.354203
#Sta/Elev= 30
       0  458.72  420.04   451.4    1001     455    1775     456    1902     453
    2277     452 2291.79   448.3 2834.74  449.39 2861.32  446.72  2956.3  451.33
 3289.97  446.26 3310.08  444.45 3333.24  434.38 3364.56  432.44 3392.98  412.48
 3445.37  410.23 3471.69  411.77  3491.7  416.68 3521.11   446.5 3534.01  447.12
 3975.73   441.5 4477.45  438.63 5269.41  440.86 5460.45  444.56 5646.82  441.53
 5882.75  449.86 5904.49  451.29 5908.16  455.94 5917.78   456.9  6119.9  456.84
#Mann= 8 ,-1,0
       0     .07       0    1001      .1       0    1902    .055       0
    2277     .06       0 2291.79    .075       0 3289.97     .05       0
 3534.01    .055       0 3975.73    .075       0
#XS Ineff= 2 , 0
            2637     460
Permanent Ineff=
       F       F
Bank Sta=3289.97,3534.01
XS Rating Curve= 0 ,0
Exp/Cntr=0.3,0.1

Type RM Length L Ch R = 1 ,57586   ,354,283,357
BEGIN DESCRIPTION:
This cross section corresponds to cross section 57586 of the non-georeferenced CDC model which was the source of this model.
Upstream bounding cross-section.
Section data is generated through the TXdot's topo file.
END DESCRIPTION:
XS GIS Cut Line= 6
  2423532.232701  6975340.146435  2423560.017751  6973565.834367
  2423325.022158  6972440.851709  2422977.504152  6971655.989434
  2422200.099539  6970525.219057  2421528.704884  6969571.131727
#Sta/Elev= 30
    2807     462    3307  449.63    3583   453.5 4024.62   446.6 4177.12   450.8
 4739.32   452.8 4903.42   448.2 5756.12   448.4 6006.02   447.1 6029.82   444.3
 6032.72  439.46 6047.22   439.8 6063.82   430.8 6141.52   419.2 6176.42   423.7
 6201.42     421 6237.12  409.88 6278.62   414.1 6303.32     435 6350.22   442.4
 6353.92   442.9 7292.62   439.2 8270.82   441.3 8334.92   436.7 8605.92     440
 8939.92   451.7 8974.52   449.2 9065.82     465 9128.12   469.210587.26  466.36
#Mann= 4 ,-1,0
    2807     .07       0 5756.12    .075       0 6032.72     .05       0
 6353.92    .075       0
#XS Ineff= 2 , 0
            5445     460 9422.26          488.86
Permanent Ineff=
       F       F
Bank Sta=6032.72,6350.22
XS Rating Curve= 0 ,0
Exp/Cntr=0.3,0.1

Type RM Length L Ch R = 3 ,57495   ,,,
BEGIN DESCRIPTION:
SH161
END DESCRIPTION:
Bridge Culvert--1,0,-1,-1, 0
Deck Dist Width WeirC Skew NumUp NumDn MinLoCord MaxHiCord MaxSubmerge Is_Ogee
47,166,2.6,0, 57, 57, , , 0.98, 0, 0,0,,
 1179.12 3430.12 3430.12 3525.12 3641.12 3757.12 3872.12 3982.12 4092.12 4202.12
 4312.12 4422.12 4532.12 4637.12 4747.12 4857.12 4967.12 5077.12 5187.12 5307.12
 5427.12 5547.12 5667.12 5787.12 5907.12 6107.12 6327.12 6527.12 6647.12 6767.12
 6887.12 7007.12 7127.12 7247.12 7367.12 7487.12 7595.26 7715.26 7835.26 7955.26
 8075.26 8176.26 8277.26 8377.26 8477.26 8577.26 8677.26 8777.26 8877.26 8977.26
 9077.26 9177.26 9285.26    9335 9387.26 9387.2610587.26
  494.14  482.33  482.33  482.16  481.56  480.52  479.04  477.28  475.13  473.17
  471.11  469.17  467.76  466.94  466.65  466.93  467.51   468.1  468.69  469.33
  469.97  470.61  471.25   471.9  472.54  473.61  474.78  475.85  476.49  477.13
  477.77  478.41  479.06   479.7  480.34  480.98  481.56   482.2  482.84  483.48
  484.12  484.66   485.2  485.74  486.27   486.8  487.34  487.87  488.41  488.94
  489.42  489.58   489.4  488.86  488.86  488.86  488.86
       0       0  472.33  472.04  471.44   470.4  468.95  467.16  465.01  463.05
  460.99  459.05  457.64  456.82  456.53  456.81  457.39  457.98  458.57  459.21
  459.85  460.49  461.13  461.78  462.42  463.49  464.66  465.73  466.37  467.01
  467.65  468.29  468.94  469.58  470.22  470.86  471.44  472.08  472.72  473.36
     474  474.54  475.08  475.62  476.15  476.68  477.22  477.75  478.29  478.82
   479.3  479.46  479.28  478.74  478.74       0       0
 1179.12 3430.12 3430.12 3525.12 3641.12 3757.12 3872.12 3982.12 4092.12 4202.12
 4312.12 4422.12 4532.12 4637.12 4747.12 4857.12 4967.12 5077.12 5187.12 5307.12
 5427.12 5547.12 5667.12 5787.12 5907.12 6107.12 6327.12 6527.12 6647.12 6767.12
 6887.12 7007.12 7127.12 7247.12 7367.12 7487.12 7595.26 7715.26 7835.26 7955.26
 8075.26 8176.26 8277.26 8377.26 8477.26 8577.26 8677.26 8777.26 8877.26 8977.26
 9077.26 9177.26 9285.26    9335 9387.26 9387.2610587.26
  494.14  482.33  482.33  482.16  481.56  480.52  479.04  477.28  475.13  473.17
  471.11  469.17  467.76  466.94  466.65  466.93  467.51   468.1  468.69  469.33
  469.97  470.61  471.25   471.9  472.54  473.61  474.78  475.85  476.49  477.13
  477.77  478.41  479.06   479.7  480.34  480.98  481.56   482.2  482.84  483.48
  484.12  484.66   485.2  485.74  486.27   486.8  487.34  487.87  488.41  488.94
  489.42  489.58   489.4  488.86  488.86  488.86  488.86
       0       0  472.33  472.04  471.44   470.4  468.95  467.16  465.01  463.05
  460.99  459.05  457.64  456.82  456.53  456.81  457.39  457.98  458.57  459.21
  459.85  460.49  461.13  461.78  462.42  463.49  464.66  465.73  466.37  467.01
  467.65  468.29  468.94  469.58  470.22  470.86  471.44  472.08  472.72  473.36
     474  474.54  475.08  475.62  476.15  476.68  477.22  477.75  478.29  478.82
   479.3  479.46  479.28  478.74  478.74       0       0
Pier Skew, UpSta & Num, DnSta & Num=  ,3525.12, 2 ,3525.12, 2 , 0 , 0 , 0 ,,
       4       4
     440  482.33
       4       4
     440  482.33
Pier Skew, UpSta & Num, DnSta & Num=  ,3641.12, 2 ,3641.12, 2 , 0 , 0 , 0 ,,
       4       4
     440  482.33
       4       4
     440  482.33
Pier Skew, UpSta & Num, DnSta & Num=  ,3757.12, 2 ,3757.12, 2 , 0 , 0 , 0 ,,
       4       4
     440  482.33
       4       4
     440  482.33
Pier Skew, UpSta & Num, DnSta & Num=  ,3872.12, 2 ,3872.12, 2 , 0 , 0 , 0 ,,
       4       4
     440  482.33
       4       4
     440  482.33
Pier Skew, UpSta & Num, DnSta & Num=  ,3982.12, 2 ,3982.12, 2 , 0 , 0 , 0 ,,
       4       4
     440  482.33
       4       4
     440  482.33
Pier Skew, UpSta & Num, DnSta & Num=  ,4092.12, 2 ,4092.12, 2 , 0 , 0 , 0 ,,
       4       4
     440  482.33
       4       4
     440  482.33
Pier Skew, UpSta & Num, DnSta & Num=  ,4202.12, 2 ,4202.12, 2 , 0 , 0 , 0 ,,
       4       4
     440  482.33
       4       4
     440  482.33
Pier Skew, UpSta & Num, DnSta & Num=  ,4312.12, 2 ,4312.12, 2 , 0 , 0 , 0 ,,
       4       4
     440  482.33
       4       4
     440  482.33
Pier Skew, UpSta & Num, DnSta & Num=  ,4422.12, 2 ,4422.12, 2 , 0 , 0 , 0 ,,
       4       4
     440  482.33
       4       4
     440  482.33
Pier Skew, UpSta & Num, DnSta & Num=  ,4532.12, 2 ,4532.12, 2 , 0 , 0 , 0 ,,
       4       4
     440  482.33
       4       4
     440  482.33
Pier Skew, UpSta & Num, DnSta & Num=  ,4632.12, 2 ,4632.12, 2 , 0 , 0 , 0 ,,
       4       4
     440  482.33
       4       4
     440  482.33
Pier Skew, UpSta & Num, DnSta & Num=  ,4747.12, 2 ,4747.12, 2 , 0 , 0 , 0 ,,
       4       4
     440  482.33
       4       4
     440  482.33
Pier Skew, UpSta & Num, DnSta & Num=  ,4857.12, 2 ,4857.12, 2 , 0 , 0 , 0 ,,
       4       4
     440  482.33
       4       4
     440  482.33
Pier Skew, UpSta & Num, DnSta & Num=  ,4967.12, 2 ,4967.12, 2 , 0 , 0 , 0 ,,
       4       4
     440  482.33
       4       4
     440  482.33
Pier Skew, UpSta & Num, DnSta & Num=  ,5077.12, 2 ,5077.12, 2 , 0 , 0 , 0 ,,
       4       4
     440  482.33
       4       4
     440  482.33
Pier Skew, UpSta & Num, DnSta & Num=  ,5187.12, 2 ,5187.12, 2 , 0 , 0 , 0 ,,
       4       4
     440  482.33
       4       4
     440  482.33
Pier Skew, UpSta & Num, DnSta & Num=  ,5307.12, 2 ,5307.12, 2 , 0 , 0 , 0 ,,
       4       4
     440  482.33
       4       4
     440  482.33
Pier Skew, UpSta & Num, DnSta & Num=  ,5427.12, 2 ,5427.12, 2 , 0 , 0 , 0 ,,
       4       4
     440  482.33
       4       4
     440  482.33
Pier Skew, UpSta & Num, DnSta & Num=  ,5547.12, 2 ,5547.12, 2 , 0 , 0 , 0 ,,
       4       4
     440  482.33
       4       4
     440  482.33
Pier Skew, UpSta & Num, DnSta & Num=  ,5667.12, 2 ,5667.12, 2 , 0 , 0 , 0 ,,
       4       4
     440  482.33
       4       4
     440  482.33
Pier Skew, UpSta & Num, DnSta & Num=  ,5787.12, 2 ,5787.12, 2 , 0 , 0 , 0 ,,
       4       4
     440  482.33
       4       4
     440  482.33
Pier Skew, UpSta & Num, DnSta & Num=  ,5907.12, 2 ,5907.12, 2 , 0 , 0 , 0 ,,
       4       4
     440  482.33
       4       4
     440  482.33
Pier Skew, UpSta & Num, DnSta & Num=  ,6107.12, 2 ,6107.12, 2 , 0 , 0 , 0 ,,
       4       4
     440  482.33
       4       4
     440  482.33
Pier Skew, UpSta & Num, DnSta & Num=  ,6327.12, 2 ,6327.12, 2 , 0 , 0 , 0 ,,
       4       4
     440  482.33
       4       4
     440  482.33
Pier Skew, UpSta & Num, DnSta & Num=  ,6527.12, 2 ,6527.12, 2 , 0 , 0 , 0 ,,
       4       4
     440  482.33
       4       4
     440  482.33
Pier Skew, UpSta & Num, DnSta & Num=  ,6647.12, 2 ,6647.12, 2 , 0 , 0 , 0 ,,
       4       4
     440  482.33
       4       4
     440  482.33
Pier Skew, UpSta & Num, DnSta & Num=  ,6767.12, 2 ,6767.12, 2 , 0 , 0 , 0 ,,
       4       4
     440  482.33
       4       4
     440  482.33
Pier Skew, UpSta & Num, DnSta & Num=  ,6887.12, 2 ,6887.12, 2 , 0 , 0 , 0 ,,
       4       4
     440  482.33
       4       4
     440  482.33
Pier Skew, UpSta & Num, DnSta & Num=  ,7007.12, 2 ,7007.12, 2 , 0 , 0 , 0 ,,
       4       4
     440  482.33
       4       4
     440  482.33
Pier Skew, UpSta & Num, DnSta & Num=  ,7127.12, 2 ,7127.12, 2 , 0 , 0 , 0 ,,
       4       4
     440  482.33
       4       4
     440  482.33
Pier Skew, UpSta & Num, DnSta & Num=  ,7247.12, 2 ,7247.12, 2 , 0 , 0 , 0 ,,
       4       4
     440  482.33
       4       4
     440  482.33
Pier Skew, UpSta & Num, DnSta & Num=  ,7367.12, 2 ,7367.12, 2 , 0 , 0 , 0 ,,
       4       4
     440  482.33
       4       4
     440  482.33
Pier Skew, UpSta & Num, DnSta & Num=  ,7487.12, 2 ,7487.12, 2 , 0 , 0 , 0 ,,
       4       4
     440  482.33
       4       4
     440  482.33
Pier Skew, UpSta & Num, DnSta & Num=  ,7595.26, 2 ,7595.26, 2 , 0 , 0 , 0 ,,
       4       4
     440  482.33
       4       4
     440  482.33
Pier Skew, UpSta & Num, DnSta & Num=  ,7715.26, 2 ,7715.26, 2 , 0 , 0 , 0 ,,
       4       4
     440  482.33
       4       4
     440  482.33
Pier Skew, UpSta & Num, DnSta & Num=  ,7835.26, 2 ,7835.26, 2 , 0 , 0 , 0 ,,
       4       4
     440  482.33
       4       4
     440  482.33
Pier Skew, UpSta & Num, DnSta & Num=  ,7955.26, 2 ,7955.26, 2 , 0 , 0 , 0 ,,
       4       4
     440  482.33
       4       4
     440  482.33
Pier Skew, UpSta & Num, DnSta & Num=  ,8075.26, 2 ,8075.26, 2 , 0 , 0 , 0 ,,
       4       4
     440  482.33
       4       4
     440  482.33
Pier Skew, UpSta & Num, DnSta & Num=  ,8176.26, 2 ,8176.26, 2 , 0 , 0 , 0 ,,
       4       4
     440  482.33
       4       4
     440  482.33
Pier Skew, UpSta & Num, DnSta & Num=  ,8277.26, 2 ,8277.26, 2 , 0 , 0 , 0 ,,
       4       4
     440  482.33
       4       4
     440  482.33
Pier Skew, UpSta & Num, DnSta & Num=  ,8377.26, 2 ,8377.26, 2 , 0 , 0 , 0 ,,
       4       4
     440  482.33
       4       4
     440  482.33
Pier Skew, UpSta & Num, DnSta & Num=  ,8477.26, 2 ,8477.26, 2 , 0 , 0 , 0 ,,
       4       4
     440  482.33
       4       4
     440  482.33
Pier Skew, UpSta & Num, DnSta & Num=  ,8577.26, 2 ,8577.26, 2 , 0 , 0 , 0 ,,
       4       4
     440  482.33
       4       4
     440  482.33
Pier Skew, UpSta & Num, DnSta & Num=  ,8677.26, 2 ,8677.26, 2 , 0 , 0 , 0 ,,
       4       4
     440  482.33
       4       4
     440  482.33
Pier Skew, UpSta & Num, DnSta & Num=  ,8777.26, 2 ,8777.26, 2 , 0 , 0 , 0 ,,
       4       4
     440  482.33
       4       4
     440  482.33
Pier Skew, UpSta & Num, DnSta & Num=  ,8877.26, 2 ,8877.26, 2 , 0 , 0 , 0 ,,
       4       4
     440  482.33
       4       4
     440  482.33
Pier Skew, UpSta & Num, DnSta & Num=  ,8977.26, 2 ,8977.26, 2 , 0 , 0 , 0 ,,
       4       4
     440  482.33
       4       4
     440  482.33
Pier Skew, UpSta & Num, DnSta & Num=  ,9077.26, 2 ,9077.26, 2 , 0 , 0 , 0 ,,
       4       4
     440  482.33
       4       4
     440  482.33
Pier Skew, UpSta & Num, DnSta & Num=  ,9177.26, 2 ,9177.26, 2 , 0 , 0 , 0 ,,
       4       4
     440  482.33
       4       4
     440  482.33
Pier Skew, UpSta & Num, DnSta & Num=  ,9282.26, 2 ,9282.26, 2 , 0 , 0 , 0 ,,
       4       4
     440  482.33
       4       4
     440  482.33
Abutment Skew #Up #Dn= , 2 , 2
 3430.12    3465
  482.33     440
 3430.12    3465
  482.33     440
Abutment Skew #Up #Dn= , 2 , 2
    9335 9387.26
     440  488.86
    9335 9387.26
     440  488.86
BR Coef=-1 , 1 , 1 ,0.9, 0 ,,,0.8,-1,1.33,0,
WSPro=,,,, 1 ,,,, 0 ,,,, 0 ,,,,-1 ,-1 ,-1 , 0 , 0 , 0 , 0 , 0
BC Design=,, 0 ,, 0 ,,,,,,
BC Use User HTab Curves=0
BC User HTab FreeFlow(D)= 0

Type RM Length L Ch R = 1 ,57303   ,926,204,183
BEGIN DESCRIPTION:
This cross section corresponds to cross section 57303 of the non-georeferenced CDC model which was the source of this model.
Downstream bounding cross-section.
Copied from cross-section 57586
END DESCRIPTION:
XS GIS Cut Line= 6
  2423891.171944  6975170.664819  2423813.803004  6973375.702202
  2423283.754524  6971667.768282  2422175.043815  6969967.177523
   2421923.77332  6969645.988532  2421575.466274  6969488.870408
#Sta/Elev= 30
    2807     462    3307  449.63    3583   453.5 4024.62   446.6 4177.12   450.8
 4739.32   452.8 4903.42   448.2 5756.12   448.4 6006.02   447.1 6029.82   444.3
 6032.72  439.46 6047.22   439.8 6063.82   430.8 6141.52   419.2 6176.42   423.7
 6201.42     421 6237.12  409.88 6278.62   414.1 6303.32     435 6350.22   442.4
 6353.92   442.9 7292.62   439.2 8270.82   441.3 8334.92   436.7 8605.92     440
 8939.92   451.7 8974.52   449.2 9065.82     465 9128.12   469.210587.26  466.36
#Mann= 4 ,-1,0
    2807     .07       0 5756.12    .075       0 6032.72     .05       0
 6353.92    .075       0
#XS Ineff= 2 , 0
            5610     460 9422.26          488.86
Permanent Ineff=
       F       F
Bank Sta=6032.72,6350.22
XS Rating Curve= 0 ,0
Exp/Cntr=0.3,0.1

Type RM Length L Ch R = 1 ,57099   ,565.9,330.56,1.49
BEGIN DESCRIPTION:
Station equation. Downstream RS 56543 + 330.56 = 56873.56. RS 57099 = RS 56874
END DESCRIPTION:
XS GIS Cut Line= 6
  2424288.123906 6975794.8436888  2424204.040413 6971652.4868161
 2423303.2695767 6971277.0252966 2421937.0498682 6969627.2392262
 2421609.7276882 6969487.7001351 2421573.2051235 6969472.8313985
#Sta/Elev= 30
    1890  459.43 1909.05  453.67 2038.05  451.57 2767.17  450.58 2845.63  443.45
 3130.37  443.94 3164.76  455.56 3265.16  456.88 3288.31     451 4261.61  450.74
 5928.76  453.31    6502   450.1    6609   440.7    6671   434.5    6709   416.2
    6714   408.5    6776   409.5    6828   434.4    6861   434.9    6880   442.9
 8592.76  441.57 8625.28  436.47 8659.76  443.14 8866.51  443.26 8918.22  434.57
  9188.9  439.63 9236.77  449.29 9374.14  449.49 9467.34  462.39 9517.71  463.01
#Mann= 7 ,-1,0
    1890    .075       0 3265.16      .1       0 4261.61    .075       0
 5928.76    .075       0    6502     .12       0    6609     .05       0
    6880    .075       0
#XS Ineff= 3 ,-1
    1890    4407     455    5910    6609   440.7    6880 9517.71   442.9
Permanent Ineff=
       F       F       F
#Block Obstruct= 1 ,-1
    3197    5910     454
Bank Sta=6609,6880
XS Rating Curve= 0 ,0
Exp/Cntr=0.3,0.1

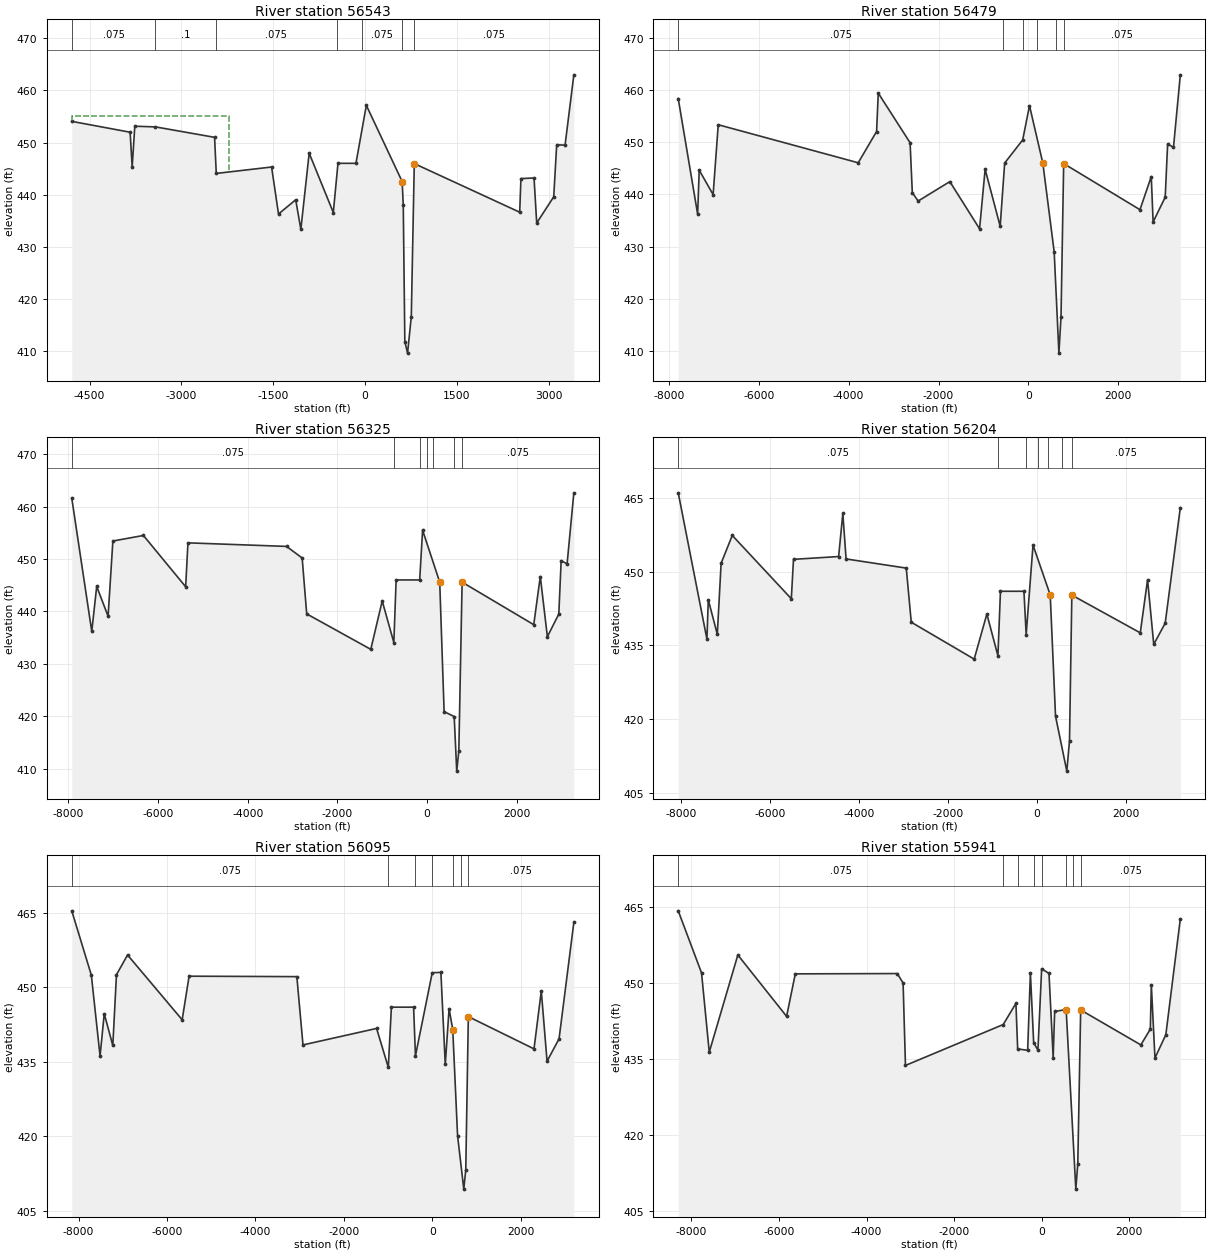
Type RM Length L Ch R = 1 ,56543   ,75.31,64.13,4.46
XS GIS Cut Line= 6
  2424668.952212 6975778.6307947 2424695.4665955 6972065.4590872
 2424319.8610475 6971055.4473277  2423127.152803 6971058.0513251
 2421937.2703402 6969627.0115363 2421609.0898942 6969486.6686412
#Sta/Elev= 30
   -4791  454.06-3837.66  451.98-3804.22  445.32-3761.33  453.13-3423.85     453
-2458.11     451-2430.43  444.08-1526.83  445.31-1413.71  436.31-1132.74  439.03
 -1048.9  433.36 -912.83  447.96 -518.56  436.59 -442.27  446.02 -148.54  446.02
   20.96  457.13  606.36  442.52  624.25  438.01  649.92  411.86  694.35  409.64
  755.45  416.63  804.26  445.97  2526.3  436.65 2546.59  443.09 2760.53  443.21
 2804.12  434.58 3082.16   439.6 3130.59  449.57 3267.35   449.5 3410.82  462.98
#Mann= 7 ,-1,0
   -4791    .075       0-3423.85      .1       0-2430.43    .075       0
-465.669      .1       0-53.7099    .075       0606.3599     .05       0
804.2598    .075       0
#XS Ineff= 2 , 0
           -2217     455
Permanent Ineff=
       F       F
Bank Sta=606.36,804.26
XS Rating Curve= 0 ,0
Exp/Cntr=0.3,0.1

Type RM Length L Ch R = 1 ,56479   ,153.13,154.18,161.09
XS GIS Cut Line= 6
  2427117.705189 6978247.1048604 2424312.0487271 6970977.3221559
 2423085.4862196  6971005.968096 2422839.2767383 6970699.7826847
 2421947.4589681 6969630.7667781 2421608.9281491 6969483.3513906
#Sta/Elev= 30
 -7792.4  458.37 -7360.4  436.22-7325.61  444.65-7016.01  439.97 -6902.2  453.36
-3787.18  446.07-3378.12  452.06-3340.58  459.41-2632.42  449.91-2583.11  440.34
-2453.19  438.74-1748.13  442.46-1086.26  433.42 -962.55  444.82  -627.6  433.91
 -527.66  446.02 -126.48  450.45   24.89  457.01  321.58     446  574.29  429.01
  679.38   409.6  726.19   416.5  785.64  445.92 2483.37  437.08 2735.06  443.43
 2775.94  434.73 3045.35  439.48 3098.68  449.64 3229.57  449.05 3381.22  462.92
#Mann= 6 ,-1,0
 -7792.4    .075       0-554.339      .1       0 -126.48    .075       0
185.8799     .06       0623.1704     .05       0785.6401    .075       0
Bank Sta=321.58,785.64
XS Rating Curve= 0 ,0
Exp/Cntr=0.3,0.1

Type RM Length L Ch R = 1 ,56325   ,124.93,120.76,118.42
XS GIS Cut Line= 6
  2427182.809061 6978214.5527601 2424313.7846161 6970828.8847887
 2423048.1598507 6970849.7180804 2422887.8963917 6970671.8332656
 2421950.1115219 6969629.8940765 2421610.7867412 6969480.2149139
#Sta/Elev= 30
-7924.38  461.62-7478.25  436.19-7368.27  444.78-7114.01  439.09-7007.32  453.45
-6326.13  454.51-5383.52  444.72-5332.52   453.1-3132.52  452.42-2784.24  450.21
-2683.19  439.54 -1253.3  432.77 -998.22  442.01 -738.87  434.06 -687.91  446.02
 -162.44  446.02  -97.42  455.51  284.49   445.6   382.8  420.88  607.36  419.94
  664.19  409.52  711.05  413.44  784.06   445.6 2382.41  437.48 2528.33  446.67
 2686.08  435.18 2941.48  439.51 2993.96   449.7  3126.3  449.09 3276.88  462.65
#Mann= 7 ,-1,0
-7924.38    .075       0 -738.87      .1       0-162.439    .075       0
7.009766    .075       0141.7202     .06       0607.3604     .05       0
784.0596    .075       0
Bank Sta=284.49,784.06
XS Rating Curve= 0 ,0
Exp/Cntr=0.3,0.1

Type RM Length L Ch R = 1 ,56204   ,118.99,108.45,100.53
XS GIS Cut Line= 6
  2427280.465362 6978201.9189272 2424308.5762931 6970705.6209277
 2422959.6180331 6970735.1346481 2422164.4792034 6969860.1347577
 2421950.4248415 6969629.0837106 2421607.0269062 6969477.8235145
#Sta/Elev= 30
-8068.33  466.03-7423.36  436.29-7392.85  444.29-7190.23  437.28-7104.36  451.71
-6853.59  457.37-5526.42   444.5-5477.43  452.51-4462.86  453.08-4368.59  461.84
-4295.54  452.59-2942.75  450.73-2830.44  439.73-1415.98  432.23-1131.11  441.39
 -882.59  432.92 -825.33  446.02 -297.78  446.02 -247.48  437.22  -93.41  455.41
  293.22  445.28   412.4  420.64  666.03  409.46  726.67  415.63  779.15  445.24
 2317.53  437.57 2481.19  448.37 2620.11  435.23 2877.73  439.54 3217.37  463.01
#Mann= 7 ,-1,0
-8068.33    .075       0-882.589      .1       0-262.189    .075       0
9.740234    .075       0253.1699     .06       0552.9502     .05       0
779.1504    .075       0
#Block Obstruct= 1 ,-1
       0     180     440
Bank Sta=293.22,779.15
XS Rating Curve= 0 ,0
Exp/Cntr=0.3,0.1

Type RM Length L Ch R = 1 ,56095   ,158.52,154.24,151.9
XS GIS Cut Line= 6
  2427356.420263 6978160.2992597 2424334.6179077 6970585.8291725
 2422888.5712591 6970641.1604267 2422023.1169533 6969702.9109908
 2421950.4428861  6969628.309434 2421606.9576806 6969476.4472049
#Sta/Elev= 30
-8154.98   465.4-7712.16  452.46   -7515  436.18-7420.31   444.7-7226.69  438.31
-7143.76  452.55-6893.08  456.52-5657.39  443.48-5500.73  452.25-3063.26  452.16
-2924.28  438.42-1259.26  441.74 -994.08  433.91 -924.23  446.02 -421.85  446.02
 -379.89  436.23       0  452.95  195.47  453.01  294.47   434.5  380.99  445.72
  464.06  441.49  572.86  420.18  713.39  409.41   758.4  413.31  816.33  444.12
 2302.08  437.63 2466.83  449.27 2597.12  435.14 2869.01  439.66 3203.27  463.07
#Mann= 7 ,-1,0
-8154.98    .075       0 -994.08      .1       0 -379.89    .075       0
       0    .075       0464.0601     .06       0652.0005     .05       0
816.3296    .075       0
Bank Sta=464.06,816.33
XS Rating Curve= 0 ,0
Exp/Cntr=0.3,0.1

Type RM Length L Ch R = 1 ,55941   ,163,156,147.12
XS GIS Cut Line= 6
  2427421.524463 6978149.4485596 2424369.3402792 6970430.4472654
 2422778.1945114 6970495.5514659 2422202.4473033 6969882.8591217
 2421951.4628971 6969627.5026771 2421608.7588581 6969473.7103337
#Sta/Elev= 30
-8300.55   464.3 -7768.5  452.04-7592.08  436.39-6939.06  455.58-5825.18  443.45
-5627.11  451.85-3297.72  451.91-3164.89  450.04-3110.61  433.76 -877.98  441.84
 -587.54  446.02 -548.29  437.03 -319.94  436.74 -257.11  452.02 -182.52  438.25
  -85.02  436.79       0  452.86   167.7  451.93  262.96  435.31   297.1  444.42
  559.35   444.8  780.35  409.33  825.47  414.38  891.27  444.72 2265.37  437.82
 2482.12  440.93 2505.06  449.69 2587.68  435.22 2836.51  439.84 3166.93  462.67
#Mann= 8 ,-1,0
-8300.55    .075       0 -877.98      .1       0 -548.29    .075       0
 -182.52    .075       0       0    .075       0559.3496     .06       0
720.5703     .05       0891.2705    .075       0
Bank Sta=559.35,891.27
XS Rating Curve= 0 ,0
Exp/Cntr=0.3,0.1

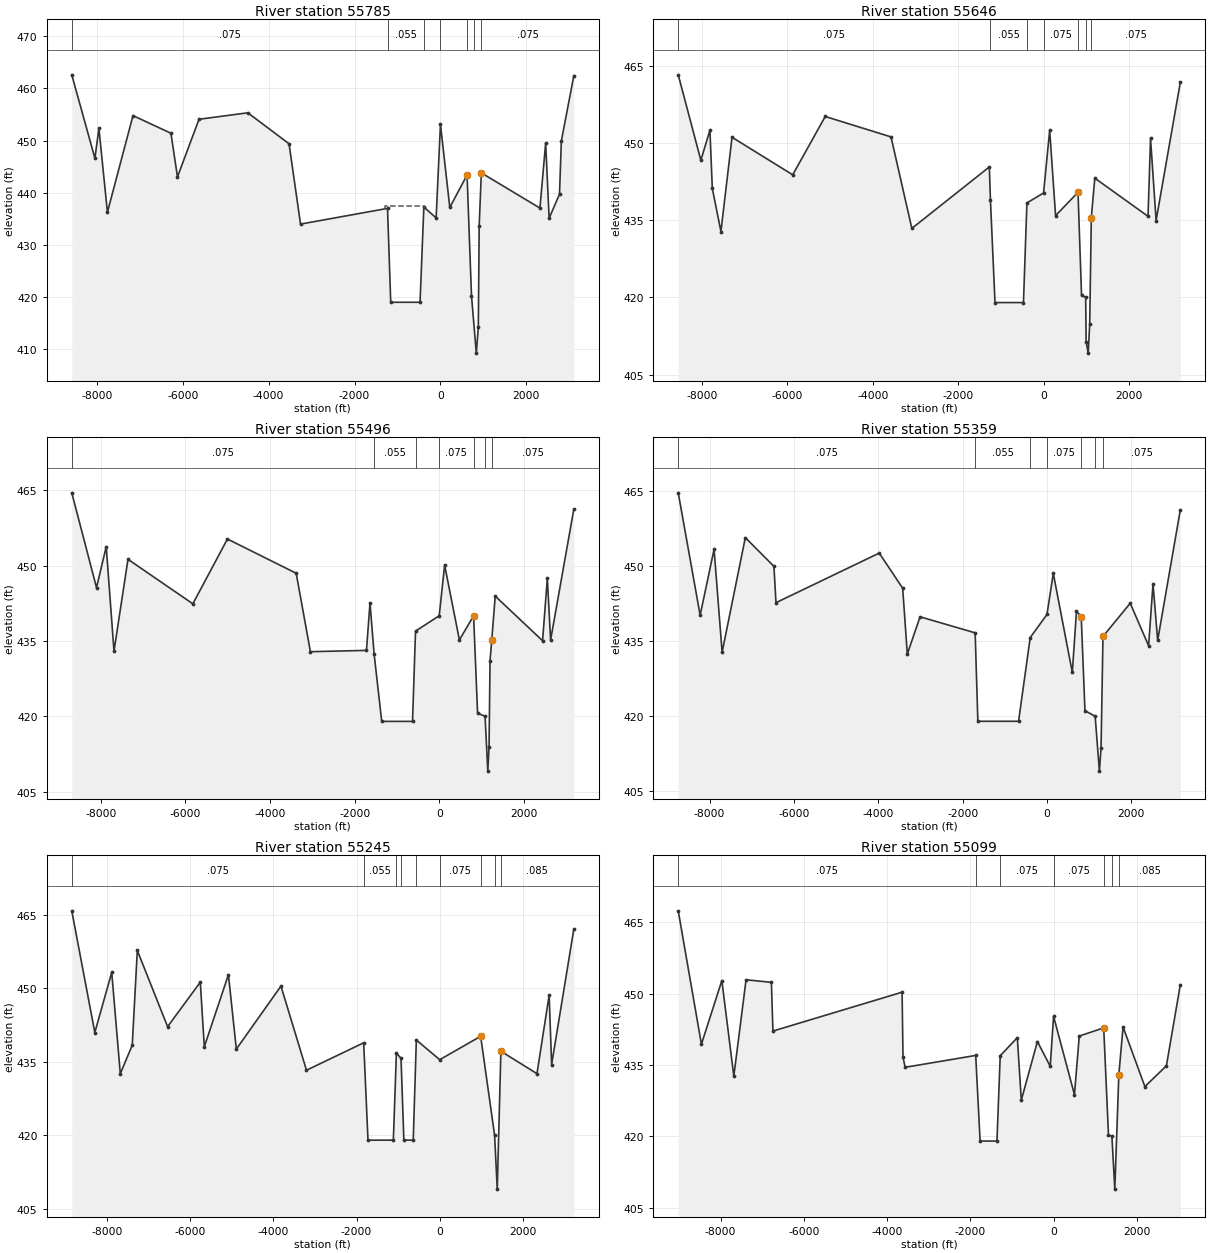
Type RM Length L Ch R = 1 ,55785   ,135.88,139.03,141.1
BEGIN DESCRIPTION:
Proposed Pond
END DESCRIPTION:
XS GIS Cut Line= 6
  2427497.479364 6978149.4485596 2424542.9035804 6970258.4138168
 2423044.2481131 6970339.6101767 2422705.5207722 6970350.4933571
 2421950.7194603 6969624.7487456 2421609.3336601 6969470.8081086
#Sta/Elev= 30
-8582.55  462.61-8043.85   446.6-7950.62  452.35-7752.65  436.26-7157.34  454.79
-6274.25  451.41-6122.02  443.04-5620.28  454.09-4484.32  455.33-3524.62  449.39
-3257.47  433.99-1232.55     437 -1157.6     419 -475.39     419 -386.67  437.25
 -100.94  435.18       0  453.09  217.27  437.18  619.02   443.4  722.45  420.23
  834.55  409.25   881.6  414.21   901.2  433.55  951.17  443.81 2315.84  437.06
 2448.75  449.53 2529.41  435.11 2771.33  439.73  2814.1  449.92 3104.94  462.45
#Mann= 7 ,-1,0
-8582.55    .075       0-1232.55    .055       0-386.669    .075       0
       0    .075       0619.0205     .06       0774.0596     .05       0
951.1699    .075       0
#XS Ineff= 1 ,-1
-1286.31-387.849   437.5
Permanent Ineff=
       T
Bank Sta=619.02,951.17
XS Rating Curve= 0 ,0
Exp/Cntr=0.3,0.1

Type RM Length L Ch R = 1 ,55646   ,153.25,149.49,141.97
BEGIN DESCRIPTION:
Proposed Pond
END DESCRIPTION:
XS GIS Cut Line= 6
  2427584.284964 6978127.7471595 2424558.0052562 6970125.7418381
 2422646.5468088 6970219.4916506 2421959.4179337 6969627.4390289
 2421937.2011146 6969616.9200211 2421613.1450042 6969467.1161868
#Sta/Elev= 30
-8555.16  463.28-8025.29  446.66-7813.25  452.52-7757.13   441.2-7555.34  432.81
-7295.39  451.14-5874.27  443.84-5112.72  455.18-3572.24  451.21-3084.46  433.42
-1269.71  445.37-1244.02  438.93-1137.11     419  -470.7     419 -389.77  438.37
       0  440.31  143.37  452.52  281.12   435.9  806.69  440.44  889.22  420.41
  986.07     420  997.09   411.4  1045.5  409.17 1080.44  414.78 1118.42  435.52
 1199.95  443.19  2446.6  435.77 2504.94  450.91 2635.46  434.95 3202.36  461.82
#Mann= 7 ,-1,0
-8555.16    .075       0-1244.02    .055       0 -389.77    .075       0
       0    .075       0806.6904     .06       0986.0703     .05       0
 1118.42    .075       0
#XS Ineff= 1 ,-1
-1265.41-376.069     436
Permanent Ineff=
       T
Bank Sta=806.69,1118.42
XS Rating Curve= 0 ,0
Exp/Cntr=0.3,0.1

Type RM Length L Ch R = 1 ,55496   ,133.85,137.36,135.3
BEGIN DESCRIPTION:
Proposed Pond
END DESCRIPTION:
XS GIS Cut Line= 5
  2427649.389165 6978106.0457593 2424615.2968083 6969964.2834996
 2422612.6925458 6970086.6792522 2421960.7827604 6969625.3077996
 2421617.9009002 6969464.7172415
#Sta/Elev= 30
-8688.73  464.49-8103.36  445.61-7873.99  453.79-7690.19  432.97-7359.58  451.26
-5825.61   442.4-5007.58   455.3-3381.99  448.48 -3045.5  432.87-1720.41  433.13
 -1636.5  442.58-1539.19  432.41-1359.62     419 -631.16     419  -559.7  436.97
       0  440.02  128.21   450.1   477.8  435.21  813.31  440.02  906.95  420.66
 1084.44     420 1149.07   409.1 1178.71  413.96 1201.99  431.11 1243.47  435.28
 1324.57  443.93 2444.08  435.05 2556.62  447.46 2633.87  435.19 3183.62  461.26
#Mann= 7 ,-1,0
-8688.73    .075       0-1539.19    .055       0  -559.7    .075       0
       0    .075       0813.3096     .06       01084.439     .05       0
 1243.47    .075       0
#XS Ineff= 1 ,-1
-1638.23 -461.53     434
Permanent Ineff=
       T
Bank Sta=813.31,1243.47
XS Rating Curve= 0 ,0
Exp/Cntr=0.3,0.1

Type RM Length L Ch R = 1 ,55359   ,128.66,114.69,113.46
BEGIN DESCRIPTION:
Proposed Pond
END DESCRIPTION:
XS GIS Cut Line= 4
  2427710.652494 6978024.7135729 2424662.1717146 6969828.8667757
  2422636.130163 6969953.8665257 2421619.2745851 6969456.0797916
#Sta/Elev= 30
-8744.43  464.65-8224.79   440.2 -7894.4  453.36-7703.92  432.79-7153.52   455.7
-6474.95  449.96 -6426.4   442.7 -3977.3  452.61-3421.74  445.59-3312.13  432.43
-3009.65  439.88-1702.99  436.67 -1639.1     419 -673.99     419 -397.23  435.73
       0  440.34  149.67  448.55   600.7  428.76  700.02  441.03  812.29  439.88
  900.78  421.12 1142.86     420 1243.16  409.04 1282.38  413.64 1328.27  435.95
 1974.41  442.59 2409.91   434.1 2514.76  446.46 2625.11  435.16 3162.05  461.25
#Mann= 7 ,-1,0
-8744.43    .075       0-1702.99    .055       0 -397.23    .075       0
       0    .075       0  812.29     .06       0 1142.86     .05       0
 1328.27    .075       0
#XS Ineff= 1 ,-1
-1754.49    -289     432
Permanent Ineff=
       T
Bank Sta=812.29,1328.27
XS Rating Curve= 0 ,0
Exp/Cntr=0.3,0.1

Type RM Length L Ch R = 1 ,55245   ,138,145,150
BEGIN DESCRIPTION:
Proposed Pond
END DESCRIPTION:
XS GIS Cut Line= 5
  2427781.595593 6978029.4996526 2427000.3455159 6975828.9787912
 2424763.7341755  6969711.679346 2422706.4426864 6969839.2834215
 2421610.4635791 6969445.5673454
#Sta/Elev= 30
-8848.43  465.81-8294.24  440.97-7887.47  453.24-7681.49  432.56-7393.82  438.38
-7272.15  457.72-6543.78  442.16-5757.58  451.25-5660.99  438.06-5080.85  452.77
-4891.05  437.58-3817.83  450.44-3203.83  433.27 -1828.3  438.87-1724.73  418.99
-1115.07     419-1041.45  436.79 -930.39  435.69 -861.79     419 -636.83     419
 -561.93  439.44       0  435.42  984.98   440.2 1320.01     420 1383.64     409
 1471.67  437.15 2339.09  432.57 2631.93  448.59 2691.65  434.43  3225.8   462.1
#Mann= 9 ,-1,0
-8848.43    .075       0 -1828.3    .055       0-1041.45    .075       0
 -930.39    .055       0-561.929    .075       0       0    .075       0
984.9805     .06       0 1320.01     .05       0 1471.67    .085       0
#XS Ineff= 1 ,-1
-2050.81 -246.23     430
Permanent Ineff=
       T
Bank Sta=984.98,1471.67
XS Rating Curve= 0 ,0
Exp/Cntr=0.3,0.1

Type RM Length L Ch R = 1 ,55099   ,179,178.4,181.81
BEGIN DESCRIPTION:
Proposed Pond
END DESCRIPTION:
XS GIS Cut Line= 5
  2427846.699466 6978016.4790093 2425151.3869435 6970060.7498421
 2424808.0050843 6969550.2210075 2422688.2133921  6969706.470695
 2421607.8293981 6969442.0831004
#Sta/Elev= 30
-9015.15  467.39-8458.27  439.35-7967.69  452.73-7680.03  432.65-7385.74   452.9
-6777.58  452.36-6740.71  442.12-3638.43  450.29-3616.35  436.67-3565.36   434.5
-1870.15     437-1764.39     419-1359.66     419-1281.25  436.94 -870.05  440.74
 -775.43  427.57 -388.11  439.91  -80.02  434.71       0  445.21  501.74  428.76
  617.18  441.07 1204.37  442.79  1319.2  420.27 1401.09     420 1470.91   408.9
 1568.11  432.97 1669.16  442.98 2193.34  430.45 2710.36  434.82 3044.34  451.85
#Mann= 7 ,-1,0
-9015.15    .075       0-1870.15    .055       0-1281.25    .075       0
       0    .075       0 1204.37     .06       0 1401.09     .05       0
 1568.11    .085       0
#XS Ineff= 1 ,-1
-1936.27-1094.96     426
Permanent Ineff=
       T
Bank Sta=1204.37,1568.11
XS Rating Curve= 0 ,0
Exp/Cntr=0.3,0.1