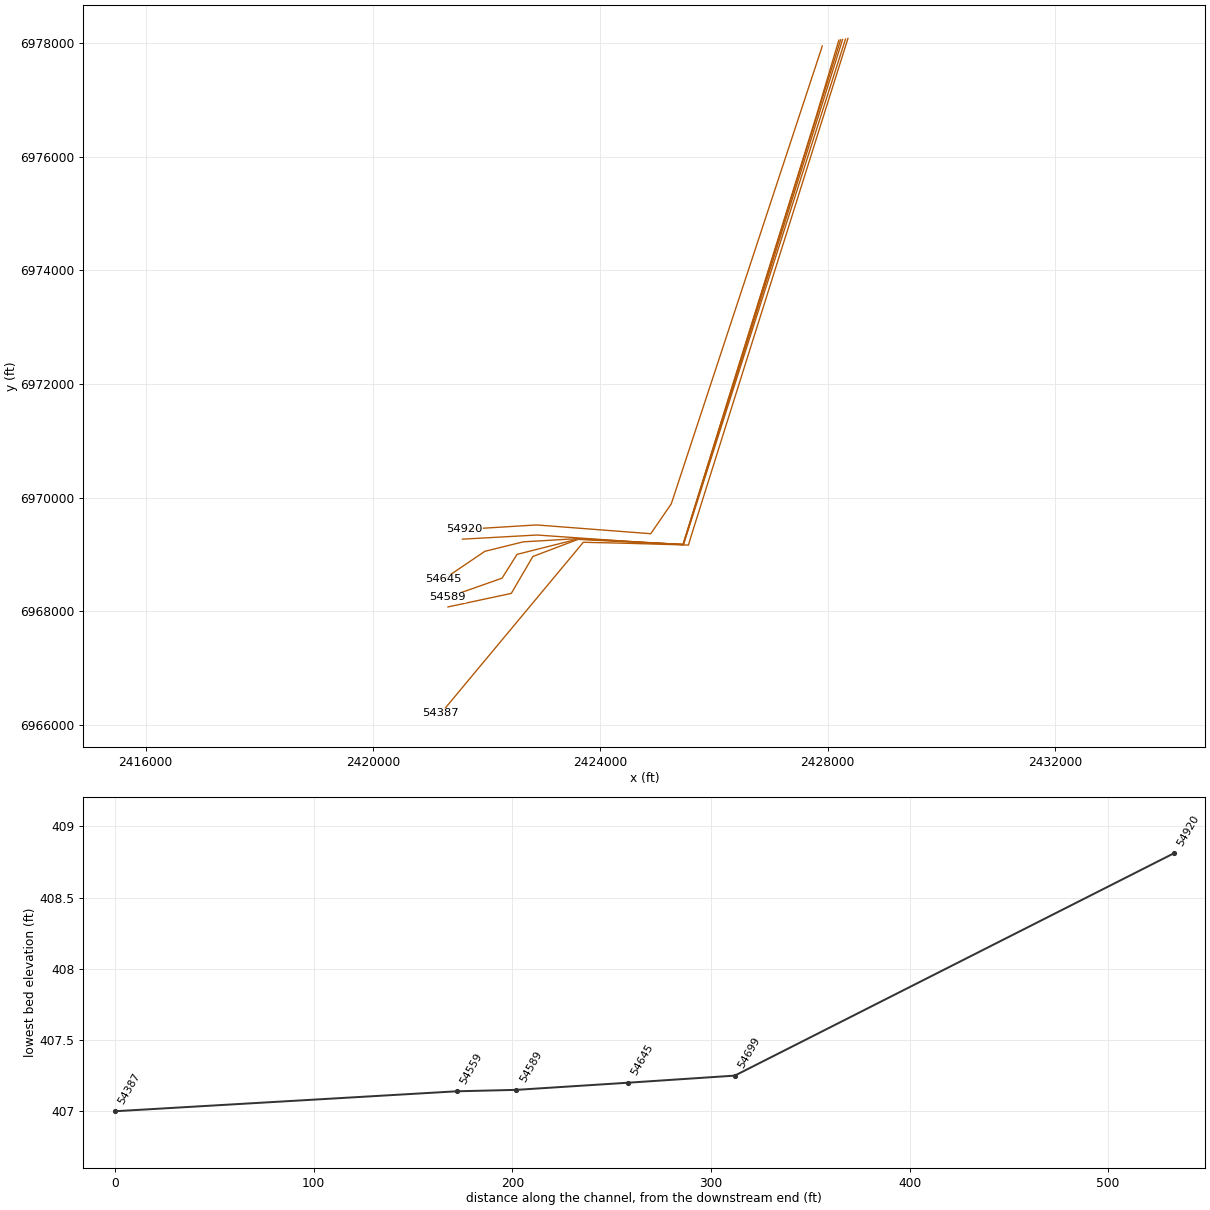
HEC-RAS study CDC_Consolidated_Model.prj: Upper Trinity CDC Consolidated Model

--- CDC_Consolidated_Model.g13 (geometry) --- (continued)

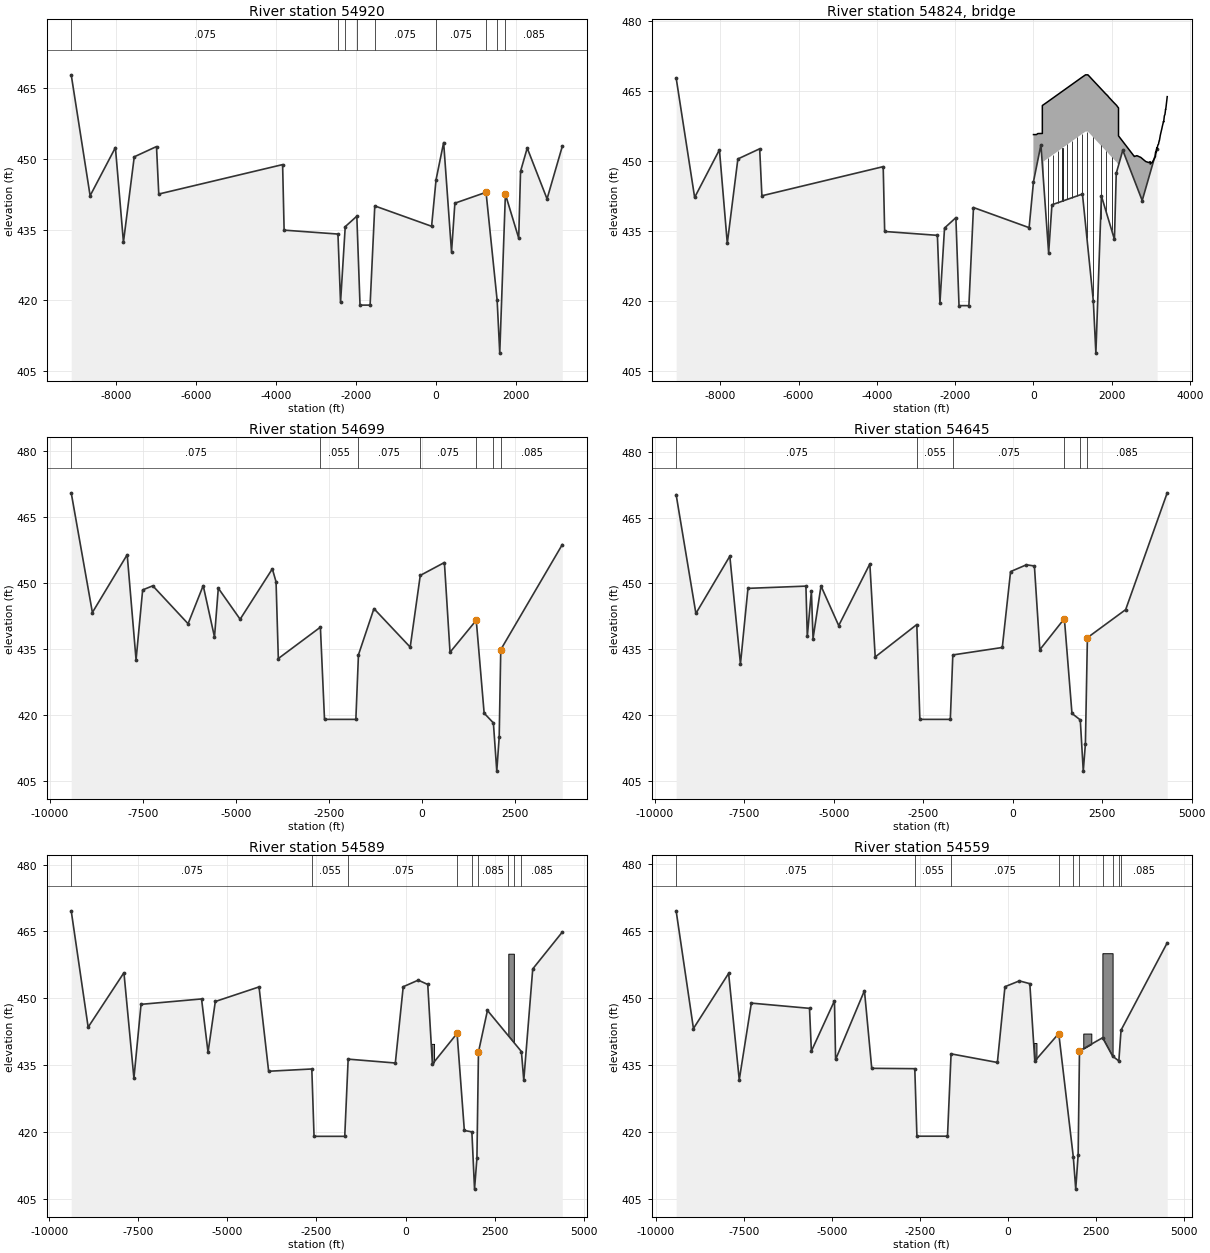
Type RM Length L Ch R = 1 ,54920   ,744,221,186.29
BEGIN DESCRIPTION:
Proposed Pond
END DESCRIPTION:
XS GIS Cut Line= 6
  2427904.781043 6977949.3351147 2427887.1731386 6977892.6387058
 2425248.4661456 6969888.3574703 2424887.4855684 6969362.9369332
 2422879.5338756 6969517.3972542 2421605.1929204 6969439.2658488
#Sta/Elev= 30
-9124.48  467.87-8651.94  442.21-8019.18  452.44-7818.42  432.36-7548.23  450.47
-6991.66  452.65-6934.98  442.57 -3837.6  448.82-3800.12  434.91-2453.77  434.08
-2388.98  419.56-2271.53  435.65-1981.93  437.87-1901.71     419-1649.79     419
-1532.67  440.05 -111.88  435.73       0  445.62  189.55   453.5  386.78  430.27
  470.59  440.63 1249.83  442.94 1527.57     420 1592.69  408.81 1734.02  442.53
 2066.71  433.21 2112.88  447.39 2279.81  452.33  2775.6  441.54 3156.88  452.69
#Mann= 9 ,-1,0
-9124.48    .075       0-2453.77    .055       0-2271.53    .075       0
-1981.93    .055       0-1532.67    .075       0       0    .075       0
 1249.83     .06       0 1527.57     .05       0 1734.02    .085       0
#XS Ineff= 1 ,-1
-2565.67-1484.11     425
Permanent Ineff=
       T
Bank Sta=1249.83,1734.02
XS Rating Curve= 0 ,0
Exp/Cntr=0.5,0.3

Type RM Length L Ch R = 3 ,54824   ,,,
BEGIN DESCRIPTION:
Wildlife Parkway
END DESCRIPTION:
Bridge Culvert--1,0,-1,-1, 0
Deck Dist Width WeirC Skew NumUp NumDn MinLoCord MaxHiCord MaxSubmerge Is_Ogee
75,110,2.6,0, 101, 101, , , 0.98, 0, 0,0,,
       0   74.93   94.67   99.74  107.56  113.26  225.72  225.82  260.82  328.82
  428.82  528.82  628.82  728.82  828.82  928.82 1028.82 1128.82 1228.82 1328.82
 1385.82 1388.82 1428.82 1528.82 1628.82 1728.82 1828.82 1882.82 1885.82 1928.82
 2028.82 2128.82 2135.82 2170.82 2170.92 2574.26 2595.02 2613.58 2616.38 2639.85
 2649.34 2672.32  2699.4 2717.22 2739.64 2753.26 2785.01 2804.42 2816.27 2827.44
 2834.86 2851.88 2864.52 2869.76 2892.11 2918.49  2939.5 2953.17 2975.01 2980.23
 2980.96 2990.29 3039.45 3101.35 3114.35 3114.64 3116.78 3124.49 3128.37 3135.11
 3146.62 3152.33 3154.73  3157.6 3164.61 3175.04 3176.29 3193.31 3198.81 3210.77
 3214.74 3233.11 3237.82 3266.96 3276.01 3276.73 3287.45 3307.18 3310.12 3315.94
  3319.4 3322.99 3338.21 3342.79 3356.48 3372.15 3372.91 3381.49 3387.14 3403.73
 3414.22
   455.7   455.7  455.82  455.84   455.9  455.92  455.94  461.94  462.14  462.54
  463.14  463.74  464.34  464.94  465.54  466.14  466.74  467.34  467.94  468.52
  468.52  468.52  468.17  467.26  466.37  465.47  464.57  464.12  464.12  463.67
  462.76   461.9  461.78  461.42  455.42     451  451.05  451.11  451.11  451.18
  451.14  451.06  450.95  450.89   450.8  450.71  450.48  450.35  450.26  450.19
  450.13  450.02  449.93  449.91  449.85  449.76   449.7  449.75  449.84  449.88
  449.38  449.45  449.84  450.81  451.01   451.8  451.93  451.85  451.87  452.24
   452.5  452.72  452.87  452.79  453.06  453.41  453.47  453.67  453.99   454.4
  454.41  455.31  455.55  456.62   456.9  456.95  457.39  458.08   458.2  458.39
  458.54  458.37  459.51  459.77  460.01  461.11  461.07  461.44  461.88  463.03
  463.84
                                                                  449.96  450.36
  450.96  451.56  452.16  452.76  453.36  453.96  454.56  455.16  455.76  456.34
  456.34  456.34  455.99  455.08  454.19  453.29  452.39  451.94  451.94  451.49
  450.58  449.72   449.6
     -90  -48.78   -42.8  -33.11   15.53   22.92   38.04   53.23   85.51   94.27
  127.63  133.79  193.16  205.67  242.45   253.9  272.74  291.62  307.54  364.52
  386.75  406.49  411.56  419.38  425.08  628.76  628.86  663.86  731.86  831.86
  931.86 1031.86 1131.86 1231.86 1331.86 1431.86 1531.86 1631.86 1731.86 1788.86
 1791.86 1831.86 1931.86 2031.86 2131.86 2231.86 2285.86 2288.86 2331.86 2431.86
 2531.86 2538.86 2573.86 2573.96 2793.08 2813.84  2832.4  2835.2 2858.67 2868.16
 2891.14 2918.22 2936.04 2958.46 2972.08 3003.83 3023.24 3035.09 3046.26 3053.68
  3070.7 3083.34 3088.58 3110.93 3137.31 3158.32 3171.99 3193.83 3199.05 3199.78
 3209.11 3258.27 3320.17 3333.17 3333.46  3335.6 3343.31 3347.19 3353.93 3365.44
 3371.15 3373.55 3376.42 3383.43 3393.86 3395.11 3412.13 3417.63 3429.59 3433.56
 3686.45
  450.78  451.17  451.23  451.36  451.98  452.61  452.76  452.92  453.22  453.31
  453.68  453.74  454.38   454.5  454.84  454.94  455.05  455.15  455.25  455.61
   455.7  455.82  455.84   455.9  455.92  455.94  461.94  462.14  462.54  463.14
  463.74  464.34  464.94  465.54  466.14  466.74  467.34  467.94  468.52  468.52
  468.52  468.17  467.26  466.37  465.47  464.57  464.12  464.12  463.67  462.76
   461.9  461.78  461.42  455.42     451  451.05  451.11  451.11  451.18  451.14
  451.06  450.95  450.89   450.8  450.71  450.48  450.35  450.26  450.19  450.13
  450.02  449.93  449.91  449.85  449.76   449.7  449.75  449.84  449.88  449.38
  449.45  449.84  450.81  451.01   451.8  451.93  451.85  451.87  452.24   452.5
  452.72  452.87  452.79  453.06  453.41  453.47  453.67  453.99   454.4  454.41
  458.58
                                                          449.96  450.36  450.96
  451.56  452.16  452.76  453.36  453.96  454.56  455.16  455.76  456.34  456.34
  456.34  455.99  455.08  454.19  453.29  452.39  451.94  451.94  451.49  450.58
  449.72   449.6
Pier Skew, UpSta & Num, DnSta & Num=  ,365, 2 ,768, 2 , 0 , 0 , 0 ,,
       3       3
     405     460
       3       3
     405     460
Pier Skew, UpSta & Num, DnSta & Num=  ,490, 2 ,893, 2 , 0 , 0 , 0 ,,
       3       3
     405     460
       3       3
     405     460
Pier Skew, UpSta & Num, DnSta & Num=  ,615, 2 ,1018, 2 , 0 , 0 , 0 ,,
       3       3
     405     460
       3       3
     405     460
Pier Skew, UpSta & Num, DnSta & Num=  ,740, 2 ,11433.41, 2 , 0 , 0 , 0 ,,
       3       3
     405     460
       3       3
     405     460
Pier Skew, UpSta & Num, DnSta & Num=  ,865, 2 ,1268, 2 , 0 , 0 , 0 ,,
       3       3
     405     460
       3       3
     405     460
Pier Skew, UpSta & Num, DnSta & Num=  ,990, 2 ,1393, 2 , 0 , 0 , 0 ,,
       3       3
     405     460
       3       3
     405     460
Pier Skew, UpSta & Num, DnSta & Num=  ,1115, 2 ,1518, 2 , 0 , 0 , 0 ,,
       3       3
     405     460
       3       3
     405     460
Pier Skew, UpSta & Num, DnSta & Num=  ,1240, 2 ,1643, 2 , 0 , 0 , 0 ,,
       3       3
     405     460
       3       3
     405     460
Pier Skew, UpSta & Num, DnSta & Num=  ,1365, 2 ,1768, 2 , 0 , 0 , 0 ,,
       3       3
     405     460
       3       3
     405     460
Pier Skew, UpSta & Num, DnSta & Num=  ,1514, 2 ,1917, 2 , 0 , 0 , 0 ,,
       3       3
     405     460
       3       3
     405     460
Pier Skew, UpSta & Num, DnSta & Num=  ,1713, 2 ,2116, 2 , 0 , 0 , 0 ,,
       3       3
     405     460
       3       3
     405     460
Pier Skew, UpSta & Num, DnSta & Num=  ,1860, 2 ,2263, 2 , 0 , 0 , 0 ,,
       3       3
     405     460
       3       3
     405     460
Pier Skew, UpSta & Num, DnSta & Num=  ,1995, 2 ,2398, 2 , 0 , 0 , 0 ,,
       3       3
     405     460
       3       3
     405     460
BR Coef=-1 , 0 , 0 ,, 0 ,,,0.8,-1,,0,
WSPro=,,,, 1 ,,,, 0 ,,,, 0 ,,,,-1 ,-1 ,-1 , 0 , 0 , 0 , 0 , 0
BC Design=,, 0 ,, 0 ,,,,,,
BC Use User HTab Curves=0
BC User HTab FreeFlow(D)= 0

Type RM Length L Ch R = 1 ,54699   ,12,54,110.52
BEGIN DESCRIPTION:
Proposed Pond
END DESCRIPTION:
XS GIS Cut Line= 6
  2428196.427113 6978051.7781513 2427794.0762119 6976697.0190498
  2425455.411926 6969174.3648038 2424813.2655725 6969204.8880367
 2422885.0971847 6969339.9858636 2421575.5669954 6969267.2579907
#Sta/Elev= 30
-9420.11  470.43-8851.92  443.26-7917.65  456.39-7679.49  432.52-7502.59  448.39
-7230.48  449.32-6283.23  440.71-5877.34  449.37-5574.33  437.69-5472.08  448.78
-4886.21  441.73-4021.68  453.17-3921.93  450.23-3860.97  432.81-2731.54  439.93
-2621.23     419 -1779.8     419-1710.12  433.65-1294.42  444.14 -320.96   435.4
     -51  451.68     597  454.61   747.9  434.23 1452.09   441.5 1663.67  420.41
 1912.01  418.19 2002.94  407.25 2067.95  415.02 2109.78  434.83 3761.42  458.68
#Mann= 7 ,-1,0
-9420.11    .075       0-2731.54    .055       0-1710.12    .075       0
     -51    .075       0 1452.09     .06       0 1912.01     .05       0
 2109.78    .085       0
#XS Ineff= 1 ,-1
-2920.11-1220.11     428
Permanent Ineff=
       T
Bank Sta=1452.09,2109.78
XS Rating Curve= 0 ,0
Exp/Cntr=0.5,0.3

Type RM Length L Ch R = 1 ,54645   ,15,56,171.74
BEGIN DESCRIPTION:
Proposed Pond
END DESCRIPTION:
XS GIS Cut Line= 6
  2428227.677378 6978056.9864742 2425457.0592324 6969173.5816689
 2423612.4182366 6969277.3481937 2422644.2843461 6969219.8155003
 2421968.3759211  6969052.834207 2421237.9088781 6968557.6130846
#Sta/Elev= 30
   -9400  470.23-8848.21  443.15 -7900.6  456.21-7603.53  431.63-7393.94  448.87
-5774.78  449.38-5736.54   437.9-5621.97  448.25-5575.92  437.43-5353.57  449.41
-4859.02  440.38-3989.22  454.45-3839.85  433.23-2677.62  440.62   -2592     419
-1741.35     419-1671.38  433.69 -289.98  435.39  -58.46  452.69  383.61  454.24
   607.3  453.97  758.68  434.88 1444.35  441.97 1656.53  420.35 1888.79  418.88
 1972.17   407.2 2031.72  413.42 2087.81  437.62 3156.18  444.02    4317  470.65
#Mann= 6 ,-1,0
   -9400    .075       0-2677.62    .055       0-1671.38    .075       0
 1444.35     .06       0 1888.79     .05       02087.811    .085       0
#XS Ineff= 1 ,-1
   -2900   -1200     428
Permanent Ineff=
       T
Bank Sta=1444.35,2087.81
XS Rating Curve= 0 ,0
Exp/Cntr=0.3,0.1

Type RM Length L Ch R = 1 ,54589   ,15,30,101.47
BEGIN DESCRIPTION:
Proposed Pond
END DESCRIPTION:
XS GIS Cut Line= 6
  2428261.531313 6978062.1947971 2425459.8476126 6969172.1531941
 2423612.7984852 6969271.1746496 2422535.2510996  6968999.279196
  2422270.863177 6968579.8118591 2421309.0065049  6968241.209846
#Sta/Elev= 30
-9385.69  469.62-8910.23   443.5-7905.75  455.73-7625.35  432.05-7425.26  448.63
-5726.98  449.84-5544.58  437.86-5340.26  449.27-4112.81  452.54-3843.61  433.61
-2631.43  434.12-2568.74     419-1706.89     419-1611.23  436.33 -286.81  435.46
   -65.5  452.58  356.05  454.06  623.41  453.09   753.5  435.21 1446.95  442.11
 1650.73  420.32  1862.2     420 1936.68  407.15 2003.75  414.08  2046.9  437.91
 2299.38  447.26 3252.61  438.03 3319.15  431.56  3570.6  456.58 4400.36  464.85
#Mann= 9 ,-1,0
-9385.69    .075       0-2631.43    .055       0-1611.23    .075       0
 1446.95     .06       0  1862.2     .05       0  2046.9    .085       0
2884.729      .1       03040.021    .045       0 3252.61    .085       0
#XS Ineff= 1 ,-1
-2885.69-1185.69     428
Permanent Ineff=
       T
#Block Obstruct= 2 ,-1
651.4795800.8301  439.762884.7293040.021     460
Bank Sta=1446.95,2046.9
XS Rating Curve= 0 ,0
Exp/Cntr=0.3,0.1

Type RM Length L Ch R = 1 ,54559   ,140,172,476.66
BEGIN DESCRIPTION:
Proposed Pond
END DESCRIPTION:
XS GIS Cut Line= 6
  2428313.397679 6978069.5733913 2425462.0500361 6969169.9360069
 2423607.6390467 6969263.4082609 2422813.0979849 6968961.7389167
 2422433.5741376 6968312.1562264 2421320.3066791 6968074.3351797
#Sta/Elev= 30
-9424.04   469.5-8932.62  443.13-7933.53  455.48 -7631.8  431.63-7287.69  448.82
 -5636.6  447.65-5583.73  438.06-4927.71  449.34-4895.71  436.19-4076.61  451.61
-3869.67  434.21-2646.68  434.13 -2586.2     419 -1717.8     419-1616.08  437.45
 -301.22  435.52  -86.06   452.5  322.56   453.8  619.93  453.18  761.43  435.83
 1442.05  442.01 1855.74   414.3 1923.75  407.14 1992.75  414.84 2030.66  438.11
 2686.61  441.06 2970.46  436.94 3148.43  435.86 3210.62  442.76 4521.87  462.33
#Mann= 10 ,-1,0
-9424.04    .075       0-2646.68    .055       0-1616.08    .075       0
 1442.05     .06       0 1855.74     .05       0 2030.66    .085       0
 2686.61      .1       0 2970.46    .045       0 3148.43    .065       0
 3210.62    .085       0
#XS Ineff= 1 ,-1
-2924.04-1224.04     428
Permanent Ineff=
       T
#Block Obstruct= 3 ,-1
652.4102808.6904  439.88 2138.14 2366.59     442 2681.25 2970.46     460
Bank Sta=1442.05,2030.66
XS Rating Curve= 0 ,0
Exp/Cntr=0.3,0.1

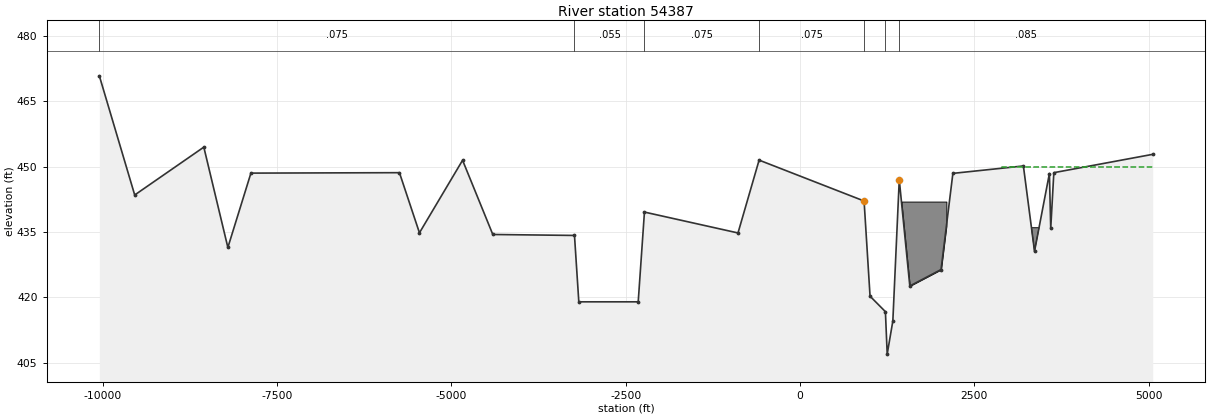
Type RM Length L Ch R = 1 ,54387   ,650,657,656
BEGIN DESCRIPTION:
Proposed Pond
END DESCRIPTION:
XS GIS Cut Line= 6
  2428357.292277 6978083.5648332 2425588.1363981 6969290.3153593
 2425551.2713143 6969163.0360863 2424511.6149291 6969193.4940306
 2423701.0840698 6969212.1413031 2421194.7491875 6966200.3034947
#Sta/Elev= 30
  -10051  470.85-9543.68  443.51-8552.43  454.49-8207.42  431.47-7876.83  448.53
-5746.63  448.63-5459.63  434.83-4841.06  451.48-4407.45  434.45-3235.95  434.23
-3173.87     419 -2321.9     419-2232.52  439.59 -890.69   434.8    -588  451.51
  917.75  442.13 1003.34  420.29 1223.66  416.74 1249.34     407 1330.23   414.6
 1422.27  447.02 1573.77  422.63 2021.75   426.4  2191.4  448.47 3202.75  450.17
 3362.45  430.61 3575.81  448.44 3594.98  435.87 3639.38  448.63 5058.02  452.84
#Mann= 7 ,-1,0
  -10051    .075       0-3235.95    .055       0-2232.52    .075       0
    -588    .075       0  917.75     .06       0 1223.66     .05       0
 1422.27    .085       0
#XS Ineff= 2 ,-1
   -3551   -2051  428.75    2900 5058.02     450
Permanent Ineff=
       T       F
#Block Obstruct= 3 ,-1
     271     534     440    1457    2098     442    3289    3631     436
Bank Sta=917.75,1422.27
XS Rating Curve= 0 ,0
Exp/Cntr=0.3,0.1