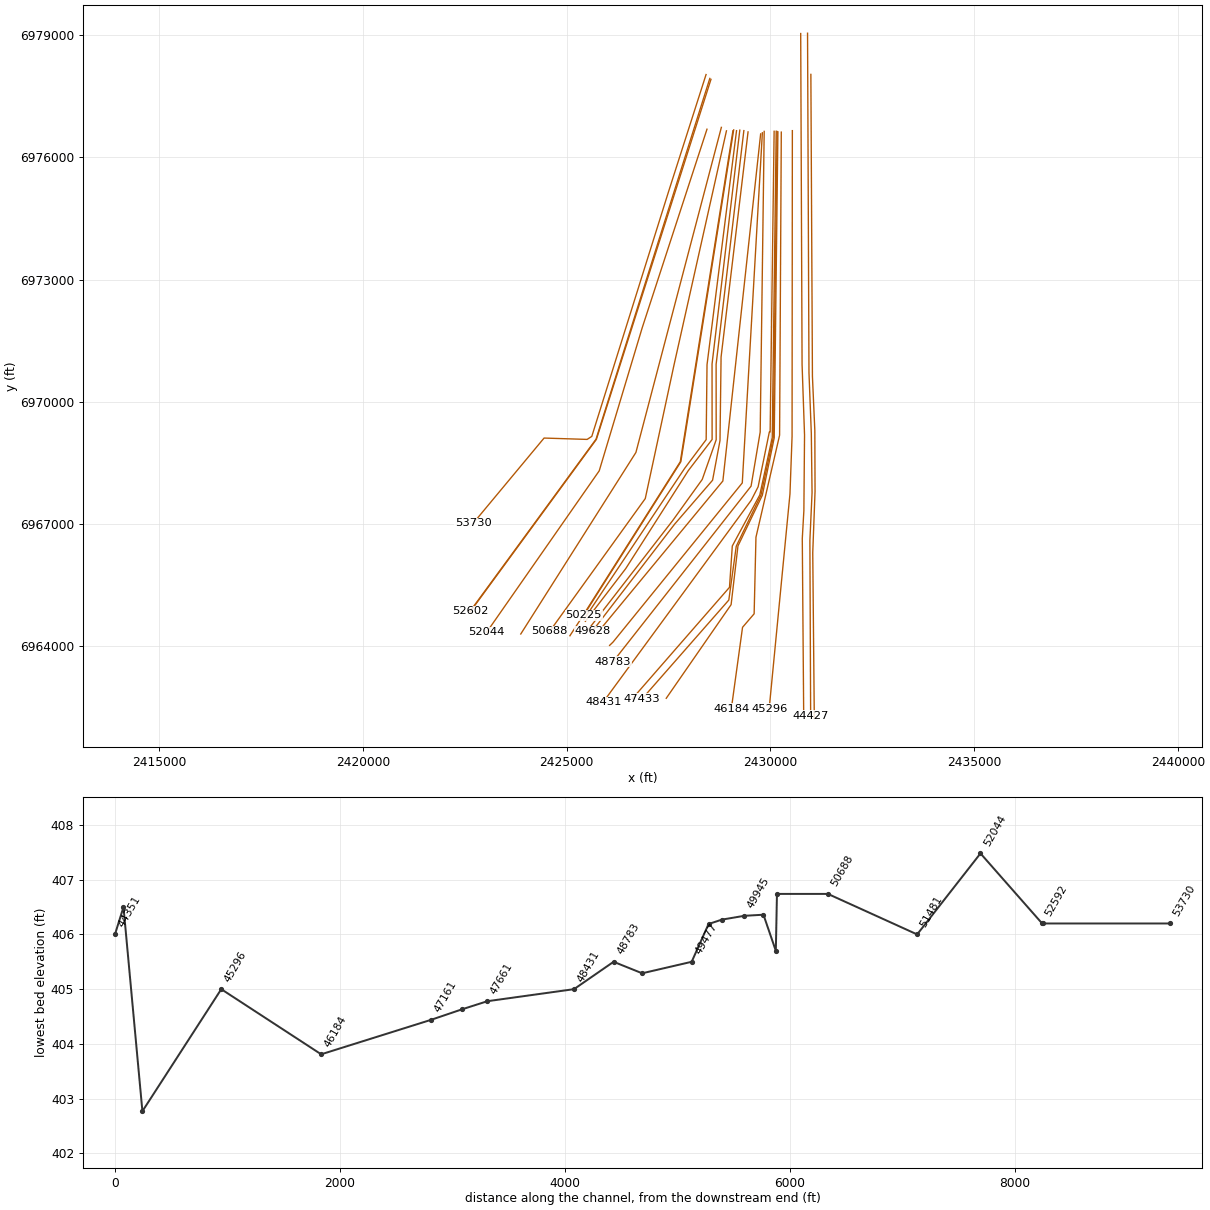
HEC-RAS study CDC_Consolidated_Model.prj: Upper Trinity CDC Consolidated Model

--- CDC_Consolidated_Model.g13 (geometry) --- (continued)

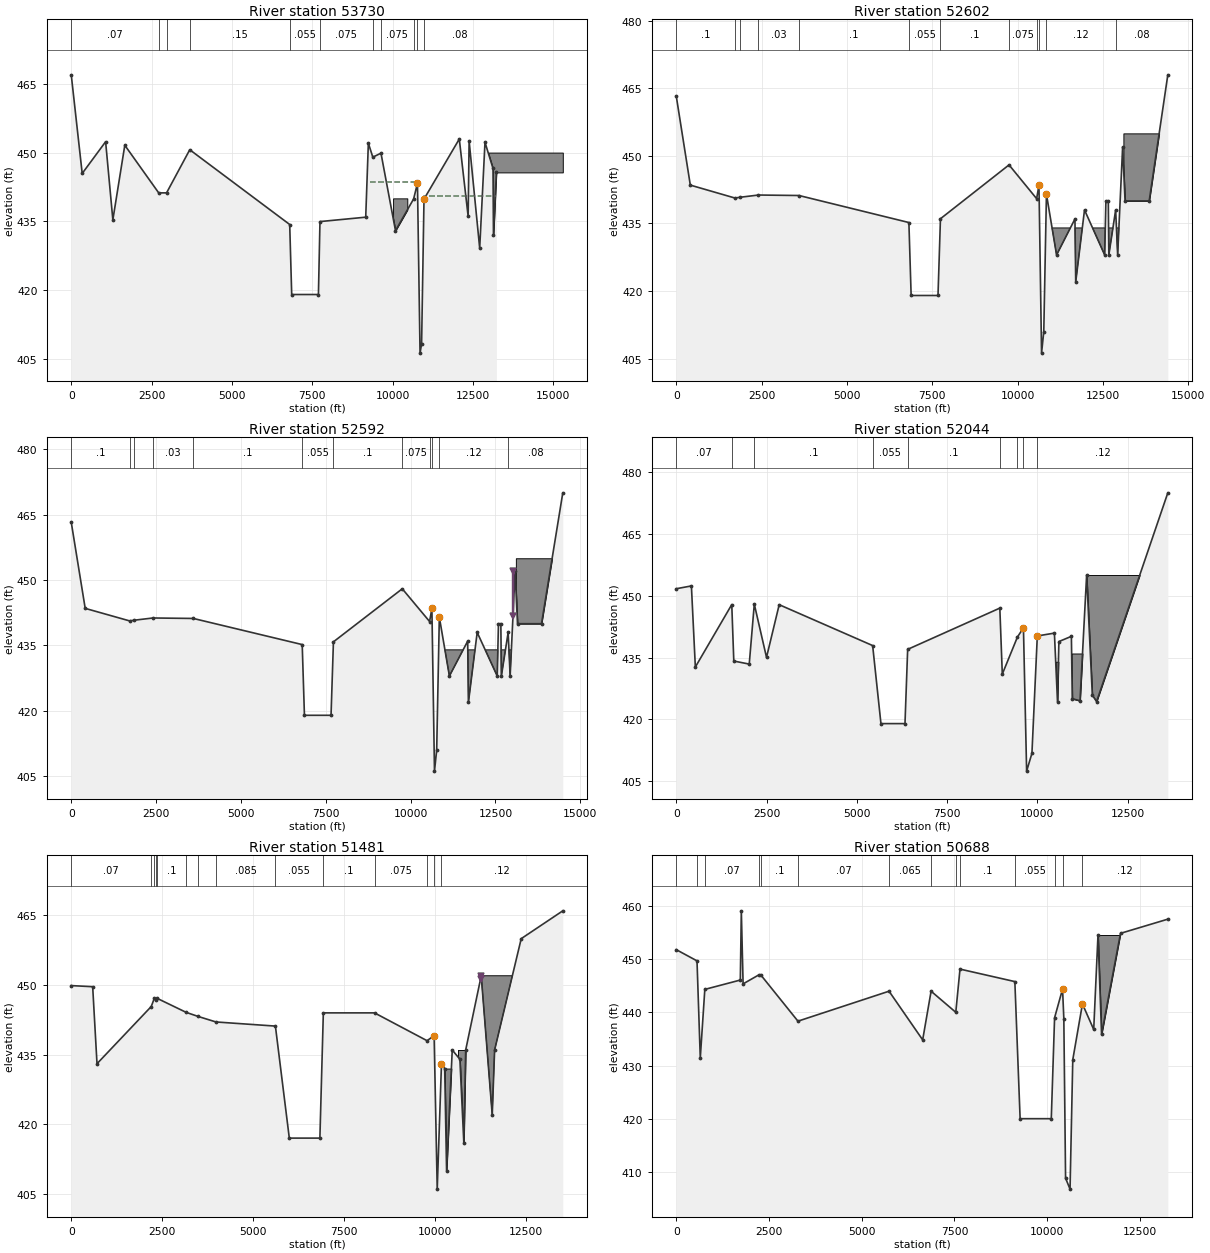
Type RM Length L Ch R = 1 ,53730   ,190,1128,1160
BEGIN DESCRIPTION:
Wildlife Phase 3 South and Proposed Pond
END DESCRIPTION:
XS GIS Cut Line= 6
  2428421.794772 6978032.9202494 2427505.1279709 6975171.8088456
 2425618.1816136 6969154.5383999 2425503.5053337 6969080.5890727
 2424447.2065933 6969113.73992512422703.874858246967018.20959677
#Sta/Elev= 30
       0  466.98  340.87  445.44 1069.55  452.37 1294.81  435.31 1666.57   451.6
2721.446   441.22966.387   441.2 3687.83  450.62 6797.99  434.29 6860.16     419
 7691.64     419 7739.76  434.93 9163.36  435.89 9245.29  452.05    9384     449
 9638.06  449.8710089.92  432.9410654.59  439.8910773.27  443.28   10854   406.2
10902.07  408.2210976.92  439.8412074.96  452.96 12350.3  436.0912380.95  452.54
12709.92  429.1312874.73  452.2513124.42  446.5313138.41  431.9913229.72  445.67
#Mann= 11 ,-1,0
       0     .07       02721.446     .03       02966.387     .07       0
 3687.83     .15       0 6797.99    .055       0 7739.76    .075       0
    9384      .1       0 9638.06    .075       010654.59     .12       0
10773.27     .05       010976.92     .08       0
#XS Ineff= 3 ,-1
    6500    8000   429.5 9286.6110773.27   443.5   1097913229.72   440.6
Permanent Ineff=
       T       F       F
#Block Obstruct= 2 ,-1
   1001510457.41     440   12874 15295.7     450
Bank Sta=10773.27,10976.92
XS Rating Curve= 0 ,0
Exp/Cntr=0.3,0.1

Type RM Length L Ch R = 1 ,52602   ,10,10,10
BEGIN DESCRIPTION:
Wildlife Phase 3 South, Wildlife Phase 3 North, and Proposed Pond
END DESCRIPTION:
XS GIS Cut Line= 4
  2428514.108892 6977938.0490481 2425753.1363961 6969184.3428022
 2425721.5921679 6969085.2242341 2422631.7436888 6964864.5955362
#Sta/Elev= 30
       0  463.26  411.38  443.51 1719.49  440.64 1857.49   440.82408.628 441.308
3597.362   441.2 6815.63   435.2 6881.51     419 7668.47     419 7740.49  436.04
 9749.81     44810558.67   440.5   10627   443.5   10703   406.2   10768     411
   10846   441.511142.78     428 11681.3     43611703.57     42211961.36     438
12552.09     42812587.85     44012658.46     44012674.16     42812873.75     438
12932.43     428 13078.3     45213149.25     440 13856.8     44014402.36     468
#Mann= 12 ,-1,0
       0      .1       0 1719.49    .065       0 1857.49      .1       0
2408.628     .03       03597.362      .1       0 6815.63    .055       0
 7740.49      .1       0 9749.81    .075       010558.67     .11       0
   10627     .05       0   10846     .12       012873.75     .08       0
#XS Ineff= 1 ,-1
    6400    8000     431
Permanent Ineff=
       T
#Block Obstruct= 2 ,-1
   11000   13070     434 13100.715041.12     455
Bank Sta=10627,10846
XS Rating Curve= 0 ,0
Exp/Cntr=0.3,0.1

Type RM Length L Ch R = 1 ,52592   ,534,548,597
BEGIN DESCRIPTION:
Wildlife Phase 3 South, Wildlife Phase 3 North, and Proposed Pond
GP 61422-1 Pollo Regio Warehouse
Cross-section 525292 - 53730
END DESCRIPTION:
XS GIS Cut Line= 4
  2428542.246959 6977915.3578205 2425762.6652485 6969181.3099999
 2425730.9602594 6969081.6851991 2422633.8985401 6964850.6598686
#Sta/Elev= 30
       0  463.26  411.38  443.51 1719.49  440.64 1857.49   440.82408.628 441.308
3597.362   441.2 6805.42  435.21 6871.23     419 7655.03     419  7725.5  435.84
 9753.81     44810558.67   440.5   10627   443.5   10703   406.2   10768     411
   10846   441.511142.78     428 11681.3     43611703.57     42211961.36     438
12552.09     42812587.85     44012658.46     44012674.16     42812873.75     438
12932.43     428 13078.3     45213149.25     440 13856.8     44014483.75     470
#Mann= 12 ,-1,0
       0      .1       0 1719.49    .065       0 1857.49      .1       0
2408.628     .03       03597.362      .1       0 6805.42    .055       0
  7725.5      .1       0 9753.81    .075       010558.67     .11       0
   10627     .05       0   10846     .12       012873.75     .08       0
Levee=0,,,-1,13016.2,452,,
#XS Ineff= 1 ,-1
    6400    8000     431
Permanent Ineff=
       T
#Block Obstruct= 2 ,-1
   11000   13070     434 13100.715103.12     455
Bank Sta=10627,10846
XS Rating Curve= 0 ,0
Exp/Cntr=0.3,0.1

Type RM Length L Ch R = 1 ,52044   ,536,563,623
BEGIN DESCRIPTION:
Wildlife Phase 3 South, Wildlife Phase 3 North, and Proposed Pond
END DESCRIPTION:
XS GIS Cut Line= 4
   2428444.27373 6976691.9773932   2426855.73196 6971822.1856237
 2425800.2350552 6968309.3835941  2423039.818332 6964351.0499754
#Sta/Elev= 30
       0   451.7   419.1  452.38  528.31  432.72 1537.27  447.86 1593.52  434.17
 2021.11  433.43  2161.2  447.96 2499.62  435.06 2850.97  447.83 5439.63  437.92
 5669.51     419 6335.49     419 6409.54     437 8962.47     447 9031.15     431
  9450.9     440 9616.73  442.22 9704.95  407.48 9851.93   411.810000.92  440.25
10474.42  440.9410560.14  424.3110598.62  438.8910944.88  440.1610969.28  425.04
 11183.9  424.5311367.29  455.0211524.82   425.911642.61  424.3413616.08  474.95
#Mann= 9 ,-1,0
       0     .07       0 1537.27    .065       0  2161.2      .1       0
 5439.63    .055       0 6409.54      .1       0 8962.47    .055       0
  9450.9    .075       0 9616.73    .055       010000.92     .12       0
#XS Ineff= 2 ,-1
    5200    6500     434    8800    9500     438
Permanent Ineff=
       T       T
#Block Obstruct= 3 ,-1
   10500   10600     434   10940   11350     43611367.29   13200  455.02
Bank Sta=9616.73,10000.92
XS Rating Curve= 0 ,0
Exp/Cntr=0.3,0.1

Type RM Length L Ch R = 1 ,51481   ,734,793,709
BEGIN DESCRIPTION:
Wildlife Phase 3 South and Wildlife Phase 3 North
END DESCRIPTION:
XS GIS Cut Line= 3
  2428797.284835 6976736.8588651 2426700.7079918 6968760.7140563
 2423875.4941541 6964306.2236215
#Sta/Elev= 30
       0  449.88  589.71  449.64  708.61  433.04 2200.56  445.37 2285.34  447.13
 2325.41  446.782371.287   447.13163.269 444.102 3493.95  443.22 3980.97  442.04
 5615.72  441.15 5998.25     417 6839.46     417 6934.35     444    8342     444
 9787.86     438    9982   439.1   10067     406   10184     43310272.72     432
10324.68     41010480.26     43610690.35     43410798.95     416 10850.2     436
11277.45     45211580.19     42211645.85     436 12377.7     46013520.99     466
#Mann= 14 ,-1,0
       0     .07       0 2200.56     .05       0 2285.34     .07       0
 2325.41      .1       02371.287      .1       03163.269     .07       0
 3493.95     .12       0 3980.97    .085       0 5615.72    .055       0
 6934.35      .1       0    8342    .075       0 9787.86     .09       0
    9982    .055       0   10184     .12       0
Levee=0,,,-1,11259.76,452,,
#XS Ineff= 1 ,-1
    5500    7200     439
Permanent Ineff=
       T
#Block Obstruct= 3 ,-1
10272.72   10550     43210637.55   10900     43611259.7613520.99     452
Bank Sta=9982,10184
XS Rating Curve= 0 ,0
Exp/Cntr=0.3,0.1

Type RM Length L Ch R = 1 ,50688   ,393,453,411
BEGIN DESCRIPTION:
Wildlife Phase 3 South and Wildlife Phase 3 North
END DESCRIPTION:
XS GIS Cut Line= 4
  2428922.215031 6976651.7773424 2427633.1526492 6970896.5690366
 2426930.0277431 6967628.3400087 2424586.2775094 6964373.1316242
#Sta/Elev= 30
       0  451.82   558.9  449.71  647.24  431.43  769.54  444.34 1726.54   446.1
 1753.79  459.13  1801.5  445.38 2228.45  447.082274.101   447.13280.432 438.359
 5735.98     444  6642.8  434.84 6869.93     444 7535.31  440.03 7649.05  448.16
 9127.99  445.81 9269.97     42010110.22     42010199.17     43910414.26  444.41
10448.36  438.8510495.47   408.810615.85  406.7410689.73   431.110949.96   441.6
11254.01  436.7911369.47  454.5811465.78  435.8911976.23  454.89   13252  457.56
#Mann= 14 ,-1,0
       0     .07       0   558.9    .065       0  769.54     .07       0
 2228.45      .1       02274.101      .1       03280.432     .07       0
 5735.98    .065       0 6869.93      .1       0 7535.31    .035       0
 7649.05      .1       0 9127.99    .055       010199.17     .09       0
10414.26     .05       010949.96     .12       0
#Block Obstruct= 1 ,-1
11369.47   12000  454.58
Bank Sta=10414.26,10949.96
XS Rating Curve= 0 ,0
Exp/Cntr=0.3,0.1

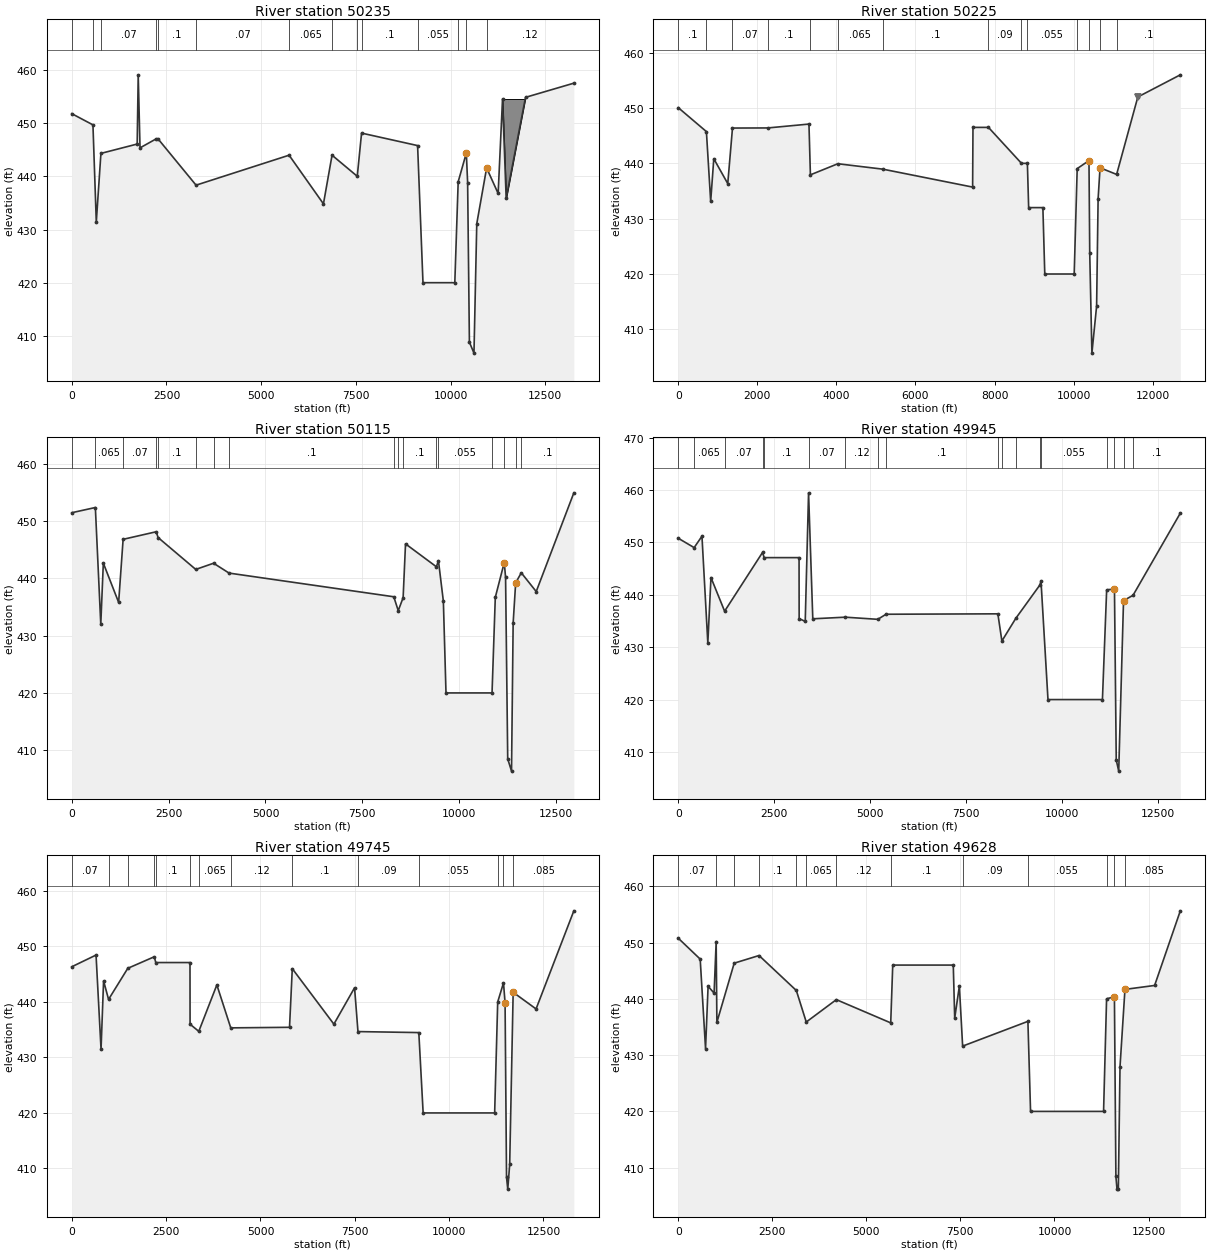
Type RM Length L Ch R = 1 ,50235   ,10,10,10
BEGIN DESCRIPTION:
Wildlife Phase 3 South
END DESCRIPTION:
XS GIS Cut Line= 5
  2429080.941092 6976653.0129042 2428983.4813134  6976040.091886
 2427789.9062727 6968533.7318987 2425336.6391976 6964655.9870296
 2425080.8109691 6964262.6502178
#Sta/Elev= 30
       0  451.82   558.9  449.71  647.24  431.43  769.54  444.34 1726.54   446.1
 1753.79  459.13  1801.5  445.38 2228.45  447.082274.101   447.13280.432 438.359
 5735.98     444  6642.8  434.84 6869.93     444 7535.31  440.03 7649.05  448.16
 9127.99  445.81 9269.97     42010110.22     42010199.17     43910414.26  444.41
10448.36  438.8510495.47   408.810615.85  406.7410689.73   431.110949.96   441.6
11254.01  436.7911369.47  454.5811465.78  435.8911976.23  454.89   13252  457.56
#Mann= 14 ,-1,0
       0     .07       0   558.9    .065       0  769.54     .07       0
 2228.45      .1       02274.101      .1       03280.432     .07       0
 5735.98    .065       0 6869.93      .1       0 7535.31    .035       0
 7649.05      .1       0 9127.99    .055       010199.17     .09       0
10414.26     .05       010949.96     .12       0
#Block Obstruct= 1 ,-1
11369.47   12000  454.58
Bank Sta=10414.26,10949.96
XS Rating Curve= 0 ,0
Exp/Cntr=0.3,0.1

Type RM Length L Ch R = 1 ,50225   ,126,110,80
BEGIN DESCRIPTION:
Wildlife Phase 3 South
END DESCRIPTION:
XS GIS Cut Line= 5
  2429099.073273 6976674.6388452 2427917.6986681 6969245.5001602
 2427802.2845288 6968531.20828172426479.543213656966440.42370765
2425421.684591536964768.32466355
#Sta/Elev= 30
       0  450.07  712.53  445.74  820.76  433.12   899.3  440.84 1252.62  436.34
 1372.33  446.38 2265.69   446.43306.666   447.13343.118 437.923  4037.1  439.93
 5175.31  438.95 7446.47  435.71 7455.54   446.5  7847.2   446.5 8682.73     440
  8831.7     440  8863.7     432  9223.7     432  9271.7     420 10015.7     420
 10091.7  439.05 10389.7   440.5 10408.7   423.8 10463.7   405.7 10582.7   414.2
 10620.7   433.6 10669.7   439.211089.03     43811625.44     45212699.94     456
#Mann= 14 ,-1,0
       0      .1       0  712.53    .065       0 1372.33     .07       0
 2265.69      .1       03343.118     .07       0  4037.1    .065       0
 5175.31      .1       0  7847.2     .09       0 8682.73    .085       0
  8831.7    .055       0 10091.7     .09       0 10389.7     .05       0
 10669.7     .04       011089.03      .1       0
Levee=0,,,-1,11625.44,452,,
#Block Obstruct= 2 , 0
                        12294.55             452
Bank Sta=10389.7,10669.7
XS Rating Curve= 0 ,0
Exp/Cntr=0.3,0.1

Type RM Length L Ch R = 1 ,50115   ,171,170,116
BEGIN DESCRIPTION:
Wildlife Phase 3 South
END DESCRIPTION:
XS GIS Cut Line= 6
   2429169.45207 6976655.9065992 2428445.4794366 6970912.8367206
 2428425.2101202 6969162.8799187 2428424.5690454 6969075.4978756
 2427897.0225283 6968370.8188387 2425423.1222924 6964661.0014552
#Sta/Elev= 30
       0  451.43  608.95  452.34  748.99  431.97  814.63  442.64 1210.06  435.79
 1325.63  446.79 2180.01  448.112228.747   447.1 3201.28  441.54 3660.93  442.62
 4061.23   440.9 8313.42  436.77 8428.68  434.35 8554.68  436.61  8616.4     446
 9414.06     442 9466.17  443.07  9593.5     436  9661.4     42010850.13     420
10934.29  436.6711165.42  442.7411199.54  440.1511254.92   408.5 11353.1  406.36
 11395.1  432.1911460.15   439.211605.28  440.9511990.82  437.6812962.14   454.9
#Mann= 17 ,-1,0
       0      .1       0  608.95    .065       0 1325.63     .07       0
 2180.01      .1       02228.747      .1       0 3201.28     .07       0
 3660.93    .065       0 4061.23      .1       0 8313.42    .035       0
 8428.68     .09       0 8554.68      .1       0 9414.06     .09       0
 9466.17    .055       010850.13     .09       011165.42     .05       0
11460.15     .04       011605.28      .1       0
Bank Sta=11165.42,11460.15
XS Rating Curve= 0 ,0
Exp/Cntr=0.3,0.1

Type RM Length L Ch R = 1 ,49945   ,243,200,176
BEGIN DESCRIPTION:
Wildlife Phase 3 South shown. XS 48783 - 49945 fill immediately west of Graff Buildings 1 and 2  in current effective no longer proposed.
END DESCRIPTION:
XS GIS Cut Line= 6
    2429249.8233 6976669.1798666 2428568.5654766 6970928.8862291
 2428570.3007093 6969078.7117799 2427985.7536501 6968314.5289251
 2426450.4053428 6965910.0668705 2425460.8295661 6964618.1196512
#Sta/Elev= 30
       0   450.8  414.14  449.01  617.85  451.19  770.55   430.8  852.62  443.29
 1207.82  436.87 2195.15  448.092238.117   447.13146.447   447.1  3148.9  435.46
 3307.19  434.92 3393.94  459.47 3504.16  435.42 4349.11  435.73 5196.94  435.32
 5411.11  436.29 8323.82  436.37 8428.53  431.18    8790   435.5 9414.61  441.84
 9447.55  442.57 9628.89     42011046.74     42011156.83  440.9411360.16  441.13
 11406.7  408.4711470.85  406.3411596.49   438.9 11843.1   439.913074.96  455.59
#Mann= 18 ,-1,0
       0      .1       0  414.14    .065       0 1207.82     .07       0
 2195.15      .1       02238.117      .1       0 3393.94     .07       0
 4349.11     .12       0 5196.94    .065       0 5411.11      .1       0
 8323.82    .035       0 8428.53     .09       0    8790      .1       0
 9414.61     .09       0 9447.55    .055       011156.83     .09       0
11360.16     .05       011596.49      .4       0 11843.1      .1       0
Bank Sta=11360.16,11596.49
XS Rating Curve= 0 ,0
Exp/Cntr=0.3,0.1

Type RM Length L Ch R = 1 ,49745   ,145,118,146
BEGIN DESCRIPTION:
Wildlife Phase 3 South shown. XS 48783 - 49945 fill immediately west of Graff Buildings 1 and 2  in current effective no longer proposed.
END DESCRIPTION:
XS GIS Cut Line= 6
  2429349.126579 6976657.3944572  2428668.570854  6970923.019443
  2428670.307071 6969071.8912555 2428327.5751449 6968097.6822459
  2427606.939119 6967094.4604991 2425518.4052383 6964398.2824925
#Sta/Elev= 30
       0  446.34  643.33  448.45  775.79  431.47  842.85  443.79  975.08  440.46
 1484.18  446.062185.969 448.1412226.249   447.13132.565   447.1 3134.79  435.99
 3365.64   434.7 3844.51  443.07 4212.62  435.33 5770.06  435.43 5843.38     446
 6945.51     436 7493.74  442.56 7583.63  434.66  9196.1  434.48  9310.8     420
 11205.8     42011286.62     44011440.04  443.4311481.94  439.8211520.39  408.45
11552.84  406.2711603.98  410.7111696.17  441.7412302.97  438.7413304.18  456.42
#Mann= 14 ,-1,0
       0     .07       0  975.08    .065       0 1484.18     .07       0
2185.969      .1       02226.249      .1       0 3134.79     .07       0
 3365.64    .065       0 4212.62     .12       0 5843.38      .1       0
 7583.63     .09       0  9196.1    .055       011286.62     .09       0
11440.04     .05       011696.17    .085       0
Bank Sta=11481.94,11696.17
XS Rating Curve= 0 ,0
Exp/Cntr=0.3,0.1

Type RM Length L Ch R = 1 ,49628   ,158,150,142
BEGIN DESCRIPTION:
Wildlife Phase 3 South shown. XS 48783 - 49945 fill immediately west of Graff Buildings 1 and 2  in current effective no longer proposed.
---------------------------------------------------------------------
Wildlife North downstream bounding cross-section but is superceded by Wildlife Phase 3 Project (CDC GP 032919-01)
CDC Wildlife North GP 071217-01. Cross-section 49628 - 53730. Located in LOB.
CDC GP 040122-1 Oakdale Industrial III
Cross-sections 49628 - 52592
Project in LOB.
END DESCRIPTION:
XS GIS Cut Line= 6
  2429452.213971 6976625.4404528 2428790.3215947 6971102.4370631
 2428763.8459259 6969052.7407032 2428581.5542957 6968078.7823493
 2427650.6335854 6967001.6083226 2425629.9916293 6964371.8379916
#Sta/Elev= 30
       0  450.78  583.69  447.06  725.96  431.15  793.64  442.23  953.13  441.02
 1008.28  450.18 1027.29  435.83 1487.76  446.34 2147.89   447.73139.083 441.485
 3402.66  435.88 4202.44  439.86    5648  435.73 5701.65     446 7310.84     446
 7348.64  436.56 7472.34  442.27 7559.28   431.6 9294.39     436 9364.82     420
11305.61     42011385.63     44011593.84  440.3811633.19  408.4411662.56  406.19
11698.27   406.311742.65  427.9611874.03  441.6812662.53  442.3813345.39  455.64
#Mann= 13 ,-1,0
       0     .07       0 1008.28    .065       0 1487.76     .07       0
 2147.89      .1       03139.083     .07       0 3402.66    .065       0
 4202.44     .12       0    5648      .1       0 7559.28     .09       0
 9294.39    .055       011385.63     .09       011593.84     .05       0
11874.03    .085       0
Bank Sta=11593.84,11874.03
XS Rating Curve= 0 ,0
Exp/Cntr=0.3,0.1

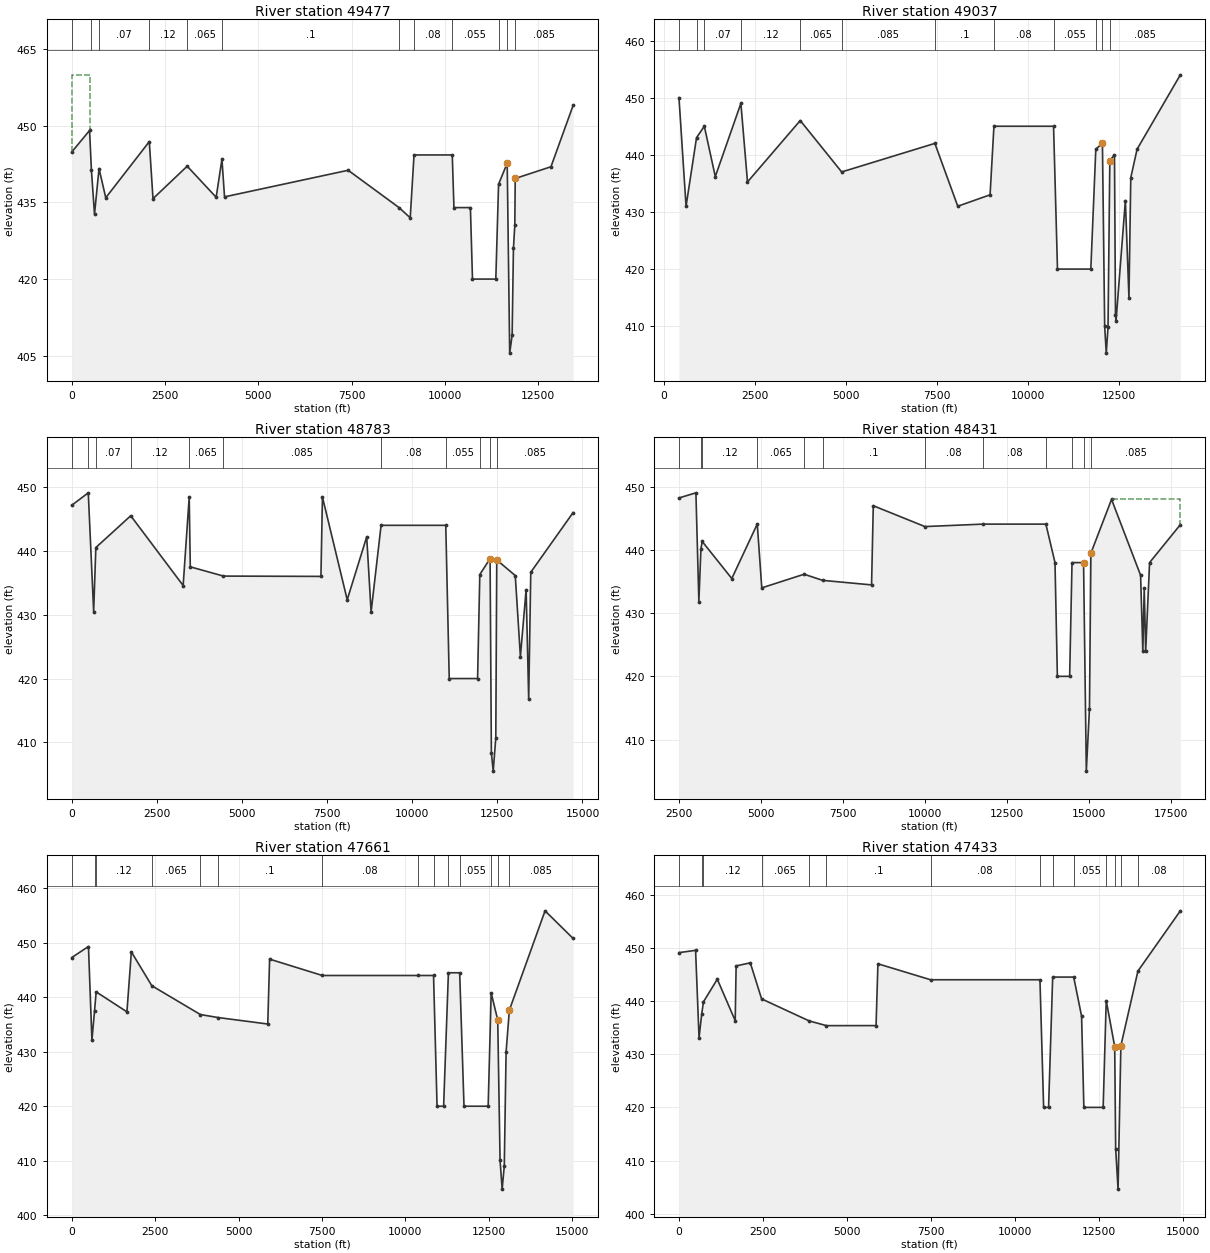
Type RM Length L Ch R = 1 ,49477   ,440,440,440
BEGIN DESCRIPTION:
XS 48783 - 49945 fill immediately west of Graff Buildings 1 and 2  in current effective no longer proposed.
END DESCRIPTION:
XS GIS Cut Line= 4
  2429761.141175 6976576.0993442 2428964.2339766 6969245.5001602
 2428834.2368612 6968060.6022676 2425734.4172735 6964307.9112821
#Sta/Elev= 30
       0  444.88   477.9   449.1  527.69  441.29  610.17   432.7   731.1  441.64
  911.56  435.93 2078.27  446.92 2177.35  435.75 3093.81  442.11 3869.88  436.02
 4024.67  443.47 4094.16   436.1 7406.48  441.31    8770     434 9069.62     432
  9171.5  444.31 10196.2  444.31   10241     434   10682     434   10738     420
   11363     420   11437  438.58   11668   442.7   11735   405.5   11800     409
   11835     426   11872   430.6   11883   439.712840.75     44213433.91     454
#Mann= 12 ,-1,0
       0      .1       0  527.69    .065       0   731.1     .07       0
 2078.27     .12       0 3093.81    .065       0 4024.67      .1       0
    8770     .11       0  9171.5     .08       0 10196.2    .055       0
   11437     .09       0   11668     .05       0   11883    .085       0
#XS Ineff= 2 , 0
           477.9     460
Permanent Ineff=
       F       F
Bank Sta=11668,11883
XS Rating Curve= 0 ,0
Exp/Cntr=0.3,0.1

Type RM Length L Ch R = 1 ,49037   ,254,254,254
BEGIN DESCRIPTION:
XS 48783 - 49945 fill immediately west of Graff Buildings 1 and 2  in current effective no longer proposed.
END DESCRIPTION:
XS GIS Cut Line= 4
  2429803.466878 6976603.8355092 2429310.5846618 6968012.5160776
 2426137.3269007 6964105.7673295 2426055.3716841 6964026.7399285
#Sta/Elev= 30
  423.38     450  617.46     431     905     443 1118.74     445 1419.58  436.19
 2121.64     449 2302.97  435.25  3750.3     446 4886.71     437 7442.92     442
 8071.29     431 8957.39     433 9063.24     44510698.84     44510806.66     420
11721.07     42011857.87     44112039.47     44212100.96     41012144.35  405.29
 12192.8  409.7912242.36     439   12370     44012397.51     412 12413.6     411
12668.88     43212766.97     41512817.15     436 12990.6  440.9914176.85     454
#Mann= 12 ,-1,0
  423.38      .1       0     905    .065       0 1118.74     .07       0
 2121.64     .12       0  3750.3    .065       0 4886.71    .085       0
 7442.92      .1       0 9063.24     .08       010698.84    .055       0
11857.87     .09       012039.47     .05       012242.36    .085       0
Bank Sta=12039.47,12242.36
XS Rating Curve= 0 ,0
Exp/Cntr=0.3,0.1

Type RM Length L Ch R = 1 ,48783   ,352,352,352
BEGIN DESCRIPTION:
XS 48783 - 49945 fill immediately west of Graff Buildings 1 and 2  in current effective no longer proposed.
END DESCRIPTION:
XS GIS Cut Line= 4
  2429848.166263 6976638.4860304 2429749.9279432 6969260.8544602
 2429526.2568026 6967933.9253556 2426140.8403451 6963628.3696622
#Sta/Elev= 30
       0  447.14  485.64  449.09  643.94  430.49  708.12  440.52 1732.77   445.5
 3272.13  434.57 3450.03  448.43 3481.61   437.5 4454.62  436.05 7318.63     436
 7362.78  448.43 8090.26  432.34 8662.64  442.19 8792.04  430.44 9085.47     444
 10984.8     44411086.66     42011919.17     42011984.35  436.2912286.03  438.79
12324.08  408.3912378.26   405.512453.97   410.712482.33  438.5813025.92  436.13
13176.78  423.4513344.96  433.9313420.15  416.7313481.34  436.6514724.51     446
#Mann= 11 ,-1,0
       0      .1       0  485.64    .065       0  708.12     .07       0
 1732.77     .12       0 3450.03    .065       0 4454.62    .085       0
 9085.47     .08       0 10984.8    .055       011984.35     .09       0
12286.03     .05       012482.33    .085       0
Bank Sta=12286.03,12482.33
XS Rating Curve= 0 ,0
Exp/Cntr=0.3,0.1

Type RM Length L Ch R = 1 ,48431   ,777,770,770
BEGIN DESCRIPTION:
XS 44427 - 48431 represent proposed Graff Building 2. See STA 8350 - 9316
END DESCRIPTION:
XS GIS Cut Line= 6
  2430092.090316 6976641.0900278 2429993.8273898 6969261.6198787
 2429974.1542008 6969261.2881864 2429699.3463515 6967917.7836556
  2429529.360471 6967586.9342517 2425896.9766596  6962634.205312
#Sta/Elev= 30
    2490  448.23 3006.64  449.04 3096.39  431.83 3159.35  440.18 3198.97  441.34
 4100.64  435.48  4877.6   444.1 5014.61     434 6306.41  436.16 6868.69  435.19
  8362.5  434.47    8415     447 9989.75   443.7   11770  444.09   13678  444.09
   13956     438   14028     420   14403     420   14475     43814826.82     438
   14911     405   15007   414.9   15051   439.515680.21     44816565.71     436
 16634.2     42416676.96     43416720.76     424 16839.9     43817778.15     444
#Mann= 12 ,-1,0
    2490     .05       0 3159.35     .07       0 3198.97     .12       0
  4877.6    .065       0 6306.41    .085       0 6868.69      .1       0
 9989.75     .08       0   11770     .08       0   13678    .055       0
   14475      .1       014826.82    .055       0   15051    .085       0
#XS Ineff= 2 , 0
                           15680             448
Permanent Ineff=
       F       F
Bank Sta=14826.82,15051
XS Rating Curve= 0 ,0
Exp/Cntr=0.3,0.1

Type RM Length L Ch R = 1 ,47661   ,191,228,194
BEGIN DESCRIPTION:
XS 44427 - 48431 represent proposed Graff Building 2. See STA 5857 - 6829
END DESCRIPTION:
XS GIS Cut Line= 6
  2430142.758194 6976641.3872713 2430045.5359478 6969127.4984277
 2429739.9804566 6967717.7761816 2429065.6579863 6966465.6687776
 2428996.8028091 6965451.1396387 2426611.3492466 6962716.0112507
#Sta/Elev= 30
       0  447.29  501.35  449.32  604.89  432.13  682.87  437.47  732.35  440.99
 1654.05  437.33 1786.95  448.33 2400.19  442.12 3855.27  436.83 4386.17  436.28
 5874.51  435.09    5930     447  7510.4     444   10379     44410842.65     444
10947.94     42011144.66     42011288.19   444.511625.81   444.511755.69     420
 12479.6     42012569.79  440.78 12766.3  435.8412836.19  410.0612898.56  404.78
12962.56  409.0313017.19  430.02 13114.8  437.6414184.35  455.87 15025.1   450.8
#Mann= 14 ,-1,0
       0     .05       0  682.87     .07       0  732.35     .12       0
 2400.19    .065       0 3855.27    .085       0 4386.17      .1       0
  7510.4     .08       0   10379     .08       010842.65    .055       0
11288.19     .08       011625.81    .055       012569.79     .09       0
 12766.3     .05       0 13114.8    .085       0
Bank Sta=12766.3,13114.8
XS Rating Curve= 0 ,0
Exp/Cntr=0.3,0.1

Type RM Length L Ch R = 1 ,47433   ,171,272,346
BEGIN DESCRIPTION:
XS 44427 - 48431 represent proposed Graff Building 2. See STA 5849 - 6837
END DESCRIPTION:
XS GIS Cut Line= 6
  2430165.847715  6976635.189121 2430072.0975745 6969132.5847036
 2429768.9725246 6967714.8765811 2429162.5252466 6966459.3305357
 2428980.2555981 6965139.1763519  2426850.302837 6962712.3842895
#Sta/Elev= 30
       0   449.1  494.65  449.53   597.5   433.1  677.32  437.57  729.38  439.85
 1141.49   444.1 1674.59  436.31 1701.77   446.6  2123.8  447.18 2460.92   440.4
    3877  436.26 4392.51  435.37 5869.28  435.38    5925     447 7492.43     444
 10750.3     444 10859.9     42011006.96     42011129.15   444.511755.36   444.5
11989.93  437.1512057.89     42012632.42     42012724.07  440.0812976.54  431.43
13004.95  412.2313076.21  404.6313160.11   431.613668.35  445.6414931.26  456.96
#Mann= 14 ,-1,0
       0     .05       0  677.32     .07       0  729.38     .12       0
 2460.92    .065       0    3877    .085       0 4392.51      .1       0
 7492.43     .08       0 10750.3    .055       011129.15     .08       0
11755.36    .055       012724.07     .09       012976.54     .05       0
13160.11     .04       013668.35     .08       0
Bank Sta=12976.54,13160.11
XS Rating Curve= 0 ,0
Exp/Cntr=0.3,0.1

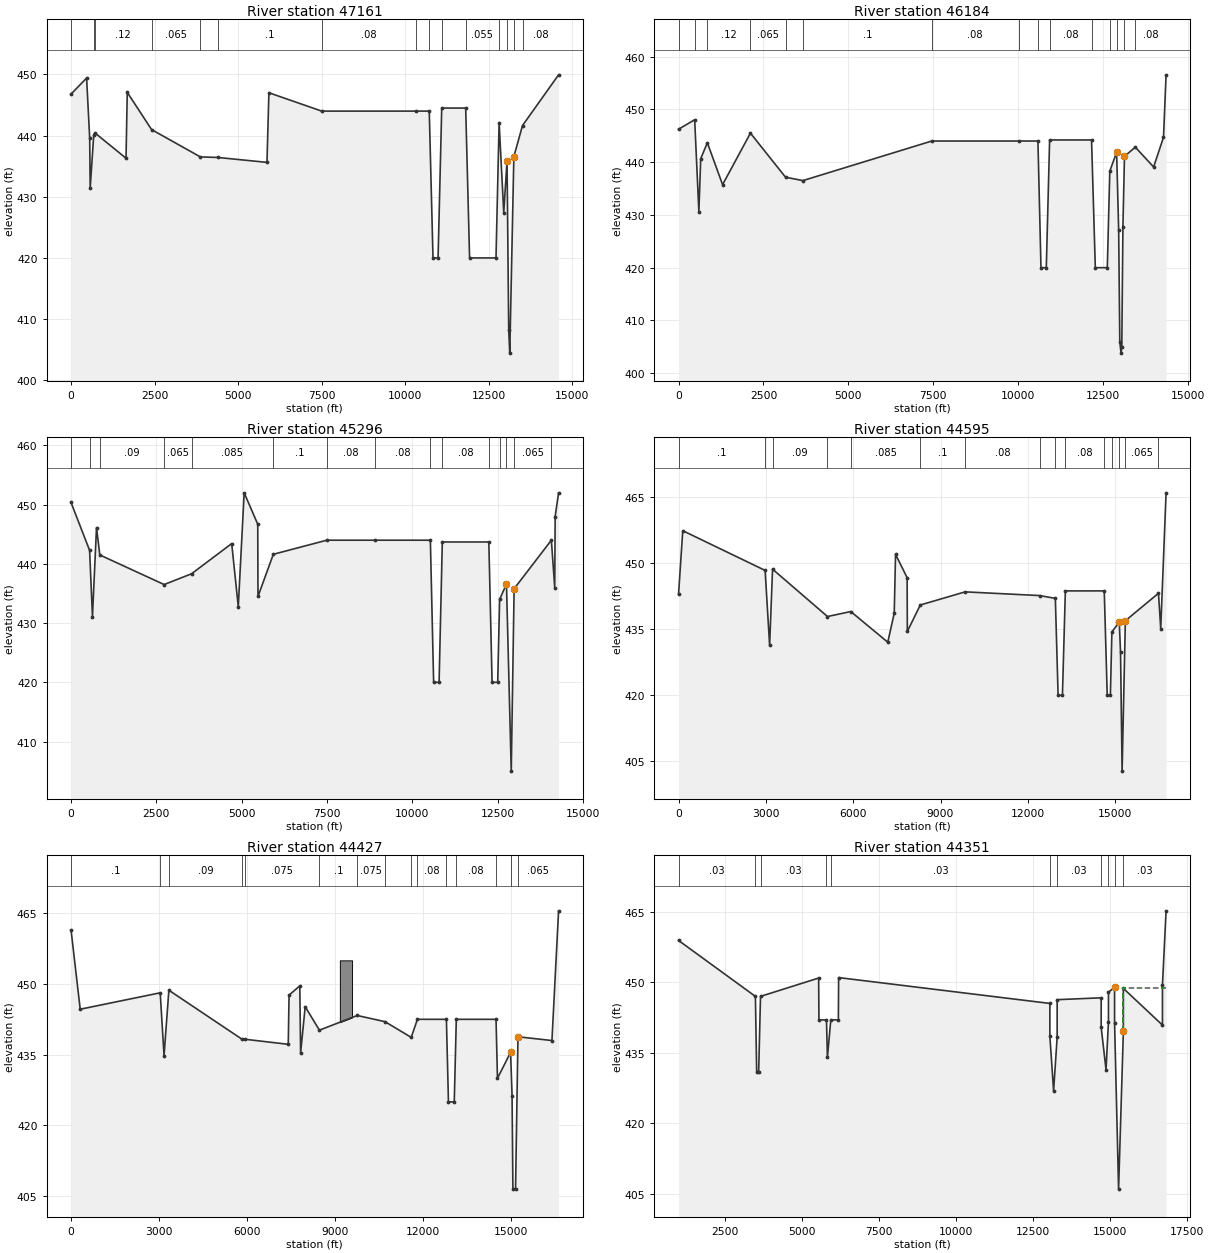
Type RM Length L Ch R = 1 ,47161   ,609,977,1187
BEGIN DESCRIPTION:
XS 44427 - 48431 represent proposed Graff Building 2. See STA 5843 - 6815
END DESCRIPTION:
XS GIS Cut Line= 6
  2430184.424777 6976627.4985196 2430094.1470711 6969120.5538878
 2429802.4803316 6967710.8316416 2429204.5523936 6966466.6146419
 2429036.3499741 6965026.4314987  2427444.770152 6962728.6887188
#Sta/Elev= 30
       0  446.78   465.5  449.41  558.06  439.56  572.64   431.4   679.8  440.15
  717.79  440.42 1645.32   436.3 1681.65  447.07 2409.71  440.98 3867.48  436.52
 4396.56  436.42 5862.39  435.62    5920     447 7499.75     444 10327.5     444
10717.82     44410830.09     42010981.92     42011091.22   444.511808.04   444.5
11924.77     42012714.87     42012808.21  442.1212946.85   427.413045.46   435.9
   13095  408.2813126.94  404.4413249.24  436.5613507.94  441.6414587.58  449.93
#Mann= 15 ,-1,0
       0     .05       0   679.8     .07       0  717.79     .12       0
 2409.71    .065       0 3867.48    .085       0 4396.56      .1       0
 7499.75     .08       0 10327.5     .08       010717.82    .055       0
11091.22     .08       011808.04    .055       012808.21     .09       0
13045.46     .05       013249.24     .04       013507.94     .08       0
Bank Sta=13045.46,13249.24
XS Rating Curve= 0 ,0
Exp/Cntr=0.3,0.1

Type RM Length L Ch R = 1 ,46184   ,851,888,930
BEGIN DESCRIPTION:
XS 44427 - 48431 represent proposed Graff Building 2. See STA 5817 - 6804
END DESCRIPTION:
XS GIS Cut Line= 6
  2430267.758272 6976620.5539797 2430226.0916891 6969183.0540909
 2429646.1305786 6966680.3248444 2429601.4633451 6964801.7373942
 2429316.9468538 6964470.3955372 2429041.2292294 6962466.8939668
#Sta/Elev= 30
       0  446.23  475.06  448.03  598.43  430.57  652.56  440.65  848.23  443.67
 1295.87  435.73 2115.86  445.49 3149.07  437.14  3659.7   436.5 7454.08     444
   10010     44410576.85     44410666.52     42010823.05     42010921.03   444.2
12154.92   444.2 12265.5     42012618.49     42012692.09  438.29 12892.7  441.87
 12952.9  427.1112985.99  405.9613022.84  403.8113044.66  405.0113078.15   427.8
13123.81  441.0813442.08  442.8413981.37  439.0814272.08  444.6914348.24  456.54
#Mann= 15 ,-1,0
       0      .1       0  475.06     .07       0  848.23     .12       0
 2115.86    .065       0 3149.07    .085       0  3659.7      .1       0
 7454.08     .08       0   10010     .08       010576.85    .055       0
10921.03     .08       012154.92    .055       012692.09     .09       0
 12892.7     .05       013123.81     .04       013442.08     .08       0
Bank Sta=12892.7,13123.81
XS Rating Curve= 0 ,0
Exp/Cntr=0.3,0.1

Type RM Length L Ch R = 1 ,45296   ,656,701,706
BEGIN DESCRIPTION:
XS 44427 - 48431 represent proposed Graff Building 2. See STA 5866 - 6839
END DESCRIPTION:
XS GIS Cut Line= 4
  2430539.170459 6976656.5060075 2430532.2259193 6969156.5059156
 2430480.5731355 6967742.5340061 2429970.7290108 6962477.3115969
#Sta/Elev= 30
       0  450.37  543.87  442.28  627.87  431.11   746.5  446.13  842.86  441.51
 2728.91  436.51 3532.39  438.33 4709.12  443.43 4902.05  432.78  5074.5     452
 5472.53   446.7 5479.53   434.5 5928.66  441.62 7496.91     444 8914.65     444
 10532.4     444   10628     420   10788     420 10882.4   443.7   12246   443.7
   12341     420   12506     420   12562     434   12763   436.6   12903     405
   12987   435.814078.53     444 14177.4     43614190.12     44814290.43     452
#Mann= 15 ,-1,0
       0      .1       0  543.87    .075       0  842.86     .09       0
 2728.91    .065       0 3532.39    .085       0 5928.66      .1       0
 7496.91     .08       0 8914.65     .08       0 10532.4    .055       0
 10882.4     .08       0   12246    .055       0   12562     .09       0
   12763     .05       0   12987    .065       014078.53     .04       0
Bank Sta=12763,12987
XS Rating Curve= 0 ,0
Exp/Cntr=0.3,0.1

Type RM Length L Ch R = 1 ,44595   ,171,168,159
BEGIN DESCRIPTION:
XS 44427 - 48431 represent proposed Graff Building 2. See STA 8251 - 9224
END DESCRIPTION:
XS GIS Cut Line= 6
  2430743.962044 6979039.4484201  2430777.724116 6970921.4741705
 2430838.1327878 6969185.1387324 2430821.8549332 6967333.8491279
 2430782.7923473 6966648.0850795 2430817.5147188 6962302.9248066
#Sta/Elev= 30
       0  442.93   145.2  457.37 2974.32  448.35 3129.11   431.3 3229.27  448.64
 5116.75  437.88 5916.52  439.01 7187.93  432.05 7409.74  438.63 7454.75     452
 7852.77   446.7 7859.77   434.5 8305.37   440.5 9845.21  443.48   12403  442.64
 12944.3     44213039.08     42013187.76     42013288.05   443.714624.24   443.7
14726.68     42014835.04     42014887.11   434.415140.43   436.615183.65  429.76
 15237.6  402.7715349.41  436.9216487.54  443.1616564.22  435.13 16748.3  465.97
#Mann= 15 ,-1,0
       0      .1       0 2974.32    .075       0 3229.27     .09       0
 5116.75    .065       0 5916.52    .085       0 8305.37      .1       0
 9845.21     .08       0   12403     .08       0 12944.3    .055       0
13288.05     .08       014624.24    .055       014887.11     .09       0
15140.43     .05       015349.41    .065       016487.54     .04       0
Bank Sta=15140.43,15349.41
XS Rating Curve= 0 ,0
Exp/Cntr=0.3,0.1

Type RM Length L Ch R = 1 ,44427   ,76,76,76
BEGIN DESCRIPTION:
XS 44427 - 48431 represent proposed Graff Building 2. See STA 8277 - 9250. Error in plan view length and model length found in old modelling for CDC GP 071217-1 and fixed.
GP 062623-1 Hopewell Belt LIne
END DESCRIPTION:
XS GIS Cut Line= 6
  2430911.982049  6979047.499257 2430947.0479243 6970717.3810747
 2431004.3922978 6969226.1878629 2431022.5690987 6967772.0490389
 2430969.2598221 6966599.2462664 2430988.0589971 6962295.6482463
#Sta/Elev= 30
       0  461.45  312.79  444.64 3043.06  448.12 3174.56  434.79 3338.56  448.67
 5831.08   438.3 5927.27  438.28 7414.16   437.2 7441.31  447.63 7807.99  449.59
 7835.46  435.35 7991.94  445.17 8477.58   440.2 9768.74  443.31   10717     442
   11611  438.67   11823   442.5   12812   442.5   12882     425   13080     425
   13150   442.5   14506   442.5   14555     430   15003   435.5   15053   426.3
   15082   406.5   15172   406.5   15255   438.8   16414     438   16641   465.5
#Mann= 15 ,-1,0
       0      .1       0 3043.06    .075       0 3338.56     .09       0
 5831.08    .065       0 5927.27    .075       0 8477.58      .1       0
 9768.74    .075       0   10717     .07       0   11611     .09       0
   11823     .08       0   12812    .055       0   13150     .08       0
   14506    .055       0   15003     .05       0   15255    .065       0
#Block Obstruct= 1 ,-1
    9175    9592     455
Bank Sta=15003,15255
XS Rating Curve= 0 ,0
Exp/Cntr=0.3,0.1

Type RM Length L Ch R = 1 ,44351   ,119,119,119
BEGIN DESCRIPTION:
Cross section 44351 - Belt Line Road upstream bounding cross section.
---------------------------------------------------------------------
Wildlife North 3 downstream bounding cross-section.
CDC GP 032919-01 Wildlife North 3
Cross-section 44351 - 58868
Located in LOB.
---------------------------------------------------------------------
END DESCRIPTION:
XS GIS Cut Line= 6
  2430993.509117 6978036.7102681 2431031.6081226 6970631.4419421
 2431090.6637788 6969296.3389693 2431095.8576661 6967804.3544205
 2431039.6710986 6966302.1563094 2431077.5745661 6962232.4203544
#Sta/Elev= 30
    1000   458.9    3492     447    3533     431    3598     431    3658     447
    5543   450.9  5552.3     442    5797     442    5827     434    5937     442
  6182.3     442    6191     451   13040   445.5   13040   438.5   13161   426.9
   13276   438.3   13276   446.3   14704   446.7   14704   440.4   14861   431.4
   14940   441.6   14940   447.9   15138   448.9   15138   441.4   15268     406
   15423   439.6   15423   448.7   16690   440.9   16691   449.5   16808   465.2
#Mann= 11 ,-1,0
    1000     .03       0    3492     .05       0    3658     .03       0
    5797     .05       0    5937     .03       0   13040     .05       0
   13276     .03       0   14704     .05       0   14940     .03       0
   15138     .05       0   15423     .03       0
#XS Ineff= 2 , 0
                           15423           448.7
Permanent Ineff=
       F       T
Bank Sta=15138,15423
XS Rating Curve= 0 ,0
Exp/Cntr=0.3,0.1