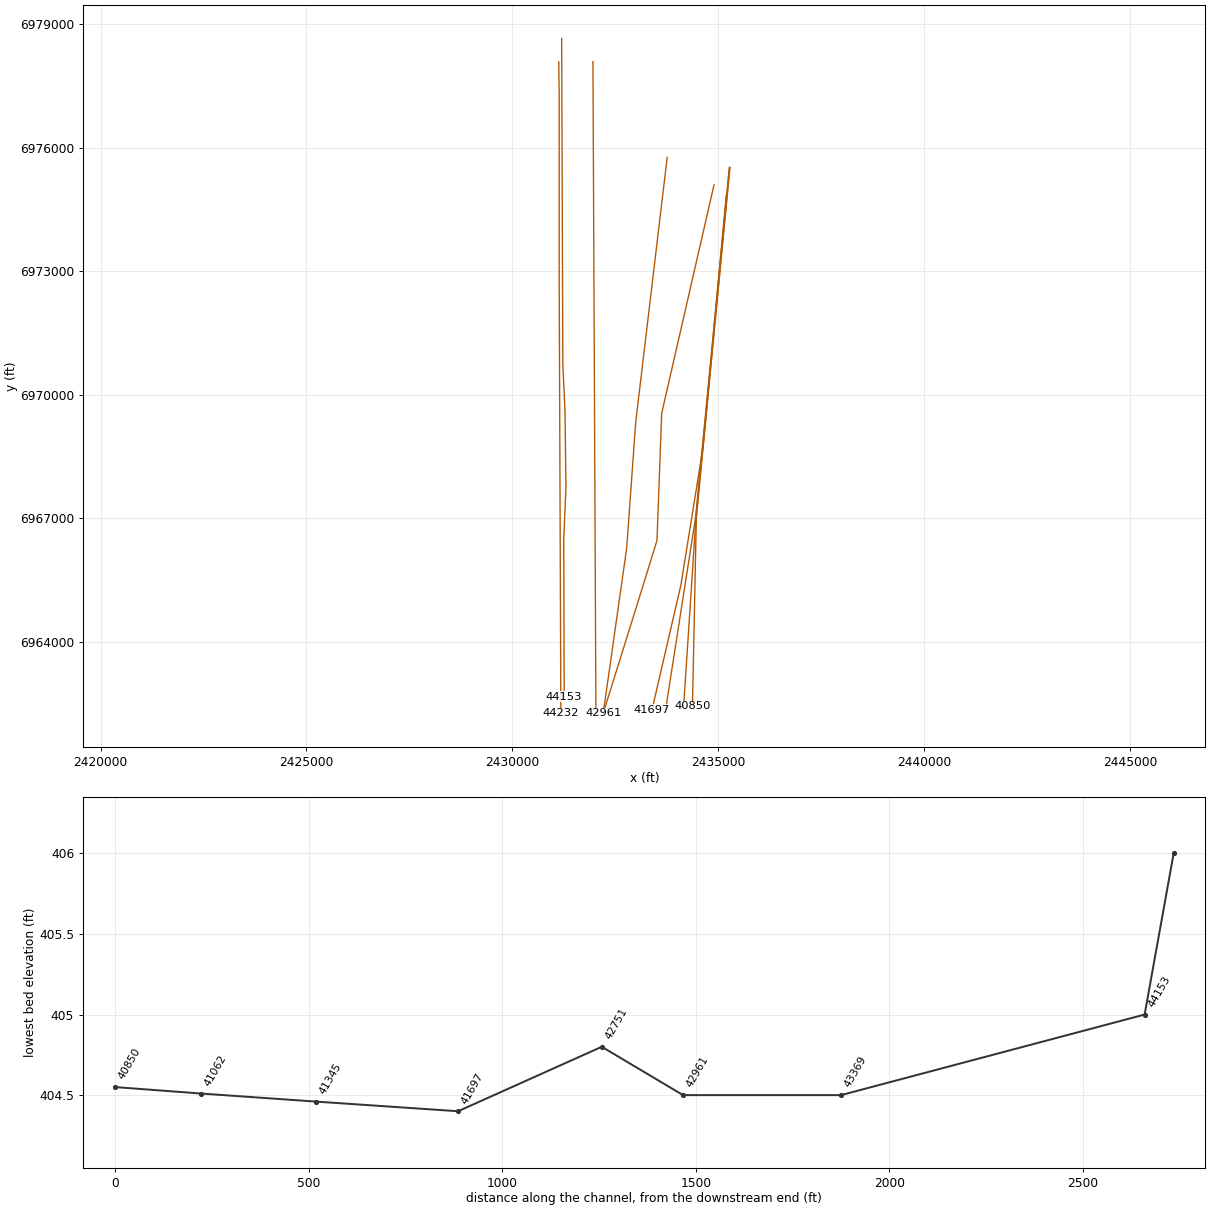
HEC-RAS study CDC_Consolidated_Model.prj: Upper Trinity CDC Consolidated Model

--- CDC_Consolidated_Model.g13 (geometry) --- (continued)

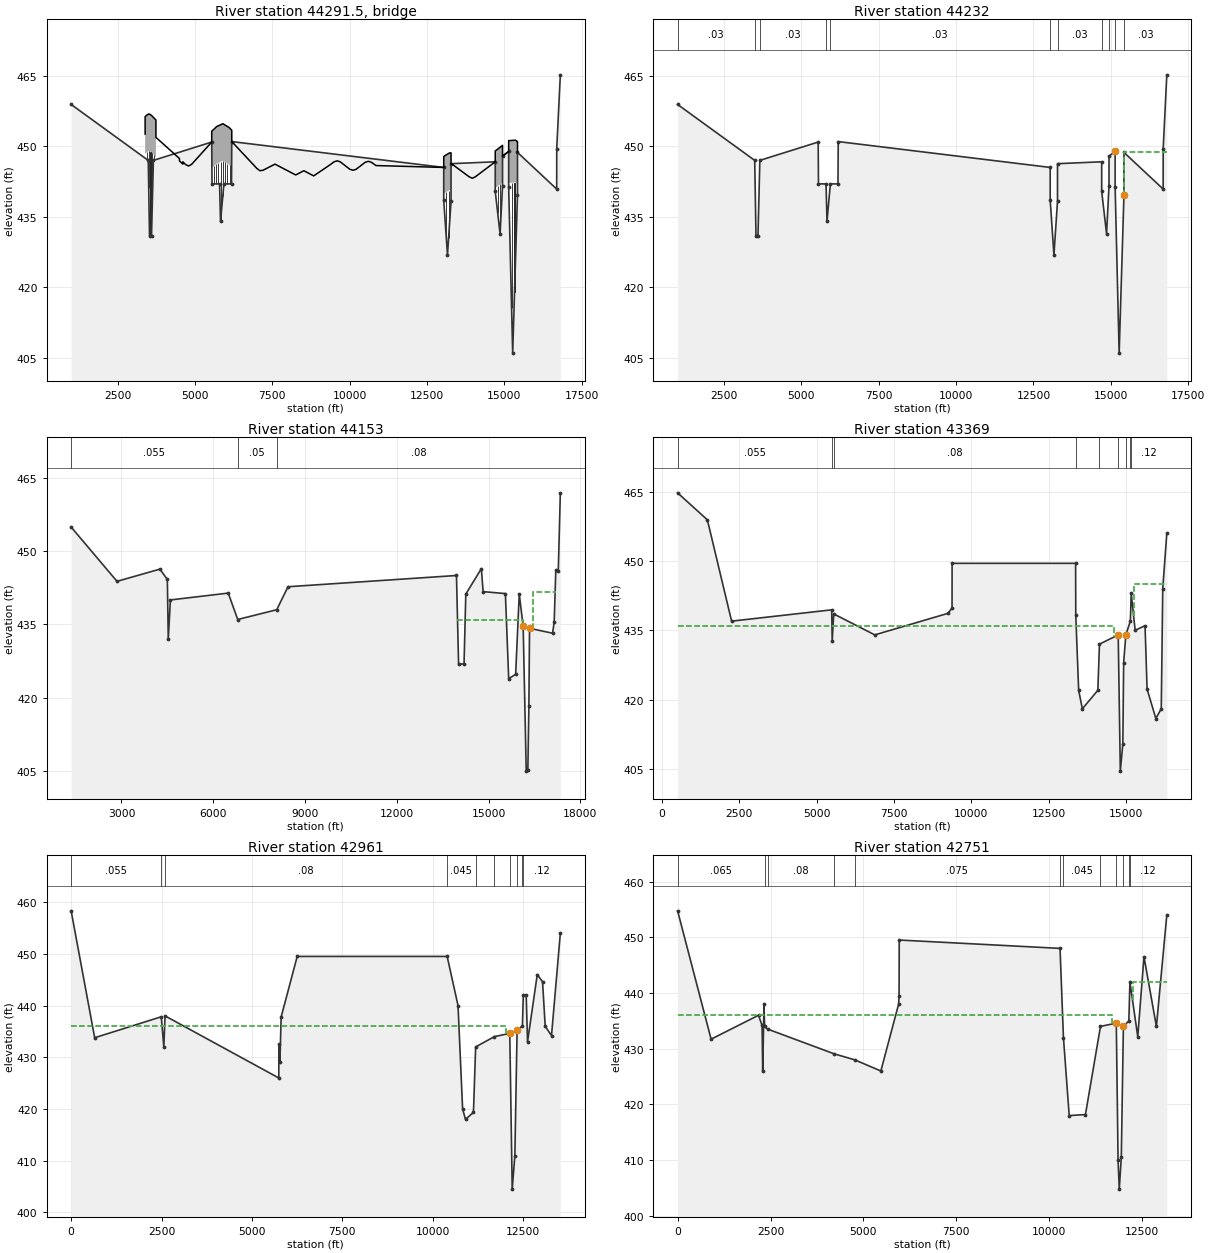
Type RM Length L Ch R = 3 ,44291.5 ,,,
BEGIN DESCRIPTION:
Belt Line Road
END DESCRIPTION:
Node Name=Belt Line Road
Bridge Culvert--1,0,-1,-1, 0
Deck Dist Width WeirC Skew NumUp NumDn MinLoCord MaxHiCord MaxSubmerge Is_Ogee
0.5,117,2.6,0, 59, 59, , , 0.95, 0, 0,0,,
    3391    3391    3438    3515    3592    3740    3740    4500    4500    4610
    4610    4700    4800    4900    5543    5543    5704    5904    6104    6191
    6191    7000    7100    7200    7587    8257    8521    8837    9397    9495
    9595    9695   10007   10107   10207   10502   10602   10702   10850   13040
   13040   13040   13100   13231   13276   13276   13350   13864   13962   14060
   14704   14704   14940   14940   15138   15138   15357   15423   15423
   452.6   456.3   456.6   456.9   456.6   455.6   451.9   447.4   446.9   446.2
   446.7   446.1   445.8   446.2   450.9   453.2   454.2   454.8     454   453.4
     451   445.3   444.8   444.9   446.2   443.9   444.8   443.7   446.2   446.7
   446.9   446.7   445.1   444.9   445.1   446.6   446.8   446.6   445.9   445.5
   445.5   447.8   448.1   448.6   448.6   446.3     446   443.5   443.2   443.5
   446.7     449   450.2   447.9   448.9   451.2   451.3     451   448.7
   452.6   448.4   448.7     449   448.7   447.7   451.9   447.4   446.9   446.2
   446.7   446.1   445.8   446.2   450.9   445.3   446.3   446.9   446.1   445.5
     451   445.3   444.8   444.9   446.2   443.9   444.8   443.7   446.2   446.7
   446.9   446.7   445.1   444.9   445.1   446.6   446.8   446.6   445.9   445.5
   445.5   439.9   440.2   440.7   440.7   446.3     446   443.5   443.2   443.5
   446.7   441.1   442.3   447.9   448.9   442.2   442.3     442   448.7
    3391    3391    3438    3515    3592    3740    3740    4500    4500    4610
    4610    4700    4800    4900    5543    5543    5704    5904    6104    6191
    6191    7000    7100    7200    7587    8257    8521    8837    9397    9495
    9595    9695   10007   10107   10207   10502   10602   10702   10850   13040
   13040   13040   13100   13231   13276   13276   13350   13864   13962   14060
   14704   14704   14940   14940   15138   15138   15357   15423   15423
   452.6   456.3   456.6   456.9   456.6   455.6   451.9   447.4   446.9   446.2
   446.7   446.1   445.8   446.2   450.9   453.2   454.2   454.8     454   453.4
     451   445.3   444.8   444.9   446.2   443.9   444.8   443.7   446.2   446.7
   446.9   446.7   445.1   444.9   445.1   446.6   446.8   446.6   445.9   445.5
   445.5   447.8   448.1   448.6   448.6   446.3     446   443.5   443.2   443.5
   446.7     449   450.2   447.9   448.9   451.2   451.3     451   448.7
   452.6   448.4   448.7     449   448.7   447.7   451.9   447.4   446.9   446.2
   446.7   446.1   445.8   446.2   450.9   445.3   446.3   446.9   446.1   445.5
     451   445.3   444.8   444.9   446.2   443.9   444.8   443.7   446.2   446.7
   446.9   446.7   445.1   444.9   445.1   446.6   446.8   446.6   445.9   445.5
   445.5   439.9   440.2   440.7   440.7   446.3     446   443.5   443.2   443.5
   446.7   441.1   442.3   447.9   448.9   442.2   442.3     442   448.7
Pier Skew, UpSta & Num, DnSta & Num=  ,3449, 2 ,3449, 2 , 0 , 0 , 0 ,,
     2.5     2.5
     430     450
     2.5     2.5
     430     450
Pier Skew, UpSta & Num, DnSta & Num=  ,3507, 2 ,3507, 2 , 0 , 0 , 0 ,,
     2.5     2.5
     430     450
     2.5     2.5
     430     450
Pier Skew, UpSta & Num, DnSta & Num=  ,3565, 2 ,3565, 2 , 0 , 0 , 0 ,,
     2.5     2.5
     430     450
     2.5     2.5
     430     450
Pier Skew, UpSta & Num, DnSta & Num=  ,3623, 2 ,3623, 2 , 0 , 0 , 0 ,,
     2.5     2.5
     430     450
     2.5     2.5
     430     450
Pier Skew, UpSta & Num, DnSta & Num=  ,3681, 2 ,36812.54, 2 , 0 , 0 , 0 ,,
     2.5     2.5
     430     450
     2.5     2.5
     430     450
Pier Skew, UpSta & Num, DnSta & Num=  ,5615, 2 ,56152.54, 2 , 0 , 0 , 0 ,,
     2.5     2.5
     430     450
     2.5     2.5
     430     450
Pier Skew, UpSta & Num, DnSta & Num=  ,5687, 2 ,56872.54, 2 , 0 , 0 , 0 ,,
     2.5     2.5
     430     450
     2.5     2.5
     430     450
Pier Skew, UpSta & Num, DnSta & Num=  ,5759, 2 ,57592.54, 2 , 0 , 0 , 0 ,,
     2.5     2.5
     430     450
     2.5     2.5
     430     450
Pier Skew, UpSta & Num, DnSta & Num=  ,5831, 2 ,58312.54, 2 , 0 , 0 , 0 ,,
     2.5     2.5
     430     450
     2.5     2.5
     430     450
Pier Skew, UpSta & Num, DnSta & Num=  ,5903, 2 ,59032.54, 2 , 0 , 0 , 0 ,,
     2.5     2.5
     430     450
     2.5     2.5
     430     450
Pier Skew, UpSta & Num, DnSta & Num=  ,5975, 2 ,59752.54, 2 , 0 , 0 , 0 ,,
     2.5     2.5
     430     450
     2.5     2.5
     430     450
Pier Skew, UpSta & Num, DnSta & Num=  ,6047, 2 ,60472.54, 2 , 0 , 0 , 0 ,,
     2.5     2.5
     430     450
     2.5     2.5
     430     450
Pier Skew, UpSta & Num, DnSta & Num=  ,6119, 2 ,61192.54, 2 , 0 , 0 , 0 ,,
     2.5     2.5
     430     450
     2.5     2.5
     430     450
Pier Skew, UpSta & Num, DnSta & Num=  ,13119, 2 ,13119, 2 , 0 , 0 , 0 ,,
     2.5     2.5
     400     444
     2.5     2.5
     400     444
Pier Skew, UpSta & Num, DnSta & Num=  ,13198, 2 ,13198, 2 , 0 , 0 , 0 ,,
     2.5     2.5
     400     444
     2.5     2.5
     400     444
Pier Skew, UpSta & Num, DnSta & Num=  ,14783, 2 ,14783, 2 , 0 , 0 , 0 ,,
     2.5     2.5
     400     444
     2.5     2.5
     400     444
Pier Skew, UpSta & Num, DnSta & Num=  ,14862, 2 ,14862, 2 , 0 , 0 , 0 ,,
     2.5     2.5
     400     444
     2.5     2.5
     400     444
Pier Skew, UpSta & Num, DnSta & Num=  ,15233, 2 ,15233, 2 , 0 , 0 , 0 ,,
       3       3
     400     444
       3       3
     400     444
Pier Skew, UpSta & Num, DnSta & Num=  ,15328, 2 ,15328, 2 , 0 , 0 , 0 ,,
       3       3
     400     444
       3       3
     400     444
BR Coef=-1 , 0 , 0 ,, 0 ,,,0.8,-1,,1,
WSPro=,,,, 1 ,,,, 0 ,,,, 0 ,,,,-1 ,-1 ,-1 , 0 , 0 , 0 , 0 , 0
BC Design=,, 0 ,, 0 ,,,,,,
BC HTab HWMax=454.8
BC Use User HTab Curves=0
BC User HTab FreeFlow(D)= 0

Type RM Length L Ch R = 1 ,44232   ,56,75,75
BEGIN DESCRIPTION:
This cross section corresponds to cross section 44232 of the non-georeferenced CDC model which was the source of this model.
Belt Line Road downstream bounding cross-section.
CDC GP080808-1 Belt Line West Reclamation
Cross-section 44232 - 55761
Located in LOB.
CDC IRV120304-1 Belt Line Road from IH30 to Rock
END DESCRIPTION:
XS GIS Cut Line= 6
  2431124.406487 6978083.6410307 2431134.5770704 6977312.3341743
 2431134.5770704 6972896.8479266 2431148.5235648 6969272.4381807
 2431172.6019287 6963012.1170399 2431175.4516606 6962265.3324442
#Sta/Elev= 30
    1000   458.9    3492     447    3533     431    3598     431    3658     447
    5543   450.9  5552.3     442    5797     442    5827     434    5937     442
  6182.3     442    6191     451   13040   445.5   13040   438.5   13161   426.9
   13276   438.3   13276   446.3   14704   446.7   14704   440.4   14861   431.4
   14940   441.6   14940   447.9   15138   448.9   15138   441.4   15268     406
   15423   439.6   15423   448.7   16690   440.9   16691   449.5   16808   465.2
#Mann= 11 ,-1,0
    1000     .03       0    3492     .05       0    3658     .03       0
    5797     .05       0    5937     .03       0   13040    .055       0
   13276     .03       0   14704     .05       0   14940     .03       0
   15138     .05       0   15423     .03       0
#XS Ineff= 2 , 0
                           15423           448.7
Permanent Ineff=
       F       T
Bank Sta=15138,15423
XS Rating Curve= 0 ,0
Exp/Cntr=0.3,0.1

Type RM Length L Ch R = 1 ,44153   ,764,784,790
BEGIN DESCRIPTION:
This cross section corresponds to cross section 44153 of the non-georeferenced CDC model which was the source of this model.
END DESCRIPTION:
XS GIS Cut Line= 6
  2431194.921402 6978653.9746285 2431223.4400817 6970733.3109151
 2431276.7490302 6969573.8358718  2431298.960928 6967747.9960196
 2431245.6519795 6966495.2301524 2431255.9631441  6962666.794463
#Sta/Elev= 30
    1355   454.9    2855   443.8    4257   446.3    4500   444.2    4530     432
    4600     440    6491   441.4    6800     436    8075     438    8444   442.7
   13950     445   14019   426.9   14197   426.9   14255   441.2   14764   446.4
   14821   441.7   15549   441.3   15657   423.9   15884   424.8   16002   441.2
   16130   434.6   16230     405   16283   405.2   16317   418.4   16338   434.2
   17090   433.2   17143   435.4   17197   446.1   17278     446   17345   461.9
#Mann= 3 ,-1,0
    1355    .055       0    6800     .05       0    8075     .08       0
#XS Ineff= 2 ,-1
   13954   16130     436   16450   17209   441.7
Permanent Ineff=
       F       T
Bank Sta=16130,16338
XS Rating Curve= 0 ,0
Exp/Cntr=0.3,0.1

Type RM Length L Ch R = 1 ,43369   ,1524,408,390
BEGIN DESCRIPTION:
This cross section corresponds to cross section 43369 of the non-georeferenced CDC model which was the source of this model.
END DESCRIPTION:
XS GIS Cut Line= 6
  2431954.349471 6978088.4298544 2431962.0452317 6976397.8681555
 2431973.5291327 6973874.3981368 2431990.9772605 6970038.7263462
 2432008.8751906 6966102.1187339 2432026.3049457 6962266.4528488
#Sta/Elev= 30
  502.22  464.77 1465.36  458.92 2249.31  436.98 5486.05  439.43 5502.55  432.76
 5551.55  438.55 6880.06  434.01 9241.59  438.66 9378.37  439.81    9380   449.5
   13375   449.5   13380   438.3 13473.4     42213592.98     41814093.83     422
14146.09     43214752.67     434 14820.7   404.514902.11  410.4214928.83     428
14999.68     434 15145.7     437 15172.7     443 15300.7     43515620.13     436
15686.37  422.2715970.38  415.8916144.95  418.0316192.98     44416324.36     456
#Mann= 9 ,-1,0
  502.22    .055       0 5486.05     .05       0 5551.55     .08       0
   13380    .045       014146.09    .065       014752.67     .05       0
14999.68     .12       0 15145.7     .06       0 15172.7     .12       0
#XS Ineff= 2 , 0
        14620.61     436 15249.7             445
Permanent Ineff=
       F       T
Bank Sta=14752.67,14999.68
XS Rating Curve= 0 ,0
Exp/Cntr=0.3,0.1

Type RM Length L Ch R = 1 ,42961   ,959,210,80
BEGIN DESCRIPTION:
This cross section corresponds to cross section 42961 of the non-georeferenced CDC model which was the source of this model.
END DESCRIPTION:
XS GIS Cut Line= 6
  2433756.997022 6975764.3681102 2433380.5187728 6972596.3711653
 2432992.1888408 6969329.3809802 2432773.6699208 6966280.6098467
 2432482.0799528 6964227.1884287   2432204.33707   6962271.55192
#Sta/Elev= 30
       0  458.32  651.49  433.78 2493.22  437.83 2563.56     432 2597.63     438
 5743.17     426 5746.48  432.47 5774.92  429.14 5808.16  437.78  6252.6   449.5
   10400   449.510700.38     44010827.49     42010907.34     41811127.15  419.34
11188.12     43211707.37     43412131.79  434.61   12199   404.512272.56  410.98
12334.37  435.31   12481     436   12506     442   12586     442   12623     433
12892.35     44613038.21   444.6 13111.5     43613285.71  434.1913530.27     454
#Mann= 10 ,-1,0
       0    .055       0 2493.22     .05       0 2597.63     .08       0
   10400    .045       011188.12     .06       011707.37    .075       0
12131.79     .05       012334.37     .12       0   12481     .06       0
   12506     .12       0
#XS Ineff= 2 , 0
        12021.51     436   12586             442
Permanent Ineff=
       F       T
Bank Sta=12131.79,12334.37
XS Rating Curve= 0 ,0
Exp/Cntr=0.3,0.1

Type RM Length L Ch R = 1 ,42751   ,295,371,363
BEGIN DESCRIPTION:
This cross section corresponds to cross section 42751 of the non-georeferenced CDC model which was the source of this model.
END DESCRIPTION:
XS GIS Cut Line= 6
   2434894.38169 6975098.5194684 2433623.2600852 6969551.4290925
 2433619.7614045 6969451.9460237 2433509.1149722 6966463.8066588
 2433107.9458271 6965164.6596508 2432206.9518942 6962279.9246067
#Sta/Elev= 30
       0  454.74  901.57  431.71 2177.29     436 2273.31  434.17 2290.27     426
 2323.98     438 2341.81     434 2421.07  433.52 4211.51  429.08 4766.46     428
 5468.73     426 5946.82     438 5958.78  439.45  5963.2   449.510289.95     448
10381.16     43210536.37     41810973.11  418.1811378.03     43411803.32  434.59
11851.23     410 11883.5   404.811938.17  410.5511994.12     434 12141.5     435
 12169.5     44212380.89  432.1712548.39  446.5112882.52     43413162.44     454
#Mann= 12 ,-1,0
       0    .065       0 2341.81     .05       0 2421.07     .08       0
 4211.51     .05       0 4766.46    .075       010289.95    .035       0
10381.16    .045       011378.03    .085       011803.32     .05       0
11994.12     .12       0 12141.5     .06       0 12169.5     .12       0
#XS Ineff= 2 , 0
         11679.3     436 12241.5             442
Permanent Ineff=
       F       T
Bank Sta=11803.32,11994.12
XS Rating Curve= 0 ,0
Exp/Cntr=0.3,0.1

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
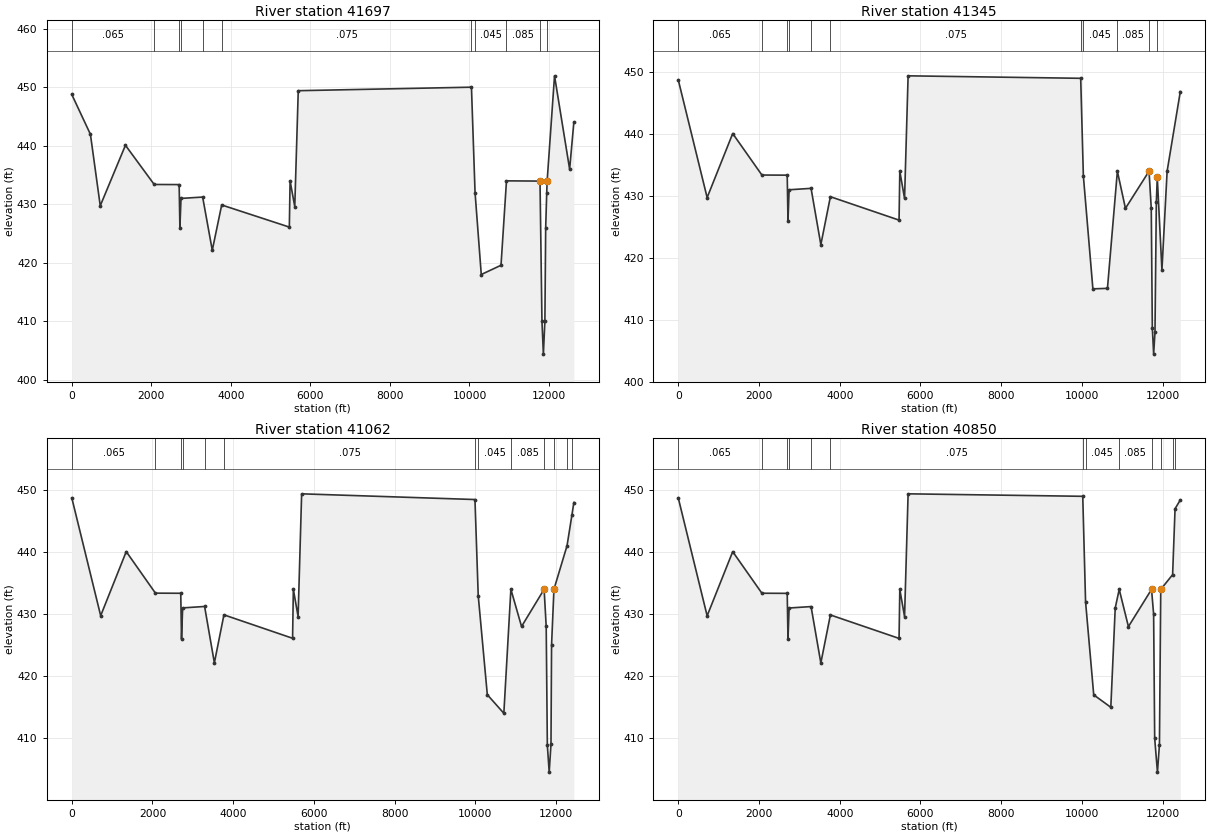
Type RM Length L Ch R = 1 ,41697   ,71,368,399
BEGIN DESCRIPTION:
41697
END DESCRIPTION:
XS GIS Cut Line= 6
  2435190.386695 6974832.8061043 2434905.2466944 6971739.3092312
 2434627.8902938 6968730.9185944 2434087.7909803 6965372.5119254
 2433727.3727378 6963816.1361012 2433389.4469045 6962357.0379695
#Sta/Elev= 30
       0  448.76     469  441.95  716.11  429.74  1349.4  440.08 2072.76  433.38
 2699.91  433.36    2719     426    2747     431 3290.84  431.23    3533  422.14
 3769.76  429.88 5470.74   426.1 5489.52     434 5607.24   429.6 5695.09   449.4
10050.02     450 10140.5     432 10296.7     41810793.14  419.5810930.77     434
 11773.7  433.9611822.75     410 11858.7   404.411896.72  410.0711916.56     426
11942.83     43211953.44     43412139.03  451.9412518.51     436 12624.6     444
#Mann= 11 ,-1,0
       0    .065       0 2072.76     .08       0 2699.91     .05       0
    2747    .075       0 3290.84     .04       0 3769.76    .075       0
10050.02    .035       0 10140.5    .045       010930.77    .085       0
 11773.7     .05       011942.83     .06       0
#XS Ineff= 2 , 0
         11773.7  433.96
Permanent Ineff=
       F       F
#Block Obstruct= 2 , 0
                           12136           451.7
Bank Sta=11773.7,11953.44
XS Rating Curve= 0 ,0
Exp/Cntr=0.3,0.1

Type RM Length L Ch R = 1 ,41345   ,58,297,322
XS GIS Cut Line= 3
  2435265.0148876975517.906010722434445.570442916967017.90601072
2433721.03340593 6962373.5917746
#Sta/Elev= 30
       0  448.76  716.11  429.74  1349.4  440.08 2072.76  433.38 2699.91  433.36
    2719     426    2747     431 3290.84  431.23    3533  422.14 3769.76  429.88
 5470.74   426.1 5489.52     434 5607.24   429.6 5695.09   449.4 9971.07     449
10037.09  433.2310272.91     41510633.78  415.0810879.53     43411079.58     428
11664.24     43411719.13     42811745.37  408.7511778.37  404.4611811.37     408
11844.75     42911868.18     43311983.57  418.04 12112.2     434 12438.9  446.86
#Mann= 11 ,-1,0
       0    .065       0 2072.76     .08       0 2699.91     .05       0
    2747    .075       0 3290.84     .04       0 3769.76    .075       0
 9971.07    .035       010037.09    .045       010879.53    .085       0
11664.24     .05       011868.18     .08       0
#XS Ineff= 2 , 0
        11664.24     43411868.18             433
Permanent Ineff=
       F       T
Bank Sta=11664.24,11868.18
XS Rating Curve= 0 ,0
Exp/Cntr=0.3,0.1

Type RM Length L Ch R = 1 ,41062   ,43,221,240
XS GIS Cut Line= 3
  2435273.590552  6975517.7179322434456.479007756967017.82643893
2434154.308868896962414.67250377
#Sta/Elev= 30
       0  448.76  716.11  429.74  1349.4  440.08 2072.76  433.38 2699.91  433.36
    2719     426    2747     431 3290.84  431.23    3533  422.14 3769.76  429.88
 5470.74   426.1 5489.52     434 5607.24   429.6 5695.09   449.4 9988.99  448.48
10069.67     43310294.96     41710704.56     41410879.02     43411143.22     428
11702.47     43411754.02     428 11782.4  408.83 11828.2  404.5111872.58     409
11886.76     42511945.88     43412270.68  441.0412391.58     446 12438.9     448
#Mann= 13 ,-1,0
       0    .065       0 2072.76     .08       0 2699.91     .05       0
    2747    .075       0 3290.84     .04       0 3769.76    .075       0
 9988.99    .035       010069.67    .045       010879.02    .085       0
11702.47     .05       011945.88     .08       012270.68     .05       0
12391.58     .08       0
#XS Ineff= 2 , 0
        11702.47     434
Permanent Ineff=
       F       F
Bank Sta=11702.47,11945.88
XS Rating Curve= 0 ,0
Exp/Cntr=0.3,0.1

Type RM Length L Ch R = 1 ,40850   ,32,164,178
XS GIS Cut Line= 3
  2435280.5617626975516.754390332434464.589540156967009.80994587
2434370.405512426962441.66758475
#Sta/Elev= 30
       0  448.76  716.11  429.74  1349.4  440.08 2072.76  433.38 2699.91  433.36
    2719     426    2747     431 3290.84  431.23    3533  422.14 3769.76  429.88
 5470.74   426.1 5489.52     434 5607.24   429.6 5695.09   449.410021.84     449
10091.54     43210293.74     41710717.01     41510826.48     431 10925.1     434
11153.24     42811726.38     43411777.66     43011804.02     41011872.51  404.55
11922.05     40911954.41     43412248.13  436.3712308.78     447 12438.9  448.41
#Mann= 13 ,-1,0
       0    .065       0 2072.76     .08       0 2699.91     .05       0
    2747    .075       0 3290.84     .04       0 3769.76    .075       0
10021.84    .035       010091.54    .045       0 10925.1    .085       0
11726.38     .05       011954.41     .08       012248.13     .05       0
12308.78     .08       0
#XS Ineff= 2 , 0
        11726.38     434
Permanent Ineff=
       F       F
Bank Sta=11726.38,11954.41
XS Rating Curve= 0 ,0
Exp/Cntr=0.3,0.1