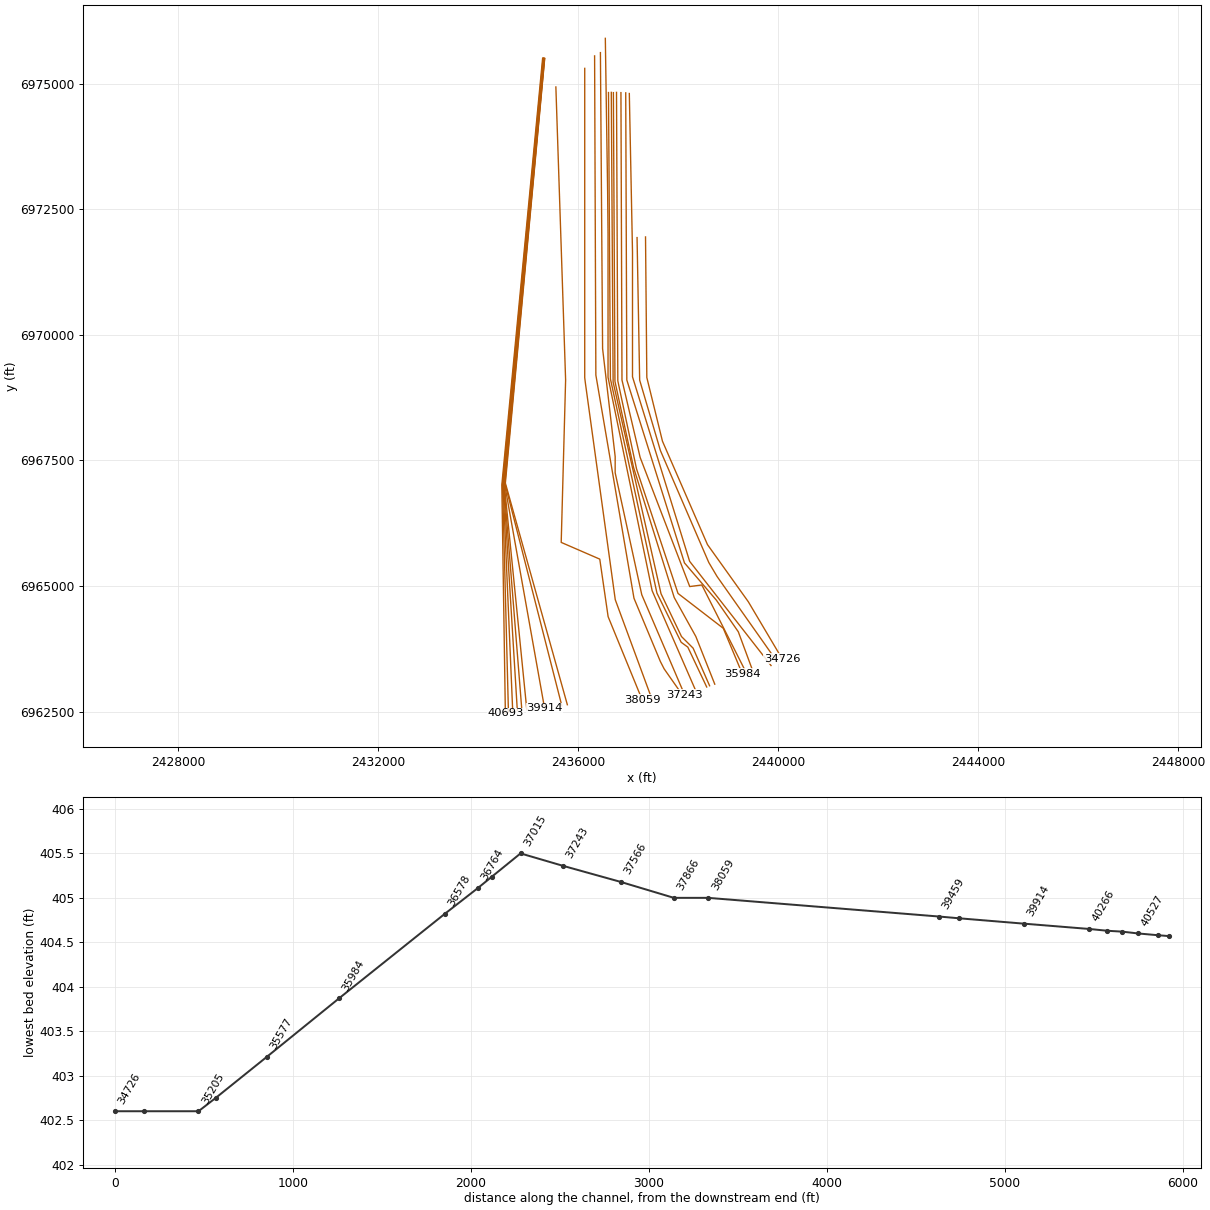
HEC-RAS study CDC_Consolidated_Model.prj: Upper Trinity CDC Consolidated Model

--- CDC_Consolidated_Model.g13 (geometry) --- (continued)

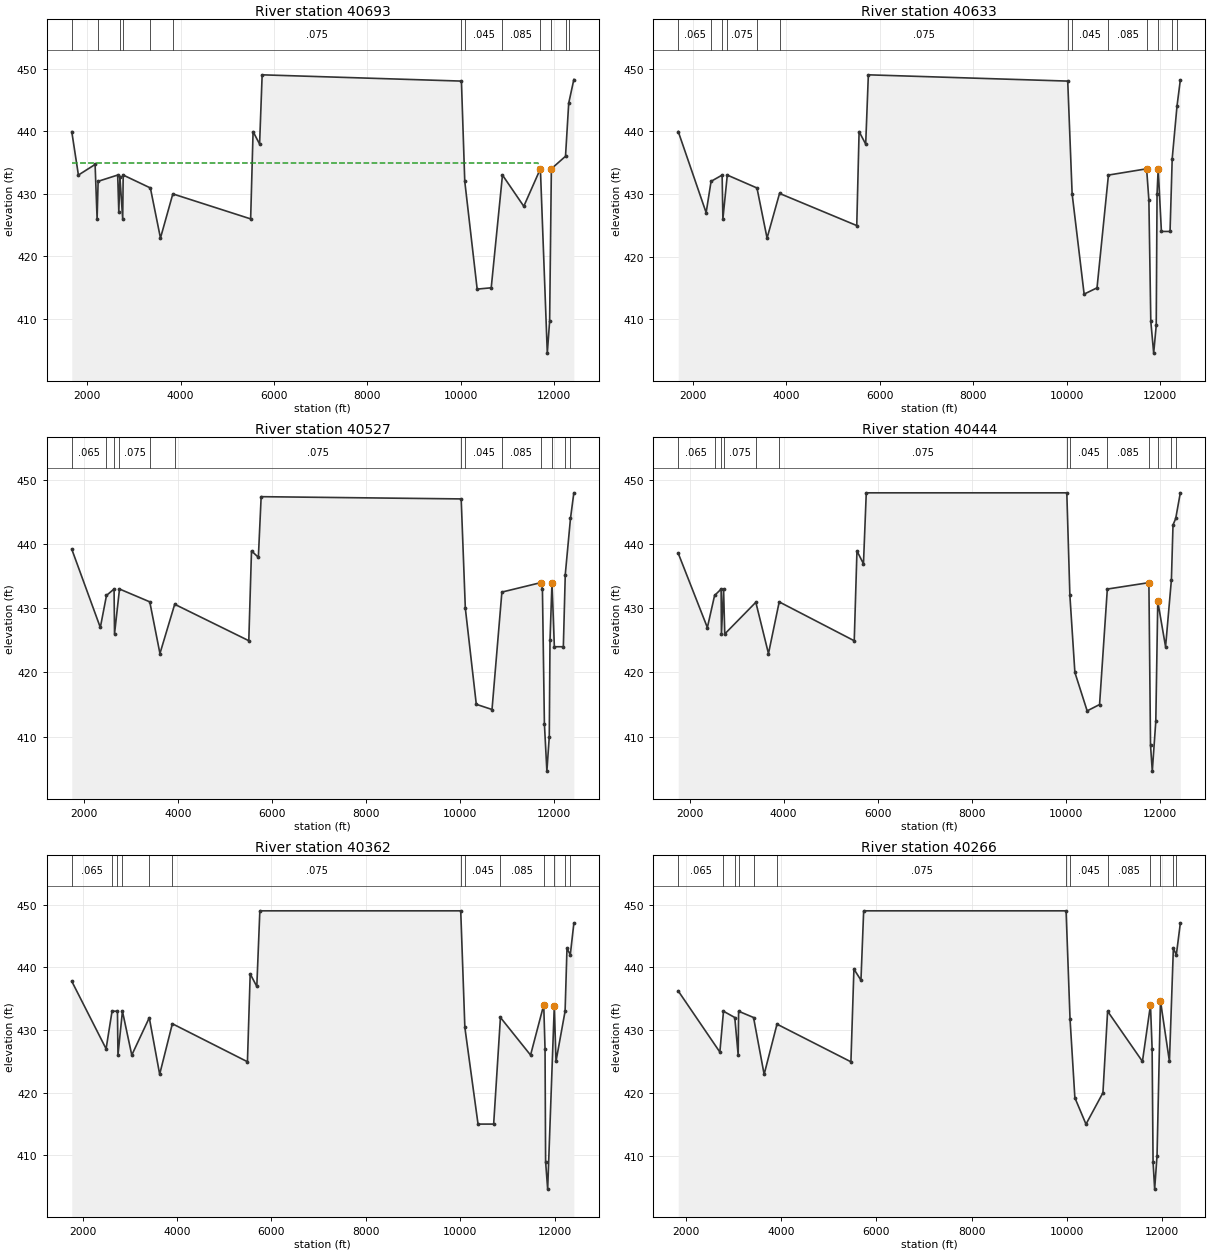
Type RM Length L Ch R = 1 ,40693   ,12,63,68
XS GIS Cut Line= 3
  2435290.1016926975511.634309312434474.129470716967013.45722598
2434545.093012366962463.18234172
#Sta/Elev= 30
    1670  439.93 1812.14     433 2169.54  434.69 2212.32     426 2234.17     432
 2653.03     433 2676.98  427.12 2700.92  432.67 2760.47     426 2770.82     433
 3353.06  430.94 3569.02  422.94  3833.7  429.99  5499.9     426 5551.96  439.94
 5691.47  437.94 5746.19     44910012.77     44810084.28     43210349.98  414.79
10650.77     41510891.76     43311348.09  428.0111703.63     43411851.56  404.57
11901.48  409.6911938.51     43412241.42     43612310.07  444.4812419.88  448.25
#Mann= 13 ,-1,0
    1670    .065       0 2234.17     .08       0 2700.92     .05       0
 2770.82    .075       0 3353.06     .04       0  3833.7    .075       0
10012.77    .035       010084.28    .045       010891.76    .085       0
11703.63     .05       011938.51     .08       012241.42     .05       0
12310.07     .08       0
#XS Ineff= 2 , 0
        11662.18     435
Permanent Ineff=
       F       F
Bank Sta=11703.63,11938.51
XS Rating Curve= 0 ,0
Exp/Cntr=0.3,0.1

Type RM Length L Ch R = 1 ,40633   ,22,112,121
XS GIS Cut Line= 3
  2435299.6123266975510.40998928 2434487.98038226967027.33707263
2434606.614641466962485.95975782
#Sta/Elev= 30
    1694  439.95 2290.53     427 2395.95     432 2632.35     433 2648.66     426
 2742.57     433 3377.01  430.94 3592.74  422.94 3859.34  430.07 5509.98  424.94
 5560.07  439.94 5701.11  437.94 5757.96     44910019.74     44810113.91     430
10370.41     41410645.94     41510889.97     43311706.15     43411754.64     429
11795.54  409.6611857.06  404.5811911.57     40911929.25     430 11953.3     434
12022.33     42412206.95     42412253.15  435.6312355.36  443.9912426.37  448.16
#Mann= 13 ,-1,0
    1694    .065       0 2395.95     .08       0 2632.35     .05       0
 2742.57    .075       0 3377.01     .04       0 3859.34    .075       0
10019.74    .035       010113.91    .045       010889.97    .085       0
11706.15     .05       0 11953.3     .09       012253.15     .05       0
12355.36     .08       0
#XS Ineff= 2 , 0
        11706.15     434
Permanent Ineff=
       F       F
Bank Sta=11706.15,11953.3
XS Rating Curve= 0 ,0
Exp/Cntr=0.3,0.1

Type RM Length L Ch R = 1 ,40527   ,17,87,95
XS GIS Cut Line= 3
  2435305.9780676975508.74621613 2434497.9485535 6967027.7566328
2434692.197685456962502.40941058
#Sta/Elev= 30
    1733  439.21 2341.23     427 2472.76     432 2634.27     433  2643.9     426
 2749.81     433 3394.86     431  3611.5  422.94 3925.91  430.62 5504.33  424.94
 5562.12  438.94 5708.17  437.94 5767.98   447.410029.35  447.0510117.64     430
10351.24  415.0210686.23  414.21 10896.6  432.5211727.33     43411760.09     433
11802.28     41211855.18   404.6 11906.3     410 11921.7     42511964.08     434
12014.43     42412205.89     42412246.95  435.26 12357.8     444 12429.6     448
#Mann= 13 ,-1,0
    1733    .065       0 2472.76     .08       0 2634.27     .05       0
 2749.81    .075       0 3394.86     .04       0 3925.91    .075       0
10029.35    .035       010117.64    .045       0 10896.6    .085       0
11727.33     .05       011964.08     .09       012246.95     .05       0
 12357.8     .08       0
#XS Ineff= 2 , 0
        11727.33     434
Permanent Ineff=
       F       F
Bank Sta=11727.33,11964.08
XS Rating Curve= 0 ,0
Exp/Cntr=0.3,0.1

Type RM Length L Ch R = 1 ,40444   ,17,85,93
XS GIS Cut Line= 3
  2435311.0778936975507.791355012434506.954629876967032.68284808
2434784.168171556962518.86629717
#Sta/Elev= 30
    1760  438.58 2379.78     427 2533.23     432 2672.55     433 2679.13     426
 2724.43     433  2749.6     426 3410.55  430.94 3679.79  422.94 3908.19     431
 5504.36  424.94 5562.23  438.94 5700.55  436.94 5760.25     44810026.44     448
10092.04     43210198.42     42010459.55  414.0110723.36     41510888.56     433
11772.99     43411807.51  408.6611845.23  404.6211919.78  412.3811961.77  431.08
12127.82     42412251.74  434.4512285.92     44312343.43     44412441.25     448
#Mann= 13 ,-1,0
    1760    .065       0 2533.23     .08       0 2672.55     .05       0
 2724.43    .075       0 3410.55     .04       0 3908.19    .075       0
10026.44    .035       010092.04    .045       010888.56    .085       0
11772.99     .05       011961.77     .09       012251.74     .05       0
12343.43     .08       0
#XS Ineff= 2 , 0
        11772.99     434
Permanent Ineff=
       F       F
Bank Sta=11772.99,11961.77
XS Rating Curve= 0 ,0
Exp/Cntr=0.3,0.1

Type RM Length L Ch R = 1 ,40362   ,19,100,108
BEGIN DESCRIPTION:
---------------------------------------------------------------------
CDC GP072315-1 IH-30 Westbound Frontage Road
Cross-sections 40362 - 40693.  Mitigation swale in ROB.
---------------------------------------------------------------------
END DESCRIPTION:
XS GIS Cut Line= 3
  2435316.358565 6975506.51097312434514.231828996967034.24534805
2434874.516840526962527.95049849
#Sta/Elev= 30
    1770  437.77 2497.34     427 2623.55     433 2738.05     433 2748.62     426
 2843.63     433 3041.39     426  3412.2  431.96 3632.22  422.94  3900.8     431
 5491.82  424.94 5550.34  438.94 5690.34  436.94 5754.68     44910010.58     449
10098.15   430.410377.16     41510708.33     41510851.66     43211490.04     426
11769.08     43411796.68     42711808.78     40911852.59  404.6311993.02  433.86
12029.02     42512221.64     43312261.65     44312331.88     44212407.07     447
#Mann= 13 ,-1,0
    1770    .065       0 2623.55     .08       0 2738.05     .05       0
 2843.63    .075       0  3412.2     .04       0  3900.8    .075       0
10010.58    .035       010098.15    .045       010851.66    .085       0
11769.08     .05       011993.02     .09       012221.64     .05       0
12331.88     .08       0
#XS Ineff= 2 , 0
        11769.08     434
Permanent Ineff=
       F       F
Bank Sta=11769.08,11993.02
XS Rating Curve= 0 ,0
Exp/Cntr=0.3,0.1

Type RM Length L Ch R = 1 ,40266   ,72,369,400
XS GIS Cut Line= 3
  2435320.0897576975506.292512432434521.514815036967039.66201472
2434973.482407636962538.86629714
#Sta/Elev= 30
    1833  436.23 2708.07  426.49 2784.41     433 3021.61     432 3093.08     426
  3102.1     433 3416.09     432 3638.88  422.94 3909.11  430.94 5463.09  424.94
 5526.23  439.72 5674.18  437.94 5731.18     449 9986.34     44910069.23   431.8
10171.08  419.2110404.73     41510760.95     42010859.21     43311591.42     425
11760.44     43411794.99     42711814.79     40911848.27  404.6511898.32     410
11970.37  434.6312158.86     42512241.47     44312304.09     44212387.59     447
#Mann= 13 ,-1,0
    1833    .065       0 2784.41     .08       0 3021.61     .05       0
  3102.1    .075       0 3416.09     .04       0 3909.11    .075       0
 9986.34    .035       010069.23    .045       010859.21    .085       0
11760.44     .05       011970.37     .09       012241.47     .05       0
12304.09     .08       0
#XS Ineff= 2 , 0
        11760.44     434
Permanent Ineff=
       F       F
Bank Sta=11760.44,11970.37
XS Rating Curve= 0 ,0
Exp/Cntr=0.3,0.1

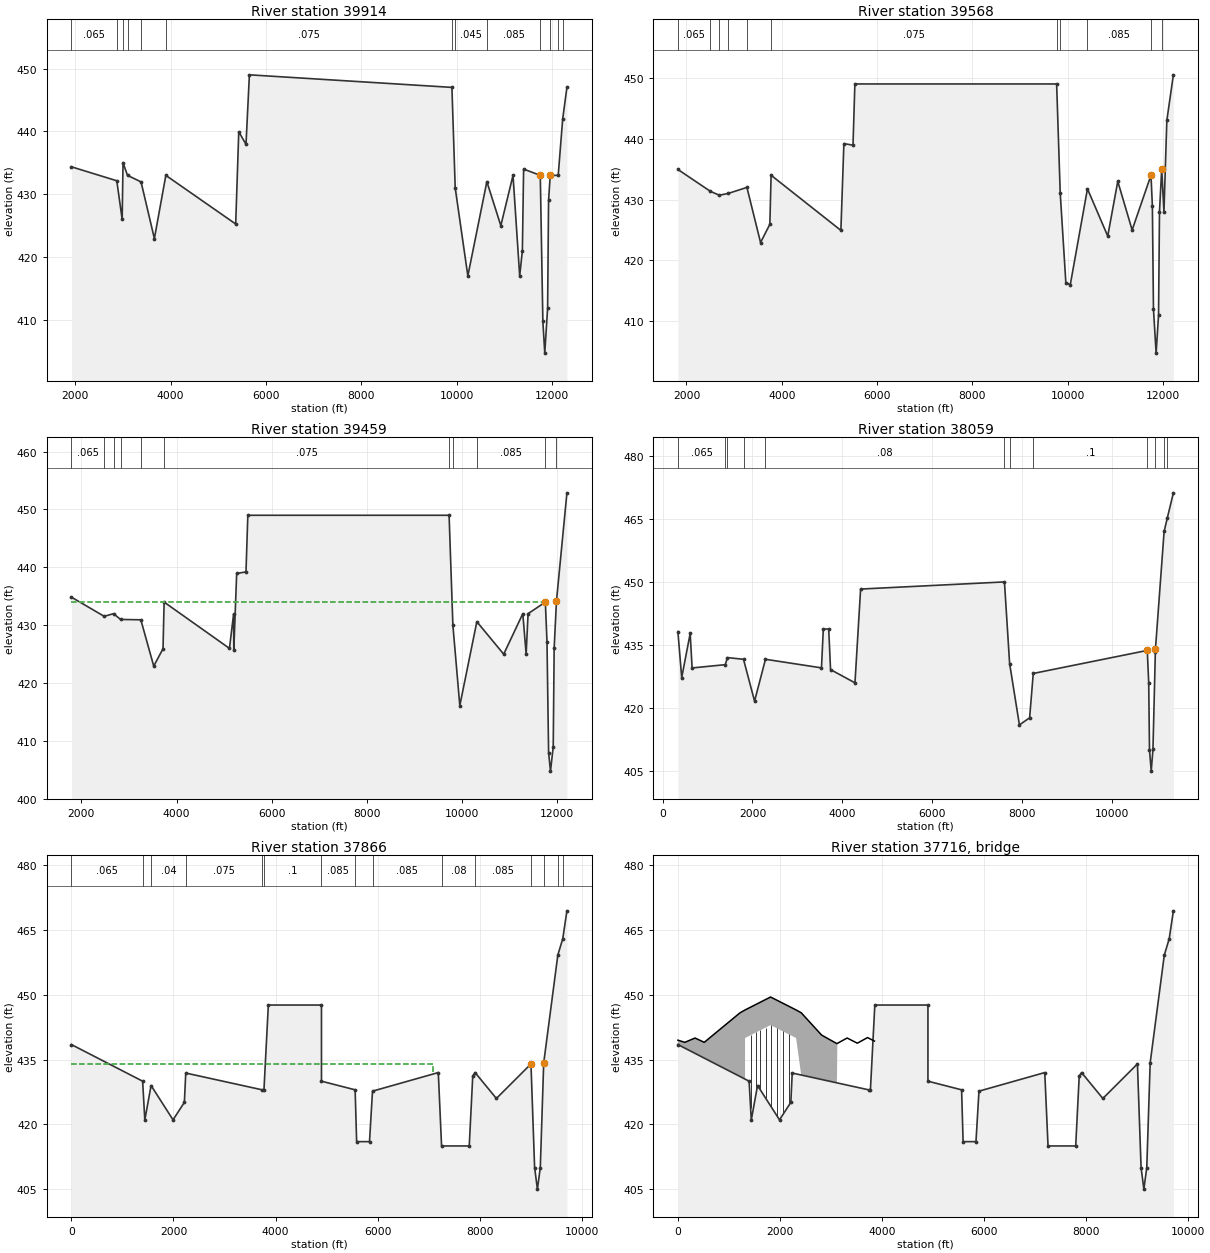
Type RM Length L Ch R = 1 ,39914   ,770,362,393
XS GIS Cut Line= 3
  2435324.4372686975505.435307562434528.321817346967040.93154599
2435329.103067376962564.00735618
#Sta/Elev= 30
    1920  434.36 2871.26  432.14  2984.1     426 3002.21     435 3096.04     433
 3380.18  431.96 3659.84  422.94 3900.19     433 5365.38  425.26 5429.85  439.94
  5581.7  437.94 5652.87     449    9901     447 9970.08     43110235.19     417
10634.12     43210926.99     425 11182.7     43311322.61     41711378.85     421
11404.99     43411754.77     433 11808.8  409.7911848.84  404.7111908.49  411.88
11928.47     42911963.39     43312130.81     43312224.97     44212313.56     447
#Mann= 13 ,-1,0
    1920    .065       0 2871.26     .08       0 3002.21     .05       0
 3096.04    .075       0 3380.18     .04       0 3900.19    .075       0
    9901    .035       0 9970.08    .045       010634.12    .085       0
11754.77     .05       011963.39     .09       012130.81     .05       0
12224.97     .08       0
#XS Ineff= 2 , 0
        11754.77     433
Permanent Ineff=
       F       F
Bank Sta=11754.77,11963.39
XS Rating Curve= 0 ,0
Exp/Cntr=0.3,0.1

Type RM Length L Ch R = 1 ,39568   ,22,114,124
XS GIS Cut Line= 3
   2435328.632876975504.561826652434536.119849776967044.36579078
2435673.815162276962615.47400838
#Sta/Elev= 30
    1820  434.95 2502.74  431.35 2688.61  430.72 2871.78     431 3268.76     432
 3554.96  422.94 3750.12  425.94 3776.22     434 5241.23  424.94 5304.13   439.2
  5495.5  438.94 5535.02     449 9770.17     449 9845.39  431.08 9963.51  416.37
10056.41     41610417.15  431.7710842.91     42411053.51     433 11355.1     425
11750.67     434 11779.8     42911802.81     41211858.47  404.7711909.44     411
11929.29     42811975.25     43512022.97     42812083.46     44312221.09   450.5
#Mann= 11 ,-1,0
    1820    .065       0 2502.74     .08       0 2688.61     .05       0
 2871.78    .075       0 3268.76     .04       0 3776.22    .075       0
 9770.17    .035       0 9845.39    .045       010417.15    .085       0
11750.67     .05       011975.25     .08       0
#XS Ineff= 2 , 0
        11750.67     434
Permanent Ineff=
       F       F
Bank Sta=11750.67,11975.25
XS Rating Curve= 0 ,0
Exp/Cntr=0.3,0.1

Type RM Length L Ch R = 1 ,39459   ,251,1297,1406
XS GIS Cut Line= 3
  2435331.6421296975504.218221352434545.059013586967048.95563455
2435784.208319136962635.11014841
#Sta/Elev= 30
    1790  434.85 2478.76  431.54 2675.31     432 2822.41     431 3248.67  430.94
 3520.09  422.94 3715.25  425.94 3738.27     434 5111.95     426 5199.39  431.95
 5203.38  425.65  5263.6  438.94 5459.52  439.22 5498.25     449 9729.32     449
 9809.03     430  9954.7  416.1210312.67  430.6110877.36     42511278.99     432
11349.19     42511389.77     43211752.86     43411787.43  427.1811821.36     408
11861.14  404.79 11918.6     40911938.03     42611986.55  434.1712206.54  452.88
#Mann= 11 ,-1,0
    1790    .065       0 2478.76     .08       0 2675.31     .05       0
 2822.41    .075       0 3248.67     .04       0 3738.27    .075       0
 9729.32    .035       0 9809.03    .045       010312.67    .085       0
11752.86     .05       011986.55     .08       0
#XS Ineff= 2 , 0
         11752.9     434
Permanent Ineff=
       F       F
Bank Sta=11752.86,11986.55
XS Rating Curve= 0 ,0
Exp/Cntr=0.3,0.1

Type RM Length L Ch R = 1 ,38059   ,710,193,200
BEGIN DESCRIPTION:
38059
END DESCRIPTION:
XS GIS Cut Line= 6
2435554.826474776974938.42010256 2435749.6282077  6969102.156369
 2435661.4889483  6965868.123467 2436432.5313695 6965535.1343036
 2436599.6320852 6964389.3009653 2437280.4043457 6962733.3626761
#Sta/Elev= 30
  342.25  438.17  426.76  427.24  615.23  437.76  658.13  429.54 1394.74  430.32
    1444     432  1800.4   431.6    2046  421.65  2288.4   431.6 3533.25  429.56
    3574   438.8    3694   438.8 3734.96  429.15 4277.66     426 4403.05   448.3
    7600     450 7714.85  430.58 7932.69     416 8159.45  417.68 8240.12  428.23
10774.35  433.7110806.32  425.9910823.78     41010862.19     405 10900.6  410.15
10954.14  433.3910955.89     43411148.62     46211221.77   465.311354.83  471.19
#Mann= 12 ,-1,0
  342.25    .065       0 1394.74     .05       0    1444     .08       0
  1800.4     .04       0  2288.4     .08       0    7600    .035       0
 7714.85    .045       0 8240.12      .1       010774.35    .055       0
10954.14    .065       011148.62     .05       011221.77    .065       0
#XS Ineff= 2 , 0
        10774.35  433.71
Permanent Ineff=
       F       F
Bank Sta=10774.35,10955.89
XS Rating Curve= 0 ,0
Exp/Cntr=0.3,0.1

Type RM Length L Ch R = 1 ,37866   ,131,300,300
BEGIN DESCRIPTION:
This cross section corresponds to cross section 37866 of the non-georeferenced CDC model which was the source of this model.
END DESCRIPTION:
XS GIS Cut Line= 6
  2436131.8889326975308.982127732436131.608093226969150.72180648
2436144.560167066969044.508764312436457.089069566966787.15730789
2436742.338827136964727.09154615 2437487.24350536962714.38231698
#Sta/Elev= 30
       0  438.48  1395.6     430 1437.89     421  1560.6     429  1991.1  421.05
  2213.1   425.1 2240.28  431.89 3737.69     428 3772.86     428 3858.86  447.64
    4900  447.64    4900     430 5559.52     428 5589.05     416 5841.23     416
 5899.89  427.69 7189.33     432 7253.33     415  7795.8     415 7864.34   431.2
 7910.54     432 8327.48     426 9005.49     434 9076.68     410  9131.5     405
 9188.45     410 9254.87  434.22 9531.91  459.22 9628.45     463 9710.02  469.46
#Mann= 15 ,-1,0
       0    .065       0  1395.6     .05       0  1560.6     .04       0
 2240.28    .075       0 3737.69    .065       0 3772.86      .1       0
    4900    .085       0 5559.52    .045       0 5899.89    .085       0
 7253.33     .08       0 7910.54    .085       0 9005.49    .055       0
 9254.87    .065       0 9531.91     .05       0 9628.45    .065       0
#XS Ineff= 2 ,-1
       0    7086     434    7086 7876.49   426.5
Permanent Ineff=
       F       T
Bank Sta=9005.49,9254.87
XS Rating Curve= 0 ,0
Exp/Cntr=0.3,0.1

Type RM Length L Ch R = 3 ,37716   ,,,
BEGIN DESCRIPTION:
Hunter Ferrell Road
END DESCRIPTION:
Node Name=Hunter Ferrell R
Bridge Culvert--1,0,-1,-1, 0
Deck Dist Width WeirC Skew NumUp NumDn MinLoCord MaxHiCord MaxSubmerge Is_Ogee
92,115,2.6,0, 17, 17, , , 0.95, 0, 0,0,,
       0     136     336   516.1  1216.1  1316.1  1316.1  1816.1  2316.1  2316.1
  2416.1  2816.1  3116.1  3316.1  3516.1  3716.1  3851.1
   439.5     439     440     439  445.83   446.5   446.5   449.5   446.5   446.5
  445.85  440.68   438.7     440   438.8   440.1  439.29
                                                     440     443     440
       0     136     336  642.15 1342.15 1442.15 1442.15 1942.15 2442.15 2442.15
 2542.15 2942.15 3242.15 3442.15 3642.15 3842.15 3977.15
   439.5     439     440     439  445.83   446.5   446.5   449.5   446.5   446.5
  445.85  440.68   438.7     440   438.8   440.1  439.29
                                                     440     443     440
Pier Skew, UpSta & Num, DnSta & Num=  ,1425.1, 2 ,1529.5, 2 , 0 , 0 , 0 ,,
       3       3
     415     443
       3       3
     415     443
Pier Skew, UpSta & Num, DnSta & Num=  ,1535.1, 2 ,1639.5, 2 , 0 , 0 , 0 ,,
       3       3
     415     443
       3       3
     415     443
Pier Skew, UpSta & Num, DnSta & Num=  ,1607.26, 2 ,1711.66, 2 , 0 , 0 , 0 ,,
       3       3
     415     443
       3       3
     415     443
Pier Skew, UpSta & Num, DnSta & Num=  ,1721.26, 2 ,1825.66, 2 , 0 , 0 , 0 ,,
       3       3
     415     443
       3       3
     415     443
Pier Skew, UpSta & Num, DnSta & Num=  ,1824, 2 ,1928.4, 2 , 0 , 0 , 0 ,,
       3       3
     415     443
       3       3
     415     443
Pier Skew, UpSta & Num, DnSta & Num=  ,1942, 2 ,2046.43, 2 , 0 , 0 , 0 ,,
       3       3
     415     443
       3       3
     415     443
Pier Skew, UpSta & Num, DnSta & Num=  ,2060, 2 ,2164.43, 2 , 0 , 0 , 0 ,,
       3       3
     415     443
       3       3
     415     443
Pier Skew, UpSta & Num, DnSta & Num=  ,2178, 2 ,2282.43, 2 , 0 , 0 , 0 ,,
       3       3
     415     443
       3       3
     415     443
Abutment Skew #Up #Dn= , 2 , 2
  1316.1  1396.1
     440     420
 1442.15 1522.15
     440     420
Abutment Skew #Up #Dn= , 2 , 2
    2236  2316.1
     420     440
 2362.15 2442.15
     420     440
BR Coef=-1 , 0 , 0 ,, 0 ,,,0.8,0,1.2,0,
WSPro=,,,, 1 ,,,, 0 ,,,, 0 ,,,,-1 ,-1 ,-1 , 0 , 0 , 0 , 0 , 0
BC Design=,, 0 ,, 0 ,,,,,,
BC Use User HTab Curves=0
BC User HTab FreeFlow(D)= 0

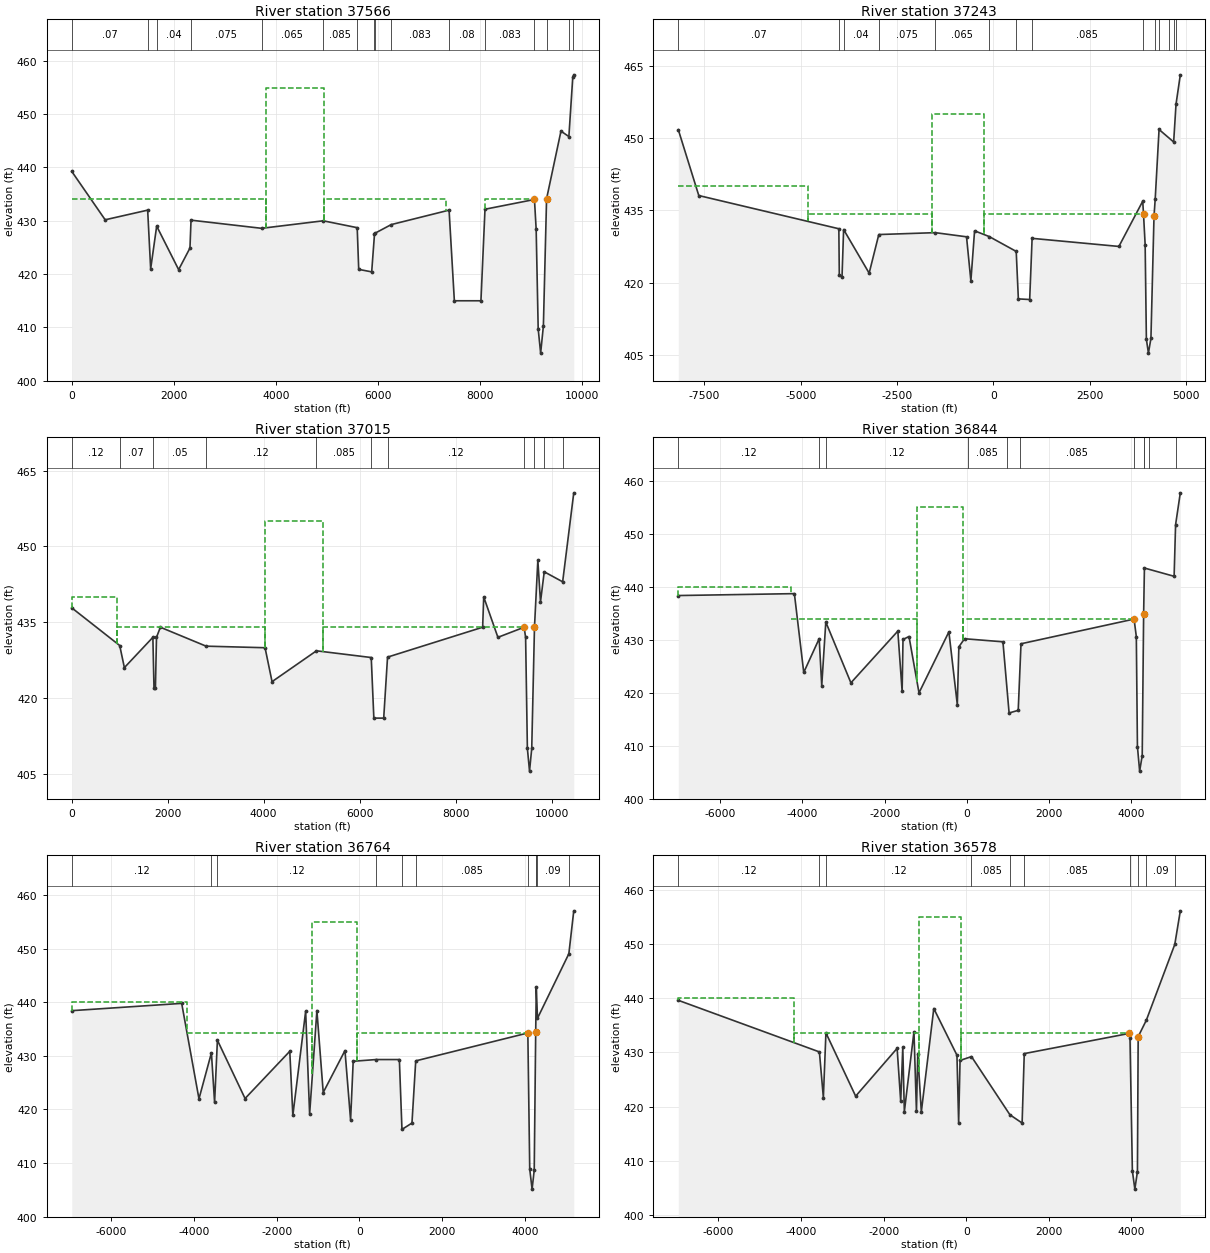
Type RM Length L Ch R = 1 ,37566   ,172,323,184
BEGIN DESCRIPTION:
---------------------------------------------------------------------
CDC IRV081607-01 Hunter Ferrell Road Improvements
Cross-section 37566 - 41697
---------------------------------------------------------------------
CDC GP083121-1 Hunter-Ferrell Industrial
Located in LOB.
CRoss-sections 37566 - 37866.
Valley storage site.
END DESCRIPTION:
XS GIS Cut Line= 6
  2436329.1844696975557.113521232436354.375036146969200.77288748
2437116.528039386964755.893981982437642.491882476963499.96211064
2437719.336873136963350.069037722438012.404856556962933.11711572
#Sta/Elev= 30
       0  439.26  654.85  430.19  1488.2     432    1547     421    1665     429
  2095.5  420.84  2317.5  424.89 2338.42  430.12 3721.44  428.59 4930.73     430
 5596.53  428.71 5626.32  420.89  5880.7  420.42 5935.55  427.48 5939.87  427.64
 6263.96  429.29    7398     432 7501.49     415 8022.82     415 8102.26  432.17
 9072.14     434 9105.54   428.4 9145.31  409.72 9193.43  405.18 9247.12  410.28
 9309.74  434.14 9591.91  446.82 9746.96   445.8 9822.88  456.88 9842.87  457.38
#Mann= 16 ,-1,0
       0     .07       0  1488.2     .05       0    1665     .04       0
 2338.42    .075       0 3721.44    .065       0 4930.73    .085       0
 5596.53     .05       0 5935.55    .071       0 5939.87    .071       0
 6263.96    .083       0    7398     .08       0 8102.26    .083       0
 9072.14    .055       0 9309.74    .065       0 9746.96     .05       0
 9822.88    .065       0
#XS Ineff= 5 ,-1
       0    3800     434    3800    4948     455    4948 7330.18     434
 7330.18 8102.26   426.5 8102.26 9072.14     434
Permanent Ineff=
       F       F       F       T       F
Bank Sta=9072.14,9309.74
XS Rating Curve= 0 ,0
Exp/Cntr=0.3,0.1

Type RM Length L Ch R = 1 ,37243   ,239,239,239
BEGIN DESCRIPTION:
With fill grading for CDC GP 070319-1.
New cross section
END DESCRIPTION:
XS GIS Cut Line= 6
  2436445.5119926975622.61470257 2436488.91479336969728.51756689
2436740.650838396967575.739720232436740.273542556967255.55302465
2437272.635994886964824.645484892438126.802593636962838.53429964
#Sta/Elev= 30
   -8178   451.7-7646.57  438.05   -4010  431.16   -3998  421.67-3928.02  421.07
-3886.03     431-3223.17  421.95-2972.23  429.96-1506.54  430.35 -694.69  429.49
 -581.71  420.36 -485.73  430.73 -105.83  429.54  595.29  426.46  651.28  416.61
  945.22  416.48  1008.2  429.17 3261.43  427.49 3880.43  436.88 3901.41  434.12
  3943.3  427.84  3975.3  408.25 4028.13  405.36  4093.3  408.41  4173.3  433.77
  4204.3   437.3  4304.3  451.75 4683.37  449.16 4744.83     457 4856.31  463.09
#Mann= 14 ,-1,0
   -8178     .07       0   -4010     .05       0-3886.03     .04       0
-2972.23    .075       0-1506.54    .065       0 -105.83    .085       0
  595.29    .045       0  1008.2    .085       0 3880.43    .055       0
  4204.3    .065       0  4304.3     .09       04551.439    .055       0
 4683.37    .055       0 4744.83    .065       0
#XS Ineff= 4 ,-1
   -8178   -4806     440   -4806 -1593.8  434.12 -1593.8  -242.6     455
  -242.6 3901.41  434.12
Permanent Ineff=
       F       F       F       F
Bank Sta=3901.41,4173.3
XS Rating Curve= 0 ,0
Exp/Cntr=0.3,0.1

Type RM Length L Ch R = 1 ,37015   ,60,160,241
BEGIN DESCRIPTION:
With fill grading for CDC GP 070319-1.
37015
END DESCRIPTION:
XS GIS Cut Line= 6
  2436543.657137 6975906.9500919 2436589.39687586972878.67826131
 2436597.85158336972023.927346142436597.682948476969156.65191273
2437479.554872396964906.894008062438355.561978646962905.79007064
#Sta/Elev= 30
       0  437.84  999.24  430.38 1096.57     426  1690.5     432 1713.73     422
 1743.65     422 1766.01     432 1846.89     434    2800  430.25 4028.45  429.94
 4174.51  423.22    5100  429.33 6241.83     428  6296.2     416  6501.7     416
  6581.7  428.08 8564.02     434 8586.23     440 8882.11     432 9428.39     434
  9459.4     432 9496.32     410    9541   405.5 9587.13     410 9644.33     434
 9714.38  447.26 9769.75  439.02 9847.71  444.9810231.52     44310463.19  460.62
#Mann= 11 ,-1,0
       0     .12       0  999.24     .07       0  1690.5     .05       0
    2800     .12       0    5100    .085       0 6241.83    .045       0
  6581.7     .12       0 9428.39    .055       0 9644.33    .065       0
 9847.71     .09       010231.52     .05       0
#XS Ineff= 4 ,-1
       0     952     440     952    4030     434    4030    5230     455
    5230 9428.39     434
Permanent Ineff=
       F       F       F       F
Bank Sta=9428.39,9644.33
XS Rating Curve= 0 ,0
Exp/Cntr=0.3,0.1

Type RM Length L Ch R = 1 ,36844   ,60,80,94
BEGIN DESCRIPTION:
With fill grading for CDC GP 070319-1.
New cross section
END DESCRIPTION:
XS GIS Cut Line= 6
  2436606.9703316974827.475872892436645.164808886969126.08701323
 2437575.76104486964858.15230764 2438060.13606036963878.98563081
2438192.948458726963782.631492812438570.552690396962988.36077164
#Sta/Elev= 30
   -7020  438.37-4195.64  438.73-3967.75  423.86-3591.93  430.24-3529.96  421.38
-3430.99  433.37 -2820.1   421.9-1678.44  431.66-1573.47  420.28-1552.48  430.08
-1406.52  430.64-1162.91  420.01 -435.88  431.52 -231.08  417.79 -193.11  428.69
  -55.24  430.22  879.36  429.64  1029.3  416.21 1251.21  416.71 1319.18  429.27
 4070.18  433.93 4125.15  430.64 4152.14  409.88 4205.91  405.24 4268.48  408.16
 4303.28  434.98  4322.2  443.56 5044.78     442 5080.76  451.74 5195.73  457.75
#Mann= 11 ,-1,0
   -7020     .12       0-3591.93    .055       0-3430.99     .12       0
33.68994    .085       0970.3198    .045       01305.189    .085       0
 4070.18    .055       04303.279    .065       0  4322.2    .055       0
4438.109     .09       0 5080.76    .065       0
#XS Ineff= 4 ,-1
   -7020 -4280.3     440 -4280.3 -1211.7  433.93 -1211.7   -82.5     455
   -82.5 4070.18  433.93
Permanent Ineff=
       F       F       F       F
Bank Sta=4070.18,4303.28
XS Rating Curve= 0 ,0
Exp/Cntr=0.3,0.1

Type RM Length L Ch R = 1 ,36764   ,165,186,136
BEGIN DESCRIPTION:
With fill grading for CDC GP 070319-1.
New cross section
END DESCRIPTION:
XS GIS Cut Line= 6
  2436663.1047336974830.890236142436699.562994056969060.05663347
2437657.09782438 6964847.04110942438066.820102056963992.87451065
2438299.111632216963761.711259072438628.538794896963013.01328139
#Sta/Elev= 30
   -6955  438.41-4296.36  439.77-3878.43  421.96-3577.48  430.53 -3500.5  421.28
-3432.51   432.9-2763.65  422.02-1682.03  430.83-1608.06  418.86-1298.17   438.3
 -1202.2  419.14-1026.23  438.43 -873.26  423.14 -347.36  430.96 -211.38  418.02
  -148.4  428.97   408.5  429.29  968.19  429.29 1031.17  416.25 1273.12  417.44
 1364.12  429.04 4075.65  434.25 4121.51  408.84 4178.36  405.11 4230.17  408.64
 4265.92  434.48 4280.01  442.77 4308.93  436.99 5067.58  449.03 5186.52  457.04
#Mann= 11 ,-1,0
   -6955     .12       0-3577.48    .055       0-3432.51     .12       0
   408.5    .085       0 1031.17    .045       0 1364.12    .085       0
 4075.65    .055       0 4265.92    .065       0 4280.01    .055       0
 4308.93     .09       0 5067.58    .065       0
#XS Ineff= 4 ,-1
   -6955 -4174.7     440 -4174.7   -1135  434.25   -1135     -50     455
     -50 4075.65  434.25
Permanent Ineff=
       F       F       F       F
Bank Sta=4075.65,4265.92
XS Rating Curve= 0 ,0
Exp/Cntr=0.3,0.1

Type RM Length L Ch R = 1 ,36578   ,75,594,598
BEGIN DESCRIPTION:
With fill grading for CDC GP 070319-1.
New cross section
END DESCRIPTION:
XS GIS Cut Line= 6
  2436704.7713166974825.681913232436736.02125446 6969075.6819303
2437108.383698726967359.37368314 2437920.98673236964770.65215456
2438353.365132636963994.43717156 2438731.83747286963044.78421523
#Sta/Elev= 30
   -6970  439.61-3554.54   430.1-3458.55   421.7-3396.56  433.61-2676.67  421.95
-1672.93  430.76-1585.95  421.01-1535.97  430.95-1497.97   419.1-1265.03  433.82
-1205.05  419.14-1173.07   429.8-1087.11  419.05 -785.26   438.1 -224.53   429.5
 -183.55  416.98 -149.57  428.53  127.29  429.24  1057.9  418.52 1352.85     417
 1404.85  429.79 3951.51  433.52 3964.45  432.73  4022.2  408.18 4082.16  404.82
 4144.67  408.05 4162.59  432.91 4360.45  435.95 5048.93  449.91 5182.83   456.1
#Mann= 10 ,-1,0
   -6970     .12       0-3554.54    .055       0-3396.56     .12       0
  127.29    .085       0  1057.9    .045       0 1404.85    .085       0
 3964.45    .055       0 4162.59    .065       0 4360.45     .09       0
 5048.93    .065       0
#XS Ineff= 4 ,-1
   -6970   -4160     440   -4160   -1146  433.52   -1146-115.669     455
-115.669 3951.51  433.52
Permanent Ineff=
       F       F       F       F
Bank Sta=3951.51,4162.59
XS Rating Curve= 0 ,0
Exp/Cntr=0.3,0.1

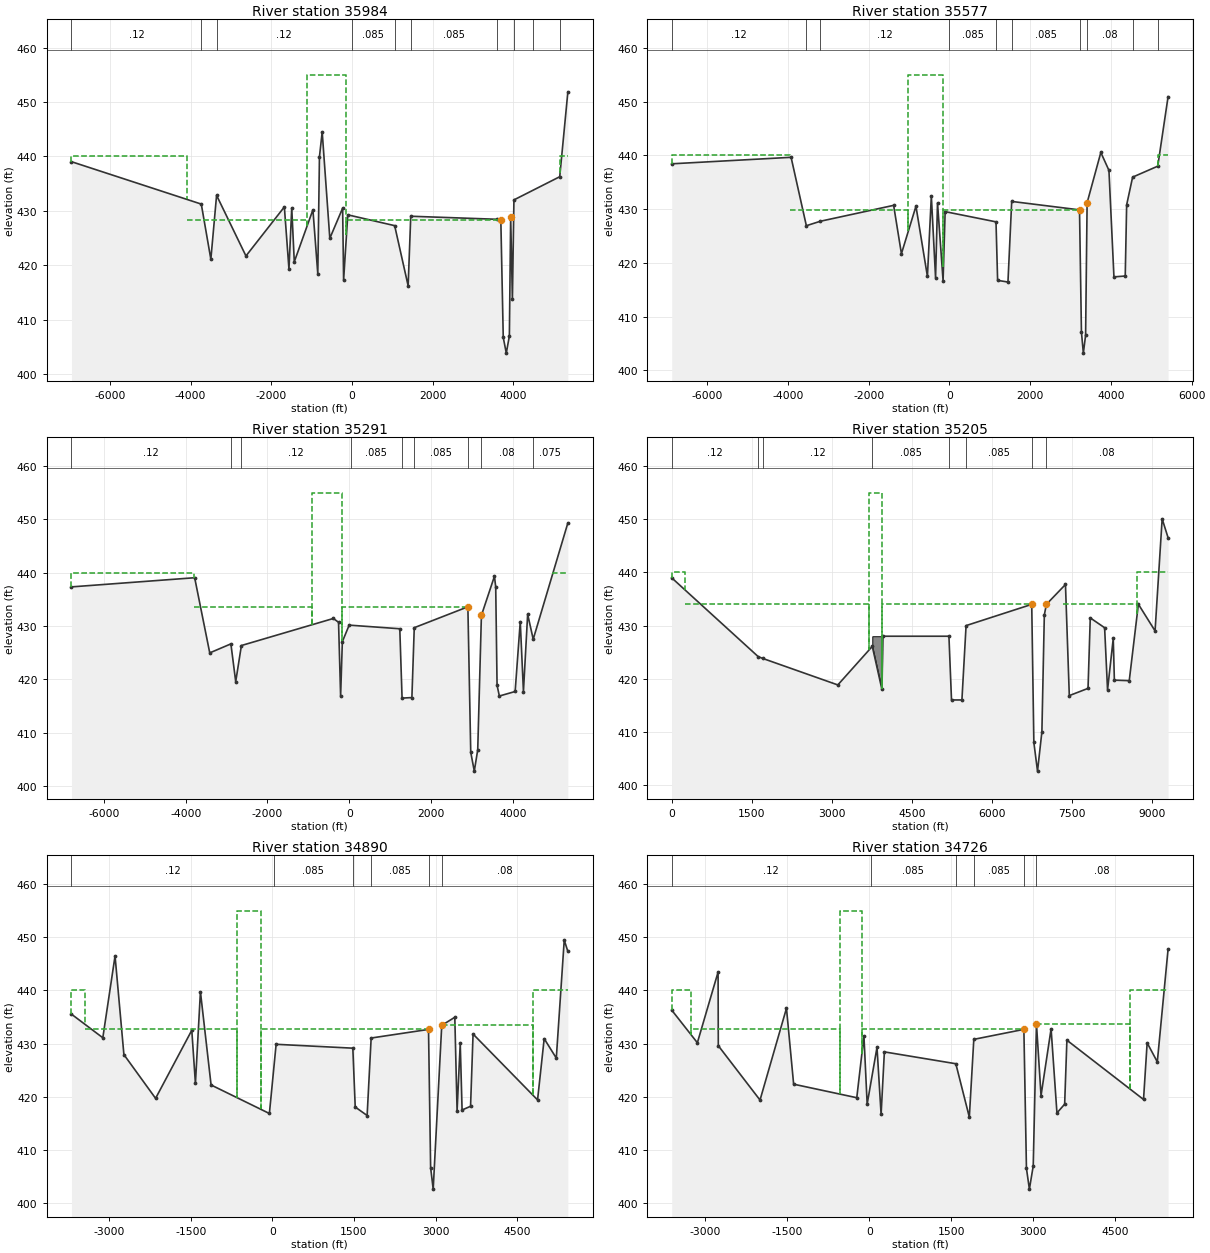
Type RM Length L Ch R = 1 ,35984   ,212,407,104
BEGIN DESCRIPTION:
With fill grading for CDC GP 070319-1.
New cross section
END DESCRIPTION:
XS GIS Cut Line= 6
  2436767.2711916974830.890236142436793.312806556969086.09857614
2437167.716913396967332.402280392437996.941632886964851.81537805
2438901.889626136964157.804955072439283.834072226963248.08269314
#Sta/Elev= 30
   -6953  439.04 -3735.6  431.25-3498.61  421.12-3356.61  432.86-2628.63  421.72
-1676.68  430.73-1562.69  419.32-1493.69  430.54-1430.69  420.65 -968.81  430.21
 -847.87  418.43 -806.89  439.94 -738.92   444.5 -550.01  424.96 -232.15  430.51
 -208.16  417.28 -105.21  429.28 1057.32  427.29 1391.27  416.24 1456.27  429.02
 3591.89  428.46 3688.88  428.28  3748.8  406.75 3824.01  403.87 3900.59  407.03
 3932.53  428.87 3975.44  413.75 4013.37  432.02 5148.48  436.28 5350.42  451.88
#Mann= 10 ,-1,0
   -6953     .12       0 -3735.6    .055       0-3356.61     .12       0
-.259765    .085       0 1057.32    .045       0 1456.27    .085       0
 3591.89    .055       0 4013.37    .065       04492.689     .09       0
 5148.48    .065       0
#XS Ineff= 6 ,-1
   -6953 -4088.2     440 -4088.2 -1109.8  428.28 -1109.8  -137.5     455
  -137.5 3688.88  428.28 3932.53  5158.2  428.87  5158.2 5350.42     440
Permanent Ineff=
       F       F       F       F       F       F
Bank Sta=3688.88,3932.53
XS Rating Curve= 0 ,0
Exp/Cntr=0.3,0.1

Type RM Length L Ch R = 1 ,35577   ,111,286,145
BEGIN DESCRIPTION:
With fill grading for CDC GP 070319-1.
New cross section
END DESCRIPTION:
XS GIS Cut Line= 6
  2436855.8130096974825.68191323 2436876.6463013 6969101.7235449
2437239.836847896967560.712191222438231.316492216964988.96831898
2438473.674275226965020.128689722439366.733184646963261.53771873
#Sta/Elev= 30
   -6876  438.44 -3919.3  439.65-3541.37  426.92-3195.43  427.75-1380.06  430.71
-1187.14  421.71 -827.31  430.55 -543.45  417.48 -446.49  432.44 -341.55  417.22
 -293.57  431.16 -155.64  416.69 -104.66  429.54 1154.82  427.64  1194.8  416.75
 1450.76  416.44 1543.76  431.44 3222.59  429.87 3270.57  407.11 3317.84  403.21
 3373.52  406.55 3411.02   431.2 3750.67  440.55 3951.49  437.22 4075.38   417.4
  4355.1  417.56 4390.06   430.8 4537.77  435.96 5160.15     438 5415.94  450.93
#Mann= 10 ,-1,0
   -6876     .12       0-3541.37    .055       0-3195.43     .12       0
1.290039    .085       0 1154.82    .045       0 1543.76    .085       0
 3222.59    .055       0 3411.02     .08       0 4537.77     .09       0
 5160.15     .08       0
#XS Ineff= 6 ,-1
   -6876 -3950.2     440 -3950.2 -1017.1  429.87 -1017.1 -145.48     455
 -145.48 3222.59  429.87 3411.02  5156.9   431.2  5156.95415.939     440
Permanent Ineff=
       F       F       F       F       F       F
Bank Sta=3222.59,3411.02
XS Rating Curve= 0 ,0
Exp/Cntr=0.3,0.1

Type RM Length L Ch R = 1 ,35291   ,119,97,213
BEGIN DESCRIPTION:
With fill grading for CDC GP 070319-1.
New cross section
END DESCRIPTION:
XS GIS Cut Line= 6
   2436951.516236974821.124507652436973.217630486969102.80851647
2438125.992555896965459.743624152438764.013261476964717.55613214
2439202.381479226964088.215855392439497.520324636963293.94513422
#Sta/Elev= 30
   -6793  437.34-3780.83  439.06-3411.87  424.95-2894.91  426.64-2776.92  419.55
-2637.94  426.33 -389.44  431.41 -262.49   430.7  -211.5  416.85 -169.52  427.05
   -2.58  430.16 1235.23  429.48 1291.23  416.46 1531.23  416.56 1589.23  429.68
  2900.3   433.6 2970.29  406.29 3057.21  402.75 3141.25  406.75 3231.23  431.99
 3550.17  439.33 3581.16  437.31 3614.15  418.87 3670.14  416.85 4056.13   417.7
 4181.12  430.81 4259.12  417.69 4362.12  432.21 4498.04  427.51 5345.59  449.35
#Mann= 9 ,-1,0
   -6793     .12       0-2894.91    .055       0-2637.94     .12       0
30.41016    .085       0 1291.23    .045       0 1589.23    .085       0
  2900.3     .05       0 3231.23     .08       04485.061    .075       0
#XS Ineff= 6 ,-1
   -6793 -3804.1     440 -3804.1  -912.7   433.6  -912.7-167.399     455
-167.399  2900.3   433.6 3231.23  4973.2  431.99  4973.2 5345.59     440
Permanent Ineff=
       F       F       F       F       F       F
Bank Sta=2900.3,3231.23
XS Rating Curve= 0 ,0
Exp/Cntr=0.3,0.1

Type RM Length L Ch R = 1 ,35205   ,267,305,178
BEGIN DESCRIPTION:
35205
END DESCRIPTION:
XS GIS Cut Line= 6
  2437023.3251416974807.811870232437086.948046066971651.66234264
2437087.070093056969165.970791732437702.065254146967187.41602181
2438229.261050136965491.521775812439856.698083976963416.27362972
#Sta/Elev= 30
       0     439 1621.39  424.16 1703.39  423.83 3113.89  418.83    3760  426.09
 3940.26     418 3952.48     428  5196.6     428 5244.83     416 5439.96     416
 5518.02     430 6748.51     434 6788.34     408    6857   402.6 6938.95     410
 6984.78     432 7023.02     434 7380.88  437.74 7452.87  416.82  7803.8  418.18
 7845.79  431.45  8114.7   429.6 8169.68   417.9 8276.64  427.58 8297.64  419.73
 8576.54  419.63 8747.49  434.03 9060.37     429 9193.33   450.1 9304.29  446.55
#Mann= 8 ,-1,0
       0     .12       0 1621.39    .055       0 1703.39     .12       0
    3760    .085       0  5196.6    .045       0 5518.02    .085       0
 6748.51    .055       0 7023.02     .08       0
#XS Ineff= 6 ,-1
       0     250     440     250    3706     434    3706    3938     455
    3938 6748.51     434 7334.89    8725     434    8725 9304.29     440
Permanent Ineff=
       F       T       F       F       F       F
#Block Obstruct= 1 ,-1
    3760    3953     428
Bank Sta=6748.51,7023.02
XS Rating Curve= 0 ,0
Exp/Cntr=0.3,0.1

Type RM Length L Ch R = 1 ,34890   ,120,164,157
BEGIN DESCRIPTION:
New cross section
END DESCRIPTION:
XS GIS Cut Line= 6
  2437178.0784416971938.746086062437230.161998476969100.20419098
2437644.658544816967697.86053897 2438612.10346036965468.42438106
2438777.034232816965190.646393312439974.950800236963497.93816456
#Sta/Elev= 30
   -3696  435.54 -3119.7   431.1-2894.78   446.5-2731.84  427.93-2149.03  419.69
-1483.25  432.51-1416.28  422.49-1324.31  439.77-1128.39  422.21  -55.89  416.84
   68.05  429.87 1478.85  429.14 1522.85  418.06 1741.85  416.46 1815.85  431.05
 2870.93  432.67 2909.81  406.64    2957   402.6 3114.18  433.43 3354.46  434.96
 3396.42  417.38 3454.39  430.05 3488.37   417.5 3644.29   418.2 3690.26   431.8
 4876.58   419.4 4998.49  430.93 5221.37  427.27 5367.22  449.48 5434.17  447.36
#Mann= 6 ,-1,0
   -3696     .12       025.07007    .085       0 1478.85    .045       0
 1815.85    .085       0 2870.93    .055       0 3114.18     .08       0
#XS Ineff= 6 ,-1
   -3696 -3454.7     440 -3454.7-649.399  432.67-649.399    -219     455
    -219 2870.93  432.67 3114.18  4796.7  433.43  4796.7 5434.17     440
Permanent Ineff=
       F       F       F       F       F       F
Bank Sta=2870.93,3114.18
XS Rating Curve= 0 ,0
Exp/Cntr=0.3,0.1

Type RM Length L Ch R = 1 ,34726   ,23,468,565
BEGIN DESCRIPTION:
New cross section
END DESCRIPTION:
XS GIS Cut Line= 6
  2437347.3494286971951.766729312437373.391042726969152.28774823
2437685.989498886967883.628868222438586.061845726965824.32721256
2439402.034295146964687.174303142440079.117586646963550.02139373
#Sta/Elev= 30
   -3615  436.31-3145.47  430.16-2766.52  443.47-2762.52   429.6-1999.63  419.37
-1515.69  436.65-1384.71  422.36 -229.99  419.81  -99.04  431.44  -40.06   418.6
  139.88   429.3  214.86  416.66  274.83  428.44 1581.49  426.21 1828.42  416.16
  1910.4   430.8 2826.16  432.68 2873.15   406.5    2927   402.6 2997.14  406.97
 3056.14  433.73 3139.93  420.21 3323.91  432.78  3430.9  416.94 3571.89   418.6
 3612.89  430.64 5014.43  419.48  5080.6  430.14 5266.43  426.56 5463.41  447.78
#Mann= 6 ,-1,0
   -3615     .12       030.91992    .085       0 1581.49    .045       0
  1910.4    .085       0 2826.16    .055       0 3056.14     .08       0
#XS Ineff= 6 ,-1
   -3615 -3260.6     440 -3260.6    -530  432.68    -530  -136.6     455
  -136.6 2826.16  432.68 3056.14  4775.9  433.73  4775.9 5463.41     440
Permanent Ineff=
       F       F       F       F       F       F
Bank Sta=2826.16,3056.14
XS Rating Curve= 0 ,0
Exp/Cntr=0.3,0.1