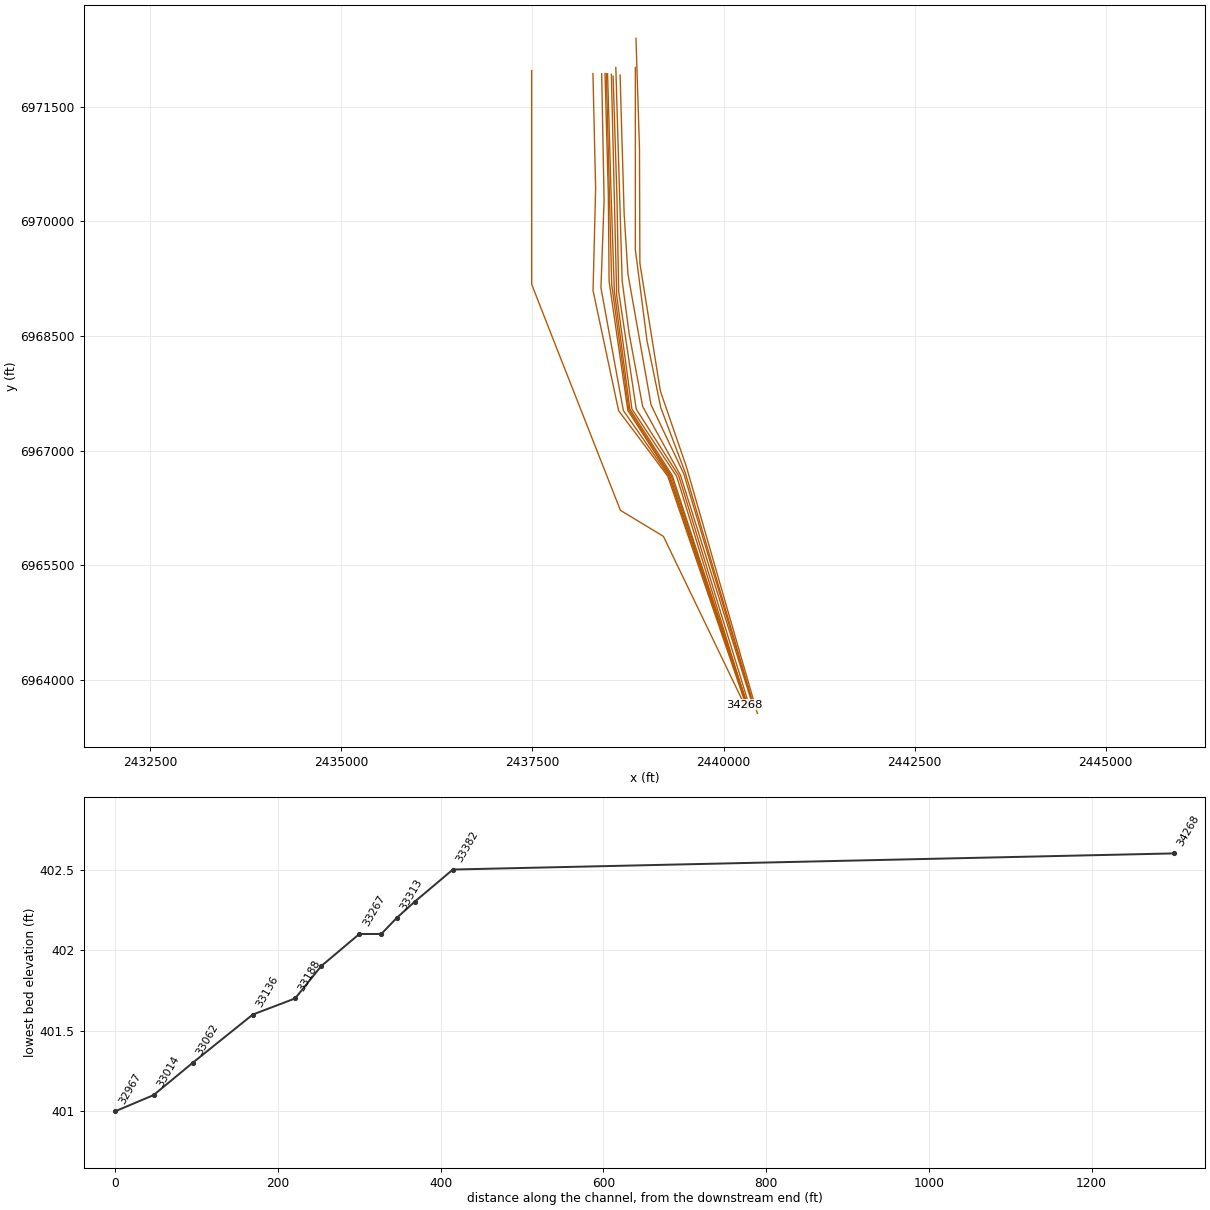
HEC-RAS study CDC_Consolidated_Model.prj: Upper Trinity CDC Consolidated Model

--- CDC_Consolidated_Model.g13 (geometry) --- (continued)

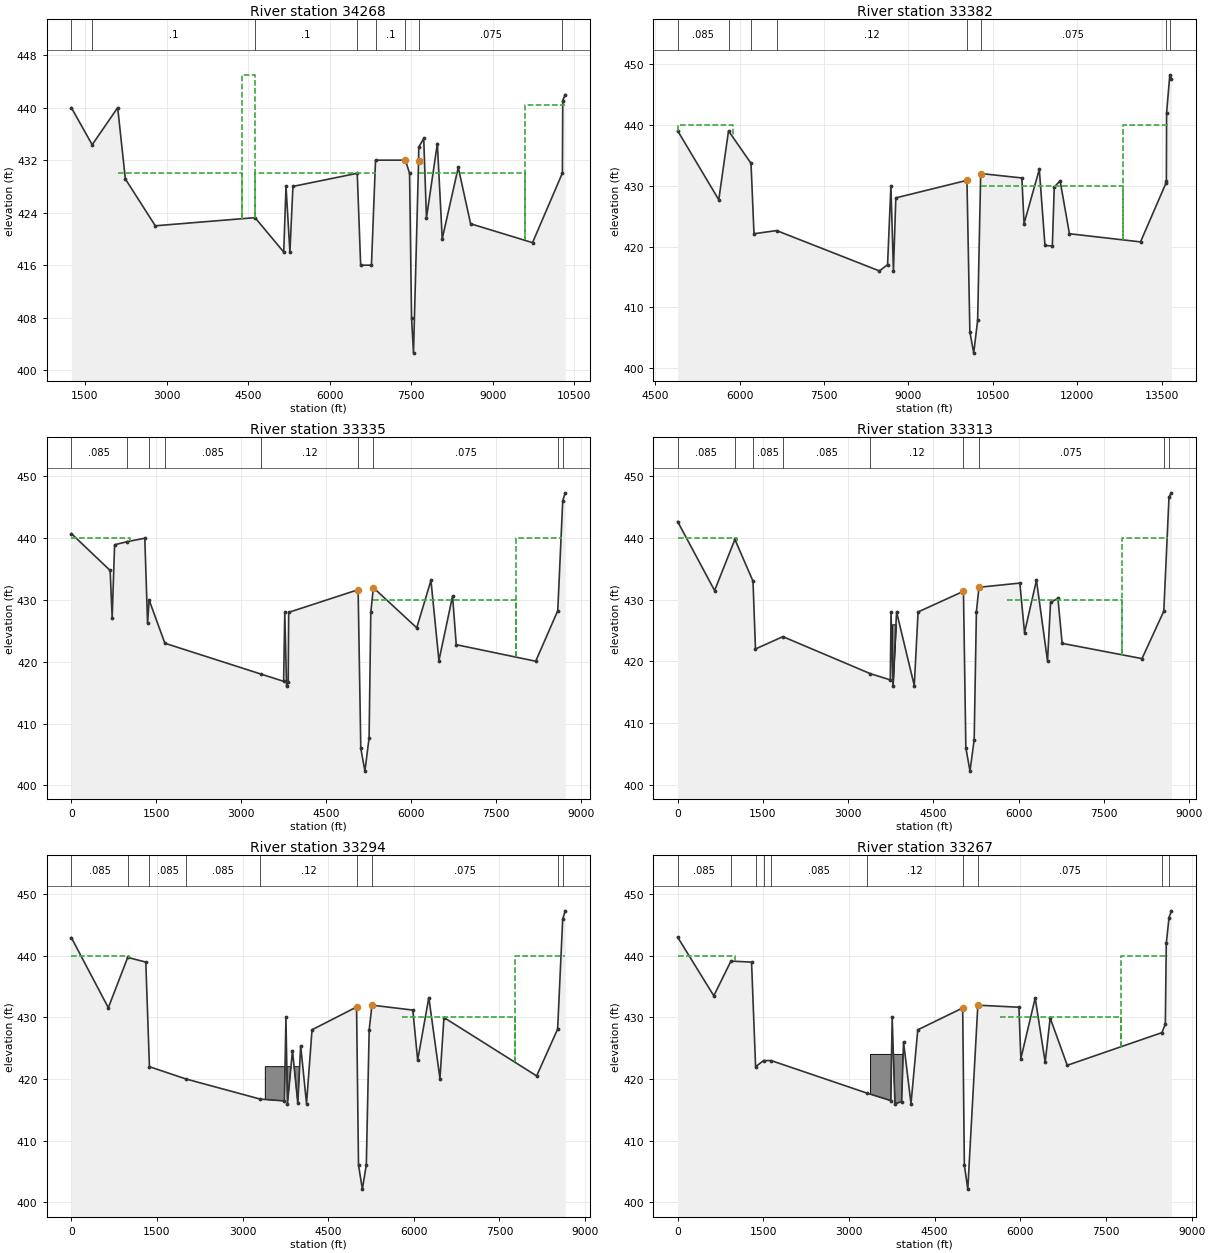
Type RM Length L Ch R = 1 ,34268   ,660,886,300
BEGIN DESCRIPTION:
STATIONS 7543-7573 ADDED FROM EFFECTIVE SECTION
FOR FLOWLINE
END DESCRIPTION:
XS GIS Cut Line= 6
  2437489.2313626971974.344768152437489.392779226969177.58034857
 2437700.49504736968636.177888072438650.537110466966217.65286948
2439213.273845886965876.417987642440272.360966556963674.98177373
#Sta/Elev= 30
    1249     440 1632.15  434.35 2101.28     440 2242.11  429.14 2793.01     422
 4627.69  423.24 5155.75     418 5197.43     428 5269.62     418 5325.11     428
 6507.97     430    6571     416 6769.38     416 6844.63     432 7393.73     432
 7470.61     430 7506.88     408    7543   402.6 7636.07  431.81 7639.87     434
 7730.86   435.3 7781.41   423.2 7981.54  434.53 8071.49  420.02 8366.35  430.89
 8593.24  422.31 9732.67  419.4310281.94 430.03510288.54  441.0810333.35     442
#Mann= 8 ,-1,0
    1249     .12       0 1632.15      .1       0 4627.69      .1       0
 6507.97    .045       0 6844.63      .1       0 7393.73    .055       0
 7639.87    .075       010281.94     .05       0
#XS Ineff= 6 ,-1
    1249 2101.28     440 2101.28    4389     430 4389.04 4626.26     445
 4626.26    6844     430    7639    9600     430    960010326.63 440.463
Permanent Ineff=
       F       F       T       F       F       F
Bank Sta=7393.73,7636.07
XS Rating Curve= 0 ,0
Exp/Cntr=0.3,0.1

Type RM Length L Ch R = 1 ,33382   ,56,47,10
BEGIN DESCRIPTION:
33382
END DESCRIPTION:
XS GIS Cut Line= 6
  2438291.2596136971935.470830142438326.285462386970426.81308632
2438292.569322476969094.10052864 2438626.77075386967522.91994397
2439270.00011039 6966664.41313082440310.726375396963618.04455164
#Sta/Elev= 30
    4895  439.03 5626.66  427.69  5799.9     439 6199.87  433.68 6253.14  422.11
 6654.71  422.63 8482.86     416 8628.25  417.03  8687.4  429.99 8732.44     416
 8775.09     42810039.77  430.8810091.57     406   10160   402.510229.52  407.87
10283.96     43211016.26  431.2711055.24  423.7811326.15  432.6811427.12  420.18
11558.08   420.111592.06  429.7811696.03   430.811861.92  422.1113125.92  420.77
13580.27430.456313585.75  430.8413589.74     44213647.01  448.2113676.11   447.6
#Mann= 8 ,-1,0
    4895    .085       0  5799.9      .1       0 6199.87    .085       0
 6654.71     .12       010039.77    .055       010283.96    .075       0
13580.27     .05       013647.01    .075       0
#XS Ineff= 4 ,-1
    4895 5874.95     440    6137    9895     430   1028312823.14     430
12823.14   13636     440
Permanent Ineff=
       T       F       F       F
Bank Sta=10039.77,10283.96
XS Rating Curve= 0 ,0
Exp/Cntr=0.3,0.1

Type RM Length L Ch R = 1 ,33335   ,55,22,13
BEGIN DESCRIPTION:
33335
END DESCRIPTION:
XS GIS Cut Line= 6
  2438405.4798576971935.231329312438437.076579396970272.24712248
 2438395.84405036969130.753998642438688.812624476967524.85104248
2439284.515829386966668.731363642440320.431736566963618.92676772
#Sta/Elev= 30
       0  440.75  685.59  434.78  721.21  427.12  764.15  438.94  987.68  439.45
 1297.84     440 1346.95  426.21 1373.92  430.01    1653     423 3354.07     418
 3751.43  416.84 3771.72     428 3803.44     416  3832.1   416.7 3840.67     428
 5068.05  431.67 5115.05     406    5188   402.3 5261.81   407.7 5291.99     428
 5337.17     432 6104.16   425.5 6355.08  433.18 6496.06  420.19 6737.02  430.64
 6802.01  422.77 8206.53  420.09 8596.03  428.27 8683.95  446.05 8727.41  447.35
#Mann= 9 ,-1,0
       0    .085       0  987.68      .1       0 1373.92    .085       0
    1653    .085       0 3354.07     .12       0 5068.05    .055       0
 5337.17    .075       0 8596.03     .05       0 8683.95    .075       0
#XS Ineff= 4 ,-1
       0 1042.63     440    1288    4867     430    5337    7857     430
    7857    8667     440
Permanent Ineff=
       T       F       F       F
Bank Sta=5068.05,5337.17
XS Rating Curve= 0 ,0
Exp/Cntr=0.3,0.1

Type RM Length L Ch R = 1 ,33313   ,50,19,13
BEGIN DESCRIPTION:
33313
STATIONS 1060-1532 2009 CGP TOPOGRAPHY
END DESCRIPTION:
XS GIS Cut Line= 6
  2438449.0834456971937.828765062438492.486245476970352.54223748
2438502.251973976969218.644570892438747.477533396967524.85104248
2439295.437723556966671.986606482440324.843145066963618.92676772
#Sta/Elev= 30
       0  442.66  650.49  431.47 1007.64  439.76    1326     433    1370     422
 1852.02     424 3390.11     418 3742.22  416.99  3754.7     428 3788.34     416
 3852.63     428 4163.98  416.06 4230.62     428 5029.25  431.35 5071.39     406
    5144   402.2  5217.9   407.3 5256.99     428 5302.07     432 6020.97  432.68
 6103.89  424.65 6313.68  433.14 6508.54  420.04 6561.51  429.55 6691.44  430.21
 6765.41  422.91 8170.51  420.44 8554.25  428.12 8645.86  446.65 8689.03  447.31
#Mann= 9 ,-1,0
       0    .085       0 1007.64      .1       0    1326    .085       0
 1852.02    .085       0 3390.11     .12       0 5029.25    .055       0
 5302.07    .075       0 8554.25     .05       0 8645.86    .075       0
#XS Ineff= 4 ,-1
       0 1040.76     440    1325    4795     430    5795 7812.07     430
 7812.07    8627     440
Permanent Ineff=
       T       F       F       F
#Block Obstruct= 1 ,-1
    3770    3839     426
Bank Sta=5029.25,5302.07
XS Rating Curve= 0 ,0
Exp/Cntr=0.3,0.1

Type RM Length L Ch R = 1 ,33294   ,42,27,25
BEGIN DESCRIPTION:
33294
STATIONS 1041-1614 2009 CGP TOPOGRAPHY
END DESCRIPTION:
XS GIS Cut Line= 6
  2438466.3977146971932.283172472438536.901182896969172.12694739
2438759.470619636967536.536714642439148.939656976966922.79351956
2439316.339584636966666.023363812440325.204364816963620.20858932
#Sta/Elev= 30
       0  442.98  647.85  431.58  987.02  439.76 1304.11     439    1368     422
    2008     420  3310.3  416.73 3732.68  416.43 3759.42     430 3786.24     416
 3874.24   424.6  3967.7  416.06 4017.49  425.41  4120.3     416 4216.51     428
 4996.94   431.7 5030.93     406  5098.5   402.1 5167.67  406.06 5217.83     428
  5266.5     432 5982.48   431.2  6067.4  423.05 6262.85  433.24 6457.91  420.07
 6527.91  429.99  8151.9   420.5  8519.5  428.11 8608.24  445.98 8651.96  447.33
#Mann= 9 ,-1,0
       0    .085       0  987.02      .1       0    1368    .085       0
    2008    .085       0  3310.3     .12       0 4996.94    .055       0
  5266.5    .075       0  8519.5     .05       0 8608.24    .075       0
#XS Ineff= 4 ,-1
       0 1008.91     440    1322    4814     430    5795 7771.64     430
 7771.64 8651.96     440
Permanent Ineff=
       T       F       F       F
#Block Obstruct= 1 ,-1
    3398    4017     422
Bank Sta=4996.94,5266.5
XS Rating Curve= 0 ,0
Exp/Cntr=0.3,0.1

Type RM Length L Ch R = 1 ,33267   ,42,47,25
BEGIN DESCRIPTION:
33267
STATIONS 1027-1778 2009 CGP TOPOGRAPHY
END DESCRIPTION:
XS GIS Cut Line= 6
  2438482.6266856971933.408498322438526.897593986970412.57525389
2438571.168174716969087.054282892438774.293424646967542.78342131
2439328.980635466966672.991853822440325.725689226963620.69152798
#Sta/Elev= 30
       0  443.06  633.43  433.53  932.94  439.17 1294.16     439    1365     422
    1505     423    1636     423 3311.17  417.72 3732.06  416.49    3756     430
 3804.84     416  3921.5   416.3 3954.56     426 4085.74     416  4204.4     428
 4990.42  431.55 5019.67     406    5080   402.1 5255.59     432 5974.91  431.67
 6008.66  423.31 6259.84  433.17 6434.59  422.72 6521.96  429.92 6820.79  422.23
    8478  427.54 8538.01  428.93 8554.67  442.03 8602.72  446.25 8645.26  447.34
#Mann= 10 ,-1,0
       0    .085       0  932.94      .1       0    1365    .085       0
    1505    .085       0    1636    .085       0 3311.17     .12       0
 4990.42    .055       0 5255.59    .075       0    8478     .05       0
 8602.72    .075       0
#XS Ineff= 4 ,-1
       0  997.87     440    1301    4782     430    5645 7760.12     430
 7760.12    8580     440
Permanent Ineff=
       T       F       F       F
#Block Obstruct= 1 ,-1
    3378    3953     424
Bank Sta=4990.42,5255.59
XS Rating Curve= 0 ,0
Exp/Cntr=0.3,0.1

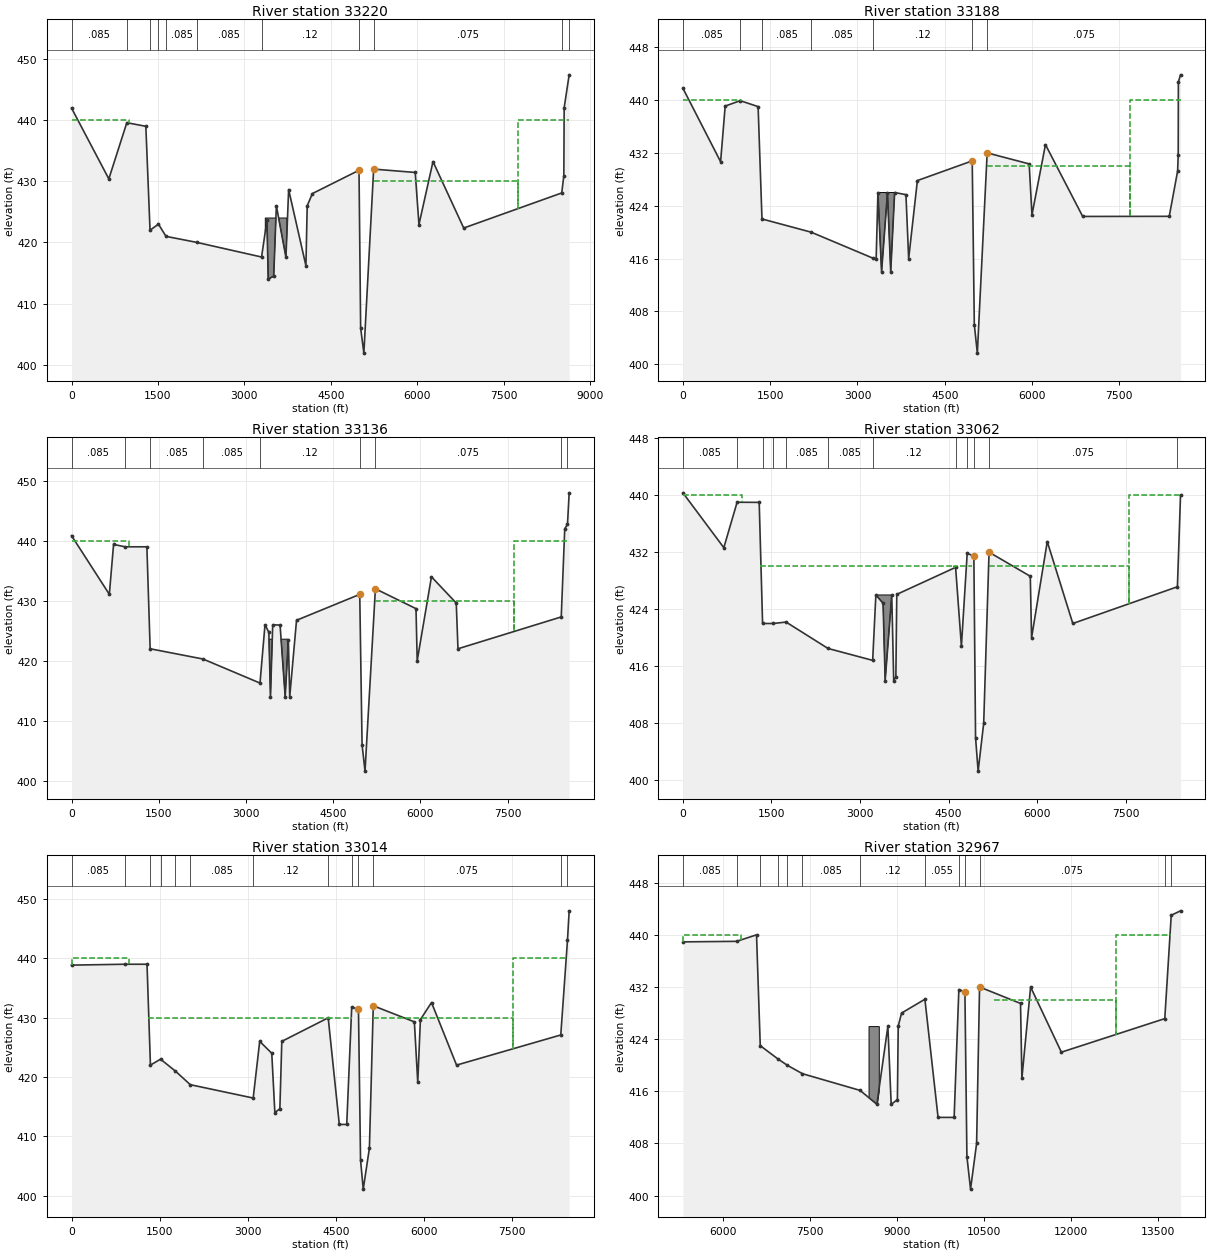
Type RM Length L Ch R = 1 ,33220   ,63,32,20
BEGIN DESCRIPTION:
33220
STATIONS 1018-1847 2009 CGP TOPOGRAPHY
END DESCRIPTION:
XS GIS Cut Line= 6
   2438532.237156971926.218223972438601.681565146969031.25321339
2438801.33438106 6967542.53768692439387.271857476966661.46136506
2440174.614442886964094.320830062440326.789663466963622.57078931
#Sta/Elev= 30
       0  441.98  647.03   430.4  959.21  439.59 1289.39     439    1362     422
    1508     423    1639     421    2180     420 3297.73  417.62 3390.82  423.64
 3412.93     414 3508.32  414.49 3554.53     426 3720.65  417.58 3767.38  428.66
 4067.54  416.19 4089.48     426 4179.87     428 4988.64  431.81 5016.95     406
    5073   401.9 5242.89     432 5964.24  431.45 6028.89  422.93 6272.57  433.23
 6805.69  422.36 8506.55   428.1 8543.01  430.89 8548.95  442.04 8635.78  447.42
#Mann= 11 ,-1,0
       0    .085       0  959.21      .1       0    1362    .085       0
    1508    .085       0    1639    .085       0    2180    .085       0
 3297.73     .12       0 4988.64    .055       0 5242.89    .075       0
 8506.55     .05       0 8635.78    .075       0
#XS Ineff= 4 ,-1
       0  997.95     440    1320    4853     430    5243 7744.36     430
 7744.36 8635.78     440
Permanent Ineff=
       T       F       F       F
#Block Obstruct= 1 ,-1
    3362    3737     424
Bank Sta=4988.64,5242.89
XS Rating Curve= 0 ,0
Exp/Cntr=0.3,0.1

Type RM Length L Ch R = 1 ,33188   ,118,52,25
BEGIN DESCRIPTION:
33188
STATIONS 1015-1794, 2009 CGP TOPOGRAPHY
END DESCRIPTION:
XS GIS Cut Line= 6
  2438555.1209626971901.796684892438606.02177955 6970289.9337669
2438627.723179716969083.336442562438857.75815272 6967542.5376869
2439413.313472056966670.142121972440331.151531386963676.44371305
#Sta/Elev= 30
       0  441.78  647.84  430.66  726.52  439.08  985.59   439.9 1292.69     439
    1359     422    2205     420  3271.2  416.05 3321.97  416.01 3352.08     426
 3414.85     414 3516.09  425.95    3572     414 3639.22     426 3833.73  425.68
 3880.52     416 4030.41  427.81 4973.02  430.79 5009.14     406    5061   401.7
 5230.03     432 5952.02  430.33 5999.99  422.62 6231.86  433.25 6872.06  422.38
 8359.79   422.4 8503.88  429.25 8513.87  431.74 8516.87  442.75 8553.83  443.81
#Mann= 7 ,-1,0
       0    .085       0  985.59      .1       0    1359    .085       0
    2205    .085       0  3271.2     .12       0 4973.02    .055       0
 5230.03    .075       0
#XS Ineff= 4 ,-1
       0  998.33     440    1320    4973     430    5230 7689.76     430
 7689.76 8553.79     440
Permanent Ineff=
       T       F       F       F
#Block Obstruct= 1 ,-1
    3352    3639     426
Bank Sta=4973.02,5230.03
XS Rating Curve= 0 ,0
Exp/Cntr=0.3,0.1

Type RM Length L Ch R = 1 ,33136   ,184,74,25
BEGIN DESCRIPTION:
33136 The reach length has been updated and it is the same with the 2018 georeferenced model.
STATIONS 1024-1873 2009 CGP TOPOGRAPHY
END DESCRIPTION:
XS GIS Cut Line= 6
2438590.401075886972015.513649062438673.477025236969220.41687706
2438763.768183226968538.219094492438941.706147556967577.18755198
2439436.497808896966676.146046982440386.298074636963652.28693722
#Sta/Elev= 30
       0  440.86  649.96  431.08  722.97   439.4   921.6     439 1295.79     439
    1352     422 2261.87  420.29 3241.53  416.28 3327.43     426 3393.52  424.76
 3421.65     414 3460.22     426 3586.96  425.95 3674.75     414  3729.4  423.52
 3752.83     414  3869.9  426.75 4957.16  431.07 4997.22     406    5048   401.6
 5226.59     432 5924.98  428.69  5945.4     420 6190.62     434  6617.3  429.62
 6646.77     422  8423.1  427.31  8483.3     442  8530.5  442.74 8559.47     448
#Mann= 9 ,-1,0
       0    .085       0   921.6      .1       0    1352    .085       0
 2261.87    .085       0 3241.53     .12       0 4957.16    .055       0
 5226.59    .075       0  8423.1     .05       0  8530.5    .075       0
#XS Ineff= 4 ,-1
       0  996.56     440    1300    4815     430    5227    7618     430
    7618    8520     440
Permanent Ineff=
       T       F       F       F
#Block Obstruct= 1 ,-1
    3327    3717   423.6
Bank Sta=4957.16,5226.59
XS Rating Curve= 0 ,0
Exp/Cntr=0.3,0.1

Type RM Length L Ch R = 1 ,33062   ,190,48,20
BEGIN DESCRIPTION:
33062 The reach length has been updated and it is the same with the 2018 georeferenced model.
STATIONS 1073-1948 2009 CGP TOPOGRAPHY
END DESCRIPTION:
XS GIS Cut Line= 6
2438646.363562396971916.28386064 2438699.51863986970095.41676748
2438748.997871556969314.167017642439051.081256886967600.62516914
2439478.164392226966699.583664152440365.240632846963740.73208122
#Sta/Elev= 30
       0  440.32  693.06  432.63  918.36     439 1292.59  438.98    1350     422
    1531     422 1747.74   422.2 2458.68   418.5 3215.26  416.83 3269.16     426
 3391.74  424.83 3426.82     414 3538.61  425.96 3571.63     414  3608.2  414.51
 3623.64  426.08 4620.26  429.87 4718.72  418.82 4816.56  431.82 4929.56  431.48
 4958.48     406    5002   401.3 5096.21     408 5187.05     432 5885.88  428.62
 5907.44     420 6173.44  433.48 6606.15     422 8378.48  427.15 8431.47     440
#Mann= 12 ,-1,0
       0    .085       0  918.36      .1       0    1350    .085       0
    1531    .085       0 1747.74    .085       0 2458.68    .085       0
 3215.26     .12       0 4620.26    .055       0 4816.56     .07       0
 4929.56    .055       0 5187.05    .075       0 8378.48     .05       0
#XS Ineff= 5 ,-1
       0  993.31     440    1300    4600     430    4600    4900     430
    5187    7559     430    7559 8431.47     440
Permanent Ineff=
       T       F       T       F       F
#Block Obstruct= 1 ,-1
    3269 3533.41     426
Bank Sta=4929.56,5187.05
XS Rating Curve= 0 ,0
Exp/Cntr=0.3,0.1

Type RM Length L Ch R = 1 ,33014   ,60,47,24
BEGIN DESCRIPTION:
33014 The reach length has been updated and it is the same with the 2018 georeferenced mode.
STATIONS 1059-1985 2009 CGP TOPOGRAPHY
END DESCRIPTION:
XS GIS Cut Line= 6
2438846.289343646972015.82434398 2438845.87267786969631.35437539
2438997.695536886968443.333457482439178.685332396967561.56258322
2439501.602009396966702.187661562440395.831192056963661.45358557
#Sta/Elev= 30
       0  438.85  910.52     439 1284.78     439    1343     422    1515     423
    1767     421    2022   418.7 3092.42  416.45 3203.19     426 3408.66     424
 3461.08     414 3546.68  414.65 3579.51     426 4369.25  429.97  4558.4     412
 4684.81     412 4769.52  431.75 4884.41  431.44 4919.89     406    4966   401.1
 5070.81     408 5136.79     432 5836.33  429.29 5893.81  419.08 5939.06  429.67
 6127.95  432.55  6554.5     422 8328.81  427.08 8442.69     443 8471.68     448
#Mann= 13 ,-1,0
       0    .085       0  910.52      .1       0    1343    .085       0
    1515    .085       0    1767    .065       0    2022    .085       0
 3092.42     .12       0 4369.25    .055       0 4769.52     .07       0
 4884.41    .055       0 5136.79    .075       0 8328.81     .05       0
 8442.69    .075       0
#XS Ineff= 5 ,-1
       0  985.48     440    1300    4350     430    4350    4780     430
    5137    7516     430    7516    8432     440
Permanent Ineff=
       T       F       T       F       F
Bank Sta=4884.41,5136.79
XS Rating Curve= 0 ,0
Exp/Cntr=0.3,0.1

Type RM Length L Ch R = 1 ,32967   ,54,48,60
BEGIN DESCRIPTION:
32967 The reach length has been updated and it is the same with the 2018 georeferenced model.
STATIONS 6649-7540 2009 CGP TOPOGRAPHY
END DESCRIPTION:
XS GIS Cut Line= 6
2438854.218789736972396.935130312438900.039564226970957.39601465
2438905.247887136969452.187738982439173.477009486967777.70847639
2439514.622980716966785.521156312440441.649341886963559.06993206
#Sta/Elev= 30
    5308  438.92 6234.57     439 6578.74     440    6643     423    6943     421
    7109     420    7372   418.7 8365.91  416.14  8655.9  414.02    8846  425.97
 8903.09     414  9010.2  414.73 9024.68     426 9082.24     428 9484.89  430.12
 9712.35     412 9989.64     412   10071   431.610175.69  431.2710210.15     406
   10273     40110377.47     40810428.55     43211135.59  429.48 11159.4     418
11309.65     43211840.67     42213625.75  427.1513737.19     44313897.58  443.68
#Mann= 13 ,-1,0
    5308    .085       0 6234.57      .1       0    6643    .085       0
    6943    .085       0    7109    .065       0    7372    .085       0
 8365.91     .12       0 9484.89    .055       0   10071     .07       0
10175.69    .055       010428.55    .075       013625.75     .05       0
13737.19    .075       0
#XS Ineff= 5 ,-1
    5308 6309.43     440    6610    9480     430    9480   10100     430
   10683   12779     430   12779   13731     440
Permanent Ineff=
       T       F       T       F       F
#Block Obstruct= 1 ,-1
    8512    8689     426
Bank Sta=10175.69,10428.55
XS Rating Curve= 0 ,0
Exp/Cntr=0.3,0.1