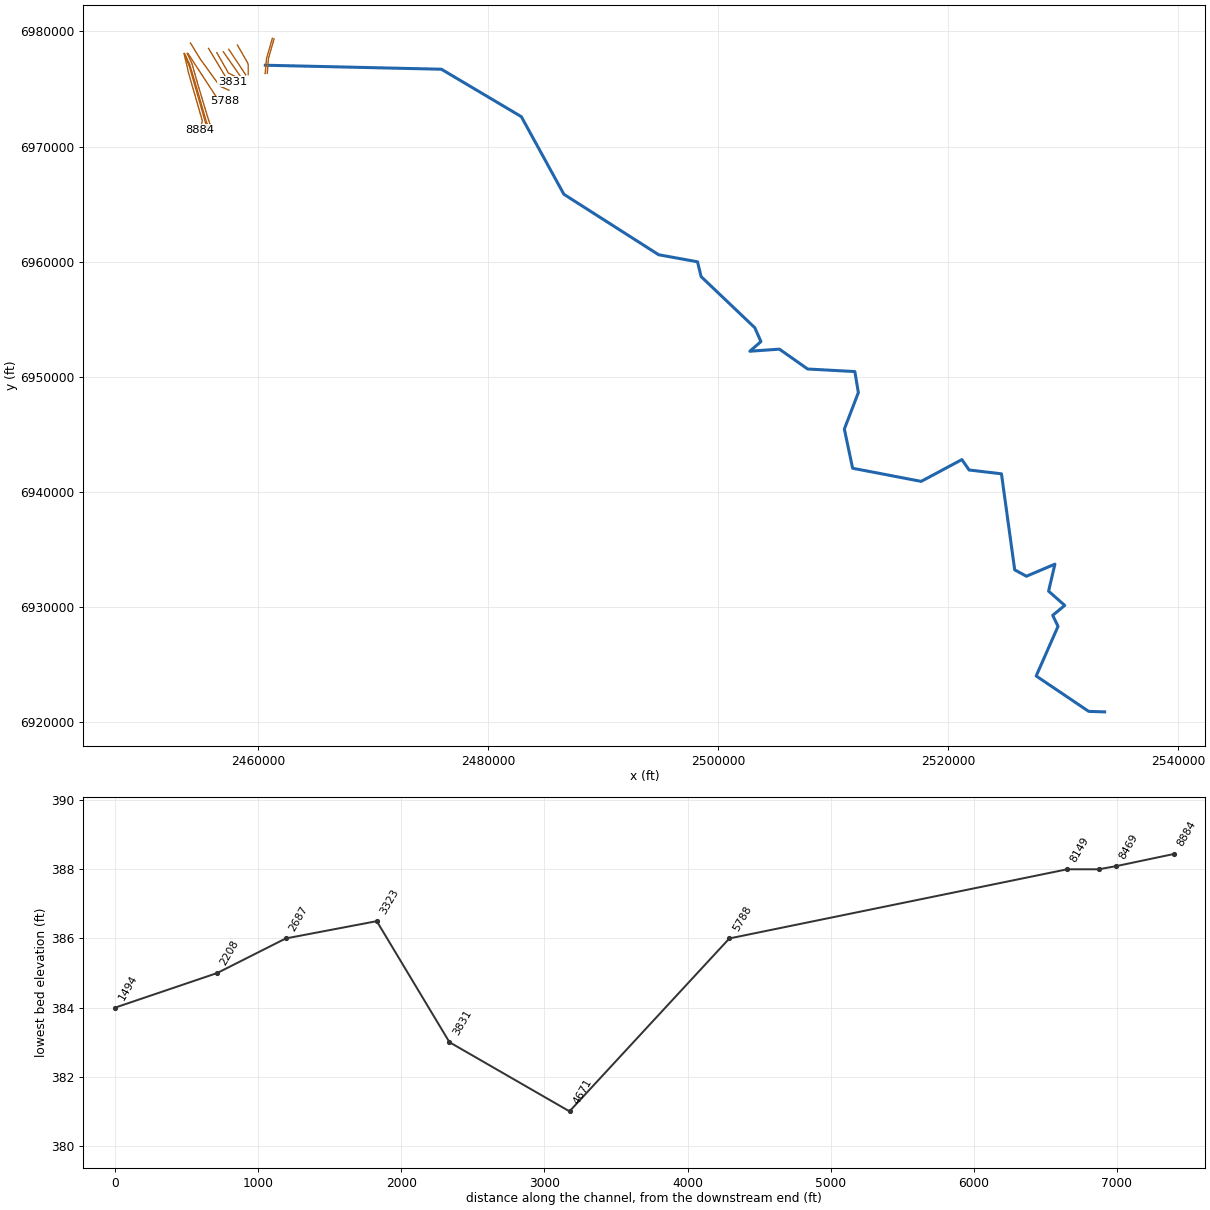
HEC-RAS study CDC_Consolidated_Model.prj: Upper Trinity CDC Consolidated Model

--- CDC_Consolidated_Model.g13 (geometry) --- (continued)

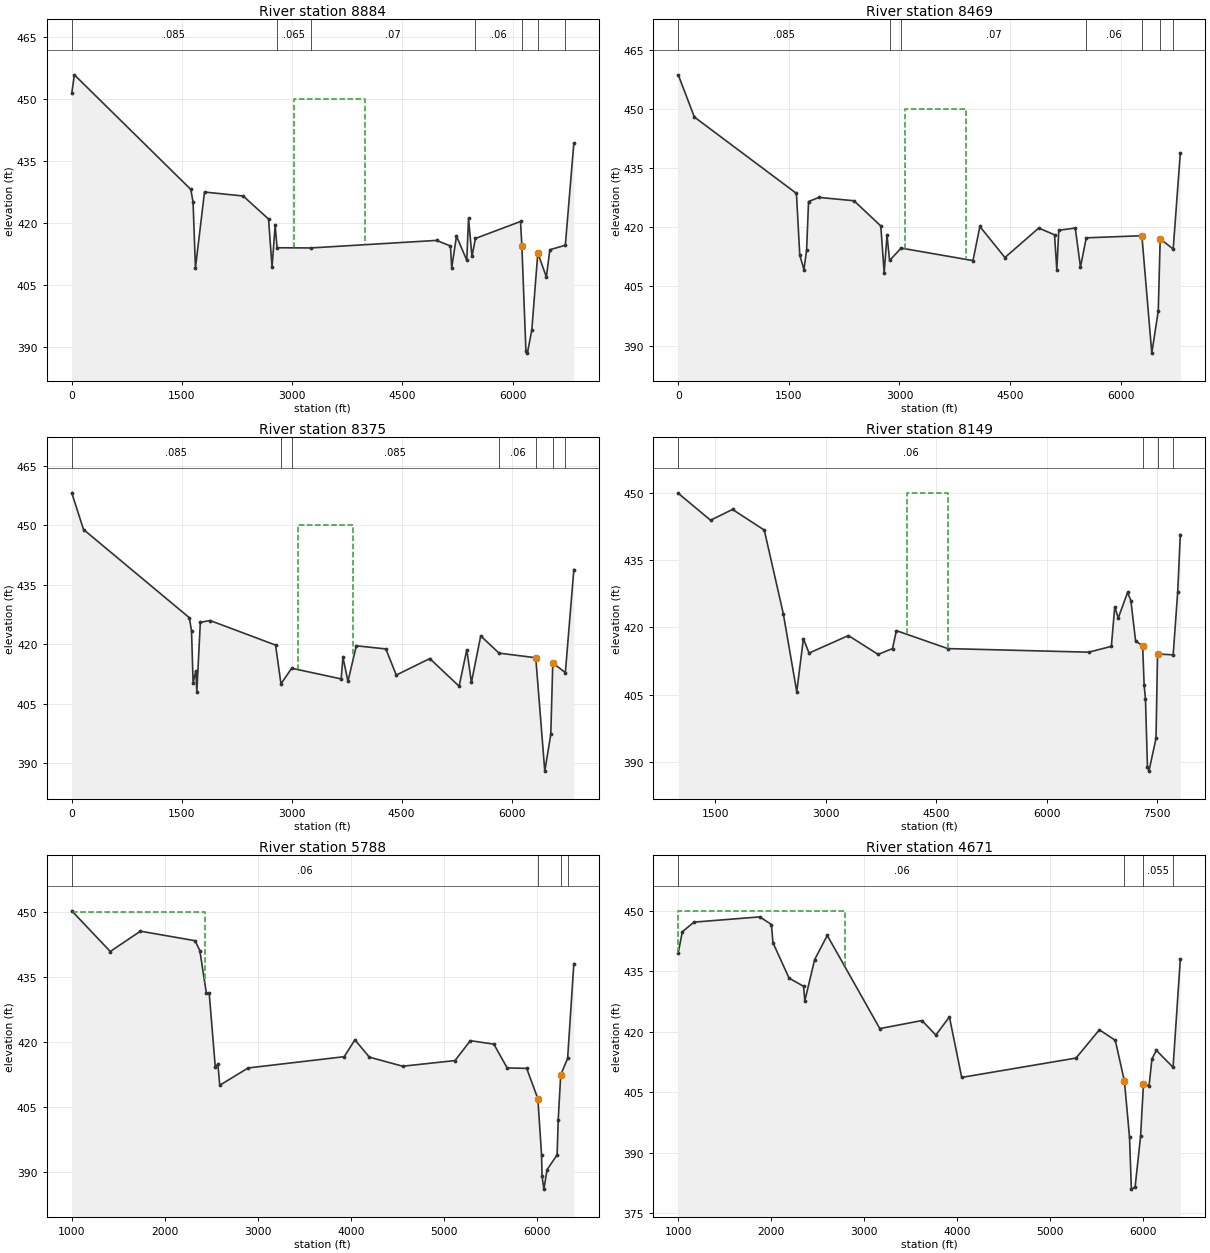
Type RM Length L Ch R = 1 ,8884    ,224,402,479
BEGIN DESCRIPTION:
This cross section corresponds to cross section 8884 of the non-georeferenced CDC model which was the source of this model.
END DESCRIPTION:
XS GIS Cut Line= 6
  2453590.094167 6978074.2020732 2453862.8373881 6976928.0836305
 2453959.7135067 6976458.6072072 2454301.0153175 6975282.6807533
 2455177.3711763 6972243.7527761 2454974.6766998  6971456.820951
#Sta/Elev= 30
       0  451.47   35.51  455.94 1619.87  428.15 1650.75  425.11 1683.29  409.11
  1806.6  427.51 2332.93  426.55 2678.33  420.96 2726.08  409.33  2768.2  419.45
 2794.51     414 3252.14  413.95 4965.23  415.78 5154.32  414.42 5171.16  409.13
 5236.28  416.82 5375.99  410.98 5400.26  421.14 5447.12  411.88 5493.85  416.25
 6107.99  420.37  6126.2  414.44 6181.13     389 6201.13  388.44 6261.13     394
 6343.02  412.74 6459.48  406.92 6507.06  413.52  6717.6   414.6 6833.56  439.37
#Mann= 7 ,-1,0
       0    .085       0 2794.51    .065       0 3252.14     .07       0
 5493.85     .06       0  6126.2    .039       0 6343.02    .055       0
  6717.6     .03       0
#XS Ineff= 1 ,-1
    3025    3990     450
Permanent Ineff=
       F
Bank Sta=6126.2,6343.02
XS Rating Curve= 0 ,0
Exp/Cntr=0.3,0.1

Type RM Length L Ch R = 1 ,8469    ,121,122,163
BEGIN DESCRIPTION:
This cross section corresponds to cross section 8469 of the non-georeferenced CDC model which was the source of this model.
END DESCRIPTION:
XS GIS Cut Line= 3
   2453615.43073 6978075.6925557 2454058.1490053 6976939.7771767
 2455591.3073563 6971586.4571746
#Sta/Elev= 30
       0  458.59  218.64   447.9 1602.62  428.55    1648   412.9  1704.4  409.27
 1740.56  414.18 1766.97  426.48 1908.12  427.54 2382.99  426.69 2746.47  420.31
 2792.23  408.47 2830.96  417.93 2866.02  411.57 3022.16   414.7 3996.56  411.53
 4090.06  420.17 4429.96  412.31 4887.92  419.77 5102.22  418.07 5133.41  409.21
 5159.88  419.21 5383.61  419.77 5453.88  409.91 5532.59   417.3 6286.71  417.83
 6421.13  388.09 6508.89  398.78 6535.11  417.04 6711.22  414.45 6807.84  438.78
#Mann= 7 ,-1,0
       0    .085       0 2866.02    .065       0 3022.16     .07       0
 5532.59     .06       0 6286.71    .039       0 6535.11    .055       0
 6711.22     .03       0
#XS Ineff= 1 ,-1
    3080    3900     450
Permanent Ineff=
       F
Bank Sta=6286.71,6535.11
XS Rating Curve= 0 ,0
Exp/Cntr=0.3,0.1

Type RM Length L Ch R = 1 ,8375    ,223,219,233
BEGIN DESCRIPTION:
This cross section corresponds to cross section 8375 of the non-georeferenced CDC model which was the source of this model.
END DESCRIPTION:
XS GIS Cut Line= 6
   2453632.43693  6978080.906128 2454067.2198533 6977168.4679922
 2454570.4179939 6975495.1839372  2455497.999144 6972263.8049013
 2455631.3771581 6971887.9231072 2455772.8240537 6971592.1681212
#Sta/Elev= 30
       0  458.17   160.3  448.92 1603.26  426.69 1633.46  423.39 1655.12  410.24
 1692.37   413.3 1705.81     408  1753.7  425.53 1887.04  425.97 2779.81  419.78
 2853.47     410 2999.54  413.94 3674.74  411.25 3699.04  416.74 3767.15  410.61
 3881.34   419.6 4283.86  418.81 4426.48  412.23 4883.62  416.38 5283.17  409.41
 5388.22  418.61 5451.24  410.35 5578.19   422.1 5827.93  417.75 6328.82  416.59
    6452     388 6533.87  397.29  6561.2   415.3  6732.5  412.83 6848.38  438.82
#Mann= 7 ,-1,0
       0    .085       0 2853.47    .065       0 2999.54    .085       0
 5827.93     .06       0 6328.82    .039       0  6561.2    .055       0
  6732.5     .03       0
#XS Ineff= 1 ,-1
    3090    3840     450
Permanent Ineff=
       F
Bank Sta=6328.82,6561.2
XS Rating Curve= 0 ,0
Exp/Cntr=0.3,0.1

Type RM Length L Ch R = 1 ,8149    ,1200,2361,2600
BEGIN DESCRIPTION:
This cross section corresponds to cross section 8149 of the non-georeferenced CDC model which was the source of this model.
---------------------------------------------------------------------
CDC IRV030300-1 Farrow Addition
CDC IRV081211-1 Trailer Storage Site
Cross-section 8149 - 9520
Located in LOB.
---------------------------------------------------------------------
END DESCRIPTION:
XS GIS Cut Line= 6
  2453864.572948 6978094.9940263 2454264.8490512 6977247.2201313
 2454816.5480791 6975307.1800482 2455604.6888912 6972676.0009273
 2455841.1310037 6971948.4859782  2455998.194994 6971627.8150316
#Sta/Elev= 30
    1000   449.9    1439   443.9    1737   446.3    2168   441.7    2426   423.1
    2609   405.7    2699   417.5    2776   414.3    3310   418.2    3714     414
    3909   415.3    3961   419.3    4660   415.3    6574   414.5    6880   415.8
    6926   424.6    6973   422.1    7100   427.8    7145     426    7209     417
    7305   415.9    7325   407.1    7343   404.1    7370     389    7390     388
    7486   395.3    7507   414.1    7719   413.9    7781     428    7816   440.7
#Mann= 4 ,-1,0
    1000     .06       0    7305    .039       0    7507    .055       0
    7719     .03       0
#XS Ineff= 1 ,-1
    4100    4660     450
Permanent Ineff=
       F
Bank Sta=7305,7507
XS Rating Curve= 0 ,0
Exp/Cntr=0.3,0.1

Type RM Length L Ch R = 1 ,5788    ,860,1117,1050
BEGIN DESCRIPTION:
This cross section corresponds to cross section 5788 of the non-georeferenced CDC model which was the source of this model.
END DESCRIPTION:
XS GIS Cut Line= 6
  2453934.336917 6978081.8500237 2454553.8652055 6977131.8378162
 2455276.6934843 6976023.5050591 2455896.2992004 6975073.5190982
 2456515.9410057 6974123.5449482 2457167.6270383 6973927.6129254
#Sta/Elev= 30
    1000   450.3    1414   440.9    1738   445.6    2325   443.4    2377   441.1
    2447   431.3    2478   431.2    2543   414.2    2571   414.9    2591     410
    2897     414    3929   416.6    4044   420.5    4199   416.5    4557   414.4
    5120   415.7    5285   420.3    5538   419.5    5681     414    5891   413.9
    6011   406.9    6051   393.9    6056     389    6076     386    6110   390.5
    6218   393.9    6230     402    6257   412.4    6331   416.2    6398   438.1
#Mann= 4 ,-1,0
    1000     .06       0    6011    .039       0    6257    .055       0
    6331     .03       0
#XS Ineff= 2 , 0
            2430     450
Permanent Ineff=
       F       F
Bank Sta=6011,6257
XS Rating Curve= 0 ,0
Exp/Cntr=0.3,0.1

Type RM Length L Ch R = 1 ,4671    ,1049,839,829
BEGIN DESCRIPTION:
This cross section corresponds to cross section 4671 of the non-georeferenced CDC model which was the source of this model.
END DESCRIPTION:
XS GIS Cut Line= 6
  2454143.389976  6978999.297992 2454621.3942699 6978220.9973832
 2455003.8141087 6977598.3621456  2455879.415704 6976387.9187003
   2456700.35107 6975253.1499725 2457491.4170732   6974899.32194
#Sta/Elev= 30
    1000   439.6    1044   444.8    1169   447.2    1877   448.5    2002   446.6
    2018   442.1    2192   433.3    2347   431.3    2361   427.7    2466   437.9
    2602   443.9    3167   420.8    3620   422.8    3769   419.2    3915   423.7
    4047   408.7    5276   413.5    5527   420.5    5698   417.9    5796   407.8
    5851   393.9    5871     381    5911   381.5    5970   394.1    6001   407.1
    6061   406.6    6092   413.3    6140   415.4    6319   411.2    6397     438
#Mann= 4 ,-1,0
    1000     .06       0    5796    .039       0    6001    .055       0
    6319     .03       0
#XS Ineff= 2 , 0
            2790     450
Permanent Ineff=
       F       F
Bank Sta=5796,6001
XS Rating Curve= 0 ,0
Exp/Cntr=0.3,0.1

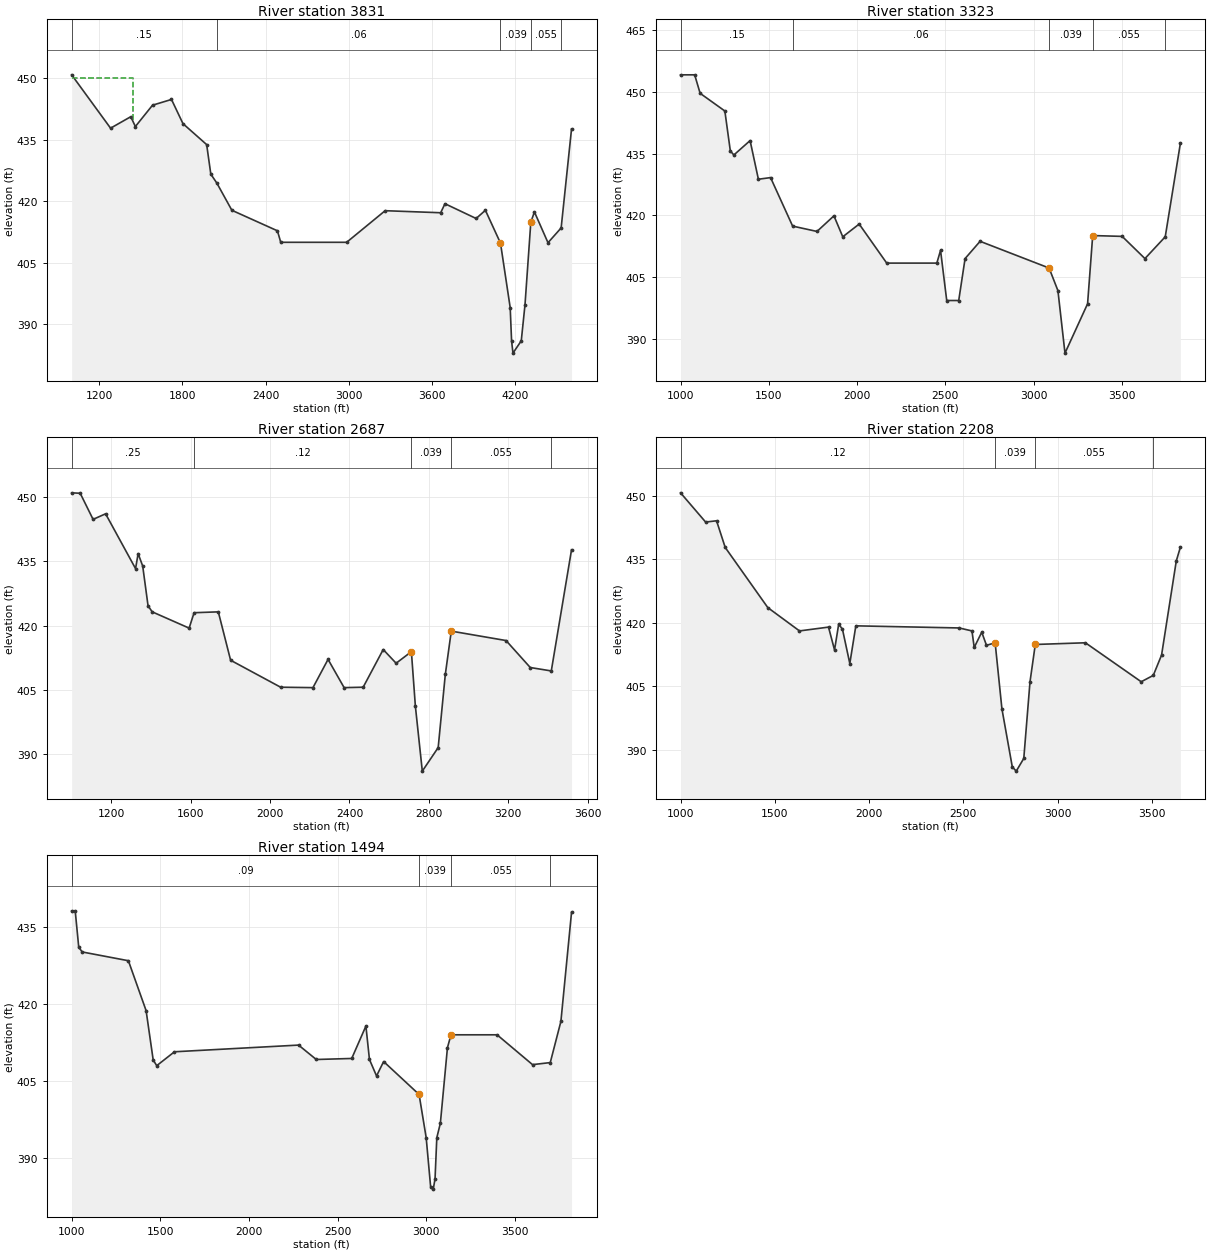
Type RM Length L Ch R = 1 ,3831    ,420,508,510
BEGIN DESCRIPTION:
This cross section corresponds to cross section 3831 of the non-georeferenced CDC model which was the source of this model.
END DESCRIPTION:
XS GIS Cut Line= 6
  2455714.583028 6978536.5180777 2456156.7386402 6977800.7049167
 2456500.6513382 6977228.4101296  2456893.708951 6976574.3635374
 2457286.7819837 6975920.3218665 2457775.2160462 6975634.8729623
#Sta/Elev= 30
    1000   450.8    1281   437.8    1427   440.6    1460   438.2    1584   443.4
    1721   444.8    1804   438.9    1975   433.8    2005   426.6    2049   424.4
    2157   417.8    2486   412.8    2510     410    2986     410    3264   417.7
    3665   417.2    3696   419.4    3921   415.8    3988   417.8    4097   409.8
    4167   394.1    4177     386    4187     383    4247     386    4274   394.8
    4316   414.9    4342   417.4    4440   409.9    4535   413.5    4610   437.6
#Mann= 5 ,-1,0
    1000     .15       0    2049     .06       0    4097    .039       0
    4316    .055       0    4535     .03       0
#XS Ineff= 2 , 0
            1445     450
Permanent Ineff=
       F       F
Bank Sta=4097,4316
XS Rating Curve= 0 ,0
Exp/Cntr=0.3,0.1

Type RM Length L Ch R = 1 ,3323    ,620,636,430
BEGIN DESCRIPTION:
This cross section corresponds to cross section 3323 of the non-georeferenced CDC model which was the source of this model.
END DESCRIPTION:
XS GIS Cut Line= 6
  2456438.118982 6978157.4850431 2456667.1680655 6977756.3920132
 2456942.0343137 6977275.0826084 2457216.9087639 6976793.7755002
 2457445.9768753 6976392.6880477 2458166.4659199 6976025.6559734
#Sta/Elev= 30
    1000   454.2    1080   454.2    1111   449.7    1251   445.4    1282   435.7
    1302   434.7    1394   438.2    1441   428.8    1510   429.2    1635   417.4
    1773   416.1    1869   419.9    1919   414.8    2012   417.9    2168   408.4
    2452   408.4    2473   411.5    2508   399.3    2576   399.3    2612   409.5
    2697   413.7    3088   407.2    3138   401.7    3178   386.5    3306   398.5
    3335   415.1    3502   414.9    3631   409.5    3746   414.8    3832   437.6
#Mann= 5 ,-1,0
    1000     .15       0    1635     .06       0    3088    .039       0
    3335    .055       0    3746     .03       0
#Block Obstruct= 2 , 0
            2729   414.1
Bank Sta=3088,3335
XS Rating Curve= 0 ,0
Exp/Cntr=0.5,0.3

Type RM Length L Ch R = 1 ,2687    ,480,479,480
BEGIN DESCRIPTION:
This cross section corresponds to cross section 2687 of the non-georeferenced CDC model which was the source of this model.
END DESCRIPTION:
XS GIS Cut Line= 6
  2456998.734003 6978241.2548887 2457373.5990673 6977703.7891001
 2457587.8128777 6977396.6676671 2457748.4759423 6977166.3279047
 2458069.8092891 6976705.6500202 2458444.7091298 6976168.1970269
#Sta/Elev= 30
    1000     451    1043   450.9    1108   444.8    1171   446.1    1322   433.3
    1335   436.8    1358   433.9    1385   424.6    1406   423.2    1592   419.4
    1617     423    1739   423.2    1801   411.9    2053   405.6    2216   405.5
    2292   412.1    2373   405.5    2469   405.6    2570   414.4    2635   411.2
    2712   413.9    2732   401.2    2767     386    2847   391.5    2883   408.6
    2913   418.7    3189   416.5    3311   410.2    3417   409.4    3519   437.7
#Mann= 5 ,-1,0
    1000     .25       0    1617     .12       0    2712    .039       0
    2913    .055       0    3417     .03       0
#Block Obstruct= 2 , 0
            2570   414.4
Bank Sta=2712,2913
XS Rating Curve= 0 ,0
Exp/Cntr=0.5,0.3

Type RM Length L Ch R = 1 ,2208    ,849,713,499
BEGIN DESCRIPTION:
This cross section corresponds to cross section 2208 of the non-georeferenced CDC model which was the source of this model.
END DESCRIPTION:
XS GIS Cut Line= 6
  2457478.800956 6978447.4578883 2457847.0571099 6977893.3622117
 2458215.3257303 6977339.2708002  2458373.158748 6977101.8044117
 2458583.6064898 6976785.1839819 2458951.9000446 6976231.1011006
#Sta/Elev= 30
    1000   450.7    1133   443.8    1191   444.1    1237   437.8    1463   423.6
    1631   418.1    1785     419    1817   413.6    1839   419.7    1859   418.5
    1898   410.4    1930   419.3    2478   418.8    2546   418.1    2558   414.2
    2598   417.8    2623   414.7    2669   415.3    2705   399.7    2760     386
    2781     385    2821     388    2854   406.1    2882   414.9    3148   415.3
    3444   406.1    3508   407.6    3552   412.4    3630   434.6    3652   437.9
#Mann= 4 ,-1,0
    1000     .12       0    2669    .039       0    2882    .055       0
    3508     .03       0
#Block Obstruct= 2 , 0
            1930   419.3
Bank Sta=2669,2882
XS Rating Curve= 0 ,0
Exp/Cntr=0.5,0.3

Type RM Length L Ch R = 1 ,1494    ,1494,1494,1494
BEGIN DESCRIPTION:
This cross section corresponds to cross section 1494 of the non-georeferenced CDC model which was the source of this model.
END DESCRIPTION:
XS GIS Cut Line= 6
  2458223.312919 6978824.4259664 2458635.0010721 6978109.9168967
 2459046.7069416 6977395.4130764 2459133.1421362 6977230.1118978
 2459164.8340019 6977120.8440717  2459164.834001 6976250.4111013
#Sta/Elev= 30
    1000   438.1    1020   438.1    1040     431    1060   430.1    1320   428.4
    1420   418.7    1460   409.1    1480     408    1580   410.7    2280     412
    2380   409.2    2580   409.4    2660   415.7    2680   409.2    2720     406
    2760   408.8    2960   402.4    3000     394    3025   384.5    3040     384
    3050     386    3060     394    3080   396.8    3120   411.5    3140     414
    3400     414    3600   408.2    3700   408.6    3760   416.6    3820   437.8
#Mann= 4 ,-1,0
    1000     .09       0    2960    .039       0    3140    .055       0
    3700     .03       0
Bank Sta=2960,3140
XS Rating Curve= 0 ,0
Exp/Cntr=0.5,0.3

River Reach=Main Stem       ,ms
Reach XY= 30
       2460651.9      6977070.51      2475956.02        6976723.
      2482902.21      6972603.81      2486601.03      6965861.25
      2494841.05      6960609.03      2498218.33      6959996.81
      2498526.81      6958713.48      2503198.36      6954269.99
      2503727.53      6953066.56      2502765.36      6952229.44
      2505335.43      6952409.66      2507789.67       6950684.6
      2511891.32      6950462.85      2512197.38      6948638.96
      2510979.79      6945468.76      2511698.66      6942064.93
      2517657.38      6940924.33      2521195.08      6942816.26
      2521824.01      6941912.62      2524634.19      6941582.52
      2525786.79      6933236.59      2526809.67      6932685.92
       2529281.6      6933737.03      2528731.26      6931389.82
      2530135.73      6930151.29      2529089.21      6929289.76
      2529552.65      6928333.05      2527652.49        6924023.
       2532218.2      6920945.83      2533600.64      6920903.28

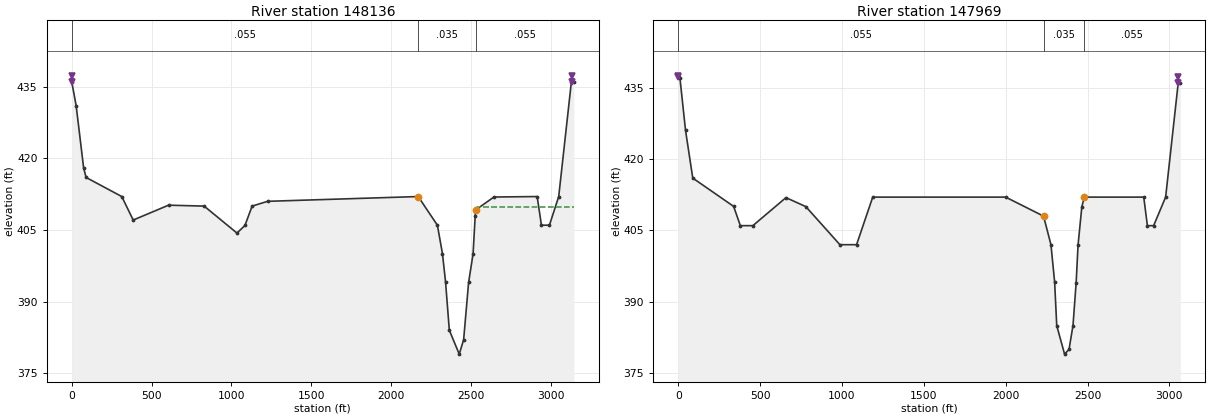
Type RM Length L Ch R = 1 ,148136  ,167,172,175
BEGIN DESCRIPTION:
Downstream of the confluence of Elm Fork and West Fork.
END DESCRIPTION:
XS GIS Cut Line= 3
2461264.280915836979412.294868132460759.000102256977671.00012238
2460636.75592417 6976344.2032353
#Sta/Elev= 30
       0     436   27.42  431.05   74.28     418   89.61     416  313.24     412
  384.89  407.08  606.27  410.19  829.29     410 1035.02  404.35 1085.06  405.95
 1129.96     410 1227.08     411 2170.34     412 2290.62     406 2322.29  400.07
 2341.66  394.16 2365.42     384 2427.49     379 2455.02     382 2486.18     394
 2514.23     400 2527.64     408 2533.03  409.26 2644.86   411.9 2915.71     412
 2942.45     406 2992.59     406 3050.72     412 3130.08     436 3145.54     436
#Mann= 3 ,0,0
       0    .055       0 2170.34    .035       0 2533.03    .055       0
Levee=-1,0,437.28,-1,3131,437.28,,
#XS Ineff= 2 , 0
         2290.62     406 2540.55          409.88
Permanent Ineff=
       F       F
Bank Sta=2170.34,2533.03
XS Rating Curve= 0 ,0
Exp/Cntr=0.3,0.1

Type RM Length L Ch R = 1 ,147969  ,163,168,171
BEGIN DESCRIPTION:
This cross section corresponds to cross section 147969 of the non-georeferenced CDC model which was the source of this model.
END DESCRIPTION:
XS GIS Cut Line= 3
2461413.161851676979361.517738712460918.000112336977632.00020038
2460822.115789686976367.85607514
#Sta/Elev= 30
       0  437.49   10.47     437   44.64     426   88.74     416  338.39  410.05
  379.26     406   455.9     406  657.92  411.89  779.46     410  987.48     402
 1089.32     402    1188     412 1999.98     412 2231.44     408 2276.59     402
 2299.04  394.18 2311.97     385  2359.8     379 2387.04     380 2411.26     385
 2430.53     394 2442.25  401.95 2465.38     410 2480.93     412 2843.47     412
 2865.69     406 2903.83     406 2977.13     412 3053.97     436 3066.78     436
#Mann= 3 ,0,0
       0    .055       0 2231.44    .035       0 2480.93    .055       0
Levee=-1,0,437.23,-1,3054,437.23,,
#XS Ineff= 2 , 0
         2231.44     408 2480.93             412
Permanent Ineff=
       F       F
Bank Sta=2231.44,2480.93
XS Rating Curve= 0 ,0
Exp/Cntr=0.3,0.1