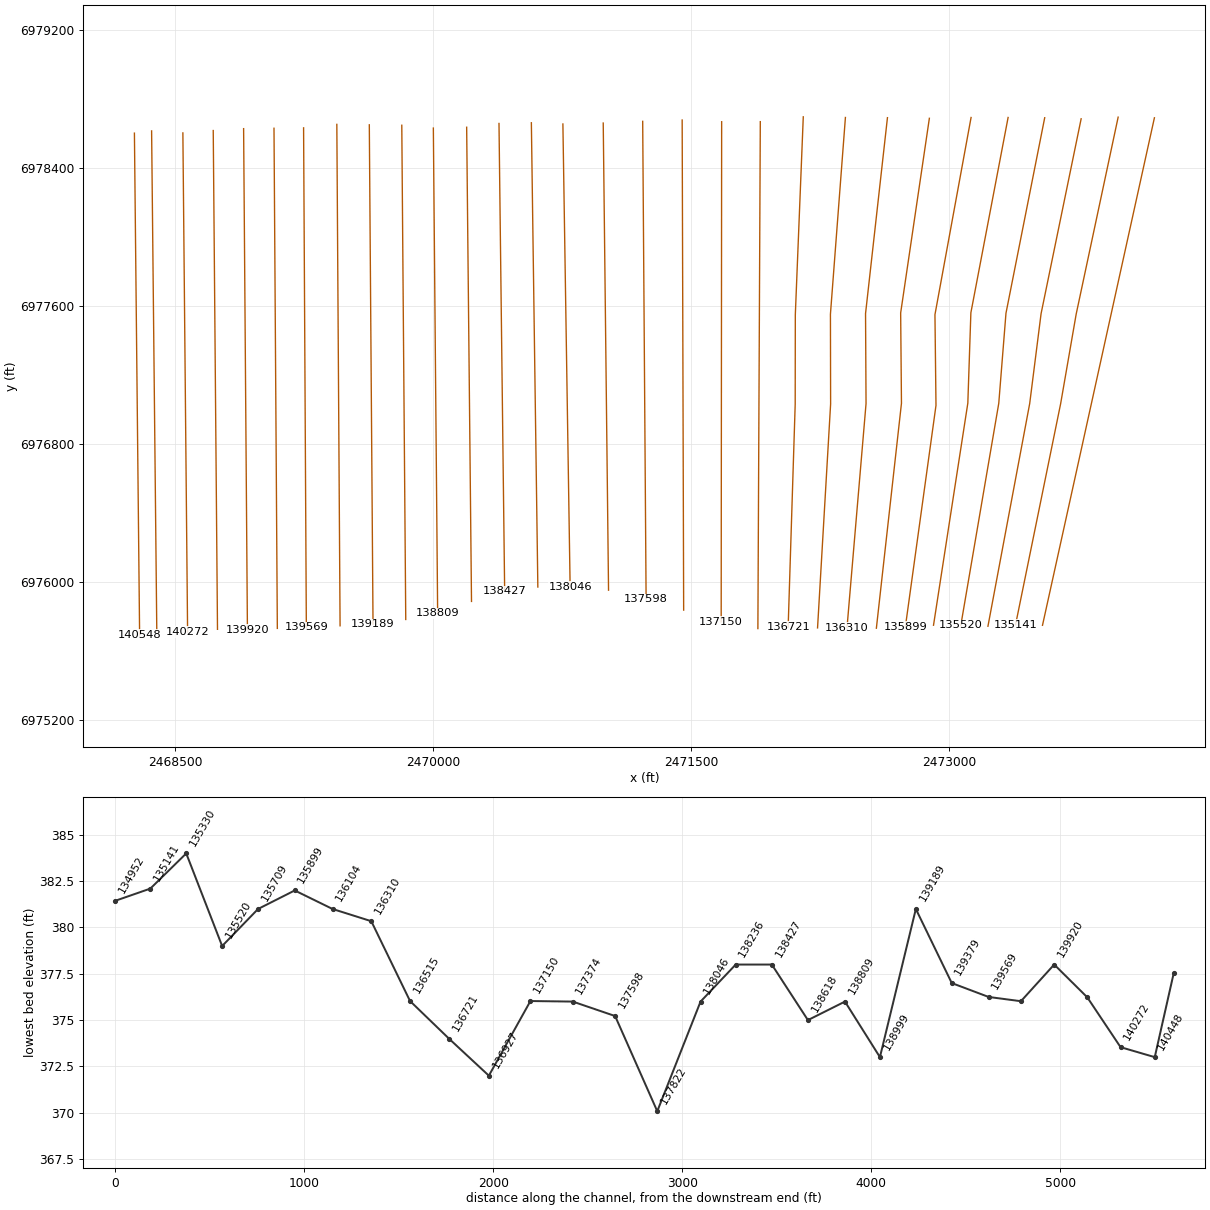
HEC-RAS study CDC_Consolidated_Model.prj: Upper Trinity CDC Consolidated Model

--- CDC_Consolidated_Model.g13 (geometry) --- (continued)

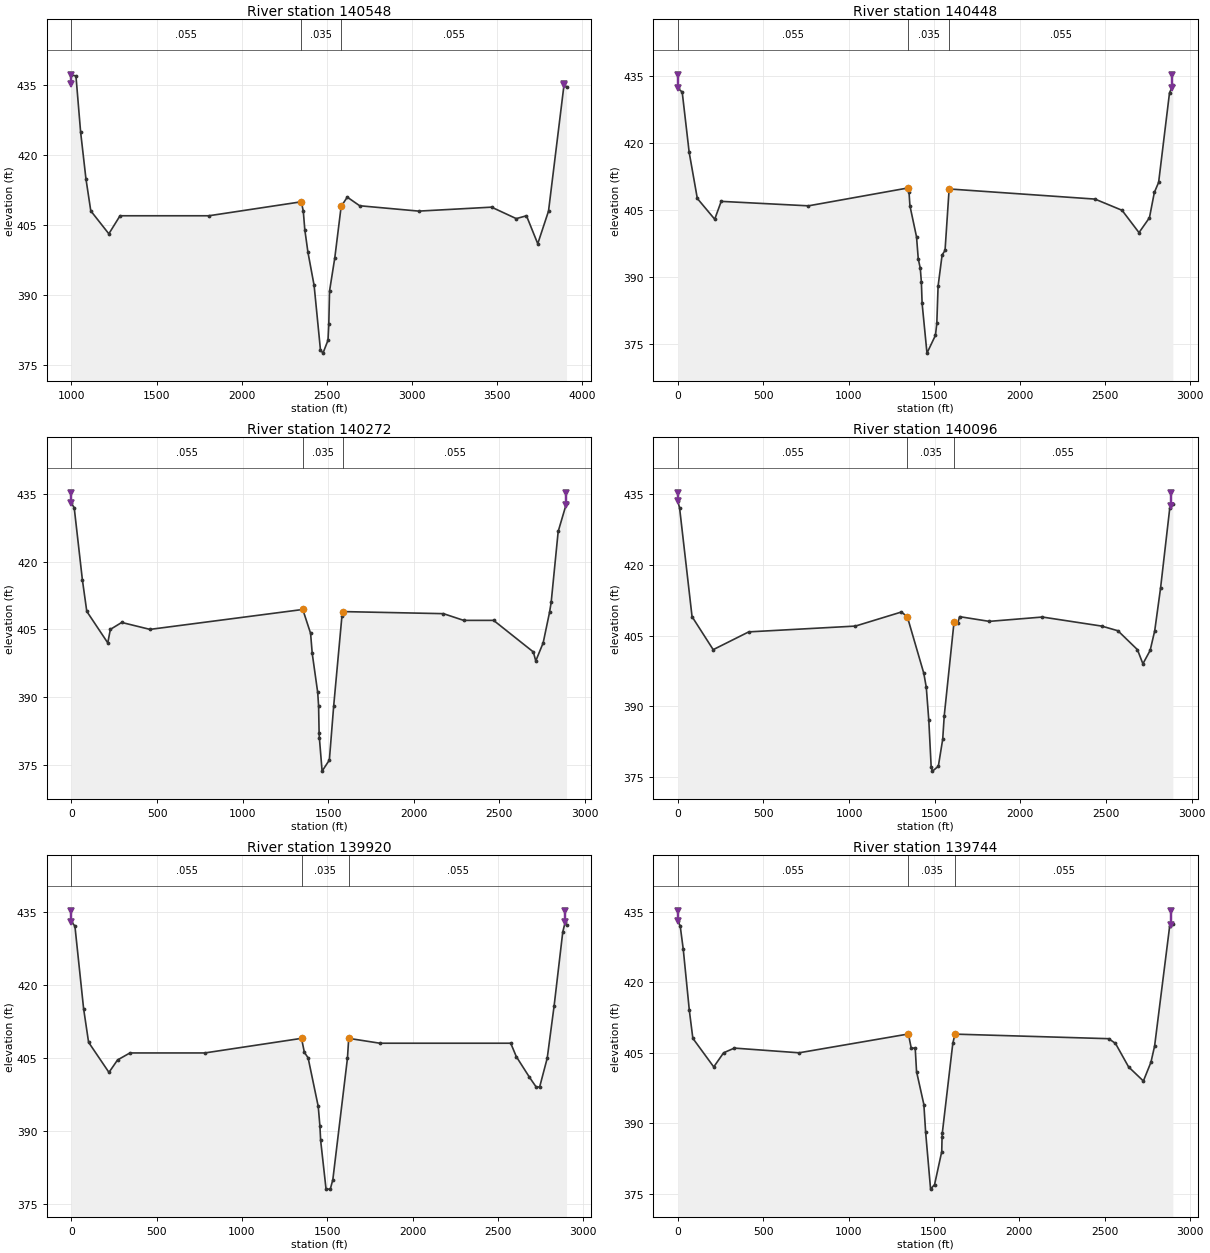
Type RM Length L Ch R = 1 ,140548  ,100,100,100
BEGIN DESCRIPTION:
This cross section corresponds to cross section 140548 of the non-georeferenced CDC model which was the source of this model.
END DESCRIPTION:
XS GIS Cut Line= 2
2468263.801365586978600.696425722468293.99684325 6975693.3029623
#Sta/Elev= 30
    1000  437.25 1026.64     437 1053.94     425 1085.28  414.93 1113.75  408.05
 1219.78  403.13 1285.44     407 1806.81     407 2349.99     410 2361.71     408
  2370.6     404 2388.98  399.18 2425.26  392.05 2462.56   378.2 2477.38  377.52
  2506.9   380.3 2511.56  383.81 2515.91  390.85 2546.77  397.98 2584.06     409
    2620     411 2692.97  409.15 3039.91     408 3467.48  408.85 3612.45  406.39
 3672.45     407 3738.64     401 3801.85     408 3892.55     435 3907.55  434.57
#Mann= 3 ,0,0
    1000    .055       0 2349.99    .035       0 2584.06    .055       0
Levee=-1,1000,435.38,-1,3893,435.38,,
#XS Ineff= 2 , 0
         2349.99     410 2584.06             409
Permanent Ineff=
       F       F
Bank Sta=2349.99,2584.06
XS Rating Curve= 0 ,0
Exp/Cntr=0.3,0.1

Type RM Length L Ch R = 1 ,140448  ,181,181,181
BEGIN DESCRIPTION:
This cross section corresponds to cross section 140448 of the non-georeferenced CDC model which was the source of this model.
END DESCRIPTION:
XS GIS Cut Line= 2
2468363.703396776978613.530717632468393.827024166975716.46728605
#Sta/Elev= 30
       0  432.38   26.15  431.49   66.87     418  114.63  407.65  216.43     403
  254.37     407  764.98     406 1346.96     410 1353.56     409 1358.79     406
 1397.39  399.05 1407.55  394.11 1419.32     392 1425.65     389 1430.04  384.16
 1458.53     373 1508.18     377 1516.08  379.69 1523.53     388 1547.09     395
 1564.24     396 1588.19  409.78 2441.62  407.51 2600.08     405  2699.3     400
 2760.35  403.33 2789.04     409 2814.13  411.26 2877.75   431.3 2897.22     433
#Mann= 3 ,0,0
       0    .055       0 1346.96    .035       0 1588.19    .055       0
Levee=-1,0,435.35,-1,2891,435.35,,
#XS Ineff= 2 , 0
         1346.96     410 1588.19          409.78
Permanent Ineff=
       F       F
Bank Sta=1346.96,1588.19
XS Rating Curve= 0 ,0
Exp/Cntr=0.3,0.1

Type RM Length L Ch R = 1 ,140272  ,176,176,176
BEGIN DESCRIPTION:
This cross section corresponds to cross section 140272 of the non-georeferenced CDC model which was the source of this model.
END DESCRIPTION:
XS GIS Cut Line= 2
2468545.414975586978601.908365552468572.809933936975710.20811221
#Sta/Elev= 30
       0     433   16.31     432   64.05     416   89.73     409  212.41     402
  227.39     405  293.93  406.54  458.71     405 1351.36  409.42 1397.01  404.12
 1406.48  399.68 1438.53     391 1443.76  388.02 1446.74     382 1448.15     381
 1464.19  373.54 1506.65     376 1531.87     388 1580.16     408 1587.49  408.95
 2173.03  408.49 2291.09     407 2466.02     407 2697.89     400 2712.26     398
 2755.36     402 2792.63  408.77  2802.2     411 2843.15  426.73 2891.83     433
#Mann= 3 ,0,0
       0    .055       0 1351.36    .035       0 1587.49    .055       0
Levee=-1,0,435.31,-1,2888,435.31,,
#XS Ineff= 2 , 0
         1351.36  409.42 1587.49          408.95
Permanent Ineff=
       F       F
Bank Sta=1351.36,1587.49
XS Rating Curve= 0 ,0
Exp/Cntr=0.3,0.1

Type RM Length L Ch R = 1 ,140096  ,175,175,175
BEGIN DESCRIPTION:
This cross section corresponds to cross section 140096 of the non-georeferenced CDC model which was the source of this model.
END DESCRIPTION:
XS GIS Cut Line= 2
2468721.880501936978615.703613552468746.573693996975725.68905239
#Sta/Elev= 30
       0  433.62      11     432    83.6     409     207     402  414.43  405.77
  1037.1     407 1305.23  409.98 1340.09     409 1436.34     397 1450.96     394
 1465.66     387 1479.62     377 1487.16  376.23 1521.28  377.27 1546.81     383
 1555.78     388 1612.87  407.84 1634.52  407.64 1645.41     409  1818.6     408
 2128.75  408.92 2474.77     407 2569.54  406.01 2683.53     402 2715.42     399
  2757.6  401.83  2784.4     406 2818.27  414.99 2872.27  432.04 2890.12  432.91
#Mann= 3 ,0,0
       0    .055       0 1340.09    .035       0 1612.87    .055       0
Levee=-1,0,435.27,-1,2880,435.27,,
#XS Ineff= 2 , 0
         1340.09     409 1612.87          407.84
Permanent Ineff=
       F       F
Bank Sta=1340.09,1612.87
XS Rating Curve= 0 ,0
Exp/Cntr=0.3,0.1

Type RM Length L Ch R = 1 ,139920  ,176,176,176
BEGIN DESCRIPTION:
This cross section corresponds to cross section 139920 of the non-georeferenced CDC model which was the source of this model.
END DESCRIPTION:
XS GIS Cut Line= 2
2468898.38507017 6978626.68882782468920.487716266975723.98301905
#Sta/Elev= 30
       0     433   20.51  432.07   71.47   415.1  100.67  408.19  220.09     402
  270.49  404.56  343.16     406  782.01     406 1349.18     409 1365.75  406.12
  1387.7     405 1447.11     395 1456.88     391 1461.28     388 1492.96     378
 1517.66     378 1532.66  379.93 1618.39  404.91  1625.8     409 1808.28     408
 2575.75     408 2608.39  405.25 2685.64     401  2724.8     399 2745.23     399
 2789.66  404.92 2830.34  415.74 2880.75  430.85  2895.7     433 2902.79  432.24
#Mann= 3 ,0,0
       0    .055       0 1349.18    .035       0  1625.8    .055       0
Levee=-1,0,435.22,-1,2896,435.22,,
#XS Ineff= 2 , 0
         1349.18     409  1625.8             409
Permanent Ineff=
       F       F
Bank Sta=1349.18,1625.8
XS Rating Curve= 0 ,0
Exp/Cntr=0.3,0.1

Type RM Length L Ch R = 1 ,139744  ,171,171,171
BEGIN DESCRIPTION:
This cross section corresponds to cross section 139744 of the non-georeferenced CDC model which was the source of this model.
END DESCRIPTION:
XS GIS Cut Line= 2
2469074.957879756978628.97195971 2469094.33316916975730.97677146
#Sta/Elev= 30
       0     433   14.31     432   32.36     427   67.91     414   88.44  408.08
  210.82     402  268.44     405  331.31     406  710.37     405 1350.02     409
 1366.79     406 1390.05     406 1397.94     401 1440.77     394 1451.07  388.12
 1480.05  376.02 1503.49     377  1545.4     384  1547.2     387 1548.93     388
 1610.12     407 1622.96  408.97 2522.53     408 2562.23     407 2639.17     402
 2725.66     399    2770     403 2791.44  406.45 2879.83     432 2898.06  432.48
#Mann= 3 ,0,0
       0    .055       0 1350.02    .035       0 1622.96    .055       0
Levee=-1,0,435.18,-1,2888,435.18,,
#XS Ineff= 2 , 0
         1350.02     409 1622.96          408.97
Permanent Ineff=
       F       F
Bank Sta=1350.02,1622.96
XS Rating Curve= 0 ,0
Exp/Cntr=0.3,0.1

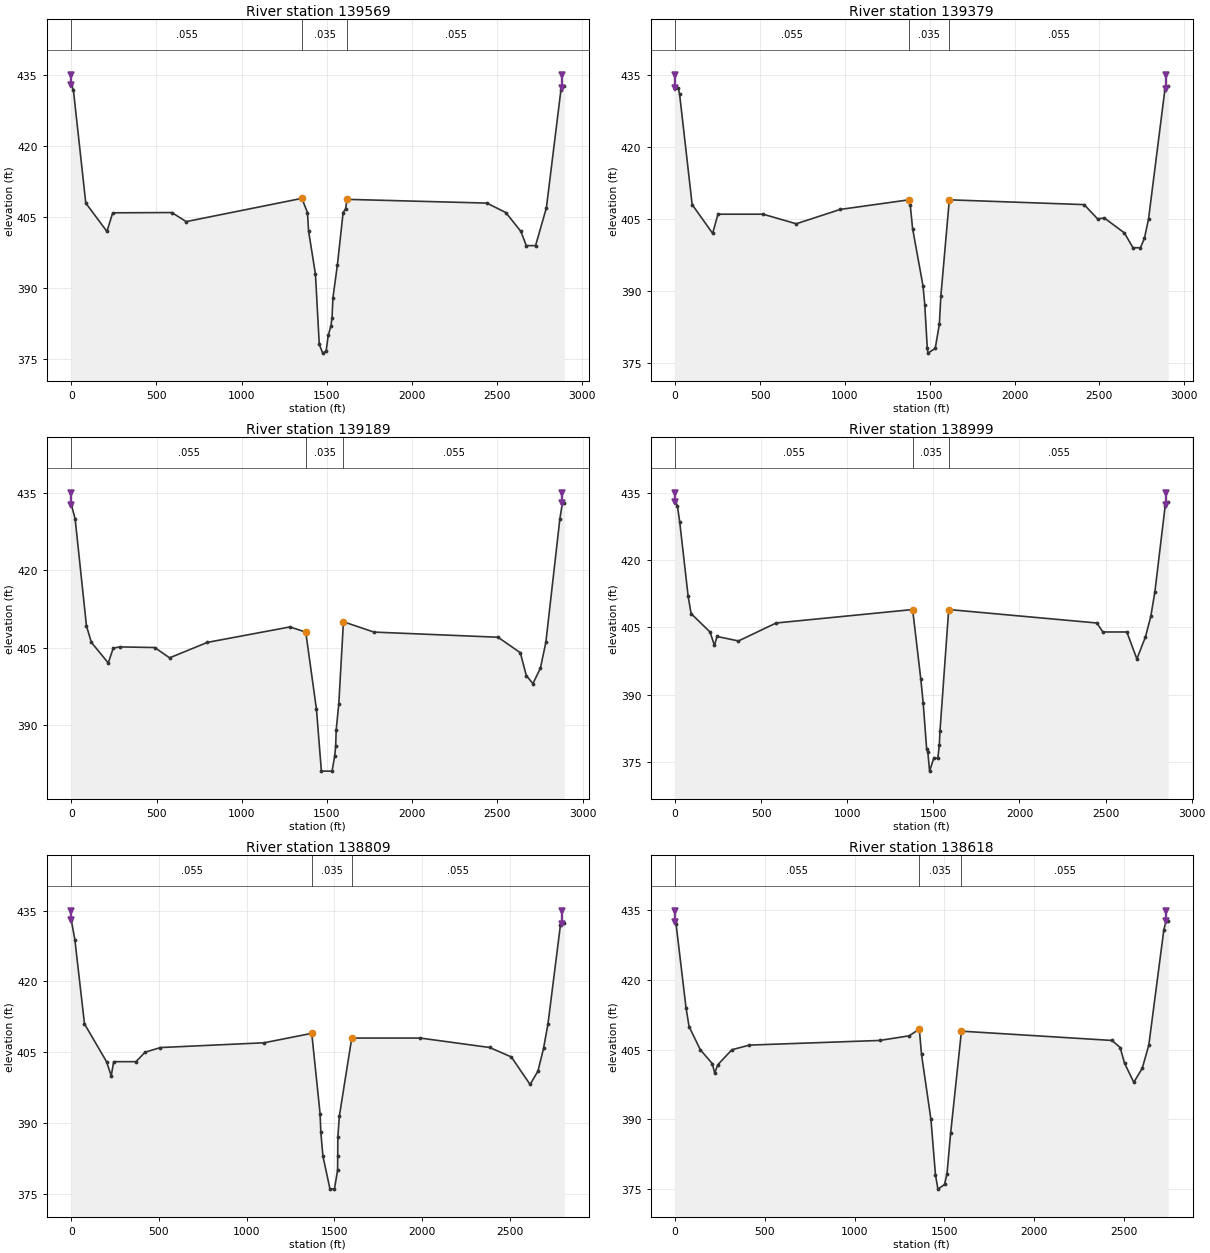
Type RM Length L Ch R = 1 ,139569  ,195,195,195
BEGIN DESCRIPTION:
This cross section corresponds to cross section 139569 of the non-georeferenced CDC model which was the source of this model.
END DESCRIPTION:
XS GIS Cut Line= 2
2469246.91357258 6978631.25771632469262.932569416975736.74217989
#Sta/Elev= 30
       0     433   11.98     432   84.92     408     209     402  242.97  405.94
     590     406  674.44  404.08 1353.45     409 1386.33     406 1392.88  402.05
    1433     393 1455.57   378.1 1475.84  376.25 1495.75  376.65 1508.11     380
 1524.06     382 1530.45  383.76 1535.68  387.93 1562.15  394.97 1595.57     406
 1610.31  406.81 1618.66  408.79 2439.14     408  2550.6     406 2639.17     402
 2670.84     399 2725.32     399 2788.85     407 2874.36     432 2894.56   432.7
#Mann= 3 ,0,0
       0    .055       0 1353.45    .035       0 1618.66    .055       0
Levee=-1,0,435.14,-1,2882,435.14,,
#XS Ineff= 2 , 0
         1353.45     409 1618.66          408.79
Permanent Ineff=
       F       F
Bank Sta=1353.45,1618.66
XS Rating Curve= 0 ,0
Exp/Cntr=0.3,0.1

Type RM Length L Ch R = 1 ,139379  ,190,190,190
BEGIN DESCRIPTION:
This cross section corresponds to cross section 139379 of the non-georeferenced CDC model which was the source of this model.
END DESCRIPTION:
XS GIS Cut Line= 2
2469440.118238666978651.492583962469458.975484436975746.05384105
#Sta/Elev= 30
       0  432.27   18.04  432.42   26.33     431  100.19     408  220.93     402
  252.29     406  518.13     406  713.38     404  973.48     407 1377.86     409
 1385.11     408 1399.14     403  1460.7     391 1470.85  387.11 1485.77     378
 1489.75     377 1532.58     378  1556.7     383 1565.88     389 1615.57     409
 2410.04     408 2488.71  405.04 2529.46  405.19 2647.11   402.1 2697.66     399
 2741.77     399 2765.32     401 2789.47     405 2885.85     432  2905.5   432.7
#Mann= 3 ,0,0
       0    .055       0 1377.86    .035       0 1615.57    .055       0
Levee=-1,0,435.09,-1,2892,435.09,,
#XS Ineff= 2 , 0
         1377.86     409 1615.57             409
Permanent Ineff=
       F       F
Bank Sta=1377.86,1615.57
XS Rating Curve= 0 ,0
Exp/Cntr=0.3,0.1

Type RM Length L Ch R = 1 ,139189  ,190,190,190
BEGIN DESCRIPTION:
This cross section corresponds to cross section 139189 of the non-georeferenced CDC model which was the source of this model.
END DESCRIPTION:
XS GIS Cut Line= 2
2469628.852769356978648.788849222469650.451479446975755.42947847
#Sta/Elev= 30
       0  432.74   22.36     430   88.89  409.19   117.7     406     217     402
  245.86  404.87  283.46  405.12  489.62     405  576.65     403  798.64     406
 1283.08     409 1375.68     408 1438.55     393  1467.4     381 1530.04     381
 1545.85     384 1551.25   385.9 1554.25     389  1569.5     394 1596.78     410
 1775.88     408 2503.76     407 2634.59     404 2670.04  399.55 2708.68     398
 2752.49  400.97 2784.61     406 2866.88     430 2881.55     433 2893.44     433
#Mann= 3 ,0,0
       0    .055       0 1375.68    .035       0 1596.78    .055       0
Levee=-1,0,435.04,-1,2882,435.04,,
#XS Ineff= 2 , 0
         1375.68     408 1596.78             410
Permanent Ineff=
       F       F
Bank Sta=1375.68,1596.78
XS Rating Curve= 0 ,0
Exp/Cntr=0.3,0.1

Type RM Length L Ch R = 1 ,138999  ,185,185,185
BEGIN DESCRIPTION:
This cross section corresponds to cross section 138999 of the non-georeferenced CDC model which was the source of this model.
END DESCRIPTION:
XS GIS Cut Line= 2
2469817.596158276978646.412869722469840.628920586975782.60527714
#Sta/Elev= 30
       0     433   12.94  432.11   26.33  428.57   75.31     412   92.51  408.09
  202.59     404  228.17     401  243.06     403  367.76     402  586.47     406
 1379.33     409 1426.61  393.56 1440.45  388.27 1460.68     378 1467.61  377.27
 1477.74     373 1502.51  375.93 1525.82  375.87 1534.33  378.86 1538.31     382
 1588.79     409 2449.54     406 2484.11     404 2623.44     404 2681.75     398
  2731.4  402.88 2762.83   407.5 2786.58     413 2845.81     432  2863.9     433
#Mann= 3 ,0,0
       0    .055       0 1379.33    .035       0 1588.79    .055       0
Levee=-1,0,435,-1,2852,435,,
#XS Ineff= 2 , 0
         1379.33     409 1588.79             409
Permanent Ineff=
       F       F
Bank Sta=1379.33,1588.79
XS Rating Curve= 0 ,0
Exp/Cntr=0.3,0.1

Type RM Length L Ch R = 1 ,138809  ,195,196,195
BEGIN DESCRIPTION:
This cross section corresponds to cross section 138809 of the non-georeferenced CDC model which was the source of this model.
END DESCRIPTION:
XS GIS Cut Line= 2
2470000.999662856978630.03429355  2470026.0002696975817.96577072
#Sta/Elev= 30
       0  432.93   20.22  428.85   75.05     411  200.89     403  227.44     400
   241.7     403  368.58     403  420.65     405  508.34  405.99 1099.55     407
 1371.32     409 1418.68     392 1423.13     388 1435.01     383 1474.87  376.09
 1500.66     376 1518.58     380 1519.34     383 1519.94     387 1528.78  391.49
 1599.31     408 1990.25     408 2386.08     406 2509.63     404 2616.49  398.17
 2661.34     401 2693.08  405.79 2718.54     411 2789.79     432 2812.18   432.4
#Mann= 3 ,0,0
       0    .055       0 1371.32    .035       0 1599.31    .055       0
Levee=-1,0,434.95,-1,2798,434.95,,
#XS Ineff= 2 , 0
         1371.32     409 1599.31             408
Permanent Ineff=
       F       F
Bank Sta=1371.32,1599.31
XS Rating Curve= 0 ,0
Exp/Cntr=0.3,0.1

Type RM Length L Ch R = 1 ,138618  ,190,191,190
BEGIN DESCRIPTION:
This cross section corresponds to cross section 138618 of the non-georeferenced CDC model which was the source of this model.
END DESCRIPTION:
XS GIS Cut Line= 2
2470194.587858356978634.829559552470222.725597356975887.25368989
#Sta/Elev= 30
       0  432.54    5.28     432   60.45  414.09   77.44     410  140.32     405
  207.28     402  220.27     400  238.09   401.8  316.23     405  413.99     406
 1139.13     407 1304.31     408 1360.69  409.45 1372.79     404 1425.39     390
 1450.55   378.1  1464.3     375 1501.06     376 1514.76  378.32 1535.07     387
 1595.34     409 2434.57     407 2479.72  405.48 2504.03  402.12  2555.8     398
 2602.88     401 2639.44     406 2723.19   430.8 2735.99  432.78 2747.72  432.74
#Mann= 3 ,0,0
       0    .055       0 1360.69    .035       0 1595.34    .055       0
Levee=-1,0,434.9,-1,2736,434.9,,
#XS Ineff= 2 , 0
         1360.69  409.45 1595.34             409
Permanent Ineff=
       F       F
Bank Sta=1360.69,1595.34
XS Rating Curve= 0 ,0
Exp/Cntr=0.3,0.1

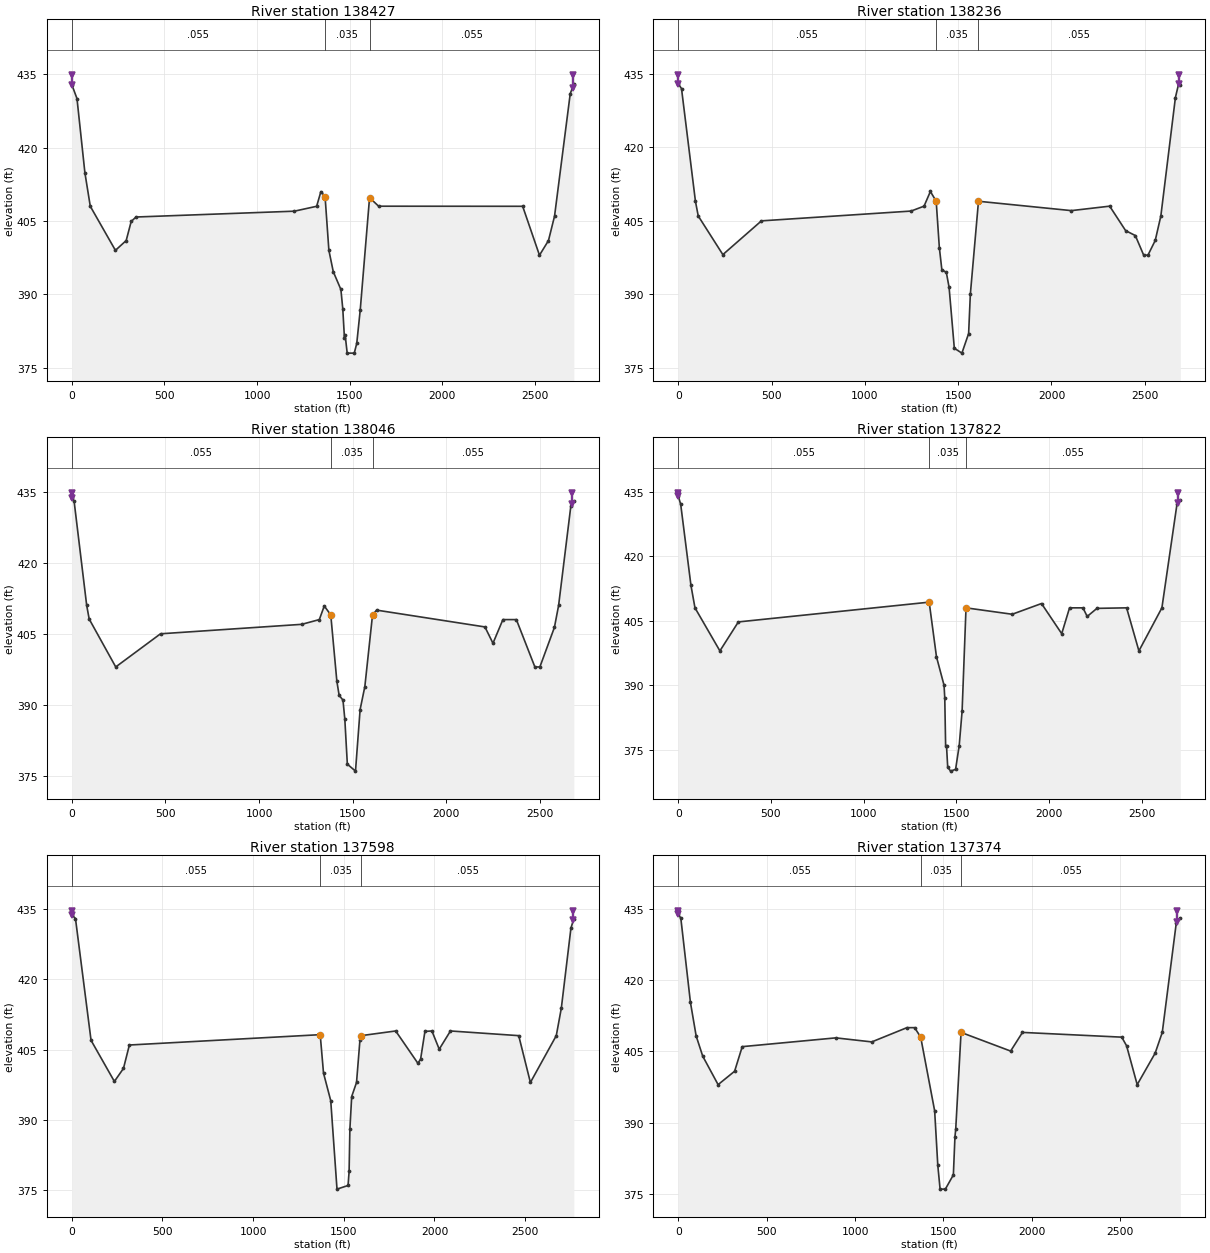
Type RM Length L Ch R = 1 ,138427  ,190,191,190
BEGIN DESCRIPTION:
This cross section corresponds to cross section 138427 of the non-georeferenced CDC model which was the source of this model.
END DESCRIPTION:
XS GIS Cut Line= 2
2470382.504477266978656.669738962470415.412547926975946.75947638
#Sta/Elev= 30
       0  432.88   28.18     430   70.93  414.83   99.97     408  235.62     399
  293.76     401  320.72   404.9  346.82  405.81 1201.22     407 1321.78     408
 1344.67     411 1367.25     410 1387.86     399 1411.53  394.64 1452.71     391
 1462.96     387 1471.83   381.1 1475.47  381.76 1486.68     378 1524.93     378
 1538.32     380 1557.21  386.87 1607.36  409.76 1656.34  408.02 2433.89     408
 2524.59     398 2573.18     401 2605.98     406 2690.62     431 2710.11     433
#Mann= 3 ,0,0
       0    .055       0 1367.25    .035       0 1607.36    .055       0
Levee=-1,0,434.86,-1,2703,434.86,,
#XS Ineff= 2 , 0
         1367.25     410 1607.36          409.76
Permanent Ineff=
       F       F
Bank Sta=1367.25,1607.36
XS Rating Curve= 0 ,0
Exp/Cntr=0.3,0.1

Type RM Length L Ch R = 1 ,138236  ,186,186,186
BEGIN DESCRIPTION:
This cross section corresponds to cross section 138236 of the non-georeferenced CDC model which was the source of this model.
END DESCRIPTION:
XS GIS Cut Line= 2
2470570.618602346978660.729770212470608.248776446975970.60326071
#Sta/Elev= 30
       0     433   17.55     432   92.16     409  107.15     406  239.11  398.11
  445.85     405  1247.7     407 1317.19     408 1351.19     411 1382.27     409
 1399.17  399.53 1412.66     395 1436.55  394.49 1451.34  391.44 1479.41     379
 1520.01     378 1556.08     382 1565.22     390 1608.86     409 2106.59  407.09
 2311.84     408 2397.51     403 2449.39     402 2494.13     398 2516.98     398
 2556.02     401  2586.1     406 2664.14  430.17  2681.4  432.98 2690.39  432.64
#Mann= 3 ,0,0
       0    .055       0 1382.27    .035       0 1608.86    .055       0
Levee=-1,0,434.81,-1,2681,434.81,,
#XS Ineff= 2 , 0
         1382.27     409 1608.86             409
Permanent Ineff=
       F       F
Bank Sta=1382.27,1608.86
XS Rating Curve= 0 ,0
Exp/Cntr=0.3,0.1

Type RM Length L Ch R = 1 ,138046  ,227,229,227
BEGIN DESCRIPTION:
This cross section corresponds to cross section 138046 of the non-georeferenced CDC model which was the source of this model.
END DESCRIPTION:
XS GIS Cut Line= 2
2470753.838380256978653.624469462470795.851747666975973.37359639
#Sta/Elev= 30
       0  433.71   12.45  433.01   79.64     411   93.03  408.11  234.73     398
  473.75     405 1227.93     407 1321.64     408 1348.09  410.87 1382.75     409
 1415.25     395 1427.52     392 1447.95     391 1457.77     387 1471.24  377.48
  1514.8     376 1539.47     389 1564.74  393.86 1605.78     409 1627.47     410
  2205.9  406.45 2248.79     403  2301.8     408 2373.72     408 2472.53     398
  2499.2     398 2576.86  406.35 2599.26     411  2664.6     432 2680.58     433
#Mann= 3 ,0,0
       0    .055       0 1382.75    .035       0 1605.78    .055       0
Levee=-1,0,434.77,-1,2671,434.77,,
#XS Ineff= 2 , 0
         1382.75     409 1605.78             409
Permanent Ineff=
       F       F
Bank Sta=1382.75,1605.78
XS Rating Curve= 0 ,0
Exp/Cntr=0.3,0.1

Type RM Length L Ch R = 1 ,137822  ,221,223,221
BEGIN DESCRIPTION:
This cross section corresponds to cross section 137822 of the non-georeferenced CDC model which was the source of this model.
END DESCRIPTION:
XS GIS Cut Line= 2
2470988.226362916978659.057529462471019.093755256975952.44352013
#Sta/Elev= 30
       0     434    13.4     432   68.62  413.19   90.24     408  224.62     398
  324.15  404.73  1352.9  409.32 1392.25  396.63 1433.14     390 1436.95     387
 1441.55     376 1446.38  375.89  1452.8     371 1468.35  370.08 1495.24  370.49
 1514.76     376 1530.36     384  1551.5     408 1800.39  406.51 1958.44     409
 2067.42     402 2109.63     408  2181.9     408 2204.81     406 2257.34  407.88
 2417.25     408 2483.58     398 2607.57     408 2688.55     432 2706.79     433
#Mann= 3 ,0,0
       0    .055       0  1352.9    .035       0  1551.5    .055       0
Levee=-1,0,434.71,-1,2695,434.71,,
#XS Ineff= 2 , 0
          1352.9  409.32  1551.5             408
Permanent Ineff=
       F       F
Bank Sta=1352.9,1551.5
XS Rating Curve= 0 ,0
Exp/Cntr=0.3,0.1

Type RM Length L Ch R = 1 ,137598  ,222,224,222
BEGIN DESCRIPTION:
This cross section corresponds to cross section 137598 of the non-georeferenced CDC model which was the source of this model.
END DESCRIPTION:
XS GIS Cut Line= 2
2471217.55234784 6978669.0627588 2471237.3935155 6975900.4639653
#Sta/Elev= 30
       0  433.86   20.47     433  106.32     407  234.96  398.22  285.12     401
  317.65     406 1369.98  408.21 1388.26     400 1428.08  394.11 1462.59  375.22
 1523.66     376 1529.34     379 1533.61     388 1543.63     395 1570.28     398
    1589     407 1595.75     408 1786.19     409 1908.65   402.1 1923.66     403
 1947.54  408.91 1985.91     409 2026.33  405.11 2088.26     409 2464.63     408
 2529.09     398 2671.81     408 2699.61  413.86 2752.63  430.96 2768.67     433
#Mann= 3 ,0,0
       0    .055       0 1369.98    .035       0 1595.75    .055       0
Levee=-1,0,434.66,-1,2766,434.66,,
#XS Ineff= 2 , 0
         1369.98  408.21 1595.75             408
Permanent Ineff=
       F       F
Bank Sta=1369.98,1595.75
XS Rating Curve= 0 ,0
Exp/Cntr=0.3,0.1

Type RM Length L Ch R = 1 ,137374  ,222,224,222
BEGIN DESCRIPTION:
This cross section corresponds to cross section 137374 of the non-georeferenced CDC model which was the source of this model.
END DESCRIPTION:
XS GIS Cut Line= 2
2471446.975773516978676.649029722471455.633892696975836.90208454
#Sta/Elev= 30
       0     434    14.8     433      69  415.32  101.36  408.25  138.49     404
   225.5     398  318.82  400.82  361.98     406  891.19  407.85 1094.75     407
 1293.39     410 1337.01     410 1371.34     408  1450.3  392.49 1468.09     381
 1481.09     376 1510.85     376 1556.17     379 1565.11     387 1569.48  388.62
 1599.63     409 1880.04  405.07 1947.01     409 2508.54     408  2535.9  406.18
 2595.91     398 2697.44  404.63 2737.74     409  2816.8     432 2839.76     433
#Mann= 3 ,0,0
       0    .055       0 1371.34    .035       0 1599.63    .055       0
Levee=-1,0,434.6,-1,2823,434.6,,
#XS Ineff= 2 , 0
         1371.34     408 1599.63             409
Permanent Ineff=
       F       F
Bank Sta=1371.34,1599.63
XS Rating Curve= 0 ,0
Exp/Cntr=0.3,0.1

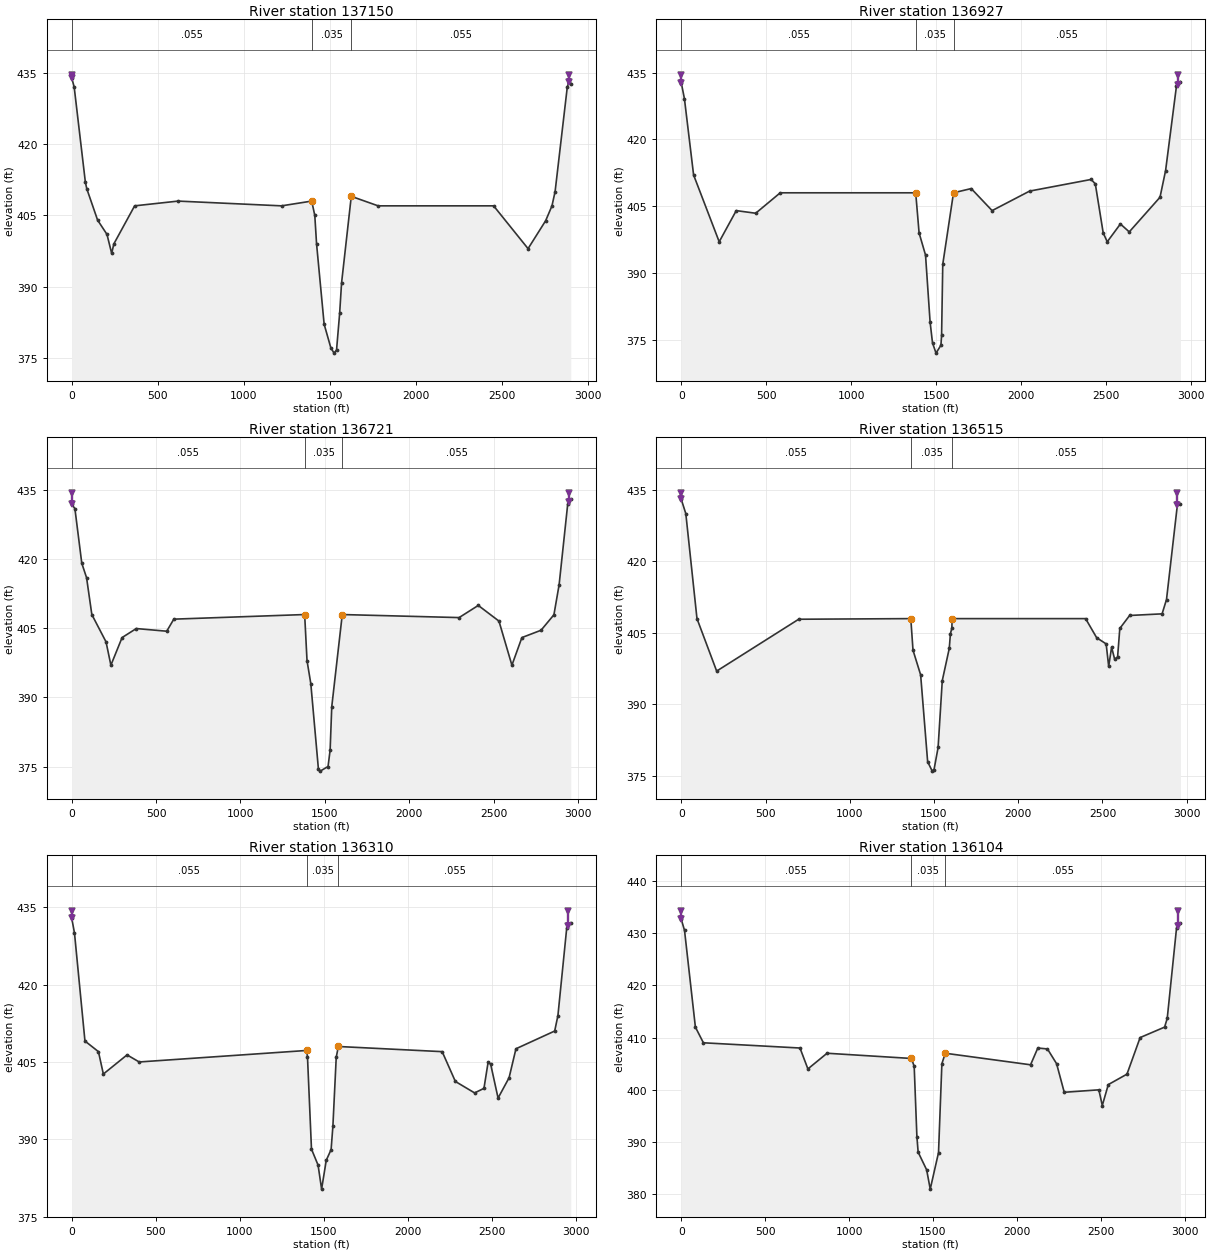
Type RM Length L Ch R = 1 ,137150  ,219,220,219
BEGIN DESCRIPTION:
This cross section corresponds to cross section 137150 of the non-georeferenced CDC model which was the source of this model.
END DESCRIPTION:
XS GIS Cut Line= 2
2471676.451364436978666.767487792471673.68923083 6975768.8087168
#Sta/Elev= 30
       0  433.98   14.81     432   79.67     412   87.96   410.6   150.8     404
  205.21     401  232.53     397  245.12     399  365.82     407  618.14     408
 1218.73     407 1393.77     408 1411.71     405 1422.01     399 1466.02  382.11
 1504.71  377.17 1523.48  376.03  1538.1  376.71 1556.14  384.44 1567.12  390.77
 1623.55     409 1779.34     407    2450     407 2649.86     398 2752.09  403.88
 2788.71     407 2806.84     410 2877.59  431.97 2886.31  432.99 2897.96   432.6
#Mann= 3 ,0,0
       0    .055       0 1393.77    .035       0 1623.55    .055       0
Levee=-1,0,434.55,-1,2886,434.55,,
#XS Ineff= 2 , 0
         1393.77     408 1623.55             409
Permanent Ineff=
       F       F
Bank Sta=1393.77,1623.55
XS Rating Curve= 0 ,0
Exp/Cntr=0.3,0.1

Type RM Length L Ch R = 1 ,136927  ,211,211,211
BEGIN DESCRIPTION:
This cross section corresponds to cross section 136927 of the non-georeferenced CDC model which was the source of this model.
END DESCRIPTION:
XS GIS Cut Line= 2
 2471901.0224376 6978667.20843182471887.003764846975729.79206255
#Sta/Elev= 30
       0  432.68   18.42  429.15   72.47     412  223.12     397  323.45     404
  437.78  403.41  582.32     408 1379.45     408 1399.36     399 1437.26  394.02
 1464.11     379 1478.34   374.3 1499.04     372 1527.94  373.78 1531.78     376
  1538.7  391.95 1601.93     408 1706.19  408.95 1829.13     404 2049.58  408.38
 2412.14     411 2436.43     410  2482.8     399  2506.6     397 2584.02     401
 2636.19  399.22 2817.13     407 2850.03     413 2914.05     432 2937.45  432.95
#Mann= 3 ,0,0
       0    .055       0 1379.45    .035       0 1601.93    .055       0
Levee=-1,0,434.49,-1,2921,434.49,,
#XS Ineff= 2 , 0
         1379.45     408 1601.93             408
Permanent Ineff=
       F       F
Bank Sta=1379.45,1601.93
XS Rating Curve= 0 ,0
Exp/Cntr=0.3,0.1

Type RM Length L Ch R = 1 ,136721  ,206,206,206
BEGIN DESCRIPTION:
This cross section corresponds to cross section 136721 of the non-georeferenced CDC model which was the source of this model.
END DESCRIPTION:
XS GIS Cut Line= 4
2472150.775875096978695.21657789 2472104.52399916977547.86519805
2472103.815010996977029.416103722472062.886615196975739.17819864
#Sta/Elev= 30
       0     432   19.42     431   60.16  419.15   88.55     416  119.73     408
  203.87  402.07  232.68     397  298.98     403  383.12  404.96  563.52  404.38
  605.43     407 1380.73     408 1394.72     398 1417.17     393 1462.47  374.37
  1472.6     374 1519.31     375  1531.7  378.58 1541.31     388 1603.56     408
 2295.83  407.34 2409.44  409.98 2531.96  406.58 2608.74     397 2667.91     403
 2781.31  404.59 2857.67  407.95 2888.47  414.47 2939.41     432 2957.62     433
#Mann= 3 ,0,0
       0    .055       0 1380.73    .035       0 1603.56    .055       0
Levee=-1,0,434.43,-1,2947,434.43,,
#XS Ineff= 2 , 0
         1380.73     408 1603.56             408
Permanent Ineff=
       F       F
Bank Sta=1380.73,1603.56
XS Rating Curve= 0 ,0
Exp/Cntr=0.3,0.1

Type RM Length L Ch R = 1 ,136515  ,206,205,206
BEGIN DESCRIPTION:
This cross section corresponds to cross section 136515 of the non-georeferenced CDC model which was the source of this model.
END DESCRIPTION:
XS GIS Cut Line= 4
2472395.642839436978691.362911052472308.582974176977551.52103063
2472309.668929996977031.354091972472233.732073996975733.77400997
#Sta/Elev= 30
       0     433    26.9     430   93.14     408     210     397  696.87  407.87
 1362.41     408  1375.5  401.38 1420.83  396.21 1462.41     378 1489.68  376.03
 1500.34  376.35 1524.52     381 1549.25     395 1590.79  401.76 1597.52  404.82
  1606.1     406 1607.73     408    2400     408 2465.63     404 2522.06   402.7
 2537.07     398 2554.38     402 2572.72  399.47 2590.04     400  2603.1  405.94
 2661.43  408.66 2854.09     409  2880.3     412  2945.4     432 2963.13     432
#Mann= 3 ,0,0
       0    .055       0 1362.41    .035       0 1607.73    .055       0
Levee=-1,0,434.37,-1,2945,434.37,,
#XS Ineff= 2 , 0
         1362.41     408 1607.73             408
Permanent Ineff=
       F       F
Bank Sta=1362.41,1607.73
XS Rating Curve= 0 ,0
Exp/Cntr=0.3,0.1

Type RM Length L Ch R = 1 ,136310  ,205,205,205
BEGIN DESCRIPTION:
This cross section corresponds to cross section 136310 of the non-georeferenced CDC model which was the source of this model.
END DESCRIPTION:
XS GIS Cut Line= 4
2472639.935657926978690.246115392472512.64194927 6977555.1771913
2472515.522848996977033.29208022 2472404.82031456975734.68969055
#Sta/Elev= 30
       0     433   17.04     430   79.24  409.06  159.42     407   188.6  402.66
  329.49  406.37  401.67     405 1397.13  407.23 1402.13     406 1425.85   388.1
 1465.07     385 1486.02  380.34 1513.82  385.95 1542.52     388 1553.13  392.53
 1573.01  405.91 1585.74     408 2202.78     407  2281.3  401.22 2395.52     399
 2451.18  399.88 2476.14     405 2491.06  404.56  2535.1     398 2600.51  401.94
  2641.4  407.56 2871.66     411  2890.9     414 2943.25     431 2967.39     432
#Mann= 3 ,0,0
       0    .055       0 1397.13    .035       0 1585.74    .055       0
Levee=-1,0,434.31,-1,2950,434.31,,
#XS Ineff= 2 , 0
         1397.13  407.23 1585.74             408
Permanent Ineff=
       F       F
Bank Sta=1397.13,1585.74
XS Rating Curve= 0 ,0
Exp/Cntr=0.3,0.1

Type RM Length L Ch R = 1 ,136104  ,201,200,201
BEGIN DESCRIPTION:
This cross section corresponds to cross section 136104 of the non-georeferenced CDC model which was the source of this model.
END DESCRIPTION:
XS GIS Cut Line= 4
2472883.536220586978686.750715552472716.700924346977558.83302388
2472721.376111846977035.23105271  2472575.5581626975732.07650679
#Sta/Elev= 30
       0  432.62   19.31   430.5   84.07     412  131.74     409  707.49     408
  754.59     404  868.78     407    1372     406 1388.13  404.48  1404.3     391
 1411.72  388.07 1462.39  384.69 1483.75     381 1533.17     388 1553.17     405
 1573.52     407 2081.67  404.79 2124.91     408 2182.44  407.82 2236.83     405
 2282.44  399.53 2488.67     400 2509.24     397    2545     401 2656.28     403
 2734.74     410 2880.61     412 2896.28  413.67 2951.86     431  2975.1  431.85
#Mann= 3 ,0,0
       0    .055       0    1372    .035       0 1573.52    .055       0
Levee=-1,0,434.25,-1,2959,434.25,,
#XS Ineff= 2 , 0
            1372     405 1559.29          405.56
Permanent Ineff=
       F       F
Bank Sta=1372,1573.52
XS Rating Curve= 0 ,0
Exp/Cntr=0.3,0.1

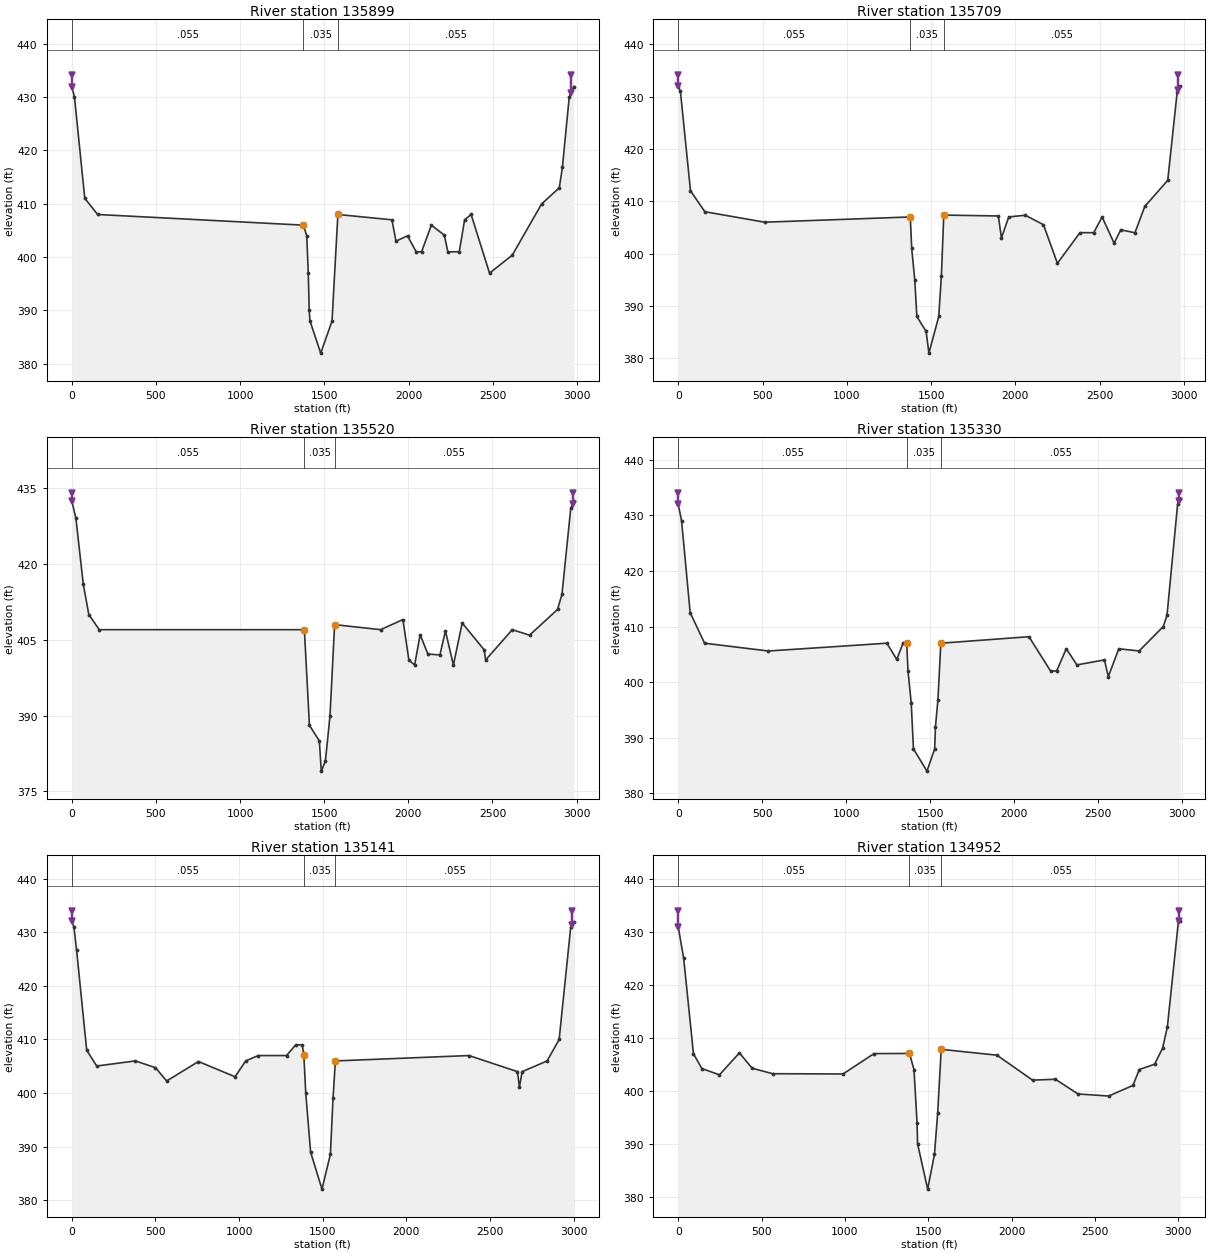
Type RM Length L Ch R = 1 ,135899  ,194,194,194
BEGIN DESCRIPTION:
This cross section corresponds to cross section 135899 of the non-georeferenced CDC model which was the source of this model.
END DESCRIPTION:
XS GIS Cut Line= 4
2473125.89039466 6978691.28515532472916.00006643 6977549.0000383
2472922.000054426977023.000106052472744.31077725 6975741.4524723
#Sta/Elev= 30
       0     432   16.09     430   77.24  411.04  153.27     408 1375.52     406
 1395.23     404 1404.35     397 1410.03     390 1414.24  388.06 1478.17     382
  1545.3     388 1580.14     408 1901.03     407 1925.09     403 1993.57     404
 2044.92     401 2077.25     401 2134.98     406 2212.02  404.13 2233.16     401
 2300.82     401 2332.65     407 2371.31     408 2480.55     397 2615.36  400.36
 2790.27     410 2894.81     413 2913.33  416.85 2953.79     430 2981.25     432
#Mann= 3 ,0,0
       0    .055       0 1375.52    .035       0 1580.14    .055       0
Levee=-1,0,434.19,-1,2964,434.19,,
#XS Ineff= 2 , 0
         1375.52     406 1580.14             408
Permanent Ineff=
       F       F
Bank Sta=1375.52,1580.14
XS Rating Curve= 0 ,0
Exp/Cntr=0.3,0.1

Type RM Length L Ch R = 1 ,135709  ,191,190,191
BEGIN DESCRIPTION:
This cross section corresponds to cross section 135709 of the non-georeferenced CDC model which was the source of this model.
END DESCRIPTION:
XS GIS Cut Line= 4
2473341.083861926978691.360942542473124.752929756977559.91012147
 2473107.03183666977036.14509289 2472907.63656616975749.28218105
#Sta/Elev= 30
       0     432   12.93     431   72.73     412  157.97     408  513.19     406
 1376.58     407 1384.88     401 1403.04     395 1415.38     388 1470.43  385.14
 1486.93     381 1545.44     388 1560.98  395.82  1575.2  407.36 1898.79  407.19
  1917.2     403 1960.38     407 2058.82  407.33 2166.46  405.52 2249.12  398.15
 2382.91     404 2464.65     404 2514.36     407 2585.48     402 2625.12  404.55
 2708.98  403.98 2767.35     409 2903.75     414 2959.68  430.88 2978.23     432
#Mann= 3 ,0,0
       0    .055       0 1376.58    .035       0  1575.2    .055       0
Levee=-1,0,434.14,-1,2965,434.14,,
#XS Ineff= 2 , 0
         1376.58     407  1575.2          407.36
Permanent Ineff=
       F       F
Bank Sta=1376.58,1575.2
XS Rating Curve= 0 ,0
Exp/Cntr=0.3,0.1

Type RM Length L Ch R = 1 ,135520  ,190,190,190
BEGIN DESCRIPTION:
This cross section corresponds to cross section 135520 of the non-georeferenced CDC model which was the source of this model.
END DESCRIPTION:
XS GIS Cut Line= 4
2473553.79144177 6978689.87570932473328.745960096977557.33007413
2473286.83298618 6977035.12114482473066.306524346975748.93638122
#Sta/Elev= 30
       0   432.5   24.47  429.08   68.45     416  101.26     410  163.31     407
 1382.24     407 1412.28  388.06 1471.06     385 1482.83     379 1507.32     381
 1534.53     390 1561.87     408 1834.93     407 1967.77     409 2003.23     401
 2037.43     400 2070.13     406 2116.08  402.18 2187.75     402 2220.41  406.77
 2267.75     400 2320.17  408.32 2450.87     403 2459.34     401 2617.63     407
 2720.53  405.91 2886.53     411  2912.9     414 2965.15     431 2983.53   432.5
#Mann= 3 ,0,0
       0    .055       0 1382.24    .035       0 1561.87    .055       0
Levee=-1,0,434.09,-1,2977,434.09,,
#XS Ineff= 2 , 0
         1382.24     407 1561.87             408
Permanent Ineff=
       F       F
Bank Sta=1382.24,1561.87
XS Rating Curve= 0 ,0
Exp/Cntr=0.3,0.1

Type RM Length L Ch R = 1 ,135330  ,191,190,191
BEGIN DESCRIPTION:
This cross section corresponds to cross section 135330 of the non-georeferenced CDC model which was the source of this model.
END DESCRIPTION:
XS GIS Cut Line= 4
 2473765.54823616978683.721194042473532.738006176977554.75101104
   2473466.635126977034.096212462473223.985014776975743.44689088
#Sta/Elev= 30
       0     432   19.93     429   71.09   412.5  156.92     407  536.84   405.6
 1242.66     407 1302.06  404.08 1338.89     407 1360.92     407 1368.79  402.01
 1387.79  396.29  1401.3     388 1481.68     384 1527.47     388 1532.26     392
 1546.89  396.77 1564.26     407 2089.19  408.17 2217.99     402 2253.73     402
  2311.5     406 2374.91   403.1 2538.78     404 2562.01     401 2624.26     406
  2745.6  405.61 2889.32     410 2911.47     412  2974.8     432 2990.82     433
#Mann= 3 ,0,0
       0    .055       0 1360.92    .035       0 1564.26    .055       0
Levee=-1,0,434.04,-1,2985,434.04,,
#XS Ineff= 2 , 0
         1360.92     407 1564.26             407
Permanent Ineff=
       F       F
Bank Sta=1360.92,1564.26
XS Rating Curve= 0 ,0
Exp/Cntr=0.3,0.1

Type RM Length L Ch R = 1 ,135141  ,187,186,187
BEGIN DESCRIPTION:
This cross section corresponds to cross section 135141 of the non-georeferenced CDC model which was the source of this model.
END DESCRIPTION:
XS GIS Cut Line= 4
2473980.609157686978693.309101392473736.731036516977552.17194797
2473646.435941526977033.071936292473384.265206016975751.62666455
#Sta/Elev= 30
       0     432   12.73     431   28.75   426.7   89.28     408  149.07  405.05
  379.82     406  500.55  404.74  567.35  402.26  757.33  405.89  976.43  403.05
 1039.78     406  1114.8     407 1283.83     407  1339.1     409 1377.81     409
 1387.47  407.13    1399     400 1427.94     389 1496.02   382.1 1546.15  388.59
 1561.97     399 1576.06     406 2374.87     407 2664.87     404 2676.21  401.14
 2692.87     404 2841.93     406 2913.92     410 2983.25     431 3001.79  431.95
#Mann= 3 ,0,0
       0    .055       0 1387.47    .035       0 1576.06    .055       0
Levee=-1,0,433.98,-1,2991,433.98,,
#XS Ineff= 2 , 0
         1387.47  407.13 1576.06             406
Permanent Ineff=
       F       F
Bank Sta=1387.47,1576.06
XS Rating Curve= 0 ,0
Exp/Cntr=0.3,0.1

Type RM Length L Ch R = 1 ,134952  ,69,69,69
BEGIN DESCRIPTION:
This cross section corresponds to cross section 134952 of the non-georeferenced CDC model which was the source of this model.
END DESCRIPTION:
XS GIS Cut Line= 2
2474191.36496976 6978689.64539482473540.961414936975748.88159131
#Sta/Elev= 30
       0   430.9   32.36  425.04   91.22     407  141.66  404.18  247.43     403
  367.05  407.14  442.96  404.25  566.38  403.21  988.67  403.16 1174.36     407
 1387.05  407.03 1414.16     404 1432.56     394 1435.69     390 1496.36  381.44
 1537.03     388 1556.23  395.77 1577.52  407.81    1912   406.7 2125.37     402
 2262.68  402.16 2397.74  399.39 2582.19     399 2727.76     401 2765.89     404
 2857.42     405 2905.38     408 2934.05     412 3000.71     432 3011.83     432
#Mann= 3 ,0,0
       0    .055       0 1387.05    .035       0 1577.52    .055       0
Levee=-1,0,433.93,-1,3001,433.93,,
#XS Ineff= 2 , 0
         1387.05  407.03 1577.52          407.81
Permanent Ineff=
       F       F
Bank Sta=1387.05,1577.52
XS Rating Curve= 0 ,0
Exp/Cntr=0.3,0.1

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