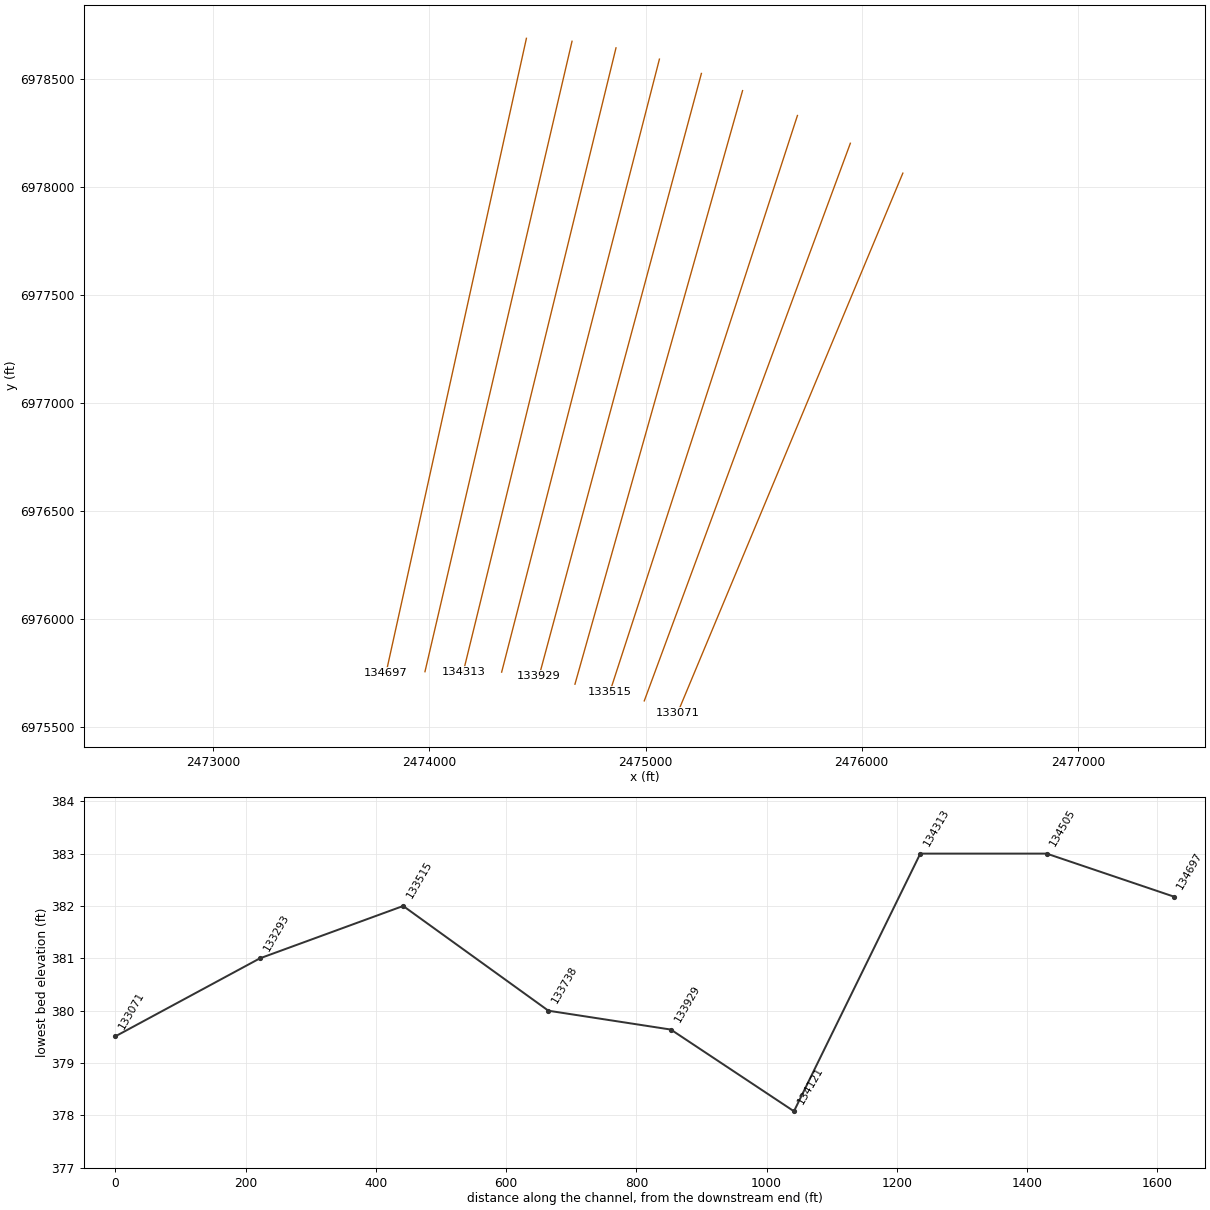
HEC-RAS study CDC_Consolidated_Model.prj: Upper Trinity CDC Consolidated Model

--- CDC_Consolidated_Model.g13 (geometry) --- (continued)

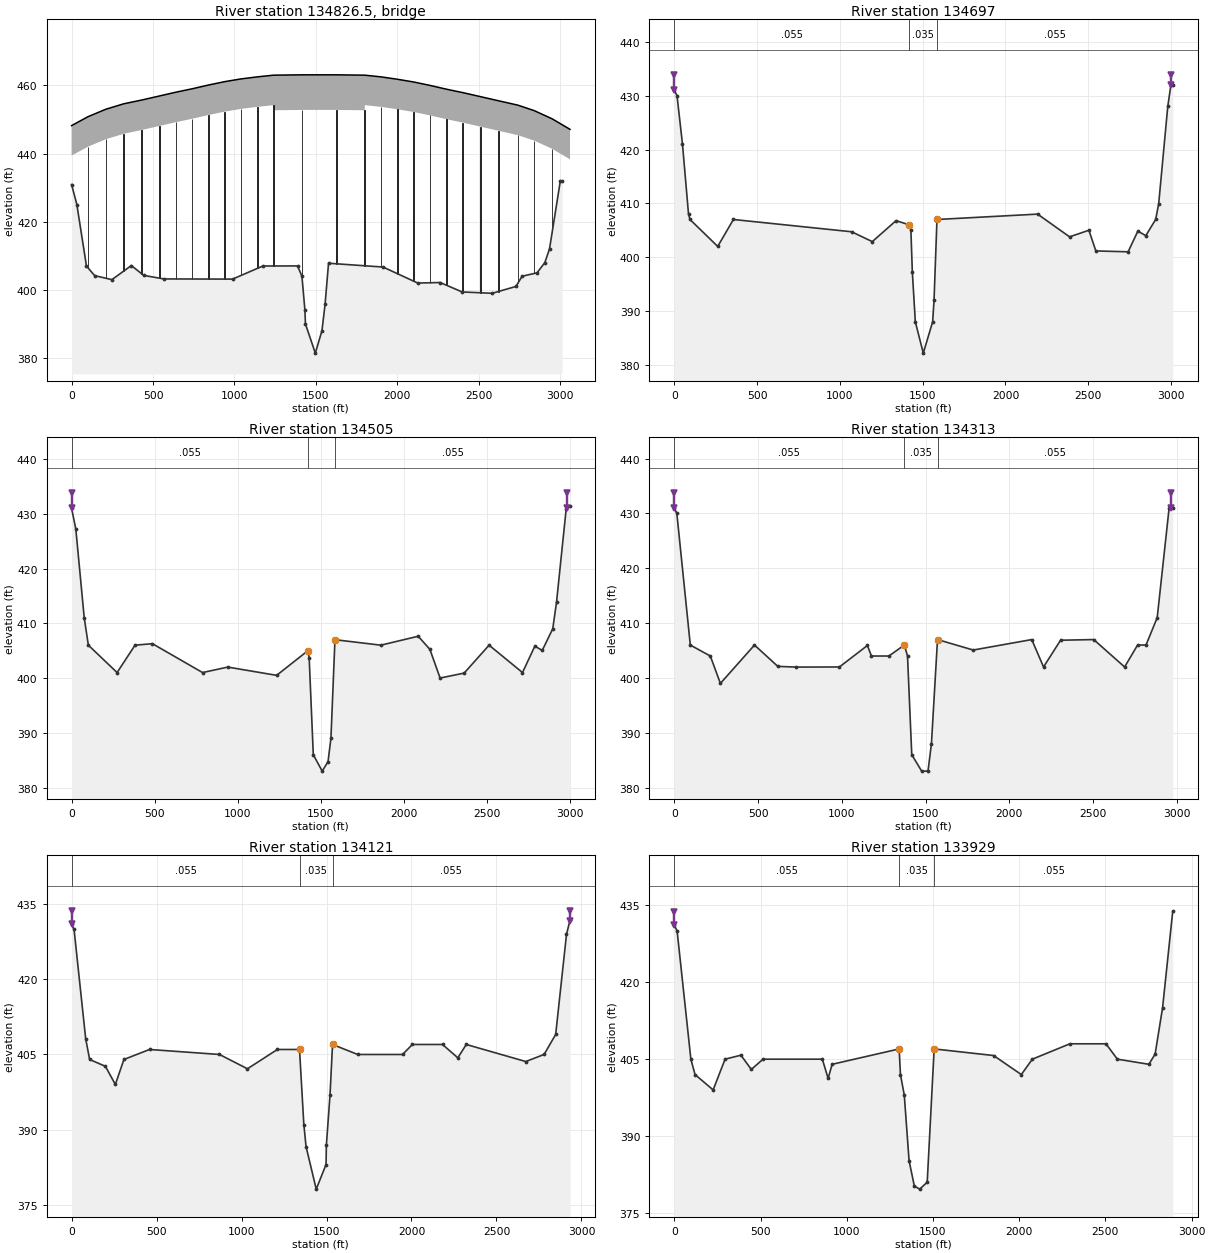
Type RM Length L Ch R = 3 ,134826.5,,,
BEGIN DESCRIPTION:
Hampton/Inwood Road
------------------------------------------------------------------
CDC DAL122205-01 Hampton/Inwood Bridge
------------------------------------------------------------------
END DESCRIPTION:
Node Name=Hampton Road
Bridge Culvert--1,0,-1,-1, 0
Deck Dist Width WeirC Skew NumUp NumDn MinLoCord MaxHiCord MaxSubmerge Is_Ogee
1,112,2.6,0, 30, 30, , , 0.95, 0, ,,,
       0     100     210     320     430     540     640     740     840     940
    1040    1140    1240    1240    1415    1625    1800    1800    1900    2000
    2100    2200    2300    2400    2510    2620    2740    2840    2950    3060
   448.2   450.8     453   454.6   455.7   456.9     458     459   460.1   461.1
   461.9   462.5     463     463   463.1   463.1     463     463   462.5   461.8
     461     460   458.9   457.9   456.7   455.5   454.2   452.6   450.2   447.1
   439.4     442   444.2   445.8   446.9   448.1   449.2   450.2   451.3   452.3
   453.1   453.7   454.2   452.7   452.8   452.8   452.7   454.2   453.7     453
   452.2   451.2   450.1   449.1   447.9   446.7   445.4   443.8   441.4   438.3
       0     100     210     320     430     540     640     740     840     940
    1040    1140    1240    1240    1415    1625    1800    1800    1900    2000
    2100    2200    2300    2400    2510    2620    2740    2840    2950    3060
   448.2   450.8     453   454.6   455.7   456.9     458     459   460.1   461.1
   461.9   462.5     463     463   463.1   463.1     463     463   462.5   461.8
     461     460   458.9   457.9   456.7   455.5   454.2   452.6   450.2   447.1
   439.4     442   444.2   445.8   446.9   448.1   449.2   450.2   451.3   452.3
   453.1   453.7   454.2   452.7   452.8   452.8   452.7   454.2   453.7     453
   452.2   451.2   450.1   449.1   447.9   446.7   445.4   443.8   441.4   438.3
Pier Skew, UpSta & Num, DnSta & Num=  ,100, 2 ,100, 2 , 0 , 0 , 0 ,,
       3       3
       0     445
       3       3
       0     445
Pier Skew, UpSta & Num, DnSta & Num=  ,210, 4 ,210, 4 , 0 , 0 , 0 ,,
     3.5     3.5       3       3
       0   431.3   431.5     445
     3.5     3.5       3       3
       0   431.3   431.5     445
Pier Skew, UpSta & Num, DnSta & Num=  ,320, 4 ,320, 4 , 0 , 0 , 0 ,,
     3.5     3.5       3       3
       0   432.7   432.7     450
     3.5     3.5       3       3
       0   432.7   432.7     450
Pier Skew, UpSta & Num, DnSta & Num=  ,430, 4 ,430, 4 , 0 , 0 , 0 ,,
     3.5     3.5       3       3
       0   433.9   433.9     450
     3.5     3.5       3       3
       0   433.9   433.9     450
Pier Skew, UpSta & Num, DnSta & Num=  ,540, 4 ,540, 4 , 0 , 0 , 0 ,,
       4       4       3       3
       0   435.1   435.1     450
       4       4       3       3
       0   435.1   435.1     450
Pier Skew, UpSta & Num, DnSta & Num=  ,640, 4 ,640, 4 , 0 , 0 , 0 ,,
       4       4       3       3
       0   436.1   436.1     450
       4       4       3       3
       0   436.1   436.1     450
Pier Skew, UpSta & Num, DnSta & Num=  ,740, 4 ,740, 4 , 0 , 0 , 0 ,,
       4       4       3       3
       0   437.2   437.2     452
       4       4       3       3
       0   437.2   437.2     452
Pier Skew, UpSta & Num, DnSta & Num=  ,840, 4 ,840, 4 , 0 , 0 , 0 ,,
       4       4       3       3
       0   438.3   438.3     452
       4       4       3       3
       0   438.3   438.3     452
Pier Skew, UpSta & Num, DnSta & Num=  ,940, 4 ,940, 4 , 0 , 0 , 0 ,,
       4       4       3       3
       0   439.2   439.2     455
       4       4       3       3
       0   439.2   439.2     455
Pier Skew, UpSta & Num, DnSta & Num=  ,1040, 4 ,1040, 4 , 0 , 0 , 0 ,,
       4       4       3       3
       0     440     440     455
       4       4       3       3
       0     440     440     455
Pier Skew, UpSta & Num, DnSta & Num=  ,1140, 4 ,1140, 4 , 0 , 0 , 0 ,,
       4       4       3       3
       0   440.7   440.7     455
       4       4       3       3
       0   440.7   440.7     455
Pier Skew, UpSta & Num, DnSta & Num=  ,1240, 2 ,1240, 2 , 0 , 0 , 0 ,,
       4       4
       0     455
       4       4
       0     455
Pier Skew, UpSta & Num, DnSta & Num=  ,1415, 2 ,1415, 2 , 0 , 0 , 0 ,,
       4       4
       0     455
       4       4
       0     455
Pier Skew, UpSta & Num, DnSta & Num=  ,1625, 2 ,1625, 2 , 0 , 0 , 0 ,,
       4       4
       0     455
       4       4
       0     455
Pier Skew, UpSta & Num, DnSta & Num=  ,1800, 2 ,1800, 2 , 0 , 0 , 0 ,,
       4       4
       0     455
       4       4
       0     455
Pier Skew, UpSta & Num, DnSta & Num=  ,1900, 4 ,1900, 4 , 0 , 0 , 0 ,,
       4       4       3       3
       0   440.6   440.6     455
       4       4       3       3
       0   440.6   440.6     455
Pier Skew, UpSta & Num, DnSta & Num=  ,2000, 4 ,2000, 4 , 0 , 0 , 0 ,,
       4       4       3       3
       0   439.9   439.9     455
       4       4       3       3
       0   439.9   439.9     455
Pier Skew, UpSta & Num, DnSta & Num=  ,2100, 4 ,2100, 4 , 0 , 0 , 0 ,,
       4       4       3       3
       0   439.1   439.1     455
       4       4       3       3
       0   439.1   439.1     455
Pier Skew, UpSta & Num, DnSta & Num=  ,2200, 4 ,2200, 4 , 0 , 0 , 0 ,,
       4       4       3       3
       0   438.1   438.1     455
       4       4       3       3
       0   438.1   438.1     455
Pier Skew, UpSta & Num, DnSta & Num=  ,2300, 4 ,2300, 4 , 0 , 0 , 0 ,,
     3.5     3.5       3       3
       0   437.1   437.1     455
     3.5     3.5       3       3
       0   437.1   437.1     455
Pier Skew, UpSta & Num, DnSta & Num=  ,2400, 4 ,2400, 4 , 0 , 0 , 0 ,,
     3.5     3.5       3       3
       0     436     436     455
     3.5     3.5       3       3
       0     436     436     455
Pier Skew, UpSta & Num, DnSta & Num=  ,2510, 4 ,2510, 4 , 0 , 0 , 0 ,,
     3.5     3.5       3       3
       0   434.8   434.8     455
     3.5     3.5       3       3
       0   434.8   434.8     455
Pier Skew, UpSta & Num, DnSta & Num=  ,2620, 4 ,2620, 4 , 0 , 0 , 0 ,,
     3.5     3.5       3       3
       0   433.7   433.7     455
     3.5     3.5       3       3
       0   433.7   433.7     455
Pier Skew, UpSta & Num, DnSta & Num=  ,2740, 4 ,2740, 4 , 0 , 0 , 0 ,,
     3.5     3.5       3       3
       0   432.3   432.3     453
     3.5     3.5       3       3
       0   432.3   432.3     453
Pier Skew, UpSta & Num, DnSta & Num=  ,2840, 4 ,2840, 4 , 0 , 0 , 0 ,,
     3.5     3.5       3       3
       0   430.8   430.8     450
     3.5     3.5       3       3
       0   430.8   430.8     450
Pier Skew, UpSta & Num, DnSta & Num=  ,2950, 2 ,2950, 2 , 0 , 0 , 0 ,,
       3       3
       0     445
       3       3
       0     445
BR Coef= 1 , 0 , 0 ,1.05, 0 ,,,0.8,-1,0.5,1,
WSPro=,,,, 1 ,,,, 0 ,,,, 0 ,,,,-1 ,-1 ,-1 , 0 , 0 , 0 , 0 , 0
BC Design=,, 0 ,, 0 ,,,,,,
BC HTab HWMax=435
BC Use User HTab Curves=0
BC User HTab FreeFlow(D)= 0

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
Type RM Length L Ch R = 1 ,134697  ,203,195,191
BEGIN DESCRIPTION:
This cross section corresponds to cross section 134697 of the non-georeferenced CDC model which was the source of this model.
END DESCRIPTION:
XS GIS Cut Line= 2
2474448.759796176978689.546641722473799.544559186975749.98460747
#Sta/Elev= 30
       0     431   16.09     430    49.1     421   85.47  408.04   94.45     407
  261.89     402  356.76     407 1070.82  404.72  1195.5  402.89 1339.01  406.78
 1419.76     406 1428.71     405 1437.33  397.29 1455.41     388 1503.55  382.18
 1560.12     388 1568.43     392 1586.18     407 2193.96     408 2387.01  403.78
 2503.73     405 2545.87  401.16 2740.72     401 2799.47  404.84 2847.49     404
 2906.99     407 2925.34  409.93 2980.18     428 2999.18     432  3010.4     432
#Mann= 3 ,0,0
       0    .055       0 1419.76    .035       0 1586.18    .055       0
Levee=-1,0,433.87,-1,3000,433.87,,
#XS Ineff= 2 , 0
         1419.76     406 1586.18             407
Permanent Ineff=
       F       F
Bank Sta=1419.76,1586.18
XS Rating Curve= 0 ,0
Exp/Cntr=0.3,0.1

Type RM Length L Ch R = 1 ,134505  ,202,194,190
BEGIN DESCRIPTION:
This cross section corresponds to cross section 134505 of the non-georeferenced CDC model which was the source of this model.
END DESCRIPTION:
XS GIS Cut Line= 2
2474659.771185166978675.920684712473979.363753356975754.71458489
#Sta/Elev= 30
       0     431   25.53  427.19   76.05     411  100.91     406  273.83     401
  381.79     406  486.56  406.27  788.21     401  939.95     402 1234.05  400.49
 1422.29     405 1429.64  403.72 1454.54     386 1508.04     383 1543.28  384.74
 1560.68     389 1584.96     407 1860.95     406 2085.77  407.63 2155.89  405.25
 2217.63     400 2362.37   400.9 2512.44     406 2713.43     401 2787.92  405.83
 2832.18  405.04 2895.61     409 2918.08  413.81 2976.61  430.95  2999.4  431.33
#Mann= 3 ,0,0
       0    .055       0 1422.29    .035       0 1584.96    .055       0
Levee=-1,0,433.82,-1,2983,433.82,,
#XS Ineff= 2 , 0
         1422.29     405 1584.96             407
Permanent Ineff=
       F       F
Bank Sta=1422.29,1584.96
XS Rating Curve= 0 ,0
Exp/Cntr=0.3,0.1

Type RM Length L Ch R = 1 ,134313  ,202,194,190
BEGIN DESCRIPTION:
This cross section corresponds to cross section 134313 of the non-georeferenced CDC model which was the source of this model.
END DESCRIPTION:
XS GIS Cut Line= 2
2474863.244531516978645.260312962474156.997256346975755.07908547
#Sta/Elev= 30
       0     431   14.93     430   95.23     406  214.75     404   274.8     399
  478.32     406  617.61  402.11  726.36  401.98  985.31     402 1152.34  405.92
 1176.61     404 1280.45     404 1372.87     406 1391.81     404 1417.15     386
 1476.34     383 1514.17     383 1534.64     388 1570.83     407 1784.32  405.09
 2133.47     407 2203.73     402 2305.35  406.88 2503.24     407 2687.74     402
 2765.07     406 2815.38     406 2882.27     411 2953.27  430.96 2975.22  430.94
#Mann= 3 ,0,0
       0    .055       0 1372.87    .035       0 1570.83    .055       0
Levee=-1,0,433.77,-1,2963,433.77,,
#XS Ineff= 2 , 0
         1372.87     406 1570.83             407
Permanent Ineff=
       F       F
Bank Sta=1372.87,1570.83
XS Rating Curve= 0 ,0
Exp/Cntr=0.3,0.1

Type RM Length L Ch R = 1 ,134121  ,197,189,185
BEGIN DESCRIPTION:
This cross section corresponds to cross section 134121 of the non-georeferenced CDC model which was the source of this model.
END DESCRIPTION:
XS GIS Cut Line= 2
2475064.134549686978593.086860882474334.185222186975752.63027146
#Sta/Elev= 30
       0     431   14.59     430   82.97  408.15  106.14     404  198.96  402.63
  257.57     399  307.91     404  458.65     406  870.16     405 1034.78  402.14
 1210.97     406 1341.12     406 1366.53     391 1379.64  386.57 1439.54  378.08
 1497.21     383 1499.23  386.92 1520.61  396.89 1535.39     407 1683.56     405
 1947.45     405 2005.12     407 2182.51     407 2272.66  404.33 2322.34     407
 2672.44  403.59 2780.12     405 2848.38     409 2912.03  428.99 2932.75  431.88
#Mann= 3 ,0,0
       0    .055       0 1341.12    .035       0 1535.39    .055       0
Levee=-1,0,433.72,-1,2931,433.72,,
#XS Ineff= 2 , 0
         1341.12     406 1535.08           406.7
Permanent Ineff=
       F       F
Bank Sta=1341.12,1535.39
XS Rating Curve= 0 ,0
Exp/Cntr=0.3,0.1

Type RM Length L Ch R = 1 ,133929  ,197,188,185
BEGIN DESCRIPTION:
This cross section corresponds to cross section 133929 of the non-georeferenced CDC model which was the source of this model.
END DESCRIPTION:
XS GIS Cut Line= 2
 2475258.36972556978526.674592142474507.580872746975735.27991247
#Sta/Elev= 30
       0  431.17   16.13     430   95.81     405  119.93     402  224.99     399
   294.1     405  386.05  405.78   446.2     403  514.56     405  858.27     405
  891.77  401.24  915.09     404 1303.69     407 1311.24     402  1333.4     398
 1361.28  385.19 1391.79  380.24 1423.37  379.64 1466.47     381 1506.74     407
 1851.42  405.71 2012.18     402 2076.26     405  2293.9     408 2503.22     408
 2569.28     405  2752.2     404 2788.23     406 2831.32     415  2890.6  433.95
#Mann= 3 ,0,0
       0    .055       0 1303.69    .035       0 1506.74    .055       0
Levee=-1,0,433.67,-1,2891,433.67,,
#XS Ineff= 2 , 0
         1303.69     407 1506.74             407
Permanent Ineff=
       F       F
Bank Sta=1303.69,1506.74
XS Rating Curve= 0 ,0
Exp/Cntr=0.3,0.1

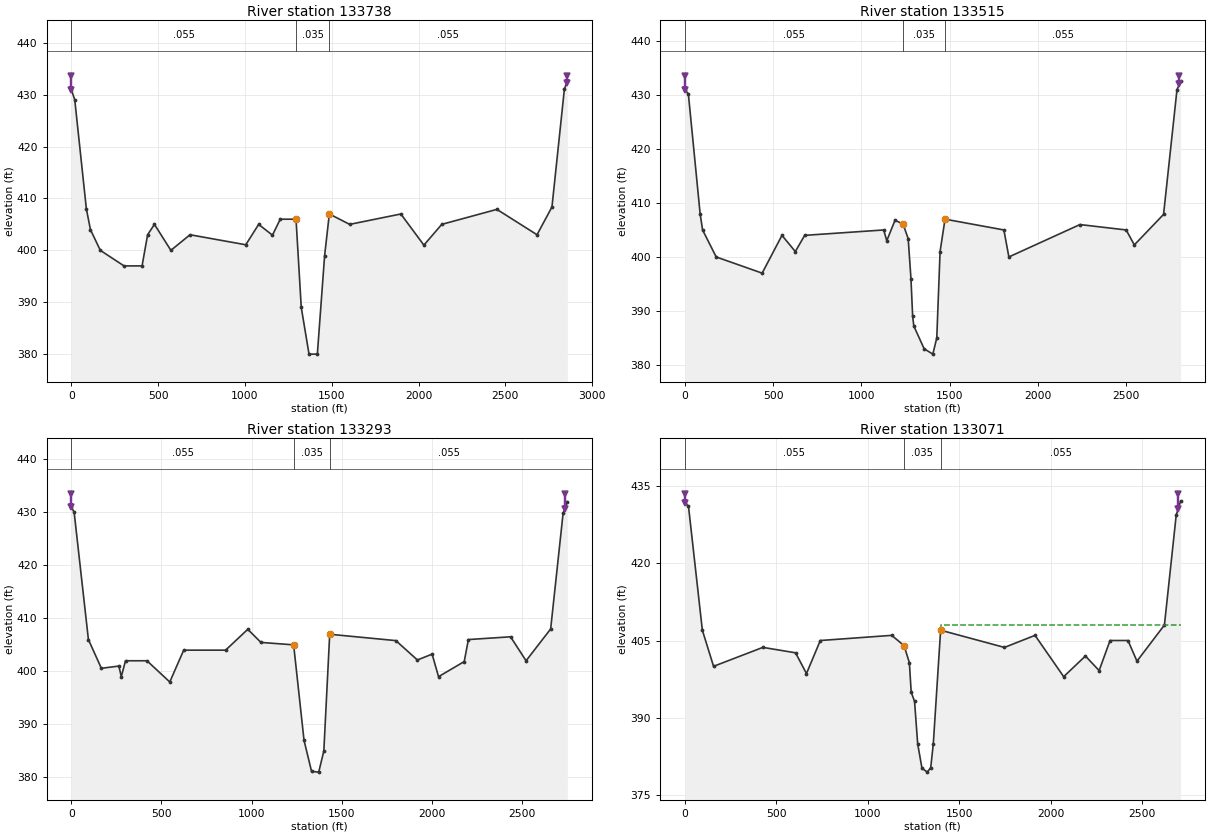
Type RM Length L Ch R = 1 ,133738  ,253,223,210
BEGIN DESCRIPTION:
This cross section corresponds to cross section 133738 of the non-georeferenced CDC model which was the source of this model.
END DESCRIPTION:
XS GIS Cut Line= 2
2475448.824725186978447.136365382474673.314465176975696.73832288
#Sta/Elev= 30
       0   430.9   19.01     429   85.87     408   109.3     404  166.14     400
  302.84     397   406.9     397  438.82     403  478.23     405  572.88     400
  683.41     403  1004.6  401.07 1078.76     405 1158.29  402.92 1203.25     406
 1294.13     406 1324.32     389 1369.03     380 1417.07     380 1458.97     399
 1486.09     407 1603.51     405 1898.25     407 2030.99     401 2134.02     405
 2451.68  407.89 2683.06     403 2769.06  408.35 2840.52     431 2857.64  432.65
#Mann= 3 ,0,0
       0    .055       0 1294.13    .035       0 1486.09    .055       0
Levee=-1,0,433.62,-1,2853,433.62,,
#XS Ineff= 2 , 0
         1294.13     406 1486.09             407
Permanent Ineff=
       F       F
Bank Sta=1294.13,1486.09
XS Rating Curve= 0 ,0
Exp/Cntr=0.3,0.1

Type RM Length L Ch R = 1 ,133515  ,252,220,208
BEGIN DESCRIPTION:
This cross section corresponds to cross section 133515 of the non-georeferenced CDC model which was the source of this model.
END DESCRIPTION:
XS GIS Cut Line= 2
2475702.735306596978331.928590552474835.012304516975661.44771105
#Sta/Elev= 30
       0     431   20.41  430.21   87.04     408  100.99     405  178.05     400
  438.21     397  550.54     404  626.11     401  679.13     404 1126.72     405
  1143.9     403  1190.6  406.79 1236.21   406.1 1265.28  403.38  1280.9     396
 1290.47     389 1297.03  387.21 1355.41     383 1404.74     382 1427.12     385
 1445.82     401 1473.88     407  1807.1     405 1835.34     400 2237.87     406
 2499.47     405 2545.81  402.23 2711.32  407.88 2787.35     431 2807.92   432.5
#Mann= 3 ,0,0
       0    .055       0 1236.21    .035       0 1473.88    .055       0
Levee=-1,0,433.55,-1,2801,433.55,,
#XS Ineff= 2 , 0
         1236.21   406.1 1473.88             407
Permanent Ineff=
       F       F
Bank Sta=1236.21,1473.88
XS Rating Curve= 0 ,0
Exp/Cntr=0.3,0.1

Type RM Length L Ch R = 1 ,133293  ,254,222,210
BEGIN DESCRIPTION:
This cross section corresponds to cross section 133293 of the non-georeferenced CDC model which was the source of this model.
END DESCRIPTION:
XS GIS Cut Line= 2
2475947.578977026978203.26611821 2474994.0418421 6975619.4172833
#Sta/Elev= 30
       0     431   14.95     430   94.17     406   166.1  400.58  263.35     401
  276.83     399  300.19     402  419.35     402  546.06     398  623.36     404
  855.98     404  979.33  407.93 1052.35  405.46 1234.05     405 1291.76     387
 1333.44  381.15 1373.41     381 1401.77     385 1434.36     407 1801.69   405.8
 1921.47  402.15 2003.12  403.25 2038.85     399 2181.55  401.85 2204.68     406
 2438.97  406.52 2525.01     402 2661.58     408 2730.65   429.8 2754.18     432
#Mann= 3 ,0,0
       0    .055       0 1234.05    .035       0 1434.36    .055       0
Levee=-1,0,433.48,-1,2740,433.48,,
#XS Ineff= 2 , 0
         1234.05     405 1434.36             407
Permanent Ineff=
       F       F
Bank Sta=1234.05,1434.36
XS Rating Curve= 0 ,0
Exp/Cntr=0.3,0.1

Type RM Length L Ch R = 1 ,133071  ,255,223,211
BEGIN DESCRIPTION:
This cross section corresponds to cross section 133071 of the non-georeferenced CDC model which was the source of this model.
END DESCRIPTION:
XS GIS Cut Line= 2
 2476190.44266456978064.769019892475148.14783308 6975563.5610958
#Sta/Elev= 30
       0   431.7   20.41     431   96.12     407  157.44     400  426.82  403.67
  605.48  402.62  665.18   398.6  740.68     405  1131.1     406 1198.46     404
 1227.38  400.71 1237.41     395 1255.78   393.2 1272.81     385  1296.2  380.27
 1325.28  379.51 1344.12  380.39 1358.23     385  1398.2     407 1747.01  403.66
 1914.01     406 2070.65     398 2189.51     402 2264.36  399.18 2324.05     405
 2422.13     405  2471.1     401 2621.18     408 2685.56  429.28 2709.69     432
#Mann= 3 ,0,0
       0    .055       0 1198.46    .035       0  1398.2    .055       0
Levee=-1,0,433.41,-1,2696,433.41,,
#XS Ineff= 2 , 0
         1198.46     404 1400.52             408
Permanent Ineff=
       F       F
Bank Sta=1198.46,1398.2
XS Rating Curve= 0 ,0
Exp/Cntr=0.3,0.1