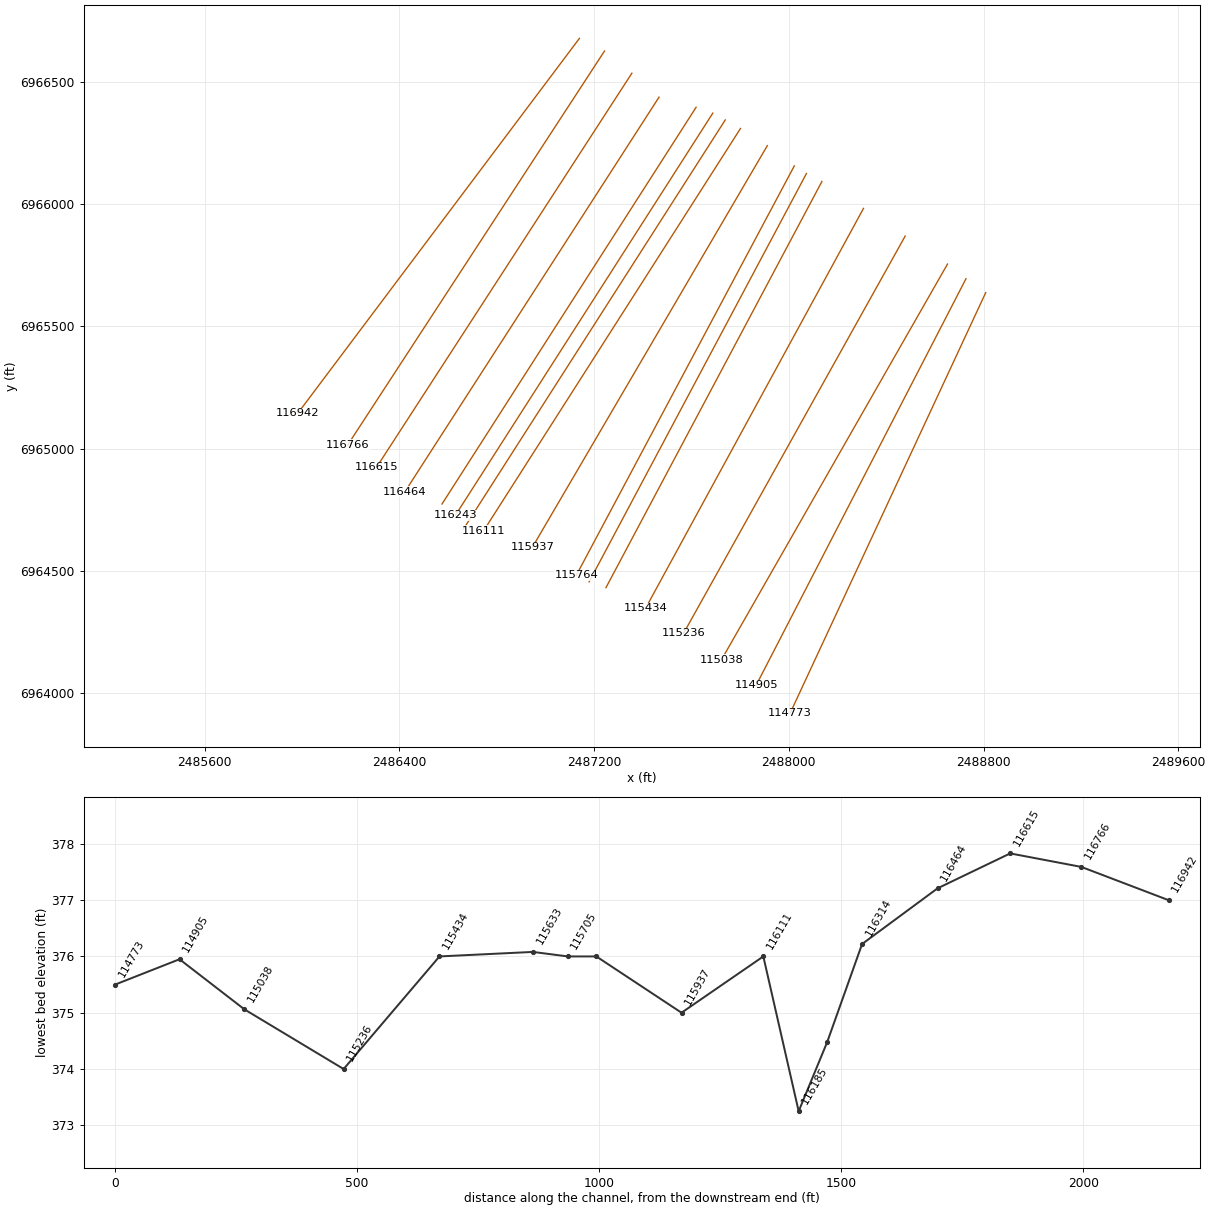
HEC-RAS study CDC_Consolidated_Model.prj: Upper Trinity CDC Consolidated Model

--- CDC_Consolidated_Model.g13 (geometry) --- (continued)

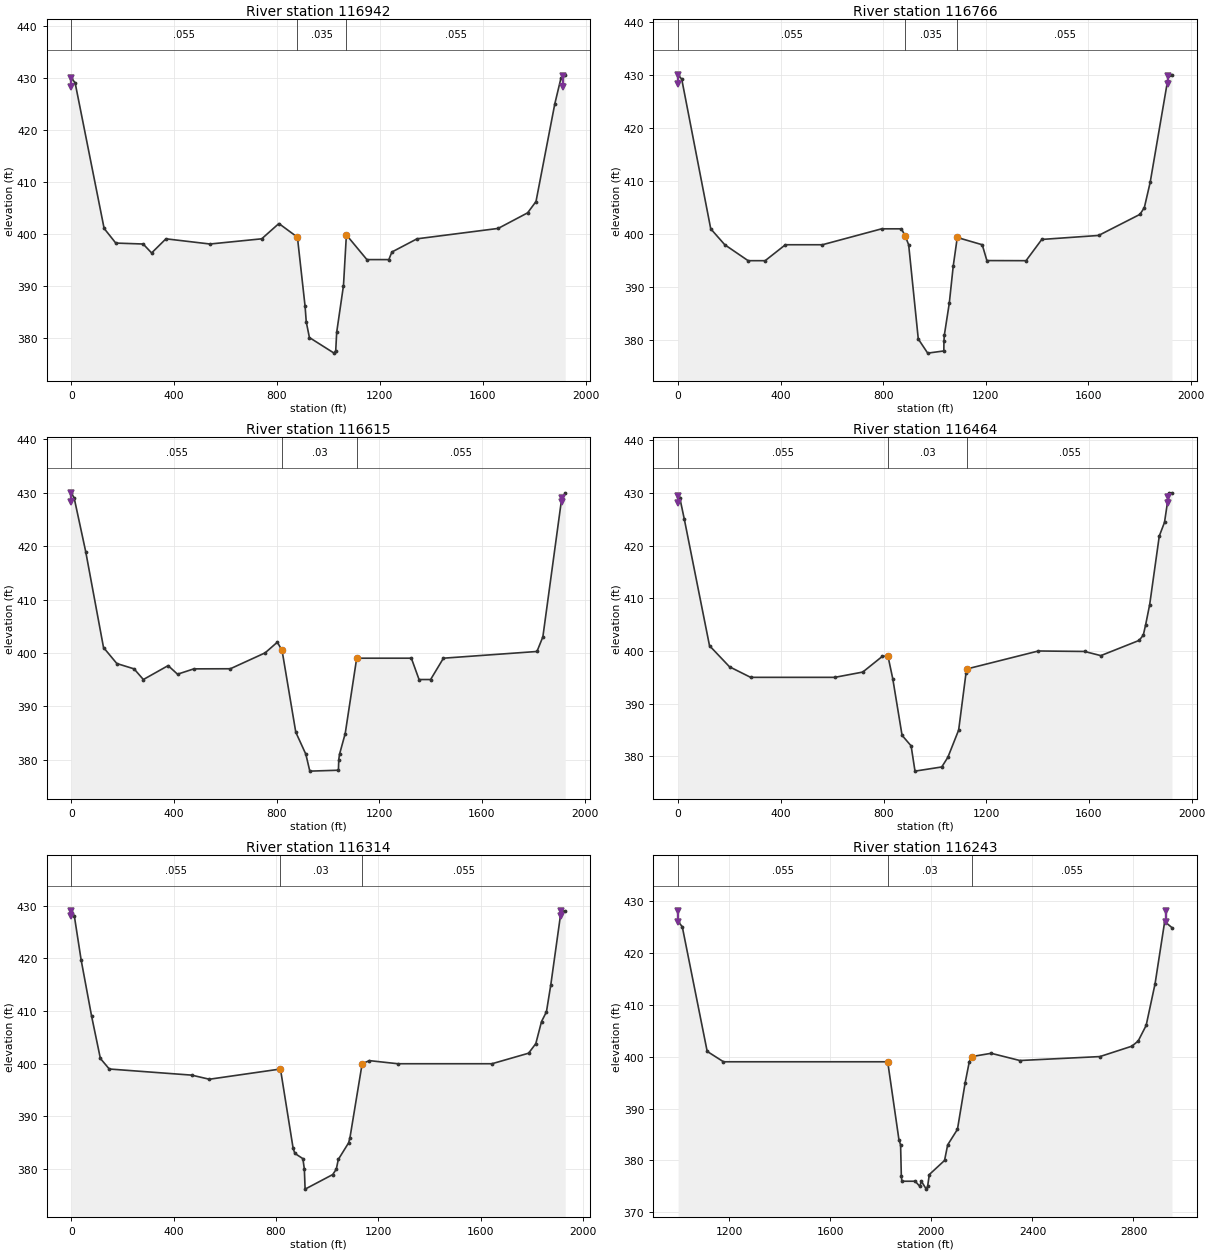
Type RM Length L Ch R = 1 ,116942  ,152,180,218
BEGIN DESCRIPTION:
This cross section corresponds to cross section 116942 of the non-georeferenced CDC model which was the source of this model.
END DESCRIPTION:
XS GIS Cut Line= 2
2487139.975883516966678.745204052485983.411595586965145.08915064
#Sta/Elev= 30
       0     430   14.73     429  127.45     401  172.76  398.18  279.26     398
  312.16  396.28   367.9     399  539.24     398  740.38     399  807.25  401.94
  876.71  399.41  879.98     399  909.13     386  913.66     383  925.93     380
 1021.78     377 1028.32  377.49 1031.99     381 1058.43     390 1069.75  399.75
 1149.51     395 1234.88     395 1246.73  396.46 1344.52     399 1660.03     401
  1774.7     404 1807.27  406.18 1880.51     425  1904.7     430 1920.87  430.56
#Mann= 3 ,0,0
       0    .055       0  876.71    .035       0 1069.75    .055       0
Levee=-1,0,428.28,-1,1912,428.28,,
#XS Ineff= 2 , 0
          876.71  399.41 1069.75          399.75
Permanent Ineff=
       F       F
Bank Sta=876.71,1069.75
XS Rating Curve= 0 ,0
Exp/Cntr=0.3,0.1

Type RM Length L Ch R = 1 ,116766  ,142,147,146
BEGIN DESCRIPTION:
This cross section corresponds to cross section 116766 of the non-georeferenced CDC model which was the source of this model.
END DESCRIPTION:
XS GIS Cut Line= 2
2487242.895625176966626.792880132486187.660530926965014.40076372
#Sta/Elev= 30
       0     430    14.1  429.18  127.27     401  182.05     398  273.18     395
  339.66     395  418.54     398  562.95     398  794.19     401  871.27     401
  885.84  399.68  899.52     398   937.1  380.25  973.81  377.59 1036.81     378
 1037.15  379.83 1038.84     381  1058.1     387  1073.5     394 1089.25  399.37
 1186.65     398 1204.78  395.02 1357.58     395    1419     399 1640.63  399.75
 1801.98  403.72 1819.21     405 1842.06  409.78 1913.63  429.94    1927     430
#Mann= 3 ,0,0
       0    .055       0  885.84    .035       0 1089.25    .055       0
Levee=-1,0,428.24,-1,1913,428.24,,
#XS Ineff= 2 , 0
          885.84  399.68 1089.25          399.37
Permanent Ineff=
       F       F
Bank Sta=885.84,1089.25
XS Rating Curve= 0 ,0
Exp/Cntr=0.3,0.1

Type RM Length L Ch R = 1 ,116615  ,146,150,149
BEGIN DESCRIPTION:
This cross section corresponds to cross section 116615 of the non-georeferenced CDC model which was the source of this model.
END DESCRIPTION:
XS GIS Cut Line= 2
2487355.378996016966536.099163892486305.956554176964922.83992322
#Sta/Elev= 30
       0     430    11.1     429   55.84     419  125.34     401  177.21     398
  244.38     397  280.63     395  377.13  397.61  413.76     396  477.46     397
  619.61  397.02  755.11     400  802.66     402  821.14  400.45  874.59  385.13
   913.8     381  929.28  377.83 1040.73     378 1042.14     380  1045.1     381
 1067.22  384.88 1111.96     399    1325     399    1355     395    1400     395
    1450     399 1814.48  400.26 1837.48     403 1911.03     429 1924.55  429.92
#Mann= 3 ,0,0
       0    .055       0  821.14     .03       0 1111.96    .055       0
Levee=-1,0,428.19,-1,1911,428.19,,
#XS Ineff= 2 , 0
          821.14  400.45 1111.96             399
Permanent Ineff=
       F       F
Bank Sta=821.14,1111.96
XS Rating Curve= 0 ,0
Exp/Cntr=0.3,0.1

Type RM Length L Ch R = 1 ,116464  ,152,156,156
BEGIN DESCRIPTION:
This cross section corresponds to cross section 116464 of the non-georeferenced CDC model which was the source of this model.
END DESCRIPTION:
XS GIS Cut Line= 2
2487466.889927836966437.993717042486422.710913846964823.03828555
#Sta/Elev= 30
       0  429.42    6.74     429    24.1     425  122.24     401  200.18     397
  282.39     395  610.15     395  718.93     396  795.78     399  817.23     399
  835.79  394.75  872.06     384   907.3     382  922.39  377.21 1026.64     378
 1050.36  379.83  1092.4     385    1121  395.79  1126.8  396.62 1403.02     400
 1582.61  399.91 1646.05  399.12 1794.88     402 1811.44     403 1820.67     405
 1836.34  408.81 1873.67   421.8 1894.03   424.4 1911.22     430 1923.12     430
#Mann= 3 ,0,0
       0    .055       0  817.23     .03       0  1126.8    .055       0
Levee=-1,0,428.14,-1,1909,428.14,,
#XS Ineff= 2 , 0
          817.23     399  1126.8          396.62
Permanent Ineff=
       F       F
Bank Sta=817.23,1126.8
XS Rating Curve= 0 ,0
Exp/Cntr=0.3,0.1

Type RM Length L Ch R = 1 ,116314  ,72,72,72
BEGIN DESCRIPTION:
This cross section corresponds to cross section 116314 of the non-georeferenced CDC model which was the source of this model.
END DESCRIPTION:
XS GIS Cut Line= 2
 2487619.2626546 6966396.62667382486575.310674256964773.14829347
#Sta/Elev= 30
       0     429   11.73     428   38.17   419.7   79.21     409  113.43     401
  148.24     399   470.3  397.84  539.25  397.06  817.23     399  866.63     384
  873.46     383  904.87     382  910.66     380  913.57  376.22 1021.39  378.98
 1035.46     380 1043.24  381.84 1083.61     385 1088.97     386 1136.48     400
 1164.77  400.59 1276.08     400 1643.88     400 1787.08     402 1815.27  403.82
 1837.58     408 1856.76  409.84 1873.77  414.95 1914.15     429 1930.16     429
#Mann= 3 ,0,0
       0    .055       0  817.23     .03       0 1136.48    .055       0
Levee=-1,0,428.08,-1,1914,428.08,,
#XS Ineff= 2 , 0
          817.23     399 1136.48             400
Permanent Ineff=
       F       F
Bank Sta=817.23,1136.48
XS Rating Curve= 0 ,0
Exp/Cntr=0.3,0.1

Type RM Length L Ch R = 1 ,116243  ,59,59,59
BEGIN DESCRIPTION:
This cross section corresponds to cross section 116243 of the non-georeferenced CDC model which was the source of this model.
END DESCRIPTION:
XS GIS Cut Line= 2
2487687.88226801 6966372.72711532486630.955904196964727.81078571
#Sta/Elev= 30
   997.2     426 1013.62     425 1112.25     401 1176.73     399 1826.91     399
 1871.43     384 1877.95     383  1880.9     377 1883.04     376 1935.75     376
 1953.88  375.02 1960.31     376 1979.46  374.48 1984.92     375 1991.73  377.29
 2051.96     380 2064.37     383 2103.08  385.99 2133.59  394.96 2149.96     399
 2159.77     400 2236.67  400.63 2350.13  399.24 2667.07     400 2793.68     402
 2818.63     403 2850.17     406  2885.4     414 2923.56     426 2952.41  424.82
#Mann= 3 ,0,0
   997.2    .055       0 1826.91     .03       0 2159.77    .055       0
Levee=-1,997.2,428.06,-1,2927,428.06,,
#XS Ineff= 2 , 0
         1826.91     399 2159.77             400
Permanent Ineff=
       F       F
Bank Sta=1826.91,2159.77
XS Rating Curve= 0 ,0
Exp/Cntr=0.3,0.1

Type RM Length L Ch R = 3 ,116214  ,,,
BEGIN DESCRIPTION:
Houston Street
END DESCRIPTION:
Node Name=Houston Street
Bridge Culvert--1,0,-1,-1, 0
Deck Dist Width WeirC Skew NumUp NumDn MinLoCord MaxHiCord MaxSubmerge Is_Ogee
1.5,56,2.6,0, 480, 480, , , 0.95, 0, ,,,
   997.2  1005.2  1013.2  1013.2  1024.7  1024.7  1027.7  1027.7  1034.1  1034.1
  1036.6  1036.6  1053.4  1053.4  1055.9  1055.9  1062.3  1062.3  1065.3  1065.3
  1076.8  1076.8  1084.8  1092.7  1092.7  1104.2  1104.2  1107.2  1107.2  1113.6
  1113.6  1116.1  1116.1  1132.9  1132.9  1135.4  1135.4  1141.8  1141.8  1144.8
  1144.8  1156.3  1156.3  1164.3  1172.2  1172.2  1183.7  1183.7  1186.7  1186.7
  1193.1  1193.1  1195.6  1195.6  1212.4  1212.4  1214.9  1214.9  1221.3  1221.3
  1224.3  1224.3  1235.8  1235.8  1243.8  1251.7  1251.7  1263.2  1263.2  1266.2
  1266.2  1272.6  1272.6  1275.1  1275.1  1291.9  1291.9  1294.4  1294.4  1300.8
  1300.8  1303.8  1303.8  1315.3  1315.3  1323.3  1331.2  1331.2  1342.7  1342.7
  1345.7  1345.7  1352.1  1352.1  1354.6  1354.6  1371.4  1371.4  1373.9  1373.9
  1380.3  1380.3  1383.3  1383.3  1394.8  1394.8  1402.8  1410.7  1410.7  1422.2
  1422.2  1425.2  1425.2  1431.6  1431.6  1434.1  1434.1  1450.9  1450.9  1453.4
  1453.4  1459.8  1459.8  1462.8  1462.8  1474.3  1474.3  1482.3  1490.2  1490.2
  1501.7  1501.7  1504.7  1504.7  1511.1  1511.1  1513.6  1513.6  1530.4  1530.4
  1532.9  1532.9  1539.3  1539.3  1542.3  1542.3  1553.8  1553.8  1561.8  1569.7
  1569.7  1581.2  1581.2  1584.2  1584.2  1590.6  1590.6  1593.1  1593.1  1609.9
  1609.9  1612.4  1612.4  1618.8  1618.8  1621.8  1621.8  1633.3  1633.3  1641.3
  1649.2  1649.2  1660.7  1660.7  1663.7  1663.7  1670.1  1670.1  1672.6  1672.6
  1689.4  1689.4  1691.9  1691.9  1698.3  1698.3  1701.3  1701.3  1712.8  1712.8
  1720.8  1728.7  1728.7  1740.2  1740.2  1740.2  1743.2  1743.2  1749.6  1749.6
  1752.1  1752.1  1768.9  1768.9  1771.4  1771.4  1777.8  1777.8  1780.8  1780.8
  1792.3  1792.3  1800.3  1808.2  1808.2  1819.7  1819.7  1822.7  1822.7  1829.1
  1829.1  1831.6  1831.6  1848.4  1848.4  1850.9  1850.9  1857.3  1857.3  1860.3
  1860.3  1871.8  1871.8  1879.8  1887.7  1887.7  1899.2  1899.2  1902.2  1902.2
  1908.6  1908.6  1911.1  1911.1  1927.9  1927.9  1930.4  1930.4  1936.8  1936.8
  1939.8  1939.8  1951.3  1951.3  1959.3  1967.2  1967.2  1978.7  1978.7  1981.7
  1981.7  1988.1  1988.1  1990.6  1990.6  2007.4  2007.4  2009.9  2009.9  2016.3
  2016.3  2019.3  2019.3  2030.8  2030.8  2038.8  2046.7  2046.7  2058.2  2058.2
  2061.2  2061.2  2067.6  2067.6  2070.1  2070.1  2086.9  2086.9  2089.4  2089.4
  2095.8  2095.8  2098.8  2098.8  2110.3  2110.3  2118.3  2126.2  2126.2  2137.7
  2137.7  2140.7  2140.7  2147.1  2147.1  2149.6  2149.6  2166.4  2166.4  2168.9
  2168.9  2175.3  2175.3  2178.3  2178.3  2189.8  2189.8  2197.8  2205.7  2205.7
  2217.2  2217.2  2220.2  2220.2  2226.6  2226.6  2229.1  2229.1  2245.9  2245.9
  2248.4  2248.4  2254.8  2254.8  2257.8  2257.8  2269.3  2269.3  2277.3  2285.2
  2285.2  2296.7  2296.7  2299.7  2299.7  2306.1  2306.1  2308.6  2308.6  2325.4
  2325.4  2327.9  2327.9  2334.3  2334.3  2337.3  2337.3  2348.8  2348.8  2356.8
  2364.7  2364.7  2376.2  2376.2  2379.2  2379.2  2385.6  2385.6  2388.1  2388.1
  2404.9  2404.9  2407.4  2407.4  2413.8  2413.8  2416.8  2416.8  2428.3  2428.3
  2436.3  2444.2  2444.2  2455.7  2455.7  2458.7  2458.7  2465.1  2465.1  2467.6
  2467.6  2484.4  2484.4  2486.9  2486.9  2493.3  2493.3  2496.3  2496.3  2507.8
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Pier Skew, UpSta & Num, DnSta & Num=  ,1045, 5 ,1045, 5 , 0 , 0 , 0 ,,
       9       8       8       4       4
   392.1   416.1   425.4   425.4     438
       9       8       8       4       4
   392.1   416.1   425.4   425.4     438
Pier Skew, UpSta & Num, DnSta & Num=  ,1124.5, 5 ,1124.5, 5 , 0 , 0 , 0 ,,
       9       8       8       4       4
   391.5   415.5   424.8   424.8   437.5
       9       8       8       4       4
   391.5   415.5   424.8   424.8   437.5
Pier Skew, UpSta & Num, DnSta & Num=  ,1204, 5 ,1204, 5 , 0 , 0 , 0 ,,
       9       8       8       4       4
   390.8   414.8   424.1   424.1   436.8
       9       8       8       4       4
   390.8   414.8   424.1   424.1   436.8
Pier Skew, UpSta & Num, DnSta & Num=  ,1283.5, 5 ,1283.5, 5 , 0 , 0 , 0 ,,
      20       8       8       4       4
   390.2   414.2   423.5   423.5   436.2
      20       8       8       4       4
   390.2   414.2   423.5   423.5   436.2
Pier Skew, UpSta & Num, DnSta & Num=  ,1363, 5 ,1363, 5 , 0 , 0 , 0 ,,
       9       8       8       4       4
   389.6   413.6   422.9   422.9   435.6
       9       8       8       4       4
   389.6   413.6   422.9   422.9   435.6
Pier Skew, UpSta & Num, DnSta & Num=  ,1442.5, 5 ,1442.5, 5 , 0 , 0 , 0 ,,
       9       8       8       4       4
     389     413   422.3   422.3     435
       9       8       8       4       4
     389     413   422.3   422.3     435
Pier Skew, UpSta & Num, DnSta & Num=  ,1522, 5 ,1522, 5 , 0 , 0 , 0 ,,
       9       8       8       4       4
   388.4   412.4   421.7   421.7   434.4
       9       8       8       4       4
   388.4   412.4   421.7   421.7   434.4
Pier Skew, UpSta & Num, DnSta & Num=  ,1601.5, 5 ,1601.5, 5 , 0 , 0 , 0 ,,
       9       8       8       4       4
   387.2   411.8   421.1   421.1   433.8
       9       8       8       4       4
   387.2   411.8   421.1   421.1   433.8
Pier Skew, UpSta & Num, DnSta & Num=  ,1681, 5 ,1681, 5 , 0 , 0 , 0 ,,
      20       8       8       4       4
   387.2   411.2   420.5   420.5   433.2
      20       8       8       4       4
   387.2   411.2   420.5   420.5   433.2
Pier Skew, UpSta & Num, DnSta & Num=  ,1760.5, 5 ,1760.5, 5 , 0 , 0 , 0 ,,
       9       8       8       4       4
   386.6   410.6   419.9   419.9   432.6
       9       8       8       4       4
   386.6   410.6   419.9   419.9   432.6
Pier Skew, UpSta & Num, DnSta & Num=  ,1840, 5 ,1840, 5 , 0 , 0 , 0 ,,
       9       8       8       4       4
   386.1   410.1   419.4   419.4   432.1
       9       8       8       4       4
   386.1   410.1   419.4   419.4   432.1
Pier Skew, UpSta & Num, DnSta & Num=  ,1919.5, 8 ,1919.5, 8 , 0 , 0 , 0 ,,
      28      18      10      10       8       8       4       4
   373.9   388.9   388.9   409.5   409.5   418.8   418.8   431.5
      28      18      10      10       8       8       4       4
   373.9   388.9   388.9   409.5   409.5   418.8   418.8   431.5
Pier Skew, UpSta & Num, DnSta & Num=  ,1999, 8 ,1999, 8 , 0 , 0 , 0 ,,
      28      18      10      10       8       8       4       4
   373.5   388.5   388.5     409     409   418.3   418.3     431
      28      18      10      10       8       8       4       4
   373.5   388.5   388.5     409     409   418.3   418.3     431
Pier Skew, UpSta & Num, DnSta & Num=  ,2078.5, 7 ,2078.5, 7 , 0 , 0 , 0 ,,
    31.5    31.5      15       8       8       4       4
     370     395     395   408.5   417.8   417.8   430.5
    31.5    31.5      15       8       8       4       4
     370     395     395   408.5   417.8   417.8   430.5
Pier Skew, UpSta & Num, DnSta & Num=  ,2158, 5 ,2158, 5 , 0 , 0 , 0 ,,
       9       8       8       4       4
   383.9   407.9   417.2   417.2   429.9
       9       8       8       4       4
   383.9   407.9   417.2   417.2   429.9
Pier Skew, UpSta & Num, DnSta & Num=  ,2237.5, 5 ,2237.5, 5 , 0 , 0 , 0 ,,
       9       8       8       4       4
   383.4   407.4   416.7   416.7   429.4
       9       8       8       4       4
   383.4   407.4   416.7   416.7   429.4
Pier Skew, UpSta & Num, DnSta & Num=  ,2317, 5 ,2317, 5 , 0 , 0 , 0 ,,
       9       8       8       4       4
   382.9   406.9   416.2   416.2   428.9
       9       8       8       4       4
   382.9   406.9   416.2   416.2   428.9
Pier Skew, UpSta & Num, DnSta & Num=  ,2396.5, 5 ,2396.5, 5 , 0 , 0 , 0 ,,
       9       8       8       4       4
   382.3   406.3   415.6   415.6   428.3
       9       8       8       4       4
   382.3   406.3   415.6   415.6   428.3
Pier Skew, UpSta & Num, DnSta & Num=  ,2476, 5 ,2476, 5 , 0 , 0 , 0 ,,
      20       8       8       4       4
   381.6   405.6   414.9   414.9   427.6
      20       8       8       4       4
   381.6   405.6   414.9   414.9   427.6
Pier Skew, UpSta & Num, DnSta & Num=  ,2555.5, 5 ,2555.5, 5 , 0 , 0 , 0 ,,
       9       8       8       4       4
     381     405   414.3   414.3     427
       9       8       8       4       4
     381     405   414.3   414.3     427
Pier Skew, UpSta & Num, DnSta & Num=  ,2635, 5 ,2635, 5 , 0 , 0 , 0 ,,
       9       8       8       4       4
   380.5   404.5   413.8   413.8   426.5
       9       8       8       4       4
   380.5   404.5   413.8   413.8   426.5
Pier Skew, UpSta & Num, DnSta & Num=  ,2714.5, 5 ,2714.5, 5 , 0 , 0 , 0 ,,
       9       8       8       4       4
     380     404   413.3   413.3     426
       9       8       8       4       4
     380     404   413.3   413.3     426
Pier Skew, UpSta & Num, DnSta & Num=  ,2794, 5 ,2794, 5 , 0 , 0 , 0 ,,
       9       8       8       4       4
   379.5   403.5   412.8   412.8   425.5
       9       8       8       4       4
   379.5   403.5   412.8   412.8   425.5
Pier Skew, UpSta & Num, DnSta & Num=  ,2829, 2 ,2829, 2 , 0 , 0 , 0 ,,
       2       2
     390     421
       2       2
     390     421
Pier Skew, UpSta & Num, DnSta & Num=  ,2859, 2 ,2859, 2 , 0 , 0 , 0 ,,
       2       2
     390     421
       2       2
     390     421
Pier Skew, UpSta & Num, DnSta & Num=  ,2889, 2 ,2889, 2 , 0 , 0 , 0 ,,
       2       2
     390     421
       2       2
     390     421
Pier Skew, UpSta & Num, DnSta & Num=  ,2919, 2 ,2919, 2 , 0 , 0 , 0 ,,
       2       2
     390     421
       2       2
     390     421
BR Coef= 1 , 1 , 1 ,1.25, 0 ,,,0.8,-1,2,1,
WSPro=,,,, 1 ,,,, 0 ,,,, 0 ,,,,-1 ,-1 ,-1 , 0 , 0 , 0 , 0 , 0
BC Design=,, 0 ,, 0 ,,,,,,
BC HTab HWMax=436.7
BC Use User HTab Curves=0
BC User HTab FreeFlow(D)= 0

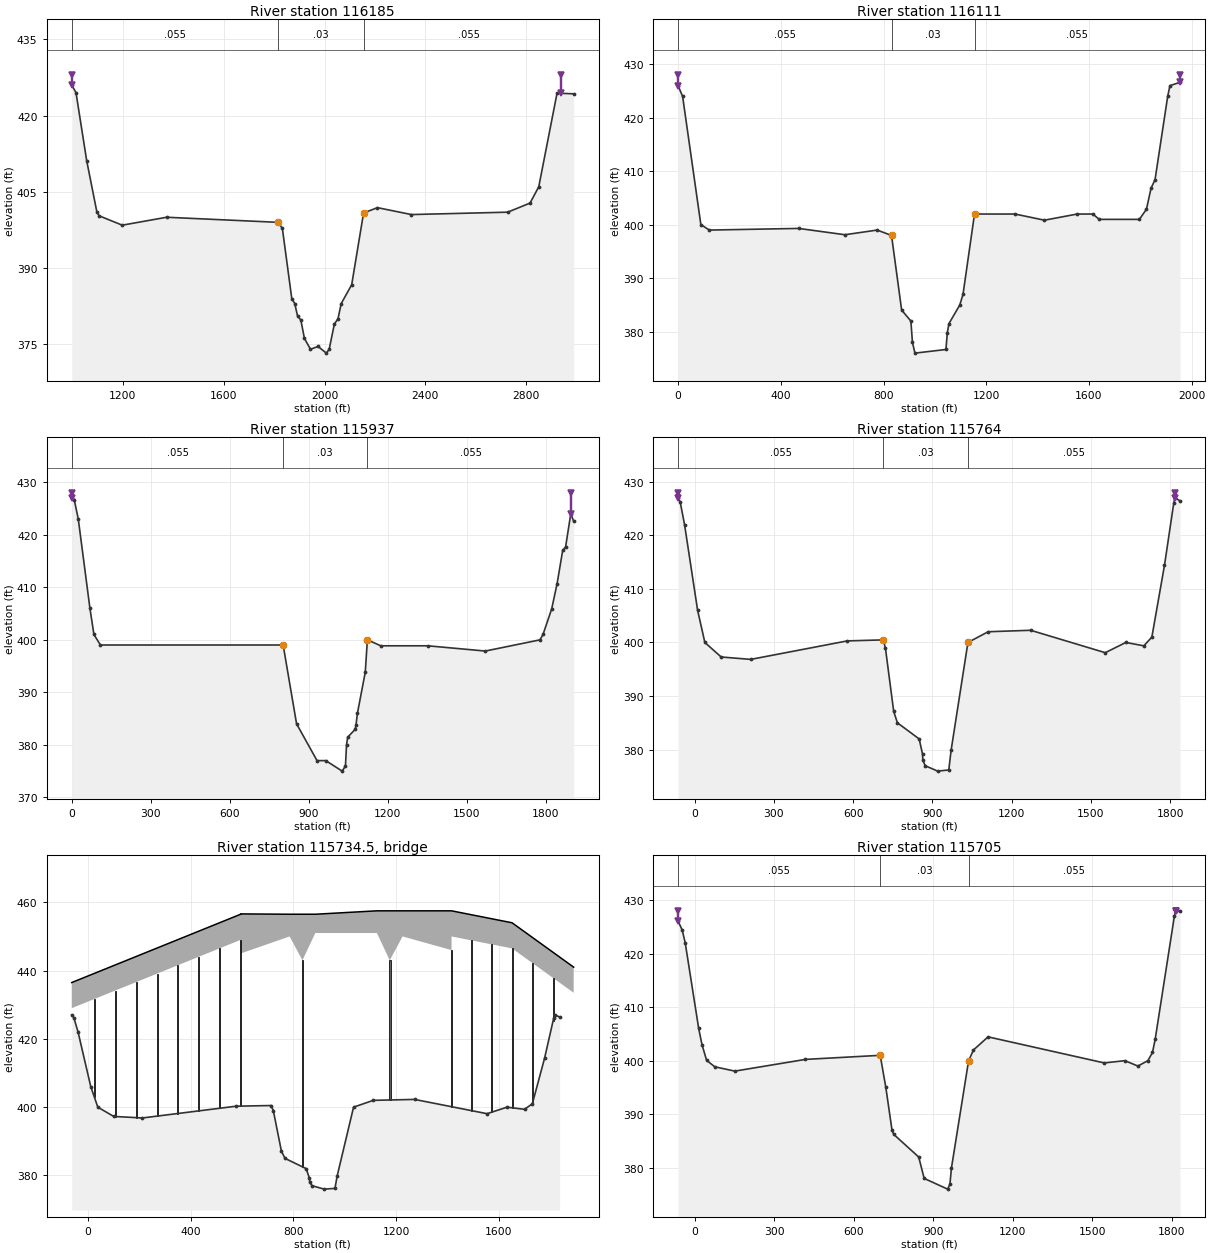
Type RM Length L Ch R = 1 ,116185  ,73,73,73
BEGIN DESCRIPTION:
This cross section corresponds to cross section 116185 of the non-georeferenced CDC model which was the source of this model.
END DESCRIPTION:
XS GIS Cut Line= 2
2487738.970748516966344.800990052486662.882677586964669.72691238
#Sta/Elev= 30
   997.2     426 1013.96  424.55 1056.37  411.15 1096.95     401 1105.95  400.28
 1197.52  398.44 1373.44     400 1815.37     399 1832.55  397.83  1869.9     384
 1881.75     383  1892.9  380.55 1905.84  379.78 1920.09  376.16 1944.17     374
 1974.15  374.57 2006.88  373.25 2018.26     374 2038.99     379 2053.26     380
 2065.97     383 2107.64  386.72 2154.71  400.83 2209.78  401.89 2344.61  400.53
 2726.43     401 2815.12  402.79 2849.68     406  2922.2  424.43 2988.14   424.3
#Mann= 3 ,0,0
   997.2    .055       0 1815.37     .03       0 2154.71    .055       0
Levee=-1,997.2,428.04,-1,2936,428.04,,
#XS Ineff= 2 , 0
         1815.37     399 2154.71          400.83
Permanent Ineff=
       F       F
Bank Sta=1815.37,2154.71
XS Rating Curve= 0 ,0
Exp/Cntr=0.3,0.1

Type RM Length L Ch R = 1 ,116111  ,155,169,184
BEGIN DESCRIPTION:
This cross section corresponds to cross section 116111 of the non-georeferenced CDC model which was the source of this model.
END DESCRIPTION:
XS GIS Cut Line= 2
2487801.524101086966309.857490382486746.872667076964664.56156838
#Sta/Elev= 30
       0     426   17.75     424   88.82  400.02  121.96     399  469.47  399.31
   649.6  398.13  775.21     399  831.24     398  870.59  384.05  906.58     382
  912.74     378  922.42     376 1043.13  376.68 1048.35  379.79 1054.87  381.52
 1097.07     385 1109.64     387 1154.38     402 1311.74     402 1426.87  400.85
 1554.37     402 1615.02     402 1640.18     401 1796.23     401 1823.79  402.89
 1841.75  406.82 1857.35  408.43 1906.56     424 1915.35     426  1954.3  426.62
#Mann= 3 ,0,0
       0    .055       0  831.24     .03       0 1154.38    .055       0
Levee=-1,0,428.02,-1,1954,428.02,,
#XS Ineff= 2 , 0
          831.24     398 1154.38             402
Permanent Ineff=
       F       F
Bank Sta=831.24,1154.38
XS Rating Curve= 0 ,0
Exp/Cntr=0.3,0.1

Type RM Length L Ch R = 1 ,115937  ,163,176,194
BEGIN DESCRIPTION:
This cross section corresponds to cross section 115937 of the non-georeferenced CDC model which was the source of this model.
END DESCRIPTION:
XS GIS Cut Line= 2
2487911.852292516966239.621738462486946.21970934 6964595.6283073
#Sta/Elev= 30
       0     427    9.69  426.57   24.66     423   68.96     406   84.25     401
  108.88     399     803     399     854     384  931.71     377  964.95     377
  1027.3     375 1039.71     376 1043.75     380  1048.2  381.46  1076.5  382.95
 1079.61   383.7 1085.14     386 1114.91  393.82 1123.03     400  1173.5  398.85
 1352.26  398.85 1570.98  397.85 1778.58  399.98 1790.14     401 1823.21  405.89
  1843.7  410.68 1864.91     417 1875.97  417.67 1895.69     424 1906.61  422.54
#Mann= 3 ,0,0
       0    .055       0     803     .03       0 1123.03    .055       0
Levee=-1,0,427.96,-1,1896,427.96,,
#XS Ineff= 2 , 0
             803     399 1123.03             399
Permanent Ineff=
       F       F
Bank Sta=803,1123.03
XS Rating Curve= 0 ,0
Exp/Cntr=0.3,0.1

Type RM Length L Ch R = 1 ,115764  ,59,59,59
BEGIN DESCRIPTION:
This cross section corresponds to cross section 115764 of the non-georeferenced CDC model which was the source of this model.
END DESCRIPTION:
XS GIS Cut Line= 2
2488022.687372686966156.803334552487126.722957256964480.84474422
#Sta/Elev= 30
     -63     427  -54.84  426.19   -38.4     422   11.08     406    38.5     400
  100.35  397.29  211.98  396.84  577.79  400.29  713.47  400.48   722.1     399
  753.56  387.13  767.64  385.01  850.05     382  862.75  379.17  863.91     378
  873.21     377  920.02     376  962.17  376.22  970.87  379.87 1034.62     400
 1111.44     402 1272.26  402.27 1554.63  398.09 1632.52     400 1700.73  399.37
 1731.03     401 1778.75  414.36 1813.97     426 1818.67     427 1837.43  426.41
#Mann= 3 ,0,0
     -63    .055       0  713.47     .03       0 1034.62    .055       0
Levee=-1,-63,427.91,-1,1818,427.91,,
#XS Ineff= 2 , 0
          713.47  400.48 1034.62             400
Permanent Ineff=
       F       F
Bank Sta=713.47,1034.62
XS Rating Curve= 0 ,0
Exp/Cntr=0.3,0.1

Type RM Length L Ch R = 3 ,115734.5,,,
BEGIN DESCRIPTION:
Jefferson Boulevard
END DESCRIPTION:
Node Name=Jefferson Blvd.
Bridge Culvert--1,0,-1,-1, 0
Deck Dist Width WeirC Skew NumUp NumDn MinLoCord MaxHiCord MaxSubmerge Is_Ogee
1,57,2.6,0, 13, 13, , , 0.95, 0, 0,0,,
     -63   594.8   594.8   785.6   835.6   885.6  1125.6  1175.6  1225.6  1416.3
  1416.3    1652    1892
   436.5   456.5   456.6   456.5   456.5   456.5   457.5   457.5   457.5   457.5
   457.5     454     441
     429     449     445     450     443     451     451     443     450     446
     450   446.5   433.5
     -63   594.8   594.8   785.6   835.6   885.6  1125.6  1175.6  1225.6  1416.3
  1416.3    1652    1892
   436.5   456.5   456.6   456.5   456.5   456.5   457.5   457.5   457.5   457.5
   457.5     454     441
     429     449     445     450     443     451     451     443     450     446
     450   446.5   433.5
Pier Skew, UpSta & Num, DnSta & Num=  ,25, 2 ,25, 2 , 0 , 0 , 0 ,,
       4       4
     370     438
       4       4
     370     438
Pier Skew, UpSta & Num, DnSta & Num=  ,106.4, 2 ,106.4, 2 , 0 , 0 , 0 ,,
       4       4
     370     440
       4       4
     370     440
Pier Skew, UpSta & Num, DnSta & Num=  ,187.8, 2 ,187.8, 2 , 0 , 0 , 0 ,,
       4       4
     370     442
       4       4
     370     442
Pier Skew, UpSta & Num, DnSta & Num=  ,269.2, 2 ,269.2, 2 , 0 , 0 , 0 ,,
       4       4
     370     443
       4       4
     370     443
Pier Skew, UpSta & Num, DnSta & Num=  ,350.6, 2 ,350.6, 2 , 0 , 0 , 0 ,,
       4       4
     370     447
       4       4
     370     447
Pier Skew, UpSta & Num, DnSta & Num=  ,432, 2 ,432, 2 , 0 , 0 , 0 ,,
       4       4
     370     449
       4       4
     370     449
Pier Skew, UpSta & Num, DnSta & Num=  ,513.4, 2 ,513.4, 2 , 0 , 0 , 0 ,,
       4       4
     370     452
       4       4
     370     452
Pier Skew, UpSta & Num, DnSta & Num=  ,594.8, 2 ,594.8, 2 , 0 , 0 , 0 ,,
       4       4
     370     453
       4       4
     370     453
Pier Skew, UpSta & Num, DnSta & Num=  ,835.6, 2 ,835.6, 2 , 0 , 0 , 0 ,,
       6       6
     370     454
       6       6
     370     454
Pier Skew, UpSta & Num, DnSta & Num=  ,1175.6, 2 ,1175.6, 2 , 0 , 0 , 0 ,,
       6       6
     370     454
       6       6
     370     454
Pier Skew, UpSta & Num, DnSta & Num=  ,1416.3, 2 ,1416.3, 2 , 0 , 0 , 0 ,,
       4       4
     370     454
       4       4
     370     454
Pier Skew, UpSta & Num, DnSta & Num=  ,1494.15, 2 ,1494.15, 2 , 0 , 0 , 0 ,,
       4       4
     370     452
       4       4
     370     452
Pier Skew, UpSta & Num, DnSta & Num=  ,1572, 2 ,1572, 2 , 0 , 0 , 0 ,,
       4       4
     370     452
       4       4
     370     452
Pier Skew, UpSta & Num, DnSta & Num=  ,1652, 2 ,1652, 2 , 0 , 0 , 0 ,,
       4       4
     370     452
       4       4
     370     452
Pier Skew, UpSta & Num, DnSta & Num=  ,1732, 2 ,1732, 2 , 0 , 0 , 0 ,,
       4       4
     370     445
       4       4
     370     445
Pier Skew, UpSta & Num, DnSta & Num=  ,1812, 2 ,1812, 2 , 0 , 0 , 0 ,,
       4       4
     370     440
       4       4
     370     440
BR Coef=-1 , 1 , 1 ,1.05, 0 ,,,0.8,-1,1.2,1,
WSPro=,,,, 1 ,,,, 0 ,,,, 0 ,,,,-1 ,-1 ,-1 , 0 , 0 , 0 , 0 , 0
BC Design=,, 0 ,, 0 ,,,,,,
BC HTab HWMax=427
BC Use User HTab Curves=0
BC User HTab FreeFlow(D)= 0

Type RM Length L Ch R = 1 ,115705  ,72,72,72
BEGIN DESCRIPTION:
This cross section corresponds to cross section 115705 of the non-georeferenced CDC model which was the source of this model.
END DESCRIPTION:
XS GIS Cut Line= 2
2488072.575396276966125.604906132487179.820620096964455.05050446
#Sta/Elev= 30
     -63  426.09  -47.33  424.42  -35.88     422   14.87  406.02   27.29  403.02
   44.73  400.07   75.57  398.86  151.33  398.05  417.79  400.24  699.91     401
  721.16     395  744.55     387  751.24  386.22  845.18     382  865.93     378
  954.45     376  963.09  376.94  968.94     380 1033.46  399.97  1051.9     402
 1107.05  404.45 1545.51  399.58 1623.23     400 1672.44     399 1710.01     400
 1727.45  401.53 1737.66     404 1810.11     427  1815.1     428 1831.14     428
#Mann= 3 ,0,0
     -63    .055       0  699.91     .03       0 1033.46    .055       0
Levee=-1,-63,427.89,-1,1815,427.89,,
#XS Ineff= 2 , 0
          699.91     401 1033.46          399.97
Permanent Ineff=
       F       F
Bank Sta=699.91,1033.46
XS Rating Curve= 0 ,0
Exp/Cntr=0.3,0.1

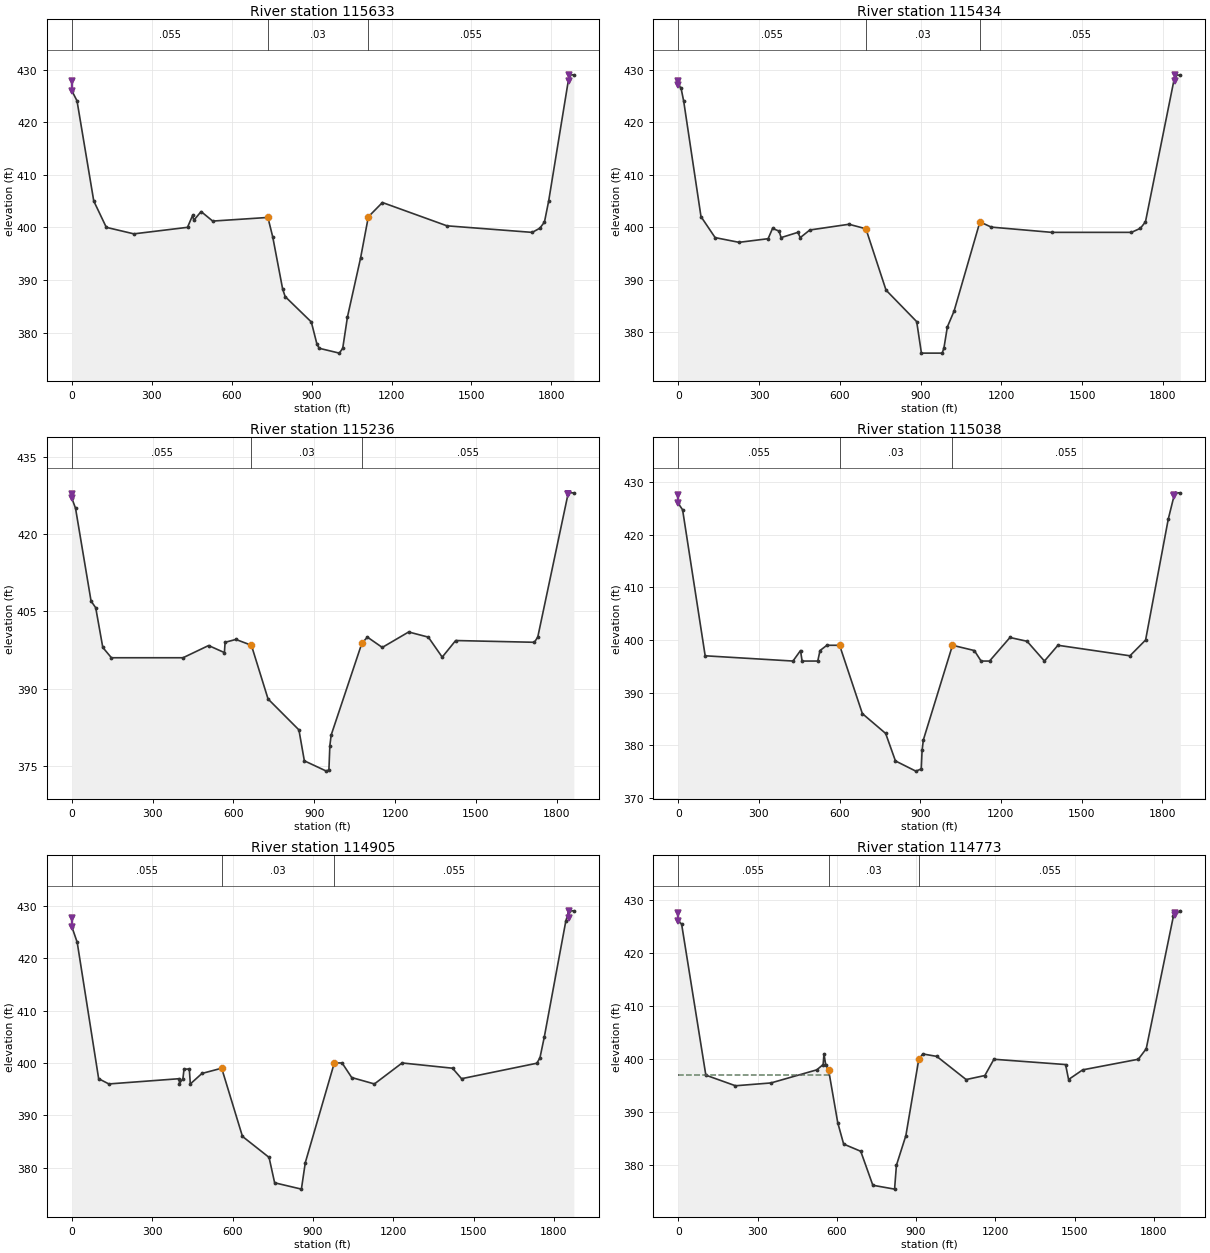
Type RM Length L Ch R = 1 ,115633  ,194,193,188
BEGIN DESCRIPTION:
This cross section corresponds to cross section 115633 of the non-georeferenced CDC model which was the source of this model.
END DESCRIPTION:
XS GIS Cut Line= 2
2488136.13432425 6966093.12531232487248.86542949 6964430.8746998
#Sta/Elev= 30
       0     426    19.7  424.05   82.55     405  129.62     400  233.03  398.76
  434.32     400  453.58  402.28  458.06  401.35  485.39     403  528.93  401.19
  736.04  401.88  754.15  398.19  791.46  388.25  800.87  386.83  899.04     382
  920.35  377.74  928.86     377 1004.09  376.08 1016.86     377 1034.76     383
 1083.81  394.15 1113.02     402 1165.81  404.72 1407.88  400.29 1728.16  399.04
 1756.62  399.84 1773.93     401 1789.72     405 1867.08     429 1884.23     429
#Mann= 3 ,0,0
       0    .055       0  736.04     .03       0 1113.02    .055       0
Levee=-1,0,427.86,-1,1867,427.86,,
#XS Ineff= 2 , 0
          736.04  401.88 1113.02             402
Permanent Ineff=
       F       F
Bank Sta=736.04,1113.02
XS Rating Curve= 0 ,0
Exp/Cntr=0.3,0.1

Type RM Length L Ch R = 1 ,115434  ,200,198,193
BEGIN DESCRIPTION:
This cross section corresponds to cross section 115434 of the non-georeferenced CDC model which was the source of this model.
END DESCRIPTION:
XS GIS Cut Line= 2
2488306.925649346965982.811884632487411.754211346964346.59927779
#Sta/Elev= 30
       0     427   10.15  426.54   20.22     424   84.54     402  137.05     398
   225.8   397.1  333.88  397.79   350.4  399.75  374.64  399.24  382.08     398
   444.4     399  453.37     398  488.76  399.45  634.29  400.54  697.14  399.68
  771.88     388  885.78     382  903.35     376  980.52     376  987.08     377
  999.77     381 1024.63     384 1120.66     401 1162.83     400 1387.38     399
 1683.58     399 1716.71  399.77 1735.63     401 1845.49     429 1865.08  428.92
#Mann= 3 ,0,0
       0    .055       0  697.14     .03       0 1120.66    .055       0
Levee=-1,0,427.79,-1,1845,427.79,,
#XS Ineff= 2 , 0
          697.14  399.68 1120.66             401
Permanent Ineff=
       F       F
Bank Sta=697.14,1120.66
XS Rating Curve= 0 ,0
Exp/Cntr=0.3,0.1

Type RM Length L Ch R = 1 ,115236  ,207,205,200
BEGIN DESCRIPTION:
This cross section corresponds to cross section 115236 of the non-georeferenced CDC model which was the source of this model.
END DESCRIPTION:
XS GIS Cut Line= 2
2488478.217957686965869.661848472487567.683033356964243.95446996
#Sta/Elev= 30
       0     427   13.97     425    71.6     407   88.85   405.7  115.15     398
   147.1     396  412.91     396   507.8  398.37  566.45     397  569.05     399
  609.21  399.55  666.67  398.42  728.48     388  843.01     382  863.18     376
  945.02     374  954.34  374.27  957.85  378.97  962.72     381 1076.64  398.82
  1097.3     400 1152.36     398 1250.27     401 1323.23     400  1374.8  396.12
 1424.74  399.34 1716.78     399 1729.38     400 1842.67     428 1863.33     428
#Mann= 3 ,0,0
       0    .055       0  666.67     .03       0 1076.64    .055       0
Levee=-1,0,427.72,-1,1842,427.72,,
#XS Ineff= 2 , 0
          666.67  398.42 1076.64          398.82
Permanent Ineff=
       F       F
Bank Sta=666.67,1076.64
XS Rating Curve= 0 ,0
Exp/Cntr=0.3,0.1

Type RM Length L Ch R = 1 ,115038  ,118,134,151
BEGIN DESCRIPTION:
This cross section corresponds to cross section 115038 of the non-georeferenced CDC model which was the source of this model.
END DESCRIPTION:
XS GIS Cut Line= 2
2488652.000090426965755.000332392487722.999651856964134.99963538
#Sta/Elev= 30
       0     426   16.22  424.77  100.21     397  426.74     396   454.8     398
  460.74     396  518.95     396  527.41     398  552.97     399  600.18     399
  684.87     386  771.49  382.23  807.89     377  883.67  375.06  903.85  375.47
  907.01     379  911.73     381 1020.12     399 1101.31     398 1126.45     396
 1157.93     396 1233.86  400.48 1297.49  399.76  1362.1     396 1412.25     399
 1680.15     397 1738.34     400 1822.67     423 1846.93     428 1867.47     428
#Mann= 3 ,0,0
       0    .055       0  600.18     .03       0 1020.12    .055       0
Levee=-1,0,427.65,-1,1844,427.65,,
#XS Ineff= 2 , 0
          600.18     399 1020.12             399
Permanent Ineff=
       F       F
Bank Sta=600.18,1020.12
XS Rating Curve= 0 ,0
Exp/Cntr=0.3,0.1

Type RM Length L Ch R = 1 ,114905  ,117,133,151
BEGIN DESCRIPTION:
This cross section corresponds to cross section 114905 of the non-georeferenced CDC model which was the source of this model.
END DESCRIPTION:
XS GIS Cut Line= 2
2488728.00912476 6965695.11232882487865.663736586964031.14157538
#Sta/Elev= 30
       0     426   20.26     423  100.35     397  138.42     396   400.9     397
     402  396.08  414.93     397  418.98  398.81  438.74  398.85  442.54     396
  485.95     398  559.57     399  637.15     386  736.44     382  757.24  377.16
  857.16  375.95  871.72     381  979.99     400 1009.05     400 1044.98  397.22
 1129.63     396 1233.15     400 1421.28     399 1454.98     397 1736.09  399.95
 1747.73     401 1764.03     405 1844.04     427 1855.18     429 1874.15     429
#Mann= 3 ,0,0
       0    .055       0  559.57     .03       0  979.99    .055       0
Levee=-1,0,427.61,-1,1855,427.61,,
#XS Ineff= 2 , 0
          559.57     399  979.99             400
Permanent Ineff=
       F       F
Bank Sta=559.57,979.99
XS Rating Curve= 0 ,0
Exp/Cntr=0.3,0.1

Type RM Length L Ch R = 1 ,114773  ,113,128,145
BEGIN DESCRIPTION:
This cross section corresponds to cross section 114773 of the non-georeferenced CDC model which was the source of this model.
END DESCRIPTION:
XS GIS Cut Line= 2
2488809.097217176965638.225959632488005.12868077 6963916.4623428
#Sta/Elev= 30
       0     426   12.61  425.55  104.46     397  216.61     395  350.87  395.53
  524.28     398  548.46     399  551.53     401  558.09     399  568.98     398
  603.83     388  626.02     384  690.75  382.64  736.53  376.23   818.8   375.5
  825.78     380  861.59  385.61  910.43     400  925.71     401  978.59  400.54
 1089.62  396.17 1160.44  396.93  1194.7     400 1465.98     399 1477.34  396.18
 1530.72     398 1741.16     400 1771.22  401.98 1874.12     427 1900.22     428
#Mann= 3 ,0,0
       0    .055       0  568.98     .03       0  910.43    .055       0
Levee=-1,0,427.58,-1,1880,427.58,,
#XS Ineff= 2 , 0
          573.37     397  910.43             400
Permanent Ineff=
       F       F
Bank Sta=568.98,910.43
XS Rating Curve= 0 ,0
Exp/Cntr=0.3,0.1