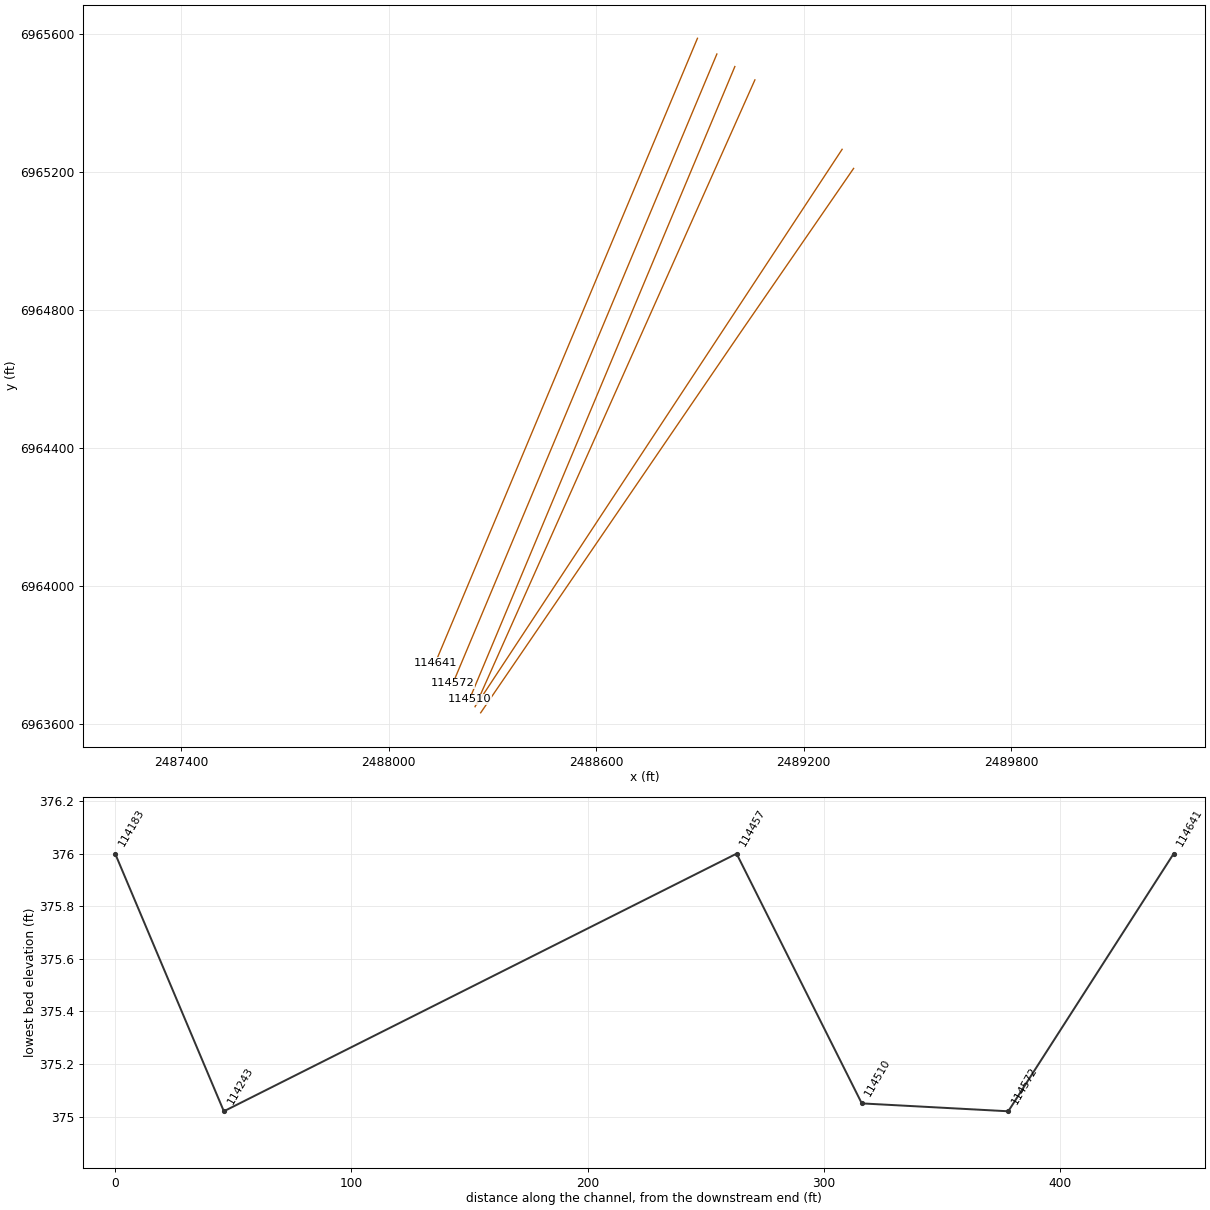
HEC-RAS study CDC_Consolidated_Model.prj: Upper Trinity CDC Consolidated Model

--- CDC_Consolidated_Model.g13 (geometry) --- (continued)

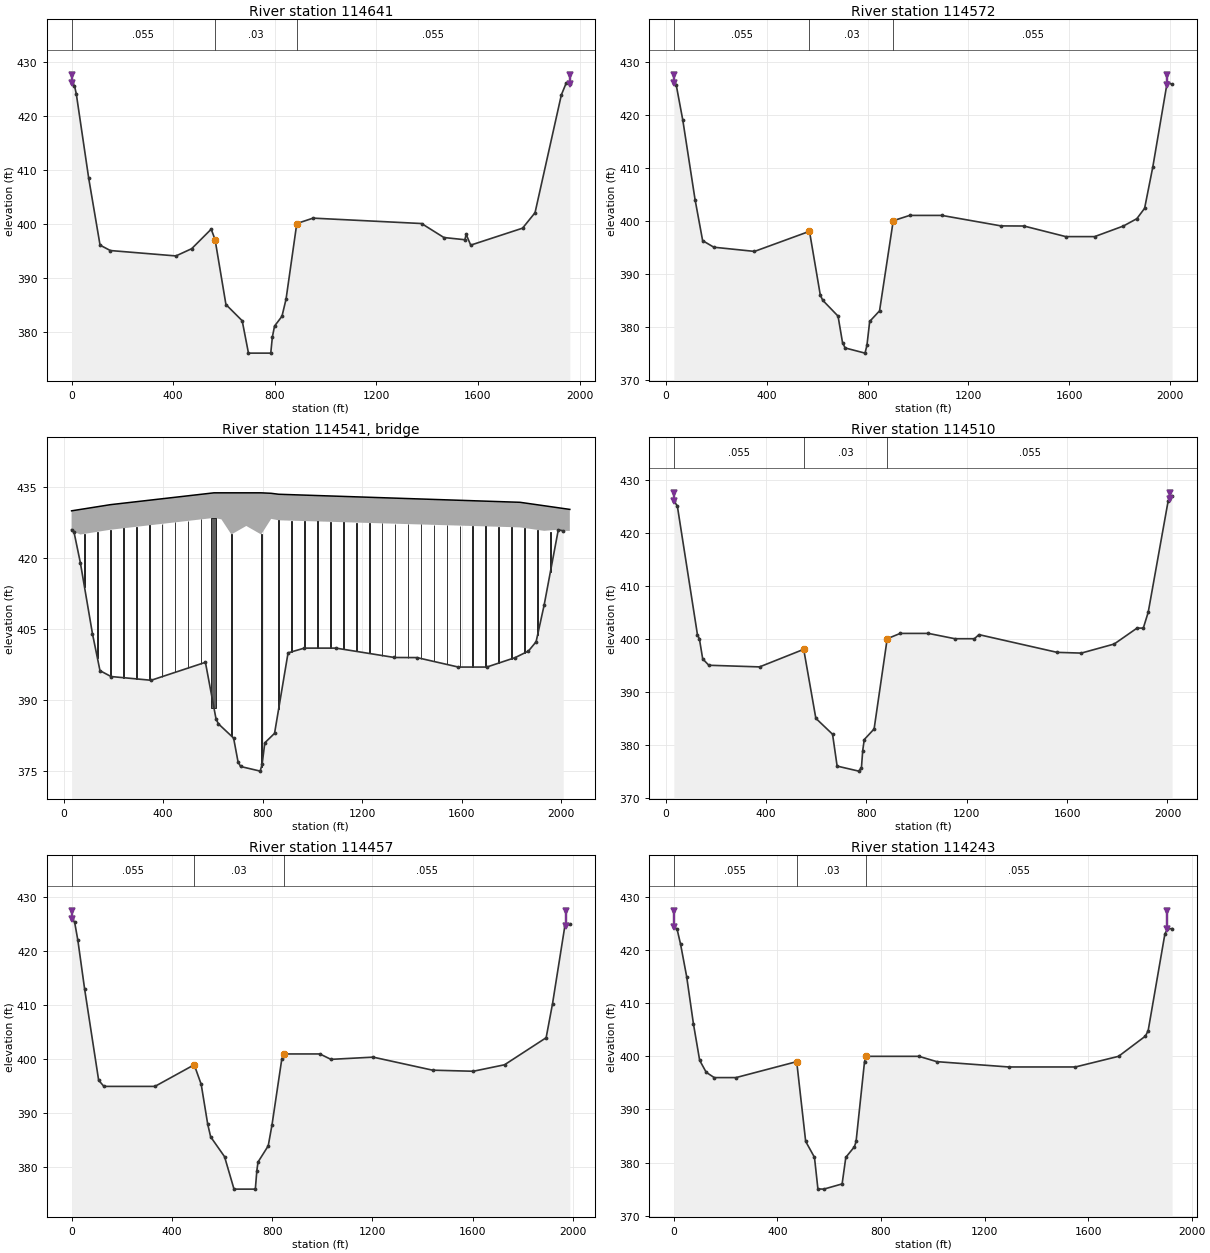
Type RM Length L Ch R = 1 ,114641  ,70,70,70
BEGIN DESCRIPTION:
This cross section corresponds to cross section 114641 of the non-georeferenced CDC model which was the source of this model.
END DESCRIPTION:
XS GIS Cut Line= 2
2488893.062600436965586.307100222488134.802962096963776.91570589
#Sta/Elev= 30
       0     426   11.43  425.54    18.6     424   67.46  408.38  112.12     396
  152.53     395  410.87     394  472.83  395.34   549.8  398.96  565.07     397
  607.75     385  671.76     382  696.49     376  784.28     376   790.6  378.99
  799.08     381  828.41  382.83  844.47     386  886.77     400  950.89     401
 1378.09     400 1465.99  397.41 1548.65     397 1553.54     398 1571.49     396
 1775.61  399.14  1824.8     402 1928.52  423.84  1947.4     426 1961.85  425.89
#Mann= 3 ,0,0
       0    .055       0  565.07     .03       0  886.77    .055       0
Levee=-1,0,427.54,-1,1961,427.54,,
#XS Ineff= 2 , 0
          565.07     397  886.77             400
Permanent Ineff=
       F       F
Bank Sta=565.07,886.77
XS Rating Curve= 0 ,0
Exp/Cntr=0.3,0.1

Type RM Length L Ch R = 1 ,114572  ,62,62,62
BEGIN DESCRIPTION:
This cross section corresponds to cross section 114572 of the non-georeferenced CDC model which was the source of this model.
END DESCRIPTION:
XS GIS Cut Line= 2
2488949.181582666965540.838359132488186.12864685 6963718.6989588
#Sta/Elev= 30
      32     426   41.68  425.54   67.41     419  116.05     404  146.14  396.24
  190.51     395  351.76  394.21  569.76     398  612.54     386  622.12     385
  683.01     382   700.7  377.02  711.05     376  789.93  375.02   797.6   376.5
  808.46     381  847.55     383  901.82     400  967.02     401 1094.45     401
 1329.26  399.02 1419.88     399 1586.01     397 1700.33     397  1814.4     399
  1867.6  400.38 1898.44  402.34 1930.78   410.1 1987.67     426 2007.46  425.76
#Mann= 3 ,0,0
      32    .055       0  569.76     .03       0  901.82    .055       0
Levee=-1,32,427.52,-1,1986,427.52,,
#XS Ineff= 2 , 0
          569.76     398  901.82             400
Permanent Ineff=
       F       F
Bank Sta=569.76,901.82
XS Rating Curve= 0 ,0
Exp/Cntr=0.3,0.1

Type RM Length L Ch R = 3 ,114541  ,,,
BEGIN DESCRIPTION:
IH 35E South Bound
END DESCRIPTION:
Node Name=IH 35E SB
Bridge Culvert--1,0,-1,-1, 0
Deck Dist Width WeirC Skew NumUp NumDn MinLoCord MaxHiCord MaxSubmerge Is_Ogee
2,58,2.6,0, 11, 11, , , 0.95, 0, ,,,
      32     188     604     634     674     734     794     834     864    1834
    2034
     430   431.3   433.8   433.8   433.8   433.8   433.8   433.7   433.5   431.8
   430.3
   424.7     426   428.5   428.2     425   426.8     425   428.3     428   426.5
     425
      32     188     604     634     674     734     794     834     864    1834
    2034
     430   431.3   433.8   433.8   433.8   433.8   433.8   433.7   433.5   431.8
   430.3
   424.7     426   428.5   428.2     425   426.8     425   428.3     428   426.5
     425
Pier Skew, UpSta & Num, DnSta & Num=  ,84, 2 ,84, 2 , 0 , 0 , 0 ,,
     2.5     2.5
     370     430
     2.5     2.5
     370     430
Pier Skew, UpSta & Num, DnSta & Num=  ,136, 2 ,136, 2 , 0 , 0 , 0 ,,
     2.5     2.5
     370     430
     2.5     2.5
     370     430
Pier Skew, UpSta & Num, DnSta & Num=  ,188, 2 ,188, 2 , 0 , 0 , 0 ,,
     2.5     2.5
     370     430
     2.5     2.5
     370     430
Pier Skew, UpSta & Num, DnSta & Num=  ,240, 2 ,240, 2 , 0 , 0 , 0 ,,
     2.5     2.5
     370     430
     2.5     2.5
     370     430
Pier Skew, UpSta & Num, DnSta & Num=  ,292, 2 ,292, 2 , 0 , 0 , 0 ,,
     2.5     2.5
     370     430
     2.5     2.5
     370     430
Pier Skew, UpSta & Num, DnSta & Num=  ,344, 2 ,344, 2 , 0 , 0 , 0 ,,
     2.5     2.5
     370     430
     2.5     2.5
     370     430
Pier Skew, UpSta & Num, DnSta & Num=  ,396, 2 ,396, 2 , 0 , 0 , 0 ,,
     2.5     2.5
     370     430
     2.5     2.5
     370     430
Pier Skew, UpSta & Num, DnSta & Num=  ,448, 2 ,448, 2 , 0 , 0 , 0 ,,
     2.5     2.5
     370     430
     2.5     2.5
     370     430
Pier Skew, UpSta & Num, DnSta & Num=  ,500, 2 ,500, 2 , 0 , 0 , 0 ,,
     2.5     2.5
     370     430
     2.5     2.5
     370     430
Pier Skew, UpSta & Num, DnSta & Num=  ,552, 2 ,552, 2 , 0 , 0 , 0 ,,
     2.5     2.5
     370     430
     2.5     2.5
     370     430
Pier Skew, UpSta & Num, DnSta & Num=  ,604, 4 ,604, 4 , 0 , 0 , 0 ,,
      20      20     2.5     2.5
     370     399     399     430
      20      20     2.5     2.5
     370     399     399     430
Pier Skew, UpSta & Num, DnSta & Num=  ,674, 4 ,674, 4 , 0 , 0 , 0 ,,
       4       4       3       3
     370     398     398     430
       4       4       3       3
     370     398     398     430
Pier Skew, UpSta & Num, DnSta & Num=  ,794, 4 ,794, 4 , 0 , 0 , 0 ,,
       4       4       3       3
     370     398     398     430
       4       4       3       3
     370     398     398     430
Pier Skew, UpSta & Num, DnSta & Num=  ,864, 2 ,864, 2 , 0 , 0 , 0 ,,
     2.5     2.5
     370     430
     2.5     2.5
     370     430
Pier Skew, UpSta & Num, DnSta & Num=  ,916, 2 ,916, 2 , 0 , 0 , 0 ,,
     2.5     2.5
     370     430
     2.5     2.5
     370     430
Pier Skew, UpSta & Num, DnSta & Num=  ,968, 2 ,968, 2 , 0 , 0 , 0 ,,
     2.5     2.5
     370     430
     2.5     2.5
     370     430
Pier Skew, UpSta & Num, DnSta & Num=  ,1020, 2 ,1020, 2 , 0 , 0 , 0 ,,
     2.5     2.5
     370     430
     2.5     2.5
     370     430
Pier Skew, UpSta & Num, DnSta & Num=  ,1072, 2 ,1072, 2 , 0 , 0 , 0 ,,
     2.5     2.5
     370     430
     2.5     2.5
     370     430
Pier Skew, UpSta & Num, DnSta & Num=  ,1124, 2 ,1124, 2 , 0 , 0 , 0 ,,
     2.5     2.5
     370     430
     2.5     2.5
     370     430
Pier Skew, UpSta & Num, DnSta & Num=  ,1176, 2 ,1176, 2 , 0 , 0 , 0 ,,
     2.5     2.5
     370     430
     2.5     2.5
     370     430
Pier Skew, UpSta & Num, DnSta & Num=  ,1228, 2 ,1228, 2 , 0 , 0 , 0 ,,
     2.5     2.5
     370     430
     2.5     2.5
     370     430
Pier Skew, UpSta & Num, DnSta & Num=  ,1280, 2 ,1280, 2 , 0 , 0 , 0 ,,
     2.5     2.5
     370     430
     2.5     2.5
     370     430
Pier Skew, UpSta & Num, DnSta & Num=  ,1332, 2 ,1332, 2 , 0 , 0 , 0 ,,
     2.5     2.5
     370     430
     2.5     2.5
     370     430
Pier Skew, UpSta & Num, DnSta & Num=  ,1384, 2 ,1384, 2 , 0 , 0 , 0 ,,
     2.5     2.5
     370     430
     2.5     2.5
     370     430
Pier Skew, UpSta & Num, DnSta & Num=  ,1436, 2 ,1436, 2 , 0 , 0 , 0 ,,
     2.5     2.5
     370     430
     2.5     2.5
     370     430
Pier Skew, UpSta & Num, DnSta & Num=  ,1488, 2 ,1488, 2 , 0 , 0 , 0 ,,
     2.5     2.5
     370     430
     2.5     2.5
     370     430
Pier Skew, UpSta & Num, DnSta & Num=  ,1540, 2 ,1540, 2 , 0 , 0 , 0 ,,
     2.5     2.5
     370     430
     2.5     2.5
     370     430
Pier Skew, UpSta & Num, DnSta & Num=  ,1592, 2 ,1592, 2 , 0 , 0 , 0 ,,
     2.5     2.5
     370     430
     2.5     2.5
     370     430
Pier Skew, UpSta & Num, DnSta & Num=  ,1644, 2 ,1644, 2 , 0 , 0 , 0 ,,
     2.5     2.5
     370     430
     2.5     2.5
     370     430
Pier Skew, UpSta & Num, DnSta & Num=  ,1696, 2 ,1696, 2 , 0 , 0 , 0 ,,
     2.5     2.5
     370     430
     2.5     2.5
     370     430
Pier Skew, UpSta & Num, DnSta & Num=  ,1748, 2 ,1748, 2 , 0 , 0 , 0 ,,
     2.5     2.5
     370     430
     2.5     2.5
     370     430
Pier Skew, UpSta & Num, DnSta & Num=  ,1800, 2 ,1800, 2 , 0 , 0 , 0 ,,
     2.5     2.5
     370     430
     2.5     2.5
     370     430
Pier Skew, UpSta & Num, DnSta & Num=  ,1852, 2 ,1852, 2 , 0 , 0 , 0 ,,
     2.5     2.5
     370     430
     2.5     2.5
     370     430
Pier Skew, UpSta & Num, DnSta & Num=  ,1904, 2 ,1904, 2 , 0 , 0 , 0 ,,
     2.5     2.5
     370     430
     2.5     2.5
     370     430
Pier Skew, UpSta & Num, DnSta & Num=  ,1956, 2 ,1956, 2 , 0 , 0 , 0 ,,
     2.5     2.5
     370     430
     2.5     2.5
     370     430
BR Coef= 1 , 1 , 1 ,1.05, 0 ,,,0.8,-1,1.2,1,
WSPro=,,,, 1 ,,,, 0 ,,,, 0 ,,,,-1 ,-1 ,-1 , 0 , 0 , 0 , 0 , 0
BC Design=,, 0 ,, 0 ,,,,,,
BC HTab HWMax=427
BC Use User HTab Curves=0
BC User HTab FreeFlow(D)= 0

Type RM Length L Ch R = 1 ,114510  ,53,53,45
BEGIN DESCRIPTION:
This cross section corresponds to cross section 114510 of the non-georeferenced CDC model which was the source of this model.
END DESCRIPTION:
XS GIS Cut Line= 2
 2489001.16507456965504.510019722488234.023892256963672.24465539
#Sta/Elev= 30
      32     426   45.96     425  126.22  400.72  133.77     400     147   396.2
  171.46     395  373.73  394.69  549.72     398   598.1     385  664.72     382
  682.92     376  769.05  375.05  779.89   375.7  784.94  378.93  791.17     381
  830.39     383  882.59     400  934.49     401  1046.9     401 1152.42     400
 1230.11     400 1248.32  400.77 1559.98  397.43 1656.25  397.29 1787.45     399
 1878.55     402 1903.58     402 1923.16     405 2002.75     426 2018.38  426.94
#Mann= 3 ,0,0
      32    .055       0  549.72     .03       0  882.59    .055       0
Levee=-1,32,427.49,-1,2009,427.49,,
#XS Ineff= 2 , 0
          549.72     398  882.59             400
Permanent Ineff=
       F       F
Bank Sta=549.72,882.59
XS Rating Curve= 0 ,0
Exp/Cntr=0.3,0.1

Type RM Length L Ch R = 1 ,114457  ,253,217,132
BEGIN DESCRIPTION:
This cross section corresponds to cross section 114457 of the non-georeferenced CDC model which was the source of this model.
END DESCRIPTION:
XS GIS Cut Line= 2
2489059.135430996965465.897892222488250.031406166963650.35920046
#Sta/Elev= 30
       0     426      12  425.42   25.12     422   52.06     413  107.97  396.14
  129.04     395  332.49     395  489.22     399  517.13  395.37  543.11     388
   554.8  385.67  610.25     382  647.98     376  733.05     376  738.98  379.37
  743.63     381  784.46     384   799.7  387.93  838.42     400  846.98     401
  990.49     401 1034.59     400 1203.09  400.41 1440.16     398 1602.51   397.8
 1727.29     399 1893.12     404 1918.59  410.29 1967.62  424.61 1987.67  425.02
#Mann= 3 ,0,0
       0    .055       0  489.22     .03       0  846.98    .055       0
Levee=-1,0,427.47,-1,1972,427.47,,
#XS Ineff= 2 , 0
          489.22     399  846.98             401
Permanent Ineff=
       F       F
Bank Sta=489.22,846.98
XS Rating Curve= 0 ,0
Exp/Cntr=0.3,0.1

Type RM Length L Ch R = 1 ,114243  ,46,46,46
BEGIN DESCRIPTION:
This cross section corresponds to cross section 114243 of the non-georeferenced CDC model which was the source of this model.
END DESCRIPTION:
XS GIS Cut Line= 2
2489311.322590686965264.811024052488254.654756526963656.61115646
#Sta/Elev= 30
       0  424.27   12.68  423.88   26.02  421.08   49.48     415    75.7  406.09
    99.7  399.25  124.94     397  155.97     396  239.94     396  474.46     399
  509.09     384  543.09     381  556.39  375.06  579.06  375.02  649.86     376
  664.14     381  697.52     383   703.8     384  736.39     399  741.97     400
  946.74     400 1015.36     399 1293.26     398 1550.97     398 1717.43     400
 1821.07   403.8 1831.75  404.82 1896.35     423 1905.91  423.97 1924.28  424.03
#Mann= 3 ,0,0
       0    .055       0  474.46     .03       0  741.97    .055       0
Levee=-1,0,427.37,-1,1906,427.37,,
#XS Ineff= 2 , 0
          474.46     399  741.97             400
Permanent Ineff=
       F       F
Bank Sta=474.46,741.97
XS Rating Curve= 0 ,0
Exp/Cntr=0.3,0.1

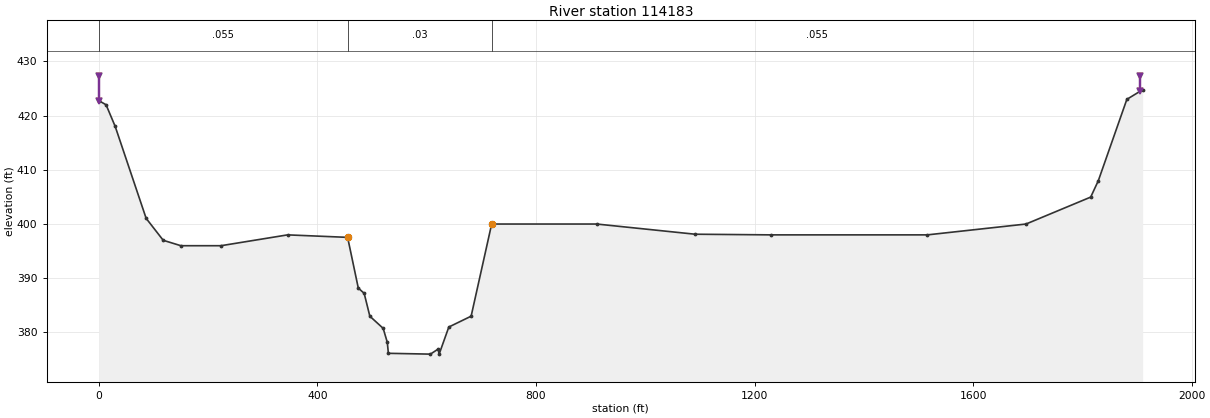
Type RM Length L Ch R = 1 ,114183  ,76,76,76
BEGIN DESCRIPTION:
This cross section corresponds to cross section 114183 of the non-georeferenced CDC model which was the source of this model.
END DESCRIPTION:
XS GIS Cut Line= 3
2489344.551526846965209.516515212489018.155854176964735.25138763
2488266.25676742 6963632.7818078
#Sta/Elev= 30
       0  422.76   13.22     422   29.92     418   86.53  401.05  117.78     397
   150.1     396  223.49     396  345.43     398  455.26  397.54  474.78  388.19
  485.56  387.21   495.9     383  520.33  380.75  527.88  378.17  529.83  376.15
  606.78     376  620.73  376.92  622.76     376  640.43     381  681.29     383
  718.87     400  911.11     400 1091.26  398.12 1230.37     398 1516.21     398
 1696.75     400 1815.13  404.97 1829.09     408 1881.28     423 1910.19  424.78
#Mann= 3 ,0,0
       0    .055       0  455.26     .03       0  718.87    .055       0
Levee=-1,0,427.34,-1,1906,427.34,,
#XS Ineff= 2 , 0
          455.26  397.54  718.87             400
Permanent Ineff=
       F       F
Bank Sta=455.26,718.87
XS Rating Curve= 0 ,0
Exp/Cntr=0.3,0.1