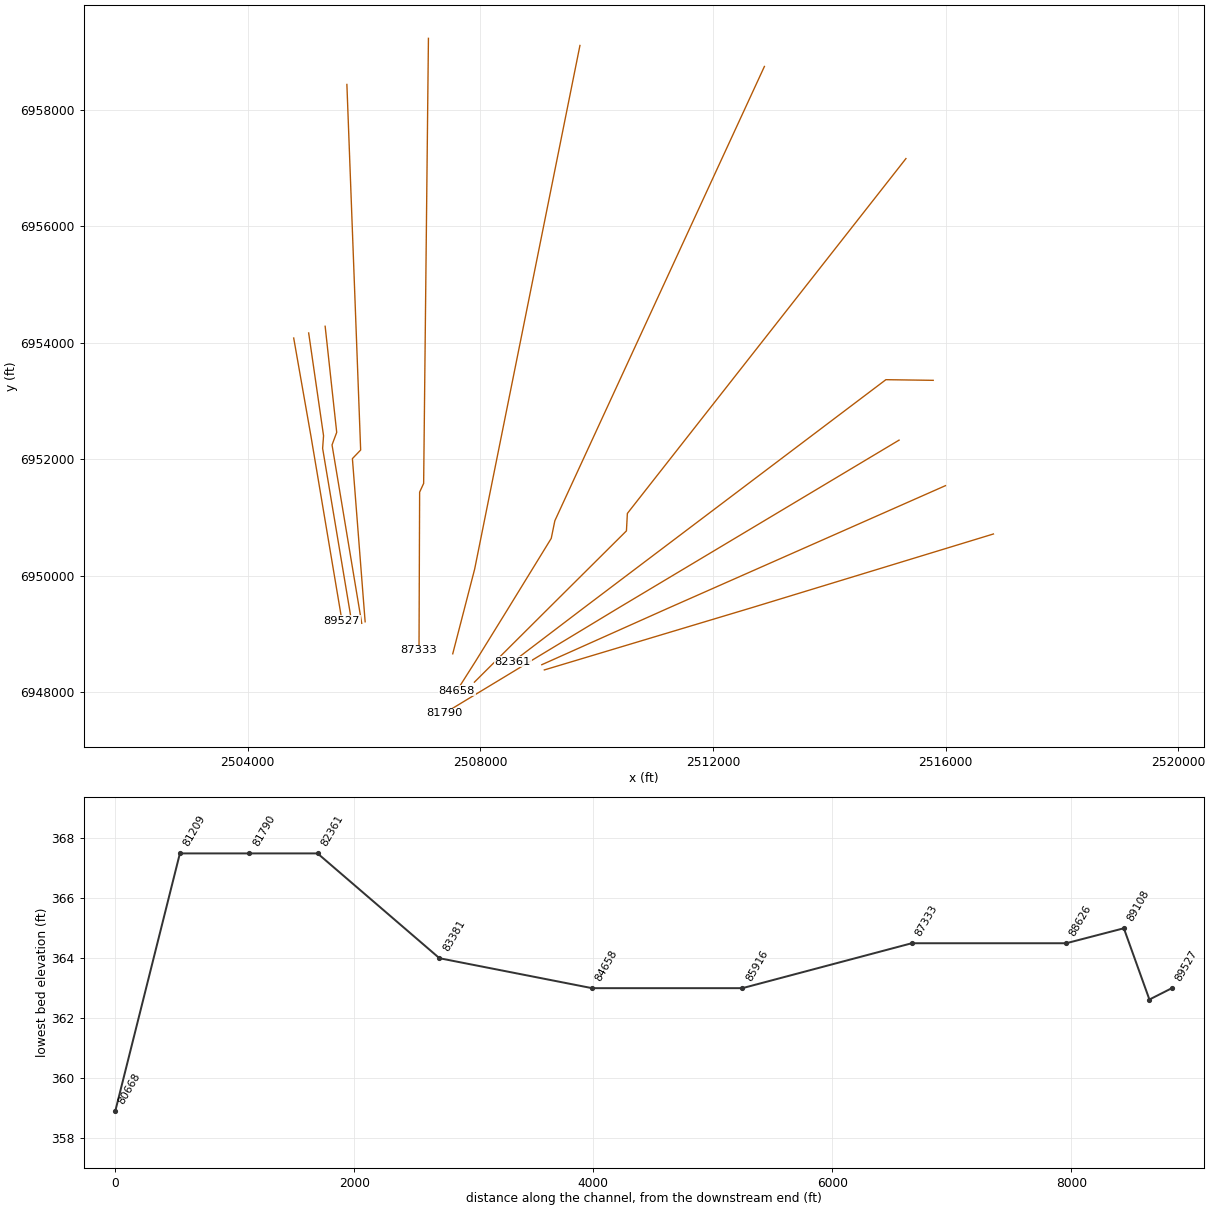
HEC-RAS study CDC_Consolidated_Model.prj: Upper Trinity CDC Consolidated Model

--- CDC_Consolidated_Model.g13 (geometry) --- (continued)

Type RM Length L Ch R = 3 ,89537   ,,,
BEGIN DESCRIPTION:
Union Pacific Railroad
END DESCRIPTION:
Node Name=Union Pacific RR
Bridge Culvert--1,0,-1,-1, 0
Deck Dist Width WeirC Skew NumUp NumDn MinLoCord MaxHiCord MaxSubmerge Is_Ogee
1,18,2.6,0, 30, 30, , , 0.95, 0, ,,,
    1150    2662    2662    2663    2663    2683    2683    2684    2684    2704
    2704    2705    2705    2725    2725    2726    2726    2746    2746    2747
    2747    2767    2767    2768    2768    2788    2788    2789    2789    4103
     411     411     420     420     411     411     420     420     411     411
     420     420     411     411     420     420     411     411     420     420
     411     411     420     420     411     411     420     420     411     411
   408.4   408.4   408.4   408.4   408.4   408.4   408.4   408.4   408.4   408.4
   408.4   408.4   408.4   408.4   408.4   408.4   408.4   408.4   408.4   408.4
   408.4   408.4   408.4   408.4   408.4   408.4   408.4   408.4   408.4   408.4
    1150    2662    2662    2663    2663    2683    2683    2684    2684    2704
    2704    2705    2705    2725    2725    2726    2726    2746    2746    2747
    2747    2767    2767    2768    2768    2788    2788    2789    2789    4103
     411     411     420     420     411     411     420     420     411     411
     420     420     411     411     420     420     411     411     420     420
     411     411     420     420     411     411     420     420     411     411
   408.4   408.4   408.4   408.4   408.4   408.4   408.4   408.4   408.4   408.4
   408.4   408.4   408.4   408.4   408.4   408.4   408.4   408.4   408.4   408.4
   408.4   408.4   408.4   408.4   408.4   408.4   408.4   408.4   408.4   408.4
Pier Skew, UpSta & Num, DnSta & Num=  ,1167, 2 ,1167, 2 , 0 , 0 , 0 ,,
       5       5
       0     410
       5       5
       0     410
Pier Skew, UpSta & Num, DnSta & Num=  ,1188, 2 ,1188, 2 , 0 , 0 , 0 ,,
     6.2     6.2
       0     410
     6.2     6.2
       0     410
Pier Skew, UpSta & Num, DnSta & Num=  ,1221, 2 ,1221, 2 , 0 , 0 , 0 ,,
     2.4     2.4
       0     410
     2.4     2.4
       0     410
Pier Skew, UpSta & Num, DnSta & Num=  ,1251, 2 ,1251, 2 , 0 , 0 , 0 ,,
     2.4     2.4
       0     410
     2.4     2.4
       0     410
Pier Skew, UpSta & Num, DnSta & Num=  ,1281, 2 ,1281, 2 , 0 , 0 , 0 ,,
     2.4     2.4
       0     410
     2.4     2.4
       0     410
Pier Skew, UpSta & Num, DnSta & Num=  ,1311, 2 ,1311, 2 , 0 , 0 , 0 ,,
     2.4     2.4
       0     410
     2.4     2.4
       0     410
Pier Skew, UpSta & Num, DnSta & Num=  ,1341, 2 ,1341, 2 , 0 , 0 , 0 ,,
     2.4     2.4
       0     410
     2.4     2.4
       0     410
Pier Skew, UpSta & Num, DnSta & Num=  ,1371, 2 ,1371, 2 , 0 , 0 , 0 ,,
     2.4     2.4
       0     410
     2.4     2.4
       0     410
Pier Skew, UpSta & Num, DnSta & Num=  ,1401, 2 ,1401, 2 , 0 , 0 , 0 ,,
     2.4     2.4
       0     410
     2.4     2.4
       0     410
Pier Skew, UpSta & Num, DnSta & Num=  ,1431, 2 ,1431, 2 , 0 , 0 , 0 ,,
     2.4     2.4
       0     410
     2.4     2.4
       0     410
Pier Skew, UpSta & Num, DnSta & Num=  ,1461, 2 ,1461, 2 , 0 , 0 , 0 ,,
     2.4     2.4
       0     410
     2.4     2.4
       0     410
Pier Skew, UpSta & Num, DnSta & Num=  ,1491, 2 ,1491, 2 , 0 , 0 , 0 ,,
     2.4     2.4
       0     410
     2.4     2.4
       0     410
Pier Skew, UpSta & Num, DnSta & Num=  ,1508, 2 ,1508, 2 , 0 , 0 , 0 ,,
       5       5
       0     410
       5       5
       0     410
Pier Skew, UpSta & Num, DnSta & Num=  ,1523, 2 ,1523, 2 , 0 , 0 , 0 ,,
     1.2     1.2
       0     410
     1.2     1.2
       0     410
Pier Skew, UpSta & Num, DnSta & Num=  ,1538, 2 ,1538, 2 , 0 , 0 , 0 ,,
     1.2     1.2
       0     410
     1.2     1.2
       0     410
Pier Skew, UpSta & Num, DnSta & Num=  ,1553, 2 ,1553, 2 , 0 , 0 , 0 ,,
     1.2     1.2
       0     410
     1.2     1.2
       0     410
Pier Skew, UpSta & Num, DnSta & Num=  ,1568, 2 ,1568, 2 , 0 , 0 , 0 ,,
     1.2     1.2
       0     410
     1.2     1.2
       0     410
Pier Skew, UpSta & Num, DnSta & Num=  ,1583, 2 ,1583, 2 , 0 , 0 , 0 ,,
     1.2     1.2
       0     410
     1.2     1.2
       0     410
Pier Skew, UpSta & Num, DnSta & Num=  ,1598, 2 ,1598, 2 , 0 , 0 , 0 ,,
     1.2     1.2
       0     410
     1.2     1.2
       0     410
Pier Skew, UpSta & Num, DnSta & Num=  ,1613, 2 ,1613, 2 , 0 , 0 , 0 ,,
     1.2     1.2
       0     410
     1.2     1.2
       0     410
Pier Skew, UpSta & Num, DnSta & Num=  ,1628, 2 ,1628, 2 , 0 , 0 , 0 ,,
     1.2     1.2
       0     410
     1.2     1.2
       0     410
Pier Skew, UpSta & Num, DnSta & Num=  ,1643, 2 ,1643, 2 , 0 , 0 , 0 ,,
     1.2     1.2
       0     410
     1.2     1.2
       0     410
Pier Skew, UpSta & Num, DnSta & Num=  ,1658, 2 ,1658, 2 , 0 , 0 , 0 ,,
     1.2     1.2
       0     410
     1.2     1.2
       0     410
Pier Skew, UpSta & Num, DnSta & Num=  ,1673, 2 ,1673, 2 , 0 , 0 , 0 ,,
     1.2     1.2
       0     410
     1.2     1.2
       0     410
Pier Skew, UpSta & Num, DnSta & Num=  ,1688, 2 ,1688, 2 , 0 , 0 , 0 ,,
     1.2     1.2
       0     410
     1.2     1.2
       0     410
Pier Skew, UpSta & Num, DnSta & Num=  ,1703, 2 ,1703, 2 , 0 , 0 , 0 ,,
     1.2     1.2
       0     410
     1.2     1.2
       0     410
Pier Skew, UpSta & Num, DnSta & Num=  ,1718, 2 ,1718, 2 , 0 , 0 , 0 ,,
     1.2     1.2
       0     410
     1.2     1.2
       0     410
Pier Skew, UpSta & Num, DnSta & Num=  ,1733, 2 ,1733, 2 , 0 , 0 , 0 ,,
     1.2     1.2
       0     410
     1.2     1.2
       0     410
Pier Skew, UpSta & Num, DnSta & Num=  ,1748, 2 ,1748, 2 , 0 , 0 , 0 ,,
     1.2     1.2
       0     410
     1.2     1.2
       0     410
Pier Skew, UpSta & Num, DnSta & Num=  ,1763, 2 ,1763, 2 , 0 , 0 , 0 ,,
     1.2     1.2
       0     410
     1.2     1.2
       0     410
Pier Skew, UpSta & Num, DnSta & Num=  ,1778, 2 ,1778, 2 , 0 , 0 , 0 ,,
     1.2     1.2
       0     410
     1.2     1.2
       0     410
Pier Skew, UpSta & Num, DnSta & Num=  ,1793, 2 ,1793, 2 , 0 , 0 , 0 ,,
     1.2     1.2
       0     410
     1.2     1.2
       0     410
Pier Skew, UpSta & Num, DnSta & Num=  ,1810, 2 ,1810, 2 , 0 , 0 , 0 ,,
     1.2     1.2
       0     410
     1.2     1.2
       0     410
Pier Skew, UpSta & Num, DnSta & Num=  ,1825, 2 ,1825, 2 , 0 , 0 , 0 ,,
     1.2     1.2
       0     410
     1.2     1.2
       0     410
Pier Skew, UpSta & Num, DnSta & Num=  ,1840, 2 ,1840, 2 , 0 , 0 , 0 ,,
     1.2     1.2
       0     410
     1.2     1.2
       0     410
Pier Skew, UpSta & Num, DnSta & Num=  ,1855, 2 ,1855, 2 , 0 , 0 , 0 ,,
     1.2     1.2
       0     410
     1.2     1.2
       0     410
Pier Skew, UpSta & Num, DnSta & Num=  ,1870, 2 ,1870, 2 , 0 , 0 , 0 ,,
     1.2     1.2
       0     410
     1.2     1.2
       0     410
Pier Skew, UpSta & Num, DnSta & Num=  ,1885, 2 ,1885, 2 , 0 , 0 , 0 ,,
     1.2     1.2
       0     410
     1.2     1.2
       0     410
Pier Skew, UpSta & Num, DnSta & Num=  ,1900, 2 ,1900, 2 , 0 , 0 , 0 ,,
     1.2     1.2
       0     410
     1.2     1.2
       0     410
Pier Skew, UpSta & Num, DnSta & Num=  ,1915, 2 ,1915, 2 , 0 , 0 , 0 ,,
     1.2     1.2
       0     410
     1.2     1.2
       0     410
Pier Skew, UpSta & Num, DnSta & Num=  ,1930, 2 ,1930, 2 , 0 , 0 , 0 ,,
     1.2     1.2
       0     410
     1.2     1.2
       0     410
Pier Skew, UpSta & Num, DnSta & Num=  ,1945, 2 ,1945, 2 , 0 , 0 , 0 ,,
     1.2     1.2
       0     410
     1.2     1.2
       0     410
Pier Skew, UpSta & Num, DnSta & Num=  ,1960, 2 ,1960, 2 , 0 , 0 , 0 ,,
     1.2     1.2
       0     410
     1.2     1.2
       0     410
Pier Skew, UpSta & Num, DnSta & Num=  ,1975, 2 ,1975, 2 , 0 , 0 , 0 ,,
     1.2     1.2
       0     410
     1.2     1.2
       0     410
Pier Skew, UpSta & Num, DnSta & Num=  ,1990, 2 ,1990, 2 , 0 , 0 , 0 ,,
     1.2     1.2
       0     410
     1.2     1.2
       0     410
Pier Skew, UpSta & Num, DnSta & Num=  ,2005, 2 ,2005, 2 , 0 , 0 , 0 ,,
     1.2     1.2
       0     410
     1.2     1.2
       0     410
Pier Skew, UpSta & Num, DnSta & Num=  ,2020, 2 ,2020, 2 , 0 , 0 , 0 ,,
     1.2     1.2
       0     410
     1.2     1.2
       0     410
Pier Skew, UpSta & Num, DnSta & Num=  ,2035, 2 ,2035, 2 , 0 , 0 , 0 ,,
     1.2     1.2
       0     410
     1.2     1.2
       0     410
Pier Skew, UpSta & Num, DnSta & Num=  ,2050, 2 ,2050, 2 , 0 , 0 , 0 ,,
     1.2     1.2
       0     410
     1.2     1.2
       0     410
Pier Skew, UpSta & Num, DnSta & Num=  ,2065, 2 ,2065, 2 , 0 , 0 , 0 ,,
     1.2     1.2
       0     410
     1.2     1.2
       0     410
Pier Skew, UpSta & Num, DnSta & Num=  ,2080, 2 ,2080, 2 , 0 , 0 , 0 ,,
     1.2     1.2
       0     410
     1.2     1.2
       0     410
Pier Skew, UpSta & Num, DnSta & Num=  ,2095, 2 ,2095, 2 , 0 , 0 , 0 ,,
     1.2     1.2
       0     410
     1.2     1.2
       0     410
Pier Skew, UpSta & Num, DnSta & Num=  ,2111, 2 ,2111, 2 , 0 , 0 , 0 ,,
     1.2     1.2
       0     410
     1.2     1.2
       0     410
Pier Skew, UpSta & Num, DnSta & Num=  ,2126, 2 ,2126, 2 , 0 , 0 , 0 ,,
     1.2     1.2
       0     410
     1.2     1.2
       0     410
Pier Skew, UpSta & Num, DnSta & Num=  ,2141, 2 ,2141, 2 , 0 , 0 , 0 ,,
     1.2     1.2
       0     410
     1.2     1.2
       0     410
Pier Skew, UpSta & Num, DnSta & Num=  ,2156, 2 ,2156, 2 , 0 , 0 , 0 ,,
     1.2     1.2
       0     410
     1.2     1.2
       0     410
Pier Skew, UpSta & Num, DnSta & Num=  ,2171, 2 ,2171, 2 , 0 , 0 , 0 ,,
     1.2     1.2
       0     410
     1.2     1.2
       0     410
Pier Skew, UpSta & Num, DnSta & Num=  ,2186, 2 ,2186, 2 , 0 , 0 , 0 ,,
     1.2     1.2
       0     410
     1.2     1.2
       0     410
Pier Skew, UpSta & Num, DnSta & Num=  ,2202, 2 ,2202, 2 , 0 , 0 , 0 ,,
     1.2     1.2
       0     410
     1.2     1.2
       0     410
Pier Skew, UpSta & Num, DnSta & Num=  ,2217, 2 ,2217, 2 , 0 , 0 , 0 ,,
     1.2     1.2
       0     410
     1.2     1.2
       0     410
Pier Skew, UpSta & Num, DnSta & Num=  ,2232, 2 ,2232, 2 , 0 , 0 , 0 ,,
     1.2     1.2
       0     410
     1.2     1.2
       0     410
Pier Skew, UpSta & Num, DnSta & Num=  ,2247, 2 ,2247, 2 , 0 , 0 , 0 ,,
     1.2     1.2
       0     410
     1.2     1.2
       0     410
Pier Skew, UpSta & Num, DnSta & Num=  ,2262, 2 ,2262, 2 , 0 , 0 , 0 ,,
     1.2     1.2
       0     410
     1.2     1.2
       0     410
Pier Skew, UpSta & Num, DnSta & Num=  ,2277, 2 ,2277, 2 , 0 , 0 , 0 ,,
     1.2     1.2
       0     410
     1.2     1.2
       0     410
Pier Skew, UpSta & Num, DnSta & Num=  ,2292, 2 ,2292, 2 , 0 , 0 , 0 ,,
     1.2     1.2
       0     410
     1.2     1.2
       0     410
Pier Skew, UpSta & Num, DnSta & Num=  ,2309, 2 ,2309, 2 , 0 , 0 , 0 ,,
     1.2     1.2
       0     410
     1.2     1.2
       0     410
Pier Skew, UpSta & Num, DnSta & Num=  ,2324, 2 ,2324, 2 , 0 , 0 , 0 ,,
     1.2     1.2
       0     410
     1.2     1.2
       0     410
Pier Skew, UpSta & Num, DnSta & Num=  ,2339, 2 ,2339, 2 , 0 , 0 , 0 ,,
     1.2     1.2
       0     410
     1.2     1.2
       0     410
Pier Skew, UpSta & Num, DnSta & Num=  ,2354, 2 ,2354, 2 , 0 , 0 , 0 ,,
     1.2     1.2
       0     410
     1.2     1.2
       0     410
Pier Skew, UpSta & Num, DnSta & Num=  ,2369, 2 ,2369, 2 , 0 , 0 , 0 ,,
     1.2     1.2
       0     410
     1.2     1.2
       0     410
Pier Skew, UpSta & Num, DnSta & Num=  ,2384, 2 ,2384, 2 , 0 , 0 , 0 ,,
     1.2     1.2
       0     410
     1.2     1.2
       0     410
Pier Skew, UpSta & Num, DnSta & Num=  ,2400, 2 ,2400, 2 , 0 , 0 , 0 ,,
     1.2     1.2
       0     410
     1.2     1.2
       0     410
Pier Skew, UpSta & Num, DnSta & Num=  ,2415, 2 ,2415, 2 , 0 , 0 , 0 ,,
     1.2     1.2
       0     410
     1.2     1.2
       0     410
Pier Skew, UpSta & Num, DnSta & Num=  ,2430, 2 ,2430, 2 , 0 , 0 , 0 ,,
     1.2     1.2
       0     410
     1.2     1.2
       0     410
Pier Skew, UpSta & Num, DnSta & Num=  ,2445, 2 ,2445, 2 , 0 , 0 , 0 ,,
     1.2     1.2
       0     410
     1.2     1.2
       0     410
Pier Skew, UpSta & Num, DnSta & Num=  ,2460, 2 ,2460, 2 , 0 , 0 , 0 ,,
     1.2     1.2
       0     410
     1.2     1.2
       0     410
Pier Skew, UpSta & Num, DnSta & Num=  ,2475, 2 ,2475, 2 , 0 , 0 , 0 ,,
     1.2     1.2
       0     410
     1.2     1.2
       0     410
Pier Skew, UpSta & Num, DnSta & Num=  ,2490, 2 ,2490, 2 , 0 , 0 , 0 ,,
     1.2     1.2
       0     410
     1.2     1.2
       0     410
Pier Skew, UpSta & Num, DnSta & Num=  ,2505, 2 ,2505, 2 , 0 , 0 , 0 ,,
     1.2     1.2
       0     410
     1.2     1.2
       0     410
Pier Skew, UpSta & Num, DnSta & Num=  ,2520, 2 ,2520, 2 , 0 , 0 , 0 ,,
     1.2     1.2
       0     410
     1.2     1.2
       0     410
Pier Skew, UpSta & Num, DnSta & Num=  ,2535, 2 ,2535, 2 , 0 , 0 , 0 ,,
     1.2     1.2
       0     410
     1.2     1.2
       0     410
Pier Skew, UpSta & Num, DnSta & Num=  ,2550, 2 ,2550, 2 , 0 , 0 , 0 ,,
     1.2     1.2
       0     410
     1.2     1.2
       0     410
Pier Skew, UpSta & Num, DnSta & Num=  ,2565, 2 ,2565, 2 , 0 , 0 , 0 ,,
     1.2     1.2
       0     410
     1.2     1.2
       0     410
Pier Skew, UpSta & Num, DnSta & Num=  ,2580, 2 ,2580, 2 , 0 , 0 , 0 ,,
     1.2     1.2
       0     410
     1.2     1.2
       0     410
Pier Skew, UpSta & Num, DnSta & Num=  ,2595, 2 ,2595, 2 , 0 , 0 , 0 ,,
     1.2     1.2
       0     410
     1.2     1.2
       0     410
Pier Skew, UpSta & Num, DnSta & Num=  ,2611, 2 ,2611, 2 , 0 , 0 , 0 ,,
     1.2     1.2
       0     410
     1.2     1.2
       0     410
Pier Skew, UpSta & Num, DnSta & Num=  ,2626, 2 ,2626, 2 , 0 , 0 , 0 ,,
     1.2     1.2
       0     410
     1.2     1.2
       0     410
Pier Skew, UpSta & Num, DnSta & Num=  ,2626, 2 ,2626, 2 , 0 , 0 , 0 ,,
     1.2     1.2
       0     410
     1.2     1.2
       0     410
Pier Skew, UpSta & Num, DnSta & Num=  ,2643, 2 ,2643, 2 , 0 , 0 , 0 ,,
     1.2     1.2
       0     410
     1.2     1.2
       0     410
Pier Skew, UpSta & Num, DnSta & Num=  ,2662, 2 ,2662, 2 , 0 , 0 , 0 ,,
       8       8
       0     410
       8       8
       0     410
Pier Skew, UpSta & Num, DnSta & Num=  ,2788, 2 ,2788, 2 , 0 , 0 , 0 ,,
       8       8
       0     410
       8       8
       0     410
Pier Skew, UpSta & Num, DnSta & Num=  ,2798, 2 ,2798, 2 , 0 , 0 , 0 ,,
     1.2     1.2
       0     410
     1.2     1.2
       0     410
Pier Skew, UpSta & Num, DnSta & Num=  ,2813, 2 ,2813, 2 , 0 , 0 , 0 ,,
     1.2     1.2
       0     410
     1.2     1.2
       0     410
Pier Skew, UpSta & Num, DnSta & Num=  ,2828, 2 ,2828, 2 , 0 , 0 , 0 ,,
     1.2     1.2
       0     410
     1.2     1.2
       0     410
Pier Skew, UpSta & Num, DnSta & Num=  ,2843, 2 ,2843, 2 , 0 , 0 , 0 ,,
     1.2     1.2
       0     410
     1.2     1.2
       0     410
Pier Skew, UpSta & Num, DnSta & Num=  ,2858, 2 ,2858, 2 , 0 , 0 , 0 ,,
     1.2     1.2
       0     410
     1.2     1.2
       0     410
Pier Skew, UpSta & Num, DnSta & Num=  ,2873, 2 ,2873, 2 , 0 , 0 , 0 ,,
       5       5
       0     410
       5       5
       0     410
Pier Skew, UpSta & Num, DnSta & Num=  ,2888, 2 ,2888, 2 , 0 , 0 , 0 ,,
     1.2     1.2
       0     410
     1.2     1.2
       0     410
Pier Skew, UpSta & Num, DnSta & Num=  ,2903, 2 ,2903, 2 , 0 , 0 , 0 ,,
     1.2     1.2
       0     410
     1.2     1.2
       0     410
Pier Skew, UpSta & Num, DnSta & Num=  ,2918, 2 ,2918, 2 , 0 , 0 , 0 ,,
     1.2     1.2
       0     410
     1.2     1.2
       0     410
Pier Skew, UpSta & Num, DnSta & Num=  ,2933, 2 ,2933, 2 , 0 , 0 , 0 ,,
     1.2     1.2
       0     410
     1.2     1.2
       0     410
Pier Skew, UpSta & Num, DnSta & Num=  ,2948, 2 ,2948, 2 , 0 , 0 , 0 ,,
     1.2     1.2
       0     410
     1.2     1.2
       0     410
Pier Skew, UpSta & Num, DnSta & Num=  ,2963, 2 ,2963, 2 , 0 , 0 , 0 ,,
     1.2     1.2
       0     410
     1.2     1.2
       0     410
Pier Skew, UpSta & Num, DnSta & Num=  ,2978, 2 ,2978, 2 , 0 , 0 , 0 ,,
     1.2     1.2
       0     410
     1.2     1.2
       0     410
Pier Skew, UpSta & Num, DnSta & Num=  ,2993, 2 ,2993, 2 , 0 , 0 , 0 ,,
     1.2     1.2
       0     410
     1.2     1.2
       0     410
Pier Skew, UpSta & Num, DnSta & Num=  ,3008, 2 ,3008, 2 , 0 , 0 , 0 ,,
     1.2     1.2
       0     410
     1.2     1.2
       0     410
Pier Skew, UpSta & Num, DnSta & Num=  ,3023, 2 ,3023, 2 , 0 , 0 , 0 ,,
     1.2     1.2
       0     410
     1.2     1.2
       0     410
Pier Skew, UpSta & Num, DnSta & Num=  ,3038, 2 ,3038, 2 , 0 , 0 , 0 ,,
     1.2     1.2
       0     410
     1.2     1.2
       0     410
Pier Skew, UpSta & Num, DnSta & Num=  ,3053, 2 ,3053, 2 , 0 , 0 , 0 ,,
     1.2     1.2
       0     410
     1.2     1.2
       0     410
Pier Skew, UpSta & Num, DnSta & Num=  ,3068, 2 ,3068, 2 , 0 , 0 , 0 ,,
     1.2     1.2
       0     410
     1.2     1.2
       0     410
Pier Skew, UpSta & Num, DnSta & Num=  ,3083, 2 ,3083, 2 , 0 , 0 , 0 ,,
     1.2     1.2
       0     410
     1.2     1.2
       0     410
Pier Skew, UpSta & Num, DnSta & Num=  ,3100, 2 ,3100, 2 , 0 , 0 , 0 ,,
     1.2     1.2
       0     410
     1.2     1.2
       0     410
Pier Skew, UpSta & Num, DnSta & Num=  ,3115, 2 ,3115, 2 , 0 , 0 , 0 ,,
     1.2     1.2
       0     410
     1.2     1.2
       0     410
Pier Skew, UpSta & Num, DnSta & Num=  ,3130, 2 ,3130, 2 , 0 , 0 , 0 ,,
     1.2     1.2
       0     410
     1.2     1.2
       0     410
Pier Skew, UpSta & Num, DnSta & Num=  ,3145, 2 ,3145, 2 , 0 , 0 , 0 ,,
     1.2     1.2
       0     410
     1.2     1.2
       0     410
Pier Skew, UpSta & Num, DnSta & Num=  ,3160, 2 ,3160, 2 , 0 , 0 , 0 ,,
     1.2     1.2
       0     410
     1.2     1.2
       0     410
Pier Skew, UpSta & Num, DnSta & Num=  ,3175, 2 ,3175, 2 , 0 , 0 , 0 ,,
     1.2     1.2
       0     410
     1.2     1.2
       0     410
Pier Skew, UpSta & Num, DnSta & Num=  ,3190, 2 ,3190, 2 , 0 , 0 , 0 ,,
     1.2     1.2
       0     410
     1.2     1.2
       0     410
Pier Skew, UpSta & Num, DnSta & Num=  ,3205, 2 ,3205, 2 , 0 , 0 , 0 ,,
     1.2     1.2
       0     410
     1.2     1.2
       0     410
Pier Skew, UpSta & Num, DnSta & Num=  ,3220, 2 ,3220, 2 , 0 , 0 , 0 ,,
     1.2     1.2
       0     410
     1.2     1.2
       0     410
Pier Skew, UpSta & Num, DnSta & Num=  ,3235, 2 ,3235, 2 , 0 , 0 , 0 ,,
     1.2     1.2
       0     410
     1.2     1.2
       0     410
Pier Skew, UpSta & Num, DnSta & Num=  ,3250, 2 ,3250, 2 , 0 , 0 , 0 ,,
     1.2     1.2
       0     410
     1.2     1.2
       0     410
Pier Skew, UpSta & Num, DnSta & Num=  ,3265, 2 ,3265, 2 , 0 , 0 , 0 ,,
       3       3
       0     410
       3       3
       0     410
Pier Skew, UpSta & Num, DnSta & Num=  ,3295, 2 ,3295, 2 , 0 , 0 , 0 ,,
       3       3
       0     410
       3       3
       0     410
Pier Skew, UpSta & Num, DnSta & Num=  ,3310, 2 ,3310, 2 , 0 , 0 , 0 ,,
     1.2     1.2
       0     410
     1.2     1.2
       0     410
Pier Skew, UpSta & Num, DnSta & Num=  ,3325, 2 ,3325, 2 , 0 , 0 , 0 ,,
     1.2     1.2
       0     410
     1.2     1.2
       0     410
Pier Skew, UpSta & Num, DnSta & Num=  ,3340, 2 ,3340, 2 , 0 , 0 , 0 ,,
     1.2     1.2
       0     410
     1.2     1.2
       0     410
Pier Skew, UpSta & Num, DnSta & Num=  ,3355, 2 ,3355, 2 , 0 , 0 , 0 ,,
     1.2     1.2
       0     410
     1.2     1.2
       0     410
Pier Skew, UpSta & Num, DnSta & Num=  ,3370, 2 ,3370, 2 , 0 , 0 , 0 ,,
     1.2     1.2
       0     410
     1.2     1.2
       0     410
Pier Skew, UpSta & Num, DnSta & Num=  ,3385, 2 ,3385, 2 , 0 , 0 , 0 ,,
     1.2     1.2
       0     410
     1.2     1.2
       0     410
Pier Skew, UpSta & Num, DnSta & Num=  ,3400, 2 ,3400, 2 , 0 , 0 , 0 ,,
     1.2     1.2
       0     410
     1.2     1.2
       0     410
Pier Skew, UpSta & Num, DnSta & Num=  ,3415, 2 ,3415, 2 , 0 , 0 , 0 ,,
     1.2     1.2
       0     410
     1.2     1.2
       0     410
Pier Skew, UpSta & Num, DnSta & Num=  ,3430, 2 ,3430, 2 , 0 , 0 , 0 ,,
     1.2     1.2
       0     410
     1.2     1.2
       0     410
Pier Skew, UpSta & Num, DnSta & Num=  ,3445, 2 ,3445, 2 , 0 , 0 , 0 ,,
     1.2     1.2
       0     410
     1.2     1.2
       0     410
Pier Skew, UpSta & Num, DnSta & Num=  ,3460, 2 ,3460, 2 , 0 , 0 , 0 ,,
     1.2     1.2
       0     410
     1.2     1.2
       0     410
Pier Skew, UpSta & Num, DnSta & Num=  ,3475, 2 ,3475, 2 , 0 , 0 , 0 ,,
     1.2     1.2
       0     410
     1.2     1.2
       0     410
Pier Skew, UpSta & Num, DnSta & Num=  ,3490, 2 ,3490, 2 , 0 , 0 , 0 ,,
     1.2     1.2
       0     410
     1.2     1.2
       0     410
Pier Skew, UpSta & Num, DnSta & Num=  ,3505, 2 ,3505, 2 , 0 , 0 , 0 ,,
     1.2     1.2
       0     410
     1.2     1.2
       0     410
Pier Skew, UpSta & Num, DnSta & Num=  ,3520, 2 ,3520, 2 , 0 , 0 , 0 ,,
     1.2     1.2
       0     410
     1.2     1.2
       0     410
Pier Skew, UpSta & Num, DnSta & Num=  ,3535, 2 ,3535, 2 , 0 , 0 , 0 ,,
     1.2     1.2
       0     410
     1.2     1.2
       0     410
Pier Skew, UpSta & Num, DnSta & Num=  ,3550, 2 ,3550, 2 , 0 , 0 , 0 ,,
     1.2     1.2
       0     410
     1.2     1.2
       0     410
Pier Skew, UpSta & Num, DnSta & Num=  ,3565, 2 ,3565, 2 , 0 , 0 , 0 ,,
     1.2     1.2
       0     410
     1.2     1.2
       0     410
Pier Skew, UpSta & Num, DnSta & Num=  ,3580, 2 ,3580, 2 , 0 , 0 , 0 ,,
     1.2     1.2
       0     410
     1.2     1.2
       0     410
Pier Skew, UpSta & Num, DnSta & Num=  ,3595, 2 ,3595, 2 , 0 , 0 , 0 ,,
     1.2     1.2
       0     410
     1.2     1.2
       0     410
Pier Skew, UpSta & Num, DnSta & Num=  ,3610, 2 ,3610, 2 , 0 , 0 , 0 ,,
     1.2     1.2
       0     410
     1.2     1.2
       0     410
Pier Skew, UpSta & Num, DnSta & Num=  ,3625, 2 ,3625, 2 , 0 , 0 , 0 ,,
     1.2     1.2
       0     410
     1.2     1.2
       0     410
Pier Skew, UpSta & Num, DnSta & Num=  ,3640, 2 ,3640, 2 , 0 , 0 , 0 ,,
     1.2     1.2
       0     410
     1.2     1.2
       0     410
Pier Skew, UpSta & Num, DnSta & Num=  ,3655, 2 ,3655, 2 , 0 , 0 , 0 ,,
     1.2     1.2
       0     410
     1.2     1.2
       0     410
Pier Skew, UpSta & Num, DnSta & Num=  ,3670, 2 ,3670, 2 , 0 , 0 , 0 ,,
     1.2     1.2
       0     410
     1.2     1.2
       0     410
Pier Skew, UpSta & Num, DnSta & Num=  ,3685, 2 ,3685, 2 , 0 , 0 , 0 ,,
       3       3
       0     410
       3       3
       0     410
Pier Skew, UpSta & Num, DnSta & Num=  ,3715, 2 ,3715, 2 , 0 , 0 , 0 ,,
       3       3
       0     410
       3       3
       0     410
Pier Skew, UpSta & Num, DnSta & Num=  ,3730, 2 ,3730, 2 , 0 , 0 , 0 ,,
     1.2     1.2
       0     410
     1.2     1.2
       0     410
Pier Skew, UpSta & Num, DnSta & Num=  ,3745, 2 ,3745, 2 , 0 , 0 , 0 ,,
     1.2     1.2
       0     410
     1.2     1.2
       0     410
Pier Skew, UpSta & Num, DnSta & Num=  ,3760, 2 ,3760, 2 , 0 , 0 , 0 ,,
     1.2     1.2
       0     410
     1.2     1.2
       0     410
Pier Skew, UpSta & Num, DnSta & Num=  ,3775, 2 ,3775, 2 , 0 , 0 , 0 ,,
     1.2     1.2
       0     410
     1.2     1.2
       0     410
Pier Skew, UpSta & Num, DnSta & Num=  ,3790, 2 ,3790, 2 , 0 , 0 , 0 ,,
     1.2     1.2
       0     410
     1.2     1.2
       0     410
Pier Skew, UpSta & Num, DnSta & Num=  ,3805, 2 ,3805, 2 , 0 , 0 , 0 ,,
     1.2     1.2
       0     410
     1.2     1.2
       0     410
Pier Skew, UpSta & Num, DnSta & Num=  ,3820, 2 ,3820, 2 , 0 , 0 , 0 ,,
     1.2     1.2
       0     410
     1.2     1.2
       0     410
Pier Skew, UpSta & Num, DnSta & Num=  ,3835, 2 ,3835, 2 , 0 , 0 , 0 ,,
     1.2     1.2
       0     410
     1.2     1.2
       0     410
Pier Skew, UpSta & Num, DnSta & Num=  ,3850, 2 ,3850, 2 , 0 , 0 , 0 ,,
     1.2     1.2
       0     410
     1.2     1.2
       0     410
Pier Skew, UpSta & Num, DnSta & Num=  ,3865, 2 ,3865, 2 , 0 , 0 , 0 ,,
     1.2     1.2
       0     410
     1.2     1.2
       0     410
Pier Skew, UpSta & Num, DnSta & Num=  ,3880, 2 ,3880, 2 , 0 , 0 , 0 ,,
     1.2     1.2
       0     410
     1.2     1.2
       0     410
Pier Skew, UpSta & Num, DnSta & Num=  ,3895, 2 ,3895, 2 , 0 , 0 , 0 ,,
     1.2     1.2
       0     410
     1.2     1.2
       0     410
Pier Skew, UpSta & Num, DnSta & Num=  ,3910, 2 ,3910, 2 , 0 , 0 , 0 ,,
       3       3
       0     410
       3       3
       0     410
Pier Skew, UpSta & Num, DnSta & Num=  ,3926, 2 ,3926, 2 , 0 , 0 , 0 ,,
     1.2     1.2
       0     410
     1.2     1.2
       0     410
Pier Skew, UpSta & Num, DnSta & Num=  ,3941, 2 ,3941, 2 , 0 , 0 , 0 ,,
     1.2     1.2
       0     410
     1.2     1.2
       0     410
Pier Skew, UpSta & Num, DnSta & Num=  ,3956, 2 ,3956, 2 , 0 , 0 , 0 ,,
     1.2     1.2
       0     410
     1.2     1.2
       0     410
Pier Skew, UpSta & Num, DnSta & Num=  ,3971, 2 ,3971, 2 , 0 , 0 , 0 ,,
     1.2     1.2
       0     410
     1.2     1.2
       0     410
Pier Skew, UpSta & Num, DnSta & Num=  ,3986, 2 ,3986, 2 , 0 , 0 , 0 ,,
     1.2     1.2
       0     410
     1.2     1.2
       0     410
Pier Skew, UpSta & Num, DnSta & Num=  ,4001, 2 ,4001, 2 , 0 , 0 , 0 ,,
     1.2     1.2
       0     410
     1.2     1.2
       0     410
Pier Skew, UpSta & Num, DnSta & Num=  ,4016, 2 ,4016, 2 , 0 , 0 , 0 ,,
     1.2     1.2
       0     410
     1.2     1.2
       0     410
Pier Skew, UpSta & Num, DnSta & Num=  ,4031, 2 ,4031, 2 , 0 , 0 , 0 ,,
     1.2     1.2
       0     410
     1.2     1.2
       0     410
Pier Skew, UpSta & Num, DnSta & Num=  ,4046, 2 ,4046, 2 , 0 , 0 , 0 ,,
     1.2     1.2
       0     410
     1.2     1.2
       0     410
Pier Skew, UpSta & Num, DnSta & Num=  ,4061, 2 ,4061, 2 , 0 , 0 , 0 ,,
     1.2     1.2
       0     410
     1.2     1.2
       0     410
Pier Skew, UpSta & Num, DnSta & Num=  ,4076, 2 ,4076, 2 , 0 , 0 , 0 ,,
     1.2     1.2
       0     410
     1.2     1.2
       0     410
Pier Skew, UpSta & Num, DnSta & Num=  ,4091, 2 ,4091, 2 , 0 , 0 , 0 ,,
     1.2     1.2
       0     410
     1.2     1.2
       0     410
BR Coef= 1 , 1 , 1 ,2.5, 0 ,,,0.8,0,1.2,2,
WSPro=,,,, 1 ,,,, 0 ,,,, 0 ,,,,-1 ,-1 ,-1 , 0 , 0 , 0 , 0 , 0
BC Design=,, 0 ,, 0 ,,,,,,
BC HTab HWMax=419
BC Use User HTab Curves=0
BC User HTab FreeFlow(D)= 0

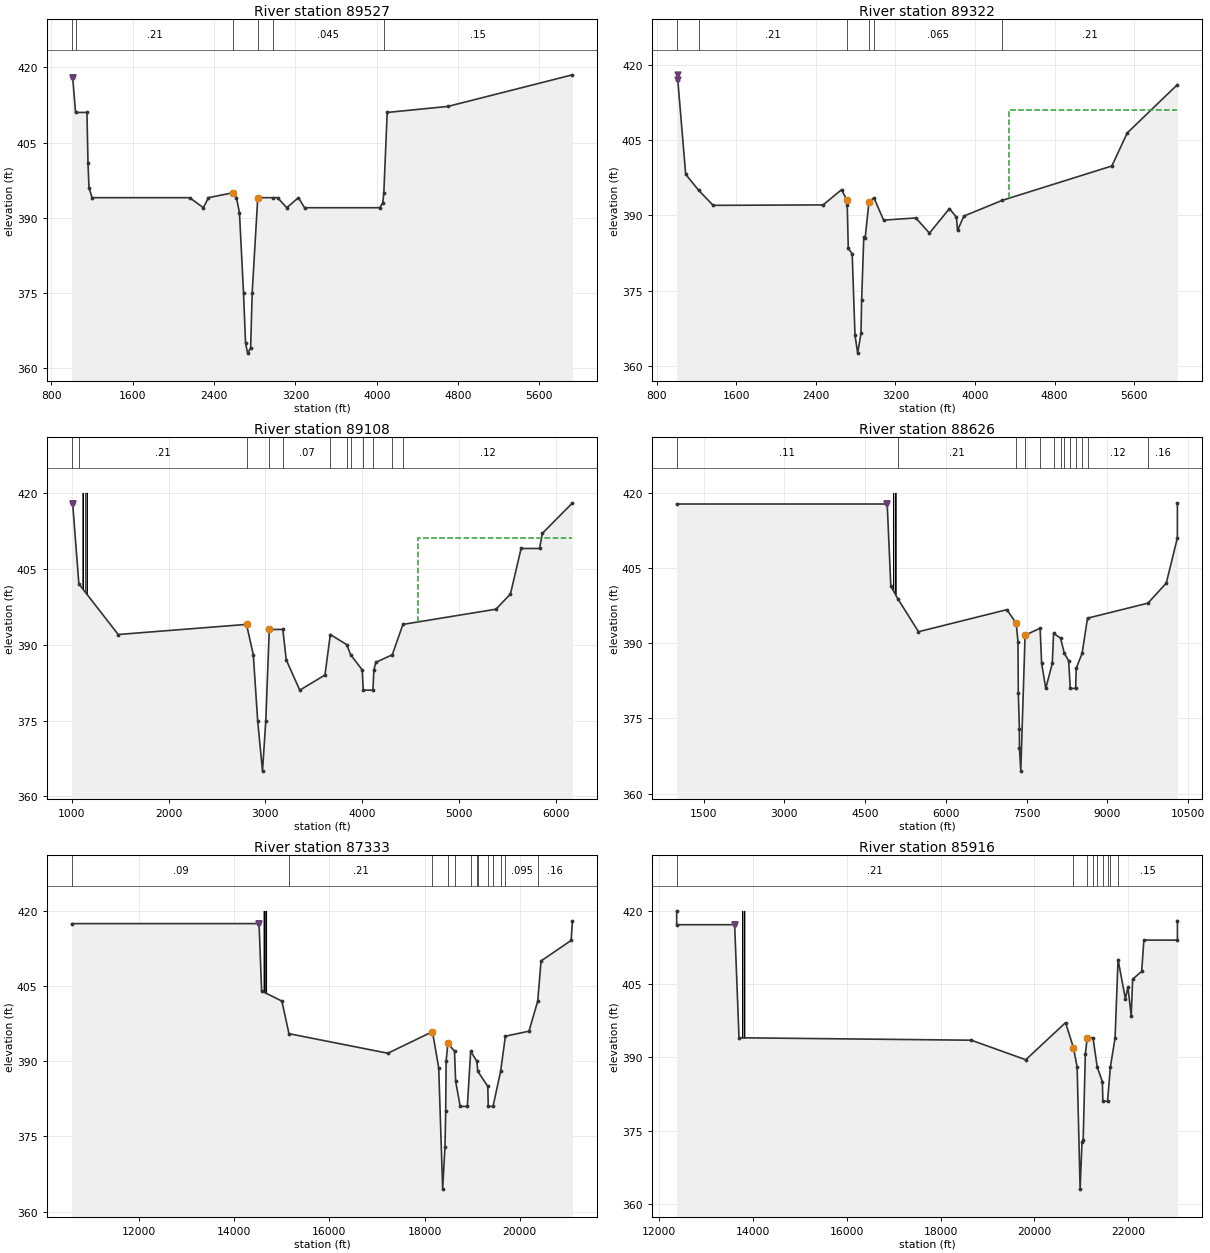
Type RM Length L Ch R = 1 ,89527   ,254,188,105
BEGIN DESCRIPTION:
Downstream bounding cross-section for Union Pacific Railroad bridge.
Rochester Park Levee in LOB.
END DESCRIPTION:
XS GIS Cut Line= 5
  2504790.695573 6954080.5371879 2505087.9743136 6952390.5865946
 2505561.5337952 6949575.3636321 2505618.8871131 6949234.4088337
 2505620.3106879 6949225.9459464
#Sta/Elev= 30
    1000   417.9    1010   417.9    1038     411    1150     411    1160     401
    1170     396    1200     394    2160     394    2295     392    2345     394
    2590     395    2620     394    2650     391    2690     375    2710     365
    2730     363    2760     364    2775     375    2830     394    2980     394
    3025     394    3115     392    3230     394    3290     392    4030     392
    4060     393    4070     395    4103     411    4700   412.2    5925   418.5
#Mann= 6 ,-1,0
    1000    .035       0    1038     .21       0    2590     .07       0
    2830     .21       0    2980    .045       0    4070     .15       0
Levee=-1,1010,417.92,0,,,,
Bank Sta=2590,2830
XS Rating Curve= 0 ,0
Exp/Cntr=0.5,0.3

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
Type RM Length L Ch R = 1 ,89322   ,208,214,220
BEGIN DESCRIPTION:
Cross-section added for potential Trinity Trails project.
Rochester Park Levee in LOB.
END DESCRIPTION:
XS GIS Cut Line= 6
2505048.149261816954167.582918252505049.585296466954157.67519057
2505299.640679596952432.451361772505304.006714866952401.44862268
2505288.048330156952185.683059992505787.692424756949201.73735177
#Sta/Elev= 30
    1000     417  1010.7     417 1090.51  398.17 1219.84  395.02  1366.4     392
 2472.41  392.09 2658.63  395.13 2711.42     393 2715.05     392 2725.34  383.49
 2764.68  382.34    2793  366.15    2820  362.62    2853  366.55 2859.76  373.26
 2881.22  385.64 2894.71  385.43 2933.56  392.74 2983.34   393.5 3080.52  389.06
 3404.22   389.5 3541.44  386.48 3742.38  391.35 3813.08  389.65  3823.9  387.02
 3887.88  389.87  4272.8  392.99 5375.83  399.83 5530.09  406.39 6034.93     416
#Mann= 6 ,-1,0
    1000    .035       0 1219.84     .21       0 2715.05     .07       0
 2933.56     .21       0 2983.34    .065       0  4272.8     .21       0
Levee=-1,1010,417.95,0,,,,
#XS Ineff= 2 , 0
                            4338             411
Permanent Ineff=
       F       F
Bank Sta=2711.42,2933.56
XS Rating Curve= 0 ,0
Exp/Cntr=0.3,0.1

Type RM Length L Ch R = 1 ,89108   ,460,482,330
BEGIN DESCRIPTION:
Wetland Cell F in ROB (two cells).
Rochester Park Levee in LOB.
18' Oncor tower as blocked obstruction Sta 1140 to 1158.  Tower 140' from top of levee.
Proposed 4' pole.
END DESCRIPTION:
XS GIS Cut Line= 6
  2505331.491933 6954282.5950276 2505332.6067196 6954272.3703058
  2505530.209316 6952459.9759971 2505449.9986008 6952244.4938513
 2505958.6719026 6949190.1942422 2505960.3615805 6949180.0486682
#Sta/Elev= 30
    1000  417.88    1010  417.88    1074     402    1480     392    2805     394
    2875     388    2920     375    2970     365    3004     375    3040     393
    3180     393    3215     387    3355     381    3615     384    3670     392
    3840     390    3880     388    4000     385    4010     381    4110     381
    4120     385    4140   386.5    4310     388    4420     394    5380     397
    5530     400    5640     409    5830     409    5860     412    6170     418
#Mann= 12 ,-1,0
    1000    .035       0    1074     .21       0    2805     .07       0
    3040     .21       0    3180     .07       0    3670     .15       0
    3840    .035       0    3880    .045       0    4010    .025       0
    4110    .045       0    4310    .035       0    4420     .12       0
Levee=-1,1010,417.88,0,,,,
#XS Ineff= 2 , 0
                            4580             411
Permanent Ineff=
       F       F
#Block Obstruct= 2 ,-1
    1111    1115     420    1140    1158     420
Bank Sta=2805,3040
XS Rating Curve= 0 ,0
Exp/Cntr=0.3,0.1

Type RM Length L Ch R = 1 ,88626   ,1180,1293,1150
BEGIN DESCRIPTION:
Wetland Cell F in ROB (two cells).
Rochester Park Levee in LOB.
Added 18' Oncor tower as blocked obstruction Sta 5050 to 5068.  Tower 140' from top of levee.
Proposed 3.5' pole.
END DESCRIPTION:
XS GIS Cut Line= 6
   2505705.22259 6958436.1860613 2505705.4837812 6958429.2594519
        2505942.        6952157.        2505800.        6952009.
 2506018.5163723 6949213.2116173 2506019.0564875 6949206.3011606
#Sta/Elev= 30
    1000  417.77    4910  417.77    4977   401.4  5105.5   398.9  5491.1   392.3
  7132.4   396.7  7305.3     394  7338.9   390.3    7345     380    7365     373
    7366   369.2    7391   364.5  7470.5   391.6    7750     393    7778     386
    7855     381    7976     386    8000     392    8130     391    8200     388
    8280   386.5    8310     381    8410     381    8420     385    8530     388
    8630     395  9752.5     398 10093.1     402   10299     411   10300     418
#Mann= 13 ,-1,0
    1000     .11       0  5105.5     .21       0  7305.3     .07       0
  7470.5     .21       0    7750     .07       0    8000     .15       0
    8130    .035       0    8200    .045       0    8310    .025       0
    8410    .045       0    8530    .035       0    8630     .12       0
  9752.5     .16       0
Levee=-1,4910,417.77,0,,,,
#Block Obstruct= 2 ,-1
  5016.5    5020     420    5050    5068     420
Bank Sta=7305.3,7470.5
XS Rating Curve= 0 ,0
Exp/Cntr=0.5,0.3

Type RM Length L Ch R = 1 ,87333   ,1530,1417,1000
BEGIN DESCRIPTION:
Wetland Cell F in ROB (two cells).
Rochester Park Levee in LOB.
18' Oncor tower as blocked obstruction Sta 14650 to 14668.  Tower 130' from top of levee.
Proposed 3.5' pole.
END DESCRIPTION:
XS GIS Cut Line= 4
  2507107.332408 6959228.2576903        2507025.        6951583.
        2506956.        6951433. 2506945.2883792 6948713.8311526
#Sta/Elev= 30
   10580  417.45   14520  417.45   14574     404   15000     402 15149.1   395.5
 17228.7   391.6 18166.4   395.9 18297.9   388.7   18381   364.5   18430     373
   18445     380 18453.5     390 18490.3   393.6   18630     392   18654     386
   18750     381   18900     381   18970     392   19100     390   19120     388
   19330     385   19340     381   19440     381   19600     388   19700     395
 20196.4     396   20380     402   20450     410 21082.5   414.1   21110     418
#Mann= 13 ,-1,0
   10580     .09       0 15149.1     .21       0 18166.4    .065       0
 18490.3     .21       0   18630     .07       0   18970     .15       0
   19100    .035       0   19120    .045       0   19340    .025       0
   19440    .045       0   19600    .035       0   19700    .095       0
   20380     .16       0
Levee=-1,14520,417.45,0,,,,
#Block Obstruct= 2 ,-1
 14616.5   14620     420   14650   14668     420
Bank Sta=18166.4,18490.3
XS Rating Curve= 0 ,0
Exp/Cntr=0.3,0.1

Type RM Length L Ch R = 1 ,85916   ,1670,1258,1000
BEGIN DESCRIPTION:
Wetland Cell F in ROB.
Rochester Park Levee in LOB.
18' Oncor tower as blocked obstruction Sta 13798 to 13816.  Tower 190' from top of levee.
Proposed 3.5' pole.
END DESCRIPTION:
XS GIS Cut Line= 3
  2509712.398053 6959105.6805302        2507902.        6950111.
 2507525.1606229 6948656.0754308
#Sta/Elev= 30
   12372     420   12372  417.16   13608  417.16   13701     394 18654.9   393.5
 19815.7   389.5 20664.6   397.1 20831.6     392 20911.6     388   20975     363
   21015   372.6   21040     373 21086.2   390.6 21125.7     394   21250     394
   21340     388   21450     385   21460     381   21560     381   21620     388
   21720   393.9   21784     410 21940.6     402 21994.6   404.4 22064.5   398.5
 22095.6     406   22288   407.6 22334.4     414   23050     414   23050     418
#Mann= 9 ,-1,0
   12372     .21       0 20831.6    .065       0 21125.7     .15       0
   21250    .035       0   21340    .045       0   21460    .025       0
   21560    .045       0   21620    .035       0   21784     .15       0
Levee=-1,13608,417.15,0,,,,
#Block Obstruct= 2 ,-1
 13764.5   13768     420   13798   13816     420
Bank Sta=20831.6,21125.7
XS Rating Curve= 0 ,0
Exp/Cntr=0.3,0.1

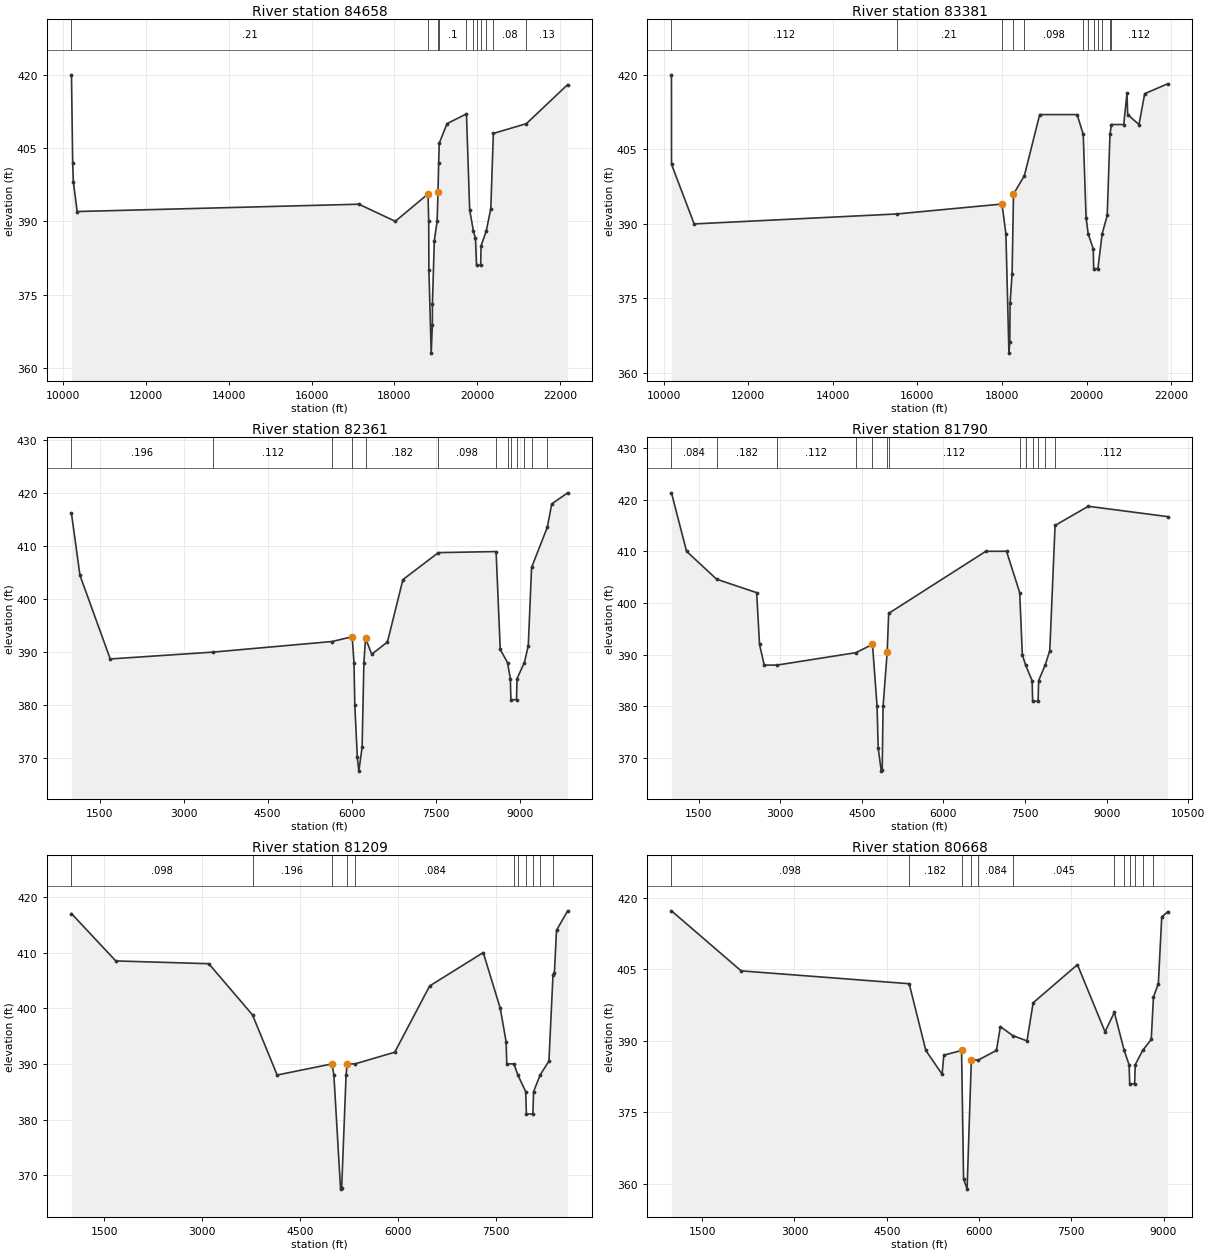
Type RM Length L Ch R = 1 ,84658   ,1500,1277,800
BEGIN DESCRIPTION:
Wetland Cell F in ROB.
END DESCRIPTION:
XS GIS Cut Line= 6
  2512884.335947 6958745.3001276        2509281.        6950942.
        2509219.        6950639.        2508472.        6949424.
        2507922.        6948535. 2507594.3593325  6948019.288756
#Sta/Elev= 30
   10200     420 10229.1     402 10245.2   398.1 10337.1     392 17143.5   393.5
 18021.9     390 18812.8   395.6   18830     390   18835     380   18890     363
   18918   368.7   18920     373   18965     386 19033.3     390 19054.3     396
 19070.9     402 19084.8     406   19273     410   19742     412   19820   392.3
   19910     388   19960   386.5   19985     381   20085     381   20095     385
   20220     388   20330   392.6   20392     408   21190     410   22187     418
#Mann= 11 ,-1,0
   10200     .21       0 18812.8     .06       0 19054.3     .17       0
 19070.9      .1       0   19742    .035       0   19910    .045       0
   19985    .025       0   20085    .045       0   20220    .035       0
   20392     .08       0   21190     .13       0
Bank Sta=18812.8,19054.3
XS Rating Curve= 0 ,0
Exp/Cntr=0.3,0.1

Type RM Length L Ch R = 1 ,83381   ,1350,1020,570
BEGIN DESCRIPTION:
Wetland Cell F in ROB.
END DESCRIPTION:
XS GIS Cut Line= 5
  2515317.839514 6957162.9241671        2510528.        6951068.
        2510512.        6950768.        2509167.        6949432.
 2507897.9988701 6948169.5774308
#Sta/Elev= 30
   10182     420 10182.9     402 10718.5     390   15510     392 18001.2     394
 18093.5     388   18165     364   18185   366.2   18192     374   18240     380
   18273     396   18530   399.7 18892.8     412   19779     412   19923     408
   19990   391.2   20040     388   20160     385   20170     381   20270     381
   20370     388   20490   391.7   20555     408   20590     410 20881.3     410
 20957.7   416.3 20974.2     412 21241.8     410 21376.8   416.2   21920   418.2
#Mann= 12 ,-1,0
   10182    .112       0   15510     .21       0 18001.2     .06       0
   18273    .182       0   18530    .098       0   19923    .035       0
   20040    .045       0   20170    .025       0   20270    .045       0
   20370    .035       0   20555    .098       0   20590    .112       0
Bank Sta=18001.2,18273
XS Rating Curve= 0 ,0
Exp/Cntr=0.3,0.1

Type RM Length L Ch R = 1 ,82361   ,700,571,380
BEGIN DESCRIPTION:
White Rock Creek.
Wetland Cell F in ROB.
END DESCRIPTION:
Node Name=White Rock Creek
XS GIS Cut Line= 6
  2515786.668526 6953353.7840178        2515771.        6953354.
        2514973.        6953365.        2509760.        6949431.
 2508571.3822722 6948528.2770229  2508558.903231  6948518.799529
#Sta/Elev= 30
    1000   416.2  1151.7   404.5  1691.6   388.7    3530     390  5649.7     392
  6008.3   392.9  6040.2     388    6055     380    6100   370.1    6127   367.5
    6185     372  6217.3     388  6246.3   392.6  6357.4   389.6  6636.9   391.9
  6913.6   403.7  7546.4   408.8    8576     409    8650   390.5    8780     388
    8830     385    8840     381    8940     381    8950     385    9080     388
    9150   391.2    9209     406    9490   413.6  9568.3     418  9852.8   420.1
#Mann= 13 ,-1,0
    1000    .196       0    3530    .112       0  5649.7    .182       0
  6008.3     .06       0  6246.3    .182       0  7546.4    .098       0
    8576    .035       0    8780    .045       0    8840    .025       0
    8940    .045       0    9080    .035       0    9209    .098       0
    9490     .14       0
Bank Sta=6008.3,6246.3
XS Rating Curve= 0 ,0
Exp/Cntr=0.3,0.1

Type RM Length L Ch R = 1 ,81790   ,750,581,400
BEGIN DESCRIPTION:
Wetland Cell F in ROB.
END DESCRIPTION:
XS GIS Cut Line= 4
  2515199.837501 6952326.9028968        2510357.        6949433.
        2507936.        6947970. 2507378.1620416 6947633.0978639
#Sta/Elev= 30
    1000   421.3    1277     410    1830   404.6  2566.3     402  2618.7     392
    2705     388    2940     388    4390   390.4  4695.6     392    4780     380
    4800     372    4857   367.5    4874   367.7    4890     380  4965.7   390.5
    4993     398    6780     410    7160     410    7402     402    7450     390
    7510     388    7630     385    7640     381    7740     381    7750     385
    7870     388    7955   390.8    8052     415    8663   418.7   10122   416.7
#Mann= 13 ,-1,0
    1000    .084       0    1830    .182       0    2940    .112       0
    4390    .182       0  4695.6     .06       0  4965.7    .196       0
    4993    .112       0    7402    .035       0    7510    .045       0
    7640    .025       0    7740    .045       0    7870    .035       0
    8052    .112       0
Bank Sta=4695.6,4965.7
XS Rating Curve= 0 ,0
Exp/Cntr=0.3,0.1

Type RM Length L Ch R = 1 ,81209   ,650,541,318
BEGIN DESCRIPTION:
Cross-section modified for Trinity Trails project.
Wetland Cell F in ROB.
END DESCRIPTION:
XS GIS Cut Line= 5
  2515997.261884 6951544.6471384        2515989.        6951541.
        2511216.        6949434. 2509064.6370308 6948472.7023868
 2509056.3916502 6948469.0180877
#Sta/Elev= 30
    1000     417  1677.9   408.5  3100.8     408    3770   398.8    4147     388
  4985.3     390  5014.8     388    5117   367.5    5134   367.7  5201.4     388
  5218.1     390  5338.1     390  5946.2   392.1    6480     404    7300     410
    7560     400    7650     394    7660     390    7770     390    7830     388
    7950     385    7960     381    8060     381    8070     385    8170     388
    8305   390.5    8367   405.9    8389   406.4  8421.1     414  8591.8   417.5
#Mann= 11 ,-1,0
    1000    .098       0    3770    .196       0  4985.3     .06       0
  5218.1    .182       0  5338.1    .084       0    7770    .035       0
    7830    .045       0    7960    .025       0    8060    .045       0
    8170    .035       0    8367    .084       0
#XS Ineff= 2 , 0
          4985.3     390  5218.1             390
Permanent Ineff=
       F       F
Bank Sta=4985.3,5218.1
XS Rating Curve= 0 ,0
Exp/Cntr=0.3,0.1

Type RM Length L Ch R = 1 ,80668   ,15,14,15
BEGIN DESCRIPTION:
Cross-section added for Trinity Trails project.
Wetland Cell F in ROB.
END DESCRIPTION:
XS GIS Cut Line= 3
  2516821.906244 6950714.6194535        2512685.        6949454.
 2509100.3511303 6948379.2935477
#Sta/Elev= 30
    1000   417.3  2132.5   404.7  4864.4     402 5135.34     388 5400.11     383
 5427.57     387  5716.5     388    5749  361.07    5806  358.89 5875.17     386
 5990.52     386 6283.35     388 6347.62     393  6547.7  391.12  6780.2     390
    6880     398    7600     406  8049.3   391.9    8200     396    8360     388
    8440     385    8450     381    8530     381    8540     385    8660     388
    8800   390.3    8836   399.2  8915.3     402  8970.8     416    9067   417.1
#Mann= 12 ,-1,0
    1000    .098       0  4864.4    .182       0  5716.5     .06       0
 5875.17    .182       0 5990.52    .084       0  6547.7    .045       0
    8200    .035       0    8360    .045       0    8450    .025       0
    8530    .045       0    8660    .035       0    8836    .084       0
Bank Sta=5716.5,5875.17
XS Rating Curve= 0 ,0
Exp/Cntr=0.3,0.1