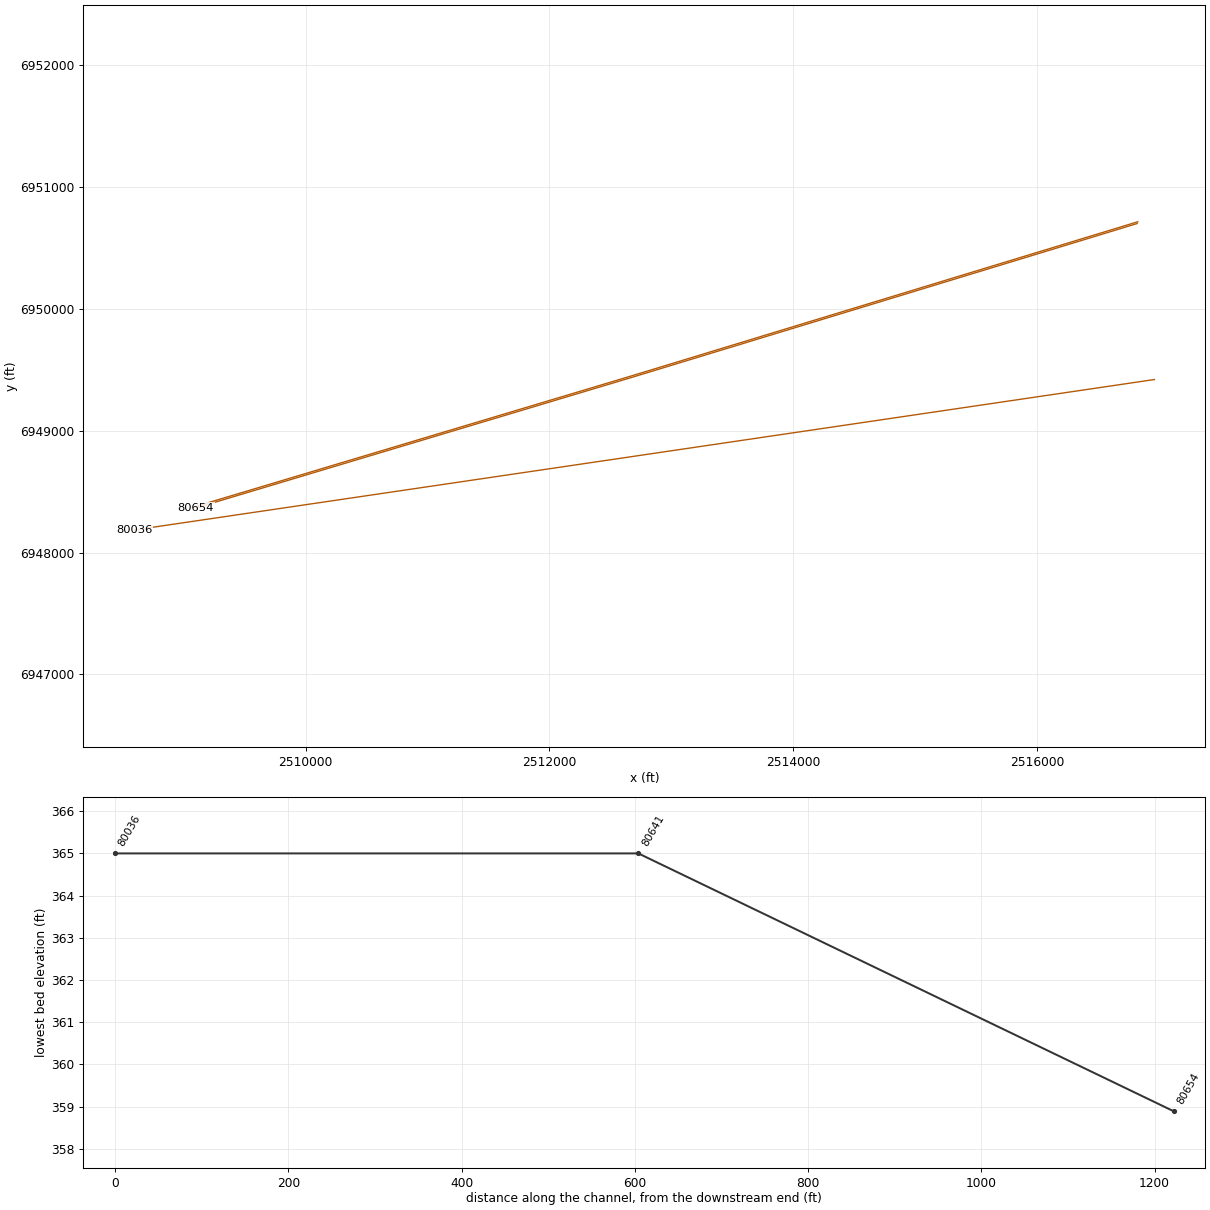
HEC-RAS study CDC_Consolidated_Model.prj: Upper Trinity CDC Consolidated Model

--- CDC_Consolidated_Model.g13 (geometry) --- (continued)

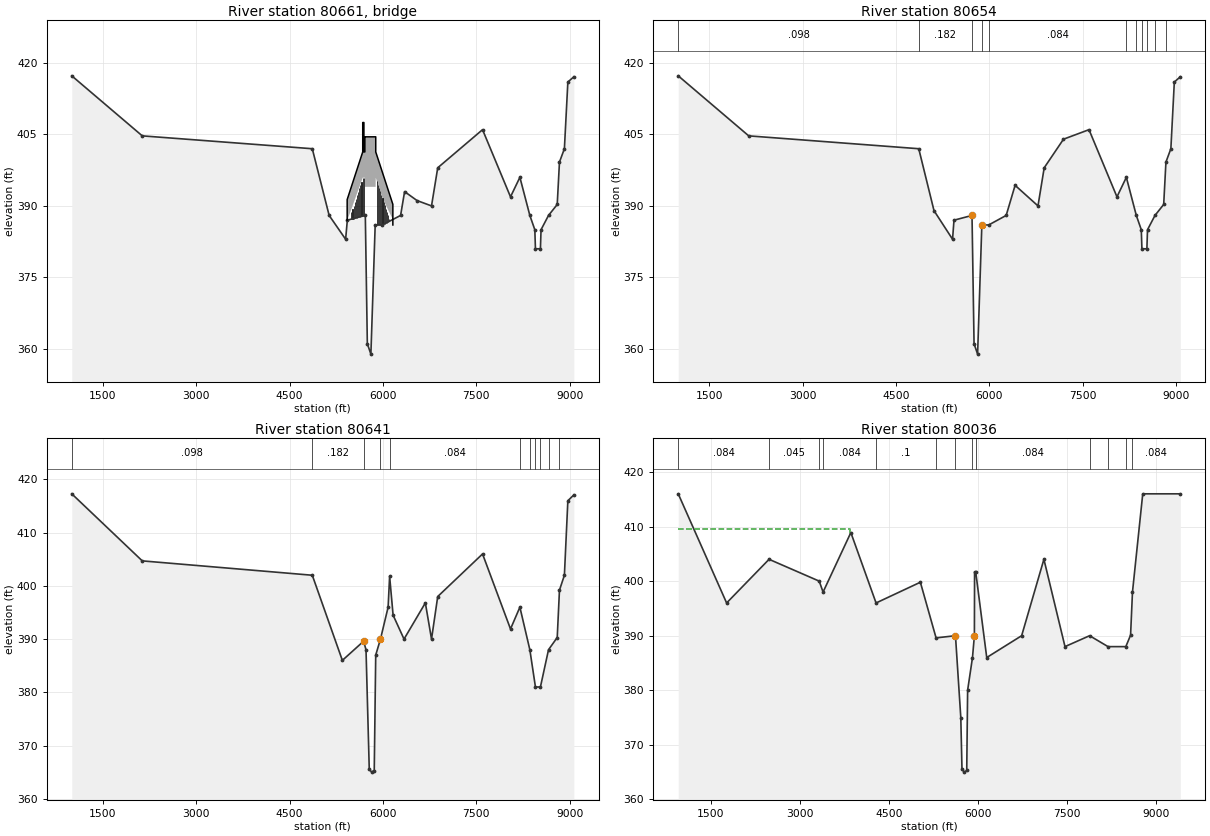
Type RM Length L Ch R = 3 ,80661   ,,,
BEGIN DESCRIPTION:
Proposed Trinity Forest Trail PedX Bridge - 08/10/09
END DESCRIPTION:
Node Name=Trinity Trail Br
Bridge Culvert--1,0,-1,-1, 0
Deck Dist Width WeirC Skew NumUp NumDn MinLoCord MaxHiCord MaxSubmerge Is_Ogee
2,10,2.6,0, 16, 16, , , 0.98, 0, 0,0,,
    5425    5425    5675    5675    5694    5694    5709    5709    5711    5711
    5882    5882    5884    5884    6159    6159
     387  391.33  401.33   407.5   407.5  401.33  401.33   404.5   404.5   404.5
   404.5   404.5   404.5  401.33  390.33     386
          385.92  395.92  395.92  395.92  395.92  395.92                     394
     394                  395.92  384.93
    5425    5425    5675    5675    5694    5694    5709    5709    5711    5711
    5882    5882    5884    5884    6159    6159
     387  391.33  401.33   407.5   407.5  401.33  401.33   404.5   404.5   404.5
   404.5   404.5   404.5  401.33  390.33     386
          385.92  395.92  395.92  395.92  395.92  395.92                     394
     394                  395.92  384.93
Pier Skew, UpSta & Num, DnSta & Num=  ,5902, 2 ,5902, 2 , 0 , 0 , 0 ,,
     1.5     1.5
  358.89  395.92
     1.5     1.5
  358.89  395.92
Pier Skew, UpSta & Num, DnSta & Num=  ,5920, 2 ,5920, 2 , 0 , 0 , 0 ,,
     1.5     1.5
  358.89  395.92
     1.5     1.5
  358.89  395.92
Pier Skew, UpSta & Num, DnSta & Num=  ,5938, 2 ,5938, 2 , 0 , 0 , 0 ,,
     1.5     1.5
  358.89  395.92
     1.5     1.5
  358.89  395.92
Pier Skew, UpSta & Num, DnSta & Num=  ,5956, 2 ,5956, 2 , 0 , 0 , 0 ,,
     1.5     1.5
  358.89  395.92
     1.5     1.5
  358.89  395.92
Pier Skew, UpSta & Num, DnSta & Num=  ,5974, 2 ,5974, 2 , 0 , 0 , 0 ,,
     1.5     1.5
  358.89  395.92
     1.5     1.5
  358.89  395.92
Pier Skew, UpSta & Num, DnSta & Num=  ,5992, 2 ,5992, 2 , 0 , 0 , 0 ,,
     1.5     1.5
  358.89  395.92
     1.5     1.5
  358.89  395.92
Pier Skew, UpSta & Num, DnSta & Num=  ,6010, 2 ,6010, 2 , 0 , 0 , 0 ,,
     1.5     1.5
  358.89  395.92
     1.5     1.5
  358.89  395.92
Pier Skew, UpSta & Num, DnSta & Num=  ,6028, 2 ,6028, 2 , 0 , 0 , 0 ,,
     1.5     1.5
  358.89  395.92
     1.5     1.5
  358.89  395.92
Pier Skew, UpSta & Num, DnSta & Num=  ,6046, 2 ,6046, 2 , 0 , 0 , 0 ,,
     1.5     1.5
  358.89  395.92
     1.5     1.5
  358.89  395.92
Pier Skew, UpSta & Num, DnSta & Num=  ,6064, 2 ,6064, 2 , 0 , 0 , 0 ,,
     1.5     1.5
  358.89  395.92
     1.5     1.5
  358.89  395.92
Pier Skew, UpSta & Num, DnSta & Num=  ,6082, 2 ,6082, 2 , 0 , 0 , 0 ,,
     1.5     1.5
  358.89  395.92
     1.5     1.5
  358.89  395.92
Pier Skew, UpSta & Num, DnSta & Num=  ,6100, 2 ,6100, 2 , 0 , 0 , 0 ,,
     1.5     1.5
  358.89  395.92
     1.5     1.5
  358.89  395.92
Pier Skew, UpSta & Num, DnSta & Num=  ,5493, 2 ,5493, 2 , 0 , 0 , 0 ,,
     1.5     1.5
  358.89  395.92
     1.5     1.5
  358.89  395.92
Pier Skew, UpSta & Num, DnSta & Num=  ,5511, 2 ,5511, 2 , 0 , 0 , 0 ,,
     1.5     1.5
  358.89  395.92
     1.5     1.5
  358.89  395.92
Pier Skew, UpSta & Num, DnSta & Num=  ,5529, 2 ,5529, 2 , 0 , 0 , 0 ,,
     1.5     1.5
  358.89  395.92
     1.5     1.5
  358.89  395.92
Pier Skew, UpSta & Num, DnSta & Num=  ,5547, 2 ,5547, 2 , 0 , 0 , 0 ,,
     1.5     1.5
  358.89  395.92
     1.5     1.5
  358.89  395.92
Pier Skew, UpSta & Num, DnSta & Num=  ,5565, 2 ,5565, 2 , 0 , 0 , 0 ,,
     1.5     1.5
  358.89  395.92
     1.5     1.5
  358.89  395.92
Pier Skew, UpSta & Num, DnSta & Num=  ,5583, 2 ,5583, 2 , 0 , 0 , 0 ,,
     1.5     1.5
  358.89  395.92
     1.5     1.5
  358.89  395.92
Pier Skew, UpSta & Num, DnSta & Num=  ,5601, 2 ,5601, 2 , 0 , 0 , 0 ,,
     1.5     1.5
  358.89  395.92
     1.5     1.5
  358.89  395.92
Pier Skew, UpSta & Num, DnSta & Num=  ,5619, 2 ,5619, 2 , 0 , 0 , 0 ,,
     1.5     1.5
  358.89  395.92
     1.5     1.5
  358.89  395.92
Pier Skew, UpSta & Num, DnSta & Num=  ,5637, 2 ,5637, 2 , 0 , 0 , 0 ,,
     1.5     1.5
  358.89  395.92
     1.5     1.5
  358.89  395.92
Pier Skew, UpSta & Num, DnSta & Num=  ,5655, 2 ,5655, 2 , 0 , 0 , 0 ,,
     1.5     1.5
  358.89  395.92
     1.5     1.5
  358.89  395.92
Pier Skew, UpSta & Num, DnSta & Num=  ,5673, 2 ,5673, 2 , 0 , 0 , 0 ,,
     1.5     1.5
  358.89  395.92
     1.5     1.5
  358.89  395.92
Pier Skew, UpSta & Num, DnSta & Num=  ,5691, 2 ,5691, 2 , 0 , 0 , 0 ,,
     1.5     1.5
  358.89  395.92
     1.5     1.5
  358.89  395.92
BR Coef=-1 , 0 , 0 ,, 0 ,,,0.8,-1,,0,
WSPro=,,,, 1 ,,,, 0 ,,,, 0 ,,,,-1 ,-1 ,-1 , 0 , 0 , 0 , 0 , 0
BC Design=,, 0 ,, 0 ,,12,5493,5493,18,1.5
BC Use User HTab Curves=0
BC User HTab FreeFlow(D)= 0

Type RM Length L Ch R = 1 ,80654   ,785,618,417
BEGIN DESCRIPTION:
Cross-section added for Trinity Trails project.
Wetland Cell F in ROB.
END DESCRIPTION:
XS GIS Cut Line= 3
2516821.252563816950701.300562612512684.346319816949440.68110911
2509099.697450116948365.97465681
#Sta/Elev= 30
    1000   417.3  2132.5   404.7  4864.4     402 5109.52     389 5407.55     383
 5430.64     387 5720.22     388    5753  361.07    5810  358.89 5878.07     386
 5988.32     386 6269.09     388 6412.54  394.32  6780.2     390    6880     398
    7190     404    7600     406  8049.3   391.9    8200     396    8360     388
    8440     385    8450     381    8530     381    8540     385    8660     388
    8800   390.3    8836   399.2  8915.3     402  8970.8     416    9067   417.1
#Mann= 11 ,-1,0
    1000    .098       0  4864.4    .182       0 5720.22     .06       0
 5878.07    .182       0 5988.32    .084       0    8200    .035       0
    8360    .045       0    8450    .025       0    8530    .045       0
    8660    .035       0    8836    .084       0
Bank Sta=5720.22,5878.07
XS Rating Curve= 0 ,0
Exp/Cntr=0.3,0.1

Type RM Length L Ch R = 1 ,80641   ,799,604,400
BEGIN DESCRIPTION:
This cross section corresponds to cross section 80641 of the non-georeferenced CDC model which was the source of this model.
END DESCRIPTION:
XS GIS Cut Line= 3
2516826.689147746950716.07699822 2512684.99992466949454.00012605
2509105.140614516948380.72963481
#Sta/Elev= 30
    1000   417.3  2132.5   404.7  4864.4     402  5347.6     386  5688.9   389.6
  5727.7     388    5780   365.5    5820     365    5860   365.3  5883.8     387
    5960     390  6082.9     396    6107   401.8  6162.9   394.5  6338.4     390
  6681.2   396.8  6780.2     390    6880     398    7600     406  8049.3   391.9
    8200     396    8360     388    8450     381    8530     381    8660     388
    8800   390.3    8836   399.2  8915.3     402  8970.8     416    9067   417.1
#Mann= 11 ,-1,0
    1000    .098       0  4864.4    .182       0  5688.9     .06       0
    5960    .182       0    6107    .084       0    8200    .035       0
    8360    .045       0    8450    .025       0    8530    .045       0
    8660    .035       0    8836    .084       0
#XS Ineff= 2 , 0
          5688.9   389.6    5960             390
Permanent Ineff=
       F       F
Bank Sta=5688.9,5960
XS Rating Curve= 0 ,0
Exp/Cntr=0.3,0.1

Type RM Length L Ch R = 1 ,80036   ,620,684,600
BEGIN DESCRIPTION:
Wetland Cell G in ROB.
Golf course in LOB.
END DESCRIPTION:
XS GIS Cut Line= 2
  2516962.746261 6949420.6066113 2508595.6168171  6948185.486215
#Sta/Elev= 30
     950     416    1765     396    2480     404    3325     400    3390     398
  3857.8   408.9  4282.5     396  5028.8   399.8  5293.4   389.6  5620.3     390
    5710     375    5730   365.5    5770     365    5810   365.3    5825     380
  5906.9     386    5939     390    5942   401.7    5961   401.7  6146.8     386
    6735     390    7110     404  7465.2     388    7880     390    8190     388
    8490     388    8570   390.1    8602     398    8775     416  9407.8     416
#Mann= 13 ,-1,0
     950    .084       0    2480    .045       0    3325    .126       0
    3390    .084       0  4282.5      .1       0  5293.4    .196       0
  5620.3     .06       0  5906.9    .182       0    5961    .084       0
    7880    .035       0    8190    .045       0    8490    .035       0
    8602    .084       0
#XS Ineff= 2 , 0
            3850   409.5    5939             390
Permanent Ineff=
       F       F
Bank Sta=5620.3,5939
XS Rating Curve= 0 ,0
Exp/Cntr=0.3,0.1