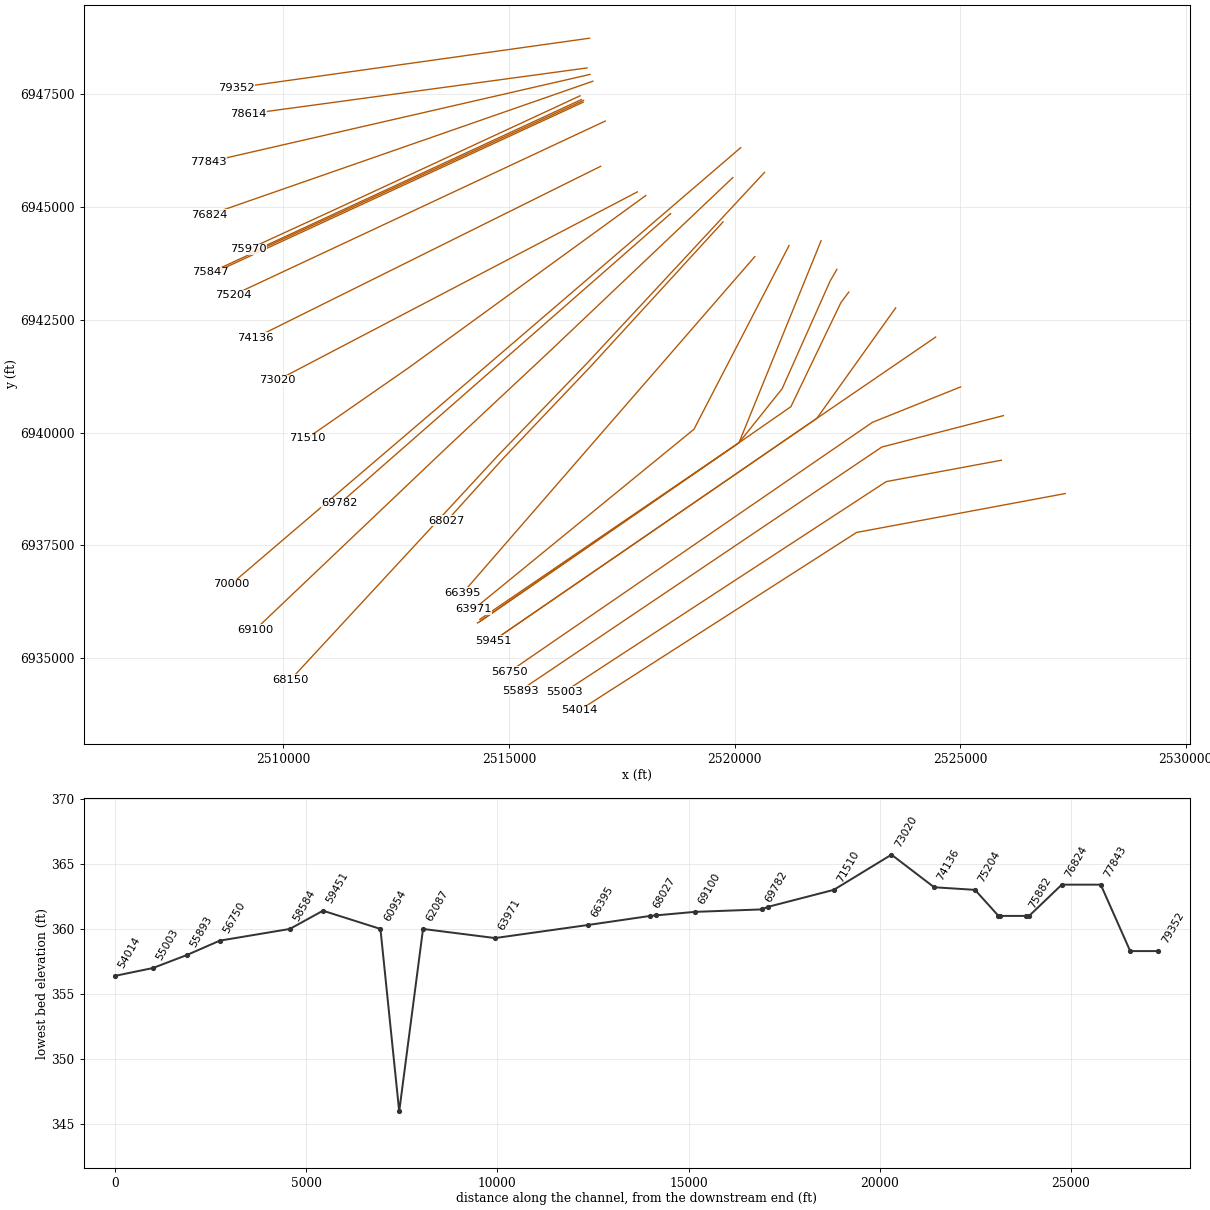
HEC-RAS study CDC_Consolidated_Model.prj: Upper Trinity CDC Consolidated Model

--- CDC_Consolidated_Model.g13 (geometry) --- (continued)

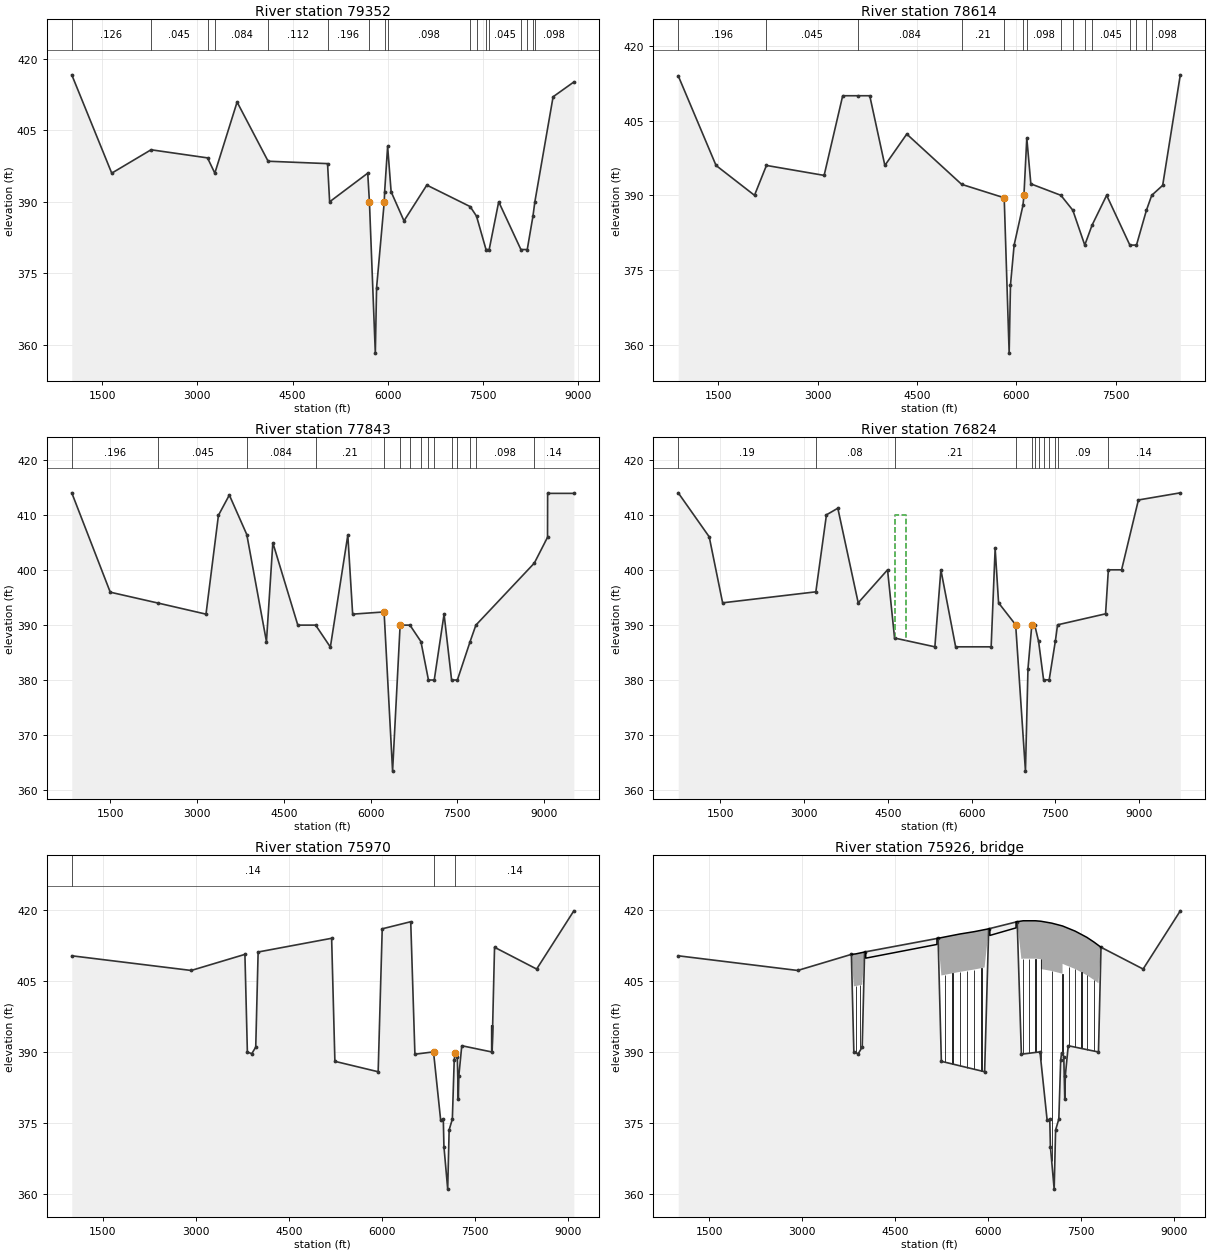
Type RM Length L Ch R = 1 ,79352   ,630,738,620
BEGIN DESCRIPTION:
Wetland Cell G in ROB.
Golf course in LOB.
END DESCRIPTION:
XS GIS Cut Line= 2
   2516787.83241 6948738.5728111 2508950.1675891  6947638.427189
#Sta/Elev= 30
    1020   416.6    1650     396    2270   400.9    3160   399.2    3275     396
  3626.1   410.9    4115   398.5    5052     398  5084.9     390  5685.5     396
  5712.1     390    5805   358.3    5825     372    5946     390  5951.4     392
    5999   401.6  6054.2   392.1  6257.1     386  6616.7   393.5    7300     389
    7400     387    7550     380    7600     380    7750     390    8100     380
    8200     380    8290     387    8320     390  8607.4     412  8934.5   415.1
#Mann= 17 ,-1,0
    1020    .126       0    2270    .045       0    3160    .126       0
    3275    .084       0    4115    .112       0    5052    .196       0
  5712.1     .06       0  5951.4    .182       0    5999    .098       0
    7300    .035       0    7400    .045       0    7550    .025       0
    7600    .045       0    8100    .025       0    8200    .045       0
    8290    .035       0    8320    .098       0
#XS Ineff= 2 , 0
            3600   409.2    5946             390
Permanent Ineff=
       F       F
Bank Sta=5712.1,5946
XS Rating Curve= 0 ,0
Exp/Cntr=0.3,0.1

Type RM Length L Ch R = 1 ,78614   ,500,771,750
BEGIN DESCRIPTION:
Wetland Cell G in ROB.
Golf course in LOB.
END DESCRIPTION:
XS GIS Cut Line= 3
  2516731.932143  6948079.581699        2516632.        6948066.
        2509230.        6947060.
#Sta/Elev= 30
     900     414    1470     396    2050     390    2230     396    3100     394
    3380     410    3615     410  3787.9     410  4015.8     396    4346   402.3
  5173.7   392.2  5815.3   389.5    5890   358.3    5910     372    5965     380
  6098.3     388    6113     390    6156   401.5    6217   392.3    6670     390
    6850     387    7030     380    7140     384    7360     390    7710     380
    7810     380    7960     387    8040     390    8205     392  8470.9   414.2
#Mann= 15 ,-1,0
     900    .196       0    2230    .045       0    3615    .084       0
  5173.7     .21       0  5815.3     .06       0  6098.3    .182       0
    6156    .098       0    6670    .035       0    6850    .045       0
    7030    .025       0    7140    .045       0    7710    .025       0
    7810    .045       0    7960    .035       0    8040    .098       0
#XS Ineff= 2 , 0
            3500     409    6113             390
Permanent Ineff=
       F       F
Bank Sta=5815.3,6113
XS Rating Curve= 0 ,0
Exp/Cntr=0.3,0.1

Type RM Length L Ch R = 1 ,77843   ,650,1019,880
BEGIN DESCRIPTION:
Wetland Cell G in ROB.
Golf course in LOB.
END DESCRIPTION:
XS GIS Cut Line= 3
  2516797.173877 6947935.8705909        2516667.        6947906.
        2508339.        6945995.
#Sta/Elev= 30
     835   414.1    1500     396    2333     394    3155     392    3370     410
  3558.3   413.7    3860   406.5    4200     387  4310.3     405    4742     390
    5050     390  5304.6     386  5606.2   406.4  5689.9     392  6233.1   392.4
    6380   363.4  6510.4     390    6680     390    6870     387    7000     380
    7100     380    7270     392    7400     380    7500     380    7720     387
    7820     390    8830   401.3    9058     406    9060     414    9513     414
#Mann= 15 ,-1,0
     835    .196       0    2333    .045       0    3860    .084       0
    5050     .21       0  6233.1     .06       0  6510.4     .08       0
    6680    .035       0    6870    .045       0    7000    .025       0
    7100    .045       0    7400    .025       0    7500    .045       0
    7720    .035       0    7820    .098       0    8830     .14       0
#XS Ineff= 2 , 0
            3500   408.5  6510.4             390
Permanent Ineff=
       F       F
Bank Sta=6233.1,6510.4
XS Rating Curve= 0 ,0
Exp/Cntr=0.3,0.1

Type RM Length L Ch R = 1 ,76824   ,700,854,860
BEGIN DESCRIPTION:
**********************************************
Begin Dallas Floodway Extension Project
**********************************************
Wetland Cell G in ROB.
END DESCRIPTION:
XS GIS Cut Line= 3
  2516860.901411 6947785.3087123        2516748.        6947746.
        2508367.        6944828.
#Sta/Elev= 30
     745     414    1300     406    1540     394    3210     396    3400     410
  3603.8   411.2  3968.9     394  4494.6     400  4620.1   387.6  5342.3     386
    5450     400  5714.2     386  6350.4     386    6422   403.9  6483.4     394
  6789.6     390    6965   363.4    7010     382    7079     390    7130     390
    7200     387    7290     380    7390     380    7500     387    7540     390
    8400     392    8450     400    8687     400  8988.2   412.7    9739     414
#Mann= 12 ,-1,0
     745     .19       0    3210     .08       0  4620.1     .21       0
  6789.6    .055       0    7079     .08       0    7130    .035       0
    7200    .045       0    7290    .025       0    7390    .045       0
    7500    .035       0    7540     .09       0    8450     .14       0
#XS Ineff= 2 ,-1
    1000    3500     408    4620    4830     410
Permanent Ineff=
       F       F
Bank Sta=6789.6,7079
XS Rating Curve= 0 ,0
Exp/Cntr=0.3,0.1

Type RM Length L Ch R = 1 ,75970   ,88,88,88
BEGIN DESCRIPTION:
Upstream bounding cross-section for SH 12 bridge.
Blocked obstruction added for Trinity Trails project
END DESCRIPTION:
XS GIS Cut Line= 5
  2516576.950481 6947461.5274525 2516562.3407504 6947454.7503471
 2511100.5823298 6944921.1710641 2509240.2282898 6944067.1689987
 2509225.5917289  6944060.450034
#Sta/Elev= 30
    1000   410.3    2927   407.2  3793.4   410.6    3833     390    3903   389.6
    3968     391  4006.6   411.1  5192.4     414    5245     388    5943   385.8
  6008.6     416  6468.4   417.5    6536   389.5    6836     390    6952   375.5
    6994   375.8    7004     370    7065     361    7088   373.5    7140   375.8
    7170   388.3    7186   389.8    7220     389    7236     380    7245     385
    7292   391.3 7779.71  389.97  7820.6   412.1    8500   407.5    9100   419.8
#Mann= 3 ,0,0
    1000     .14       0    6836    .055       0    7186     .14       0
#Block Obstruct= 1 ,-1
 7760.42 7807.42  395.65
Bank Sta=6836,7186
XS Rating Curve= 0 ,0
Exp/Cntr=0.3,0.1

Type RM Length L Ch R = 3 ,75926   ,,,
BEGIN DESCRIPTION:
SH 12
USGS gaging station 08057410 Trinity River Below Dallas located on right bank at downstream side of bridge.  Gage datum elev. 365.89 NGVD.
END DESCRIPTION:
Node Name=SH 12
Bridge Culvert--1,0,-1,-1, 0
Deck Dist Width WeirC Skew NumUp NumDn MinLoCord MaxHiCord MaxSubmerge Is_Ogee
1,86,2.6,0, 35, 35, , , 0.95, 0, ,,,
  3793.4    3864    3936  4006.6  4006.6    4025    4025    5174    5174  5192.4
  5192.4    5308    5542    5776    5893  6008.6  6008.6    6027    6027    6450
    6450  6468.4  6468.4    6565    6663    6763    6850    6850    7025    7200
    7200    7405    7592    7707  7820.6
   410.6   410.7   410.9   411.1   411.1   411.1   409.8   412.7     414     414
     414   414.3   414.9   415.4   415.7     416     416     416   414.6   416.2
   417.5   417.5   417.5   417.7   417.7   417.7   417.6   417.6   417.2   416.6
   416.6   415.5   414.2   413.2   412.1
   403.8   403.9   404.1   404.3   411.1   411.1   409.8   412.7     414     414
     406   406.3   406.9   407.4   407.7     408     416     416   414.6   416.2
   417.5   417.5   409.5   409.7   409.7   409.7   409.6   407.5   407.1   406.5
   408.6   407.5   406.2   405.2   404.1
  3793.4    3864    3936  4006.6  4006.6    4025    4025    5174    5174  5192.4
  5192.4    5308    5542    5776    5893  6008.6  6008.6    6027    6027    6450
    6450  6468.4  6468.4    6565    6663    6763    6850    6850    7025    7200
    7200    7405    7592    7707  7820.6
   410.6   410.7   410.9   411.1   411.1   411.1   409.8   412.7     414     414
     414   414.3   414.9   415.4   415.7     416     416     416   414.6   416.2
   417.5   417.5   417.5   417.7   417.7   417.7   417.6   417.6   417.2   416.6
   416.6   415.5   414.2   413.2   412.1
   403.8   403.9   404.1   404.3   411.1   411.1   409.8   412.7     414     414
     406   406.3   406.9   407.4   407.7     408     416     416   414.6   416.2
   417.5   417.5   409.5   409.7   409.7   409.7   409.6   407.5   407.1   406.5
   408.6   407.5   406.2   405.2   404.1
Pier Skew, UpSta & Num, DnSta & Num=  ,3864, 2 ,3864, 2 , 0 , 0 , 0 ,,
       3       3
       0     410
       3       3
       0     410
Pier Skew, UpSta & Num, DnSta & Num=  ,3936, 2 ,3936, 2 , 0 , 0 , 0 ,,
       3       3
       0     410
       3       3
       0     410
Pier Skew, UpSta & Num, DnSta & Num=  ,5308, 2 ,5308, 2 , 0 , 0 , 0 ,,
       3       3
       0     413
       3       3
       0     413
Pier Skew, UpSta & Num, DnSta & Num=  ,5425, 2 ,5425, 2 , 0 , 0 , 0 ,,
       3       3
       0     413
       3       3
       0     413
Pier Skew, UpSta & Num, DnSta & Num=  ,5542, 2 ,5542, 2 , 0 , 0 , 0 ,,
       3       3
       0     413
       3       3
       0     413
Pier Skew, UpSta & Num, DnSta & Num=  ,5659, 2 ,5659, 2 , 0 , 0 , 0 ,,
       3       3
       0     413
       3       3
       0     413
Pier Skew, UpSta & Num, DnSta & Num=  ,5776, 2 ,5776, 2 , 0 , 0 , 0 ,,
       3       3
       0     413
       3       3
       0     413
Pier Skew, UpSta & Num, DnSta & Num=  ,5893, 2 ,5893, 2 , 0 , 0 , 0 ,,
       3       3
       0     413
       3       3
       0     413
Pier Skew, UpSta & Num, DnSta & Num=  ,6565, 2 ,6565, 2 , 0 , 0 , 0 ,,
       3       3
       0     415
       3       3
       0     415
Pier Skew, UpSta & Num, DnSta & Num=  ,6663, 2 ,6663, 2 , 0 , 0 , 0 ,,
       3       3
       0     415
       3       3
       0     415
Pier Skew, UpSta & Num, DnSta & Num=  ,6763, 2 ,6763, 2 , 0 , 0 , 0 ,,
       3       3
       0     415
       3       3
       0     415
Pier Skew, UpSta & Num, DnSta & Num=  ,6850, 2 ,6850, 2 , 0 , 0 , 0 ,,
       3       3
       0     415
       3       3
       0     415
Pier Skew, UpSta & Num, DnSta & Num=  ,7025, 2 ,7025, 2 , 0 , 0 , 0 ,,
       4       4
       0     415
       4       4
       0     415
Pier Skew, UpSta & Num, DnSta & Num=  ,7200, 2 ,7200, 2 , 0 , 0 , 0 ,,
       3       3
       0     415
       3       3
       0     415
Pier Skew, UpSta & Num, DnSta & Num=  ,7305, 2 ,7305, 2 , 0 , 0 , 0 ,,
       3       3
       0     413
       3       3
       0     413
Pier Skew, UpSta & Num, DnSta & Num=  ,7405, 2 ,7405, 2 , 0 , 0 , 0 ,,
       3       3
       0     413
       3       3
       0     413
Pier Skew, UpSta & Num, DnSta & Num=  ,7505, 2 ,7505, 2 , 0 , 0 , 0 ,,
       3       3
       0     413
       3       3
       0     413
Pier Skew, UpSta & Num, DnSta & Num=  ,7592, 2 ,7592, 2 , 0 , 0 , 0 ,,
       3       3
       0     413
       3       3
       0     413
Pier Skew, UpSta & Num, DnSta & Num=  ,7707, 2 ,7707, 2 , 0 , 0 , 0 ,,
       3       3
       0     410
       3       3
       0     410
BR Coef= 1 , 0 , 0 ,1.05, 0 ,,,0.8,0,0.5,1,
WSPro=,,,, 1 ,,,, 0 ,,,, 0 ,,,,-1 ,-1 ,-1 , 0 , 0 , 0 , 0 , 0
BC Design=,, 0 ,, 0 ,,,,,,
BC HTab HWMax=419.8
BC Use User HTab Curves=0
BC User HTab FreeFlow(D)= 0

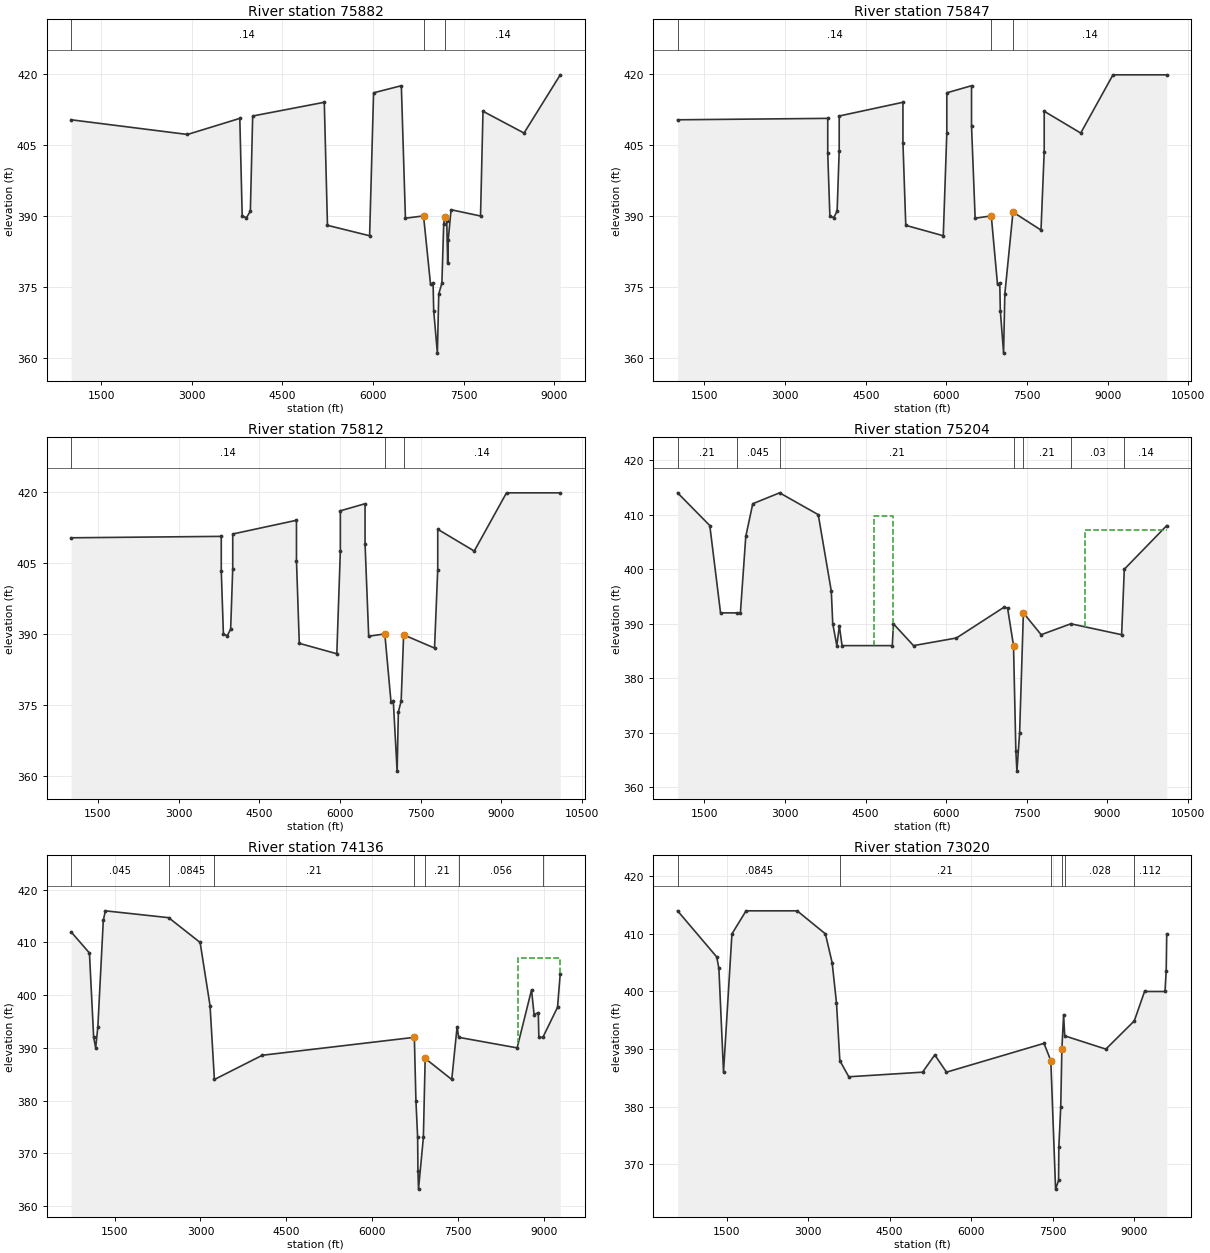
Type RM Length L Ch R = 1 ,75882   ,666,678,678
BEGIN DESCRIPTION:
Downstream bounding cross-section for SH 12 bridge.
END DESCRIPTION:
XS GIS Cut Line= 4
  2516607.665217 6947378.6686499 2516589.8902916  6947370.446838
 2509273.8042931 6943986.3830999  2509256.029367  6943978.161288
#Sta/Elev= 30
    1000   410.3    2927   407.2  3793.4   410.6    3833     390    3903   389.6
    3968     391  4006.6   411.1  5192.4     414    5245     388    5943   385.8
  6008.6     416  6468.4   417.5    6536   389.5    6836     390    6952   375.5
    6994   375.8    7004     370    7065     361    7088   373.5    7140   375.8
    7170   388.3    7186   389.8    7220     389    7236     380    7245     385
    7292   391.3 7779.71  389.97  7820.6   412.1    8500   407.5    9100   419.8
#Mann= 3 ,0,0
    1000     .14       0    6836    .055       0    7186     .14       0
Bank Sta=6836,7186
XS Rating Curve= 0 ,0
Exp/Cntr=0.3,0.1

Type RM Length L Ch R = 1 ,75847   ,35,35,35
BEGIN DESCRIPTION:
This cross section corresponds to cross section 75847 of the non-georeferenced CDC model which was the source of this model.
---------------------------------------------------------------------
CDC DAL121500-1, Trinity River Boat Ramps at Sylvan Avenue and Loop 12.
---------------------------------------------------------------------
Cross-section added.
END DESCRIPTION:
XS GIS Cut Line= 3
2516654.809242166947360.645388892509300.080185266943966.83360697
2508392.088929226943547.84449142
#Sta/Elev= 30
    1000   410.3  3793.4   410.6  3793.4   403.3    3833     390    3903   389.6
    3968     391  4006.6   403.8  4006.6   411.1  5192.4     414  5192.4   405.5
    5245     388    5943   385.8  6008.6   407.5  6008.6     416  6468.4   417.5
  6468.4     409    6536   389.5    6836     390    6952   375.5    6994   375.8
    7004     370    7065     361    7088   373.5    7240   390.8    7761     387
  7820.6   403.6  7820.6   412.1    8500   407.5    9100   419.8   10100   419.8
#Mann= 3 ,0,0
    1000     .14       0    6836    .055       0    7240     .14       0
Bank Sta=6836,7240
XS Rating Curve= 0 ,0
Exp/Cntr=0.3,0.1

Type RM Length L Ch R = 1 ,75812   ,615,615,615
BEGIN DESCRIPTION:
This cross section corresponds to cross section 75812 of the non-georeferenced CDC model which was the source of this model.
---------------------------------------------------------------------
CDC DAL121500-1, Trinity River Boat Ramps at Sylvan Avenue and Loop 12.
---------------------------------------------------------------------
Cross-section added.
END DESCRIPTION:
XS GIS Cut Line= 3
  2516645.241676 6947319.84789832509291.771802936943923.30875963
2508383.93599741 6943503.9829314
#Sta/Elev= 30
    1000   410.3  3793.4   410.6  3793.4   403.3    3833     390    3903   389.6
    3968     391  4006.6   403.8  4006.6   411.1  5192.4     414  5192.4   405.5
    5245     388    5943   385.8  6008.6   407.5  6008.6     416  6468.4   417.5
  6468.4     409    6536   389.5    6836     390    6952   375.5    6994   375.8
    7065     361    7088   373.5    7140   375.8    7186   389.8    7761     387
  7820.6   403.6  7820.6   412.1    8500   407.5    9100   419.8   10100   419.8
#Mann= 3 ,0,0
    1000     .14       0    6836    .055       0    7186     .14       0
Bank Sta=6836,7186
XS Rating Curve= 0 ,0
Exp/Cntr=0.3,0.1

Type RM Length L Ch R = 1 ,75204   ,970,1068,1030
BEGIN DESCRIPTION:
Trinity Forest Golf Course in LOB.
END DESCRIPTION:
XS GIS Cut Line= 3
  2517134.608276 6946902.0085811  2517133.904684 6946901.6794901
 2508882.6442481 6943042.3208124
#Sta/Elev= 30
    1000     414    1600     408    1800     392    2105     392    2170     392
    2270     406    2400     412    2900     414    3620     410  3862.6     396
  3889.9     390  3965.6     386  4012.9   389.6  4063.2     386  4998.8     386
    5020     390  5393.9     386    6194   387.4  7073.4     393  7145.6   392.9
  7256.6     386    7300   366.7    7320     363    7370     370  7440.4     392
  7771.5     388  8324.1     390    9270     388    9320     400   10110     408
#Mann= 7 ,-1,0
    1000     .21       0    2105    .045       0    2900     .21       0
  7256.6    .055       0  7440.4     .21       0  8324.1     .03       0
    9320     .14       0
#XS Ineff= 3 ,-1
    1000    2800   407.4    4650    5010   409.8    8580   10110   407.2
Permanent Ineff=
       F       F       F
Bank Sta=7256.6,7440.4
XS Rating Curve= 0 ,0
Exp/Cntr=0.6,0.4

Type RM Length L Ch R = 1 ,74136   ,960,1116,1030
BEGIN DESCRIPTION:
Trinity Forest Golf Course in LOB.
END DESCRIPTION:
XS GIS Cut Line= 2
  2517034.303557 6945900.1468955 2509378.8184939 6942099.5209681
#Sta/Elev= 30
     740     412    1060     408  1133.8     392    1169     390  1207.2     394
  1302.3   414.2  1338.5     416    2444   414.7  2994.1     410  3167.6     398
  3243.5     384  4080.6   388.6  6737.4     392    6765     380    6795     373
    6800   366.7    6810   363.2    6895     373  6926.6     388  7391.2     384
  7484.5     394  7512.5     392  8533.1     390    8785     401    8830   396.3
    8903   396.7    8913     392    8983     392    9239   397.7    9287   404.1
#Mann= 7 ,-1,0
     740    .045       0    2444   .0845       0  3243.5     .21       0
  6737.4    .055       0  6926.6     .21       0  7512.5    .056       0
    8983    .154       0
#XS Ineff= 2 , 0
            2000     407    8550             407
Permanent Ineff=
       F       F
Bank Sta=6737.4,6926.6
XS Rating Curve= 0 ,0
Exp/Cntr=0.3,0.1

Type RM Length L Ch R = 1 ,73020   ,900,1510,1350
BEGIN DESCRIPTION:
This cross section corresponds to cross section 73020 of the non-georeferenced CDC model which was the source of this model.
END DESCRIPTION:
XS GIS Cut Line= 3
  2517846.513146 6945332.1864865        2517483.        6945142.
        2509872.        6941160.
#Sta/Elev= 30
     600     414    1320     406    1360     404    1445     386    1600     410
    1860     414    2800     414    3320     410  3443.8     405  3523.9     398
  3585.4     388  3750.1   385.2  5107.8     386  5332.4     389  5547.7     386
  7341.7     391  7467.4     388    7555   365.7    7610   367.2    7615     373
    7650     380  7670.6     390  7702.6     396    7723   392.3    8480     390
  9003.6   394.9    9192     400  9568.3     400  9590.4   403.6    9600     410
#Mann= 6 ,-1,0
     600   .0845       0  3585.4     .21       0  7467.4    .055       0
  7670.6    .168       0    7723    .028       0  9003.6    .112       0
#XS Ineff= 2 , 0
            2000   406.6
Permanent Ineff=
       F       F
Bank Sta=7467.4,7670.6
XS Rating Curve= 0 ,0
Exp/Cntr=0.3,0.1

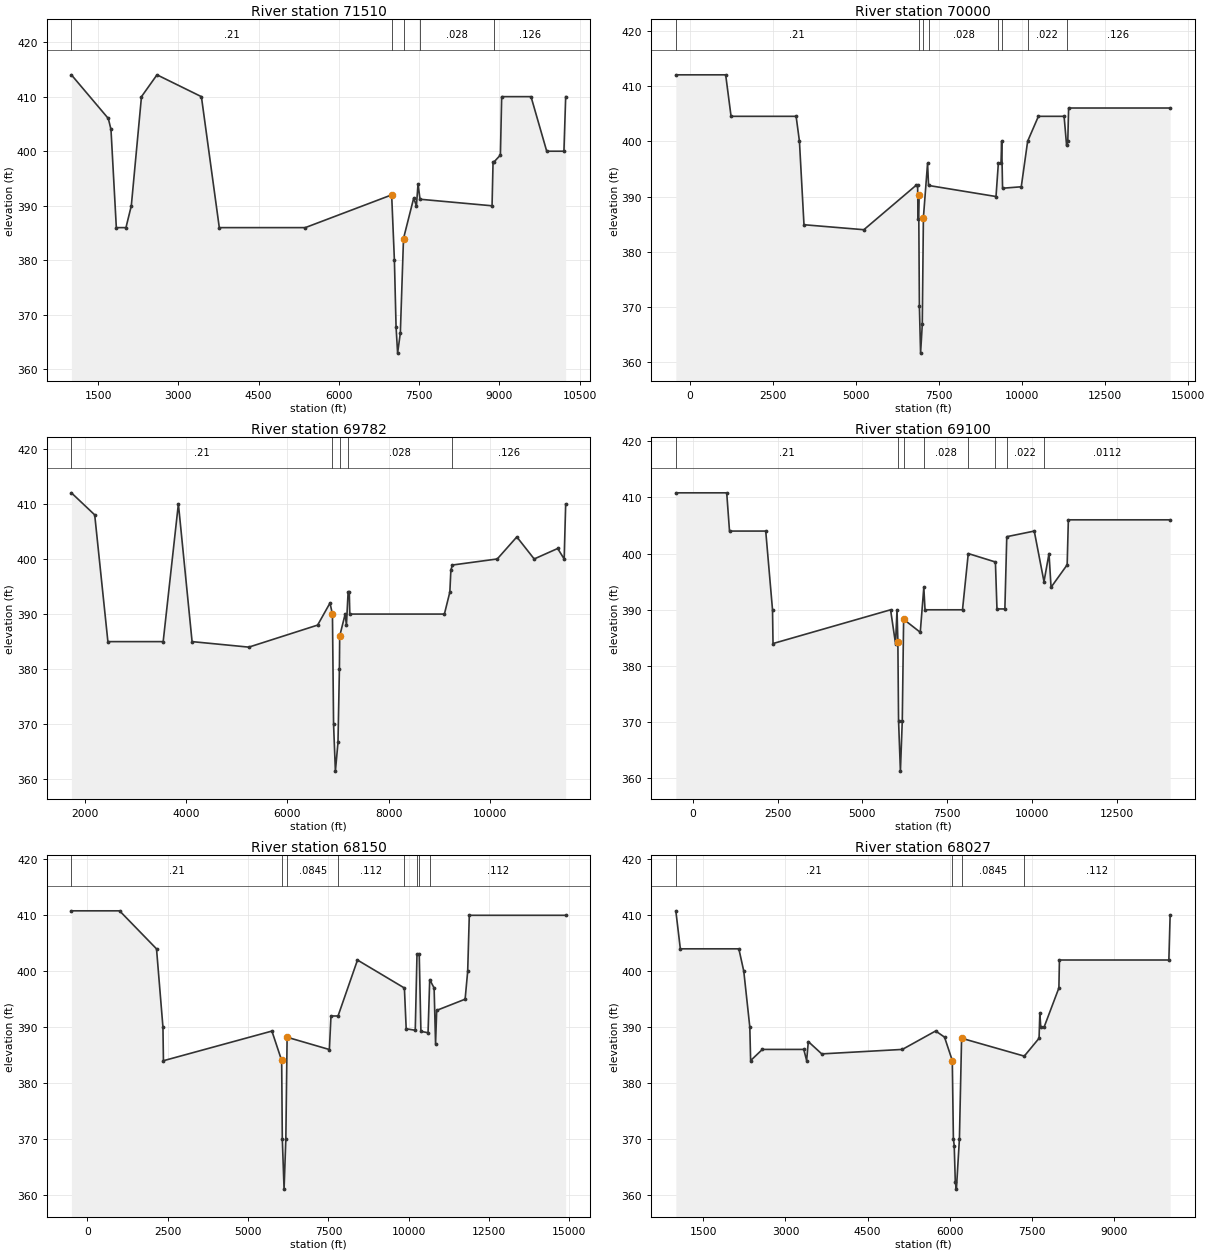
Type RM Length L Ch R = 1 ,71510   ,1000,1728,1300
BEGIN DESCRIPTION:
This cross section corresponds to cross section 71510 of the non-georeferenced CDC model which was the source of this model.
END DESCRIPTION:
XS GIS Cut Line= 6
  2518036.060532 6945253.7597794 2518036.0605324 6945253.7597794
        2518024.        6945245.        2512788.        6941442.
        2510540.        6939881. 2510527.7563388 6939872.4980627
#Sta/Elev= 30
    1000     414    1690     406    1740     404    1840     386    2020     386
    2120     390    2310     410    2600     414    3430     410  3764.4     386
    5371     386  6985.7     392    7037     380    7068   367.8    7097     363
    7148   366.7    7207     384  7397.2   391.4  7448.4     390  7478.5     394
  7515.8   391.2  8861.9     390  8880.5     398  8894.7     398  9018.2   399.3
  9041.7     410    9590     410  9883.7     400 10205.3     400   10238     410
#Mann= 5 ,-1,0
    1000     .21       0  6985.7    .055       0    7207    .196       0
  7515.8    .028       0  8894.7    .126       0
#XS Ineff= 2 , 0
            3000   406.4
Permanent Ineff=
       F       F
Bank Sta=6985.7,7207
XS Rating Curve= 0 ,0
Exp/Cntr=0.3,0.1

Type RM Length L Ch R = 1 ,70000   ,161,153,154
BEGIN DESCRIPTION:
This cross section corresponds to cross section 70000 of the non-georeferenced CDC model which was the source of this model.
END DESCRIPTION:
XS GIS Cut Line= 5
2520137.081811856946312.733870752518998.855735186945335.77870372
2513502.254851766940617.97022596 2511120.65462816938583.35716921
 2508839.68946446936634.71715064
#Sta/Elev= 30
    -420     412    1080     412  1242.3   404.5    3200   404.5    3300     400
  3436.7   384.9  5238.9     384  6805.2     392    6857     392  6869.5     386
  6887.9  390.19    6910  370.19    6946  361.69    6997  366.89  7030.8  386.19
    7156     396    7186     392    9216     390    9286     396    9366     396
    9386     400    9413   391.5    9976  391.76   10168     400   10492   404.5
   11265   404.5   11340  399.25   11376     400   11401     406   14456     406
#Mann= 8 ,-1,0
    -420     .21       0  6887.9    .055       0  7030.8    .182       0
    7186    .028       0    9286    .126       0    9386    .028       0
   10168    .022       0   11340    .126       0
Bank Sta=6887.9,7030.8
XS Rating Curve= 0 ,0
Exp/Cntr=0.3,0.1

Type RM Length L Ch R = 1 ,69782   ,1400,1755,1700
BEGIN DESCRIPTION:
This cross section corresponds to cross section 69782 of the non-georeferenced CDC model which was the source of this model.
END DESCRIPTION:
XS GIS Cut Line= 4
  2518584.893114 6944852.6926718 2518584.8931147 6944852.6926718
        2511255.        6938428.        2511255.        6938428.
#Sta/Elev= 30
    1740     412    2200     408    2460     385    3550     385    3850     410
    4120     385  5238.9     384  6595.5     388  6839.2     392  6887.9     390
    6910     370    6946   361.5    6997   366.7    7025     380  7030.8     386
  7138.5     390  7163.6     388  7196.8     394  7219.9     394    7230     390
  9095.4     390    9203     394  9223.1     398  9254.5   398.9   10138     400
 10523.5     404 10865.8     400 11329.2   401.9   11457     400   11487     410
#Mann= 5 ,-1,0
    1740     .21       0  6887.9    .055       0  7030.8    .182       0
  7196.8    .028       0  9254.5    .126       0
#XS Ineff= 2 , 0
            3850   406.3
Permanent Ineff=
       F       F
Bank Sta=6887.9,7030.8
XS Rating Curve= 0 ,0
Exp/Cntr=0.3,0.1

Type RM Length L Ch R = 1 ,69100   ,770,1016,674
BEGIN DESCRIPTION:
This cross section corresponds to cross section 69100 of the non-georeferenced CDC model which was the source of this model.
END DESCRIPTION:
XS GIS Cut Line= 6
2519962.221802626945649.507311022518874.006247346944617.13775255
 2515914.56826866941809.574798142513661.065557756939701.99075872
2511555.366685186937700.262478712509381.046201596935633.30083547
#Sta/Elev= 30
    -500   410.8    1000   410.8  1082.4     404    2150     404    2350     390
    2365     384    5830     390  5975.7     384    6020     390    6045  384.31
    6065  370.31    6120  361.31    6175  370.31  6214.5  388.31    6705     386
    6810     394    6845     390    7950     390    8120     400    8920   398.5
    8966  390.15    9199  390.15    9255     403   10065     404   10352     395
   10500     400   10560     394   11035     398   11070     406   14070     406
#Mann= 8 ,-1,0
    -500     .21       0    6045    .055       0  6214.5   .0845       0
    6810    .028       0    8120    .112       0    8920    .028       0
    9255    .022       0   10352   .0112       0
Bank Sta=6045,6214.5
XS Rating Curve= 0 ,0
Exp/Cntr=0.3,0.1

Type RM Length L Ch R = 1 ,68150   ,97,150,219
BEGIN DESCRIPTION:
This cross section corresponds to cross section 68150 of the non-georeferenced CDC model which was the source of this model.
END DESCRIPTION:
XS GIS Cut Line= 6
2520664.47891507  6945764.6722222519642.965011276944666.26002963
2516722.098805766941525.514670712514741.519105496939472.78419614
2512199.576354746936724.589233222510162.509831086934522.23595134
#Sta/Elev= 30
    -500   410.8    1000   410.8    2150     404    2350     390    2365     384
  5741.1   389.3    6045  384.04    6065  370.04    6120  361.04    6175  370.04
  6214.5   388.2    7530     386    7580     392    7800     392    8405     402
    9865     397    9921   389.7   10203  389.45   10257     403   10327     403
   10379  389.25   10601     389   10653   398.5   10790     397   10835     387
   10870     393   11755     395   11835     400   11885     410   14885     410
#Mann= 8 ,-1,0
    -500     .21       0    6045    .055       0  6214.5   .0845       0
    7800    .112       0    9865    .028       0   10257    .013       0
   10327    .028       0   10653    .112       0
Bank Sta=6045,6214.5
XS Rating Curve= 0 ,0
Exp/Cntr=0.3,0.1

Type RM Length L Ch R = 1 ,68027   ,1130,1632,1230
BEGIN DESCRIPTION:
McCommas Bluff Landfill in ROB.
END DESCRIPTION:
XS GIS Cut Line= 6
  2519746.946971 6944668.7687878 2519740.5876663 6944661.8250211
        2516822.        6941475.        2514876.        6939429.
 2513632.6074207 6938050.8346376 2513626.3000794 6938043.8436362
#Sta/Elev= 30
    1000   410.8  1082.4     404    2150     404    2240     400    2350     390
    2365     384  2578.8     386  3334.8     386    3387     384  3417.6   387.4
  3662.7   385.2  5133.9     386  5741.1   389.3  5903.2   388.2    6045     384
    6065     370    6080   368.8    6100   362.2    6120     361    6175     370
  6214.5     388  7358.5   384.8  7628.4     388  7642.4   392.5  7659.2     390
  7720.4     390  7990.2     397    8000     402  9996.9     402   10020     410
#Mann= 4 ,-1,0
    1000     .21       0    6045    .055       0  6214.5   .0845       0
  7358.5    .112       0
Bank Sta=6045,6214.5
XS Rating Curve= 0 ,0
Exp/Cntr=0.3,0.1

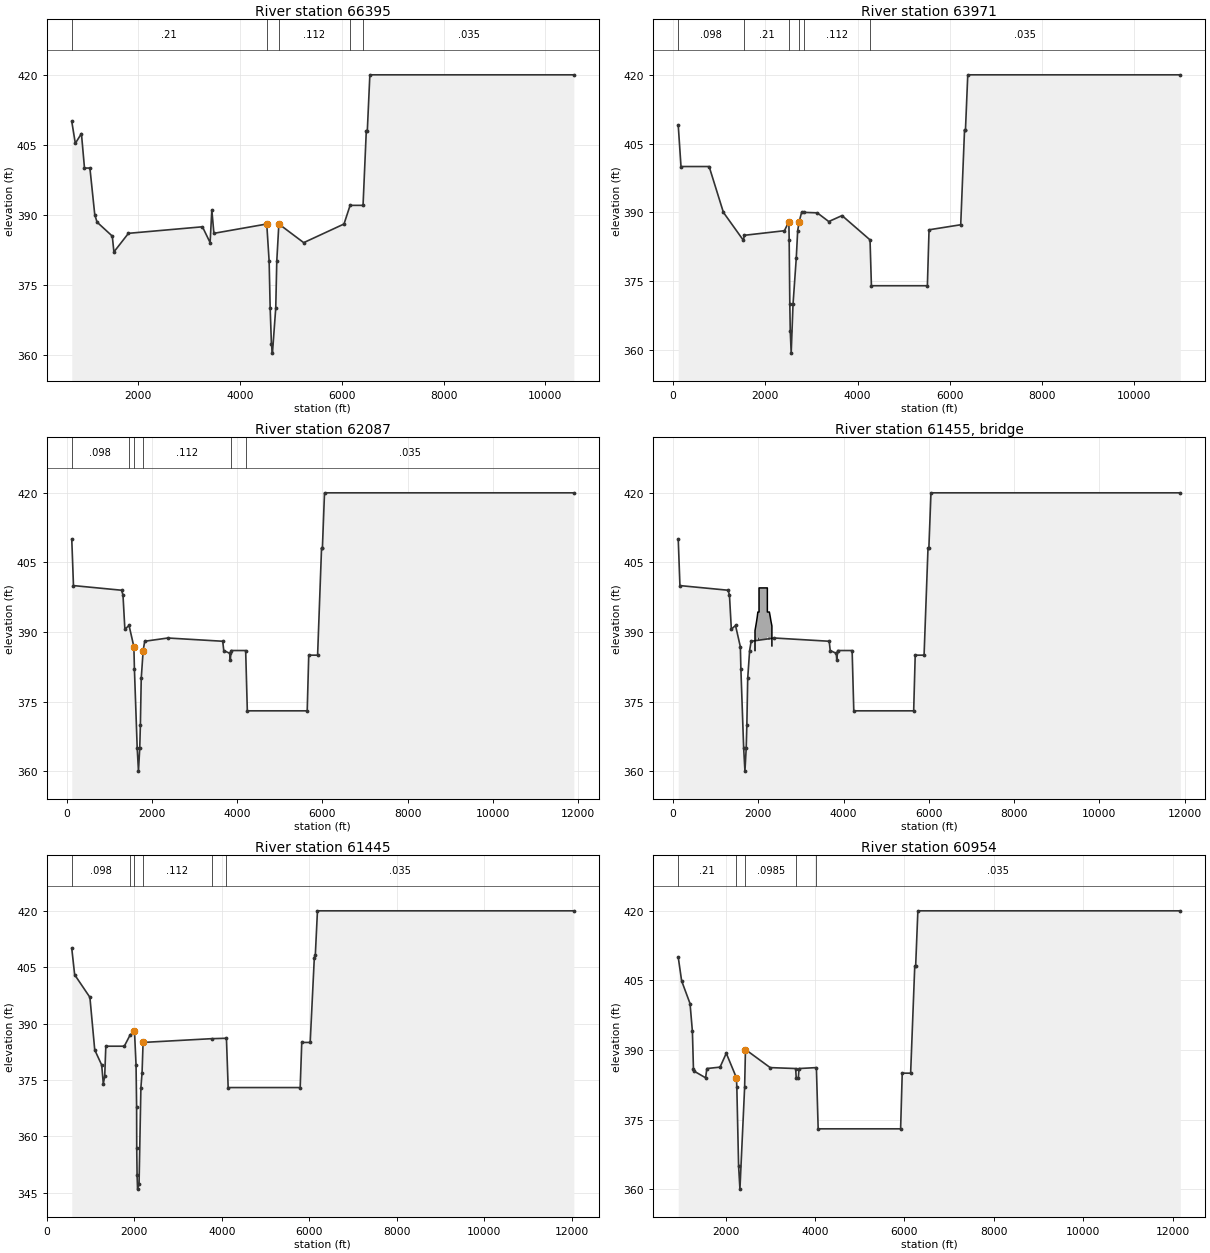
Type RM Length L Ch R = 1 ,66395   ,1000,2424,1800
BEGIN DESCRIPTION:
McCommas Bluff Landfill in ROB.
END DESCRIPTION:
XS GIS Cut Line= 2
  2520449.434805 6943897.9664471 2513978.4831703 6936445.2028704
#Sta/Elev= 30
     690     410     760   405.3     880   407.4     940     400  1046.6     400
    1142     390  1186.9   388.4  1486.6   385.4  1518.3     382    1804     386
  3259.2   387.4  3409.7     384  3443.4     391  3484.1     386    4523     388
    4570     380    4590     370    4615   362.2    4635   360.3    4700     370
    4720     380  4761.2     388  5249.3     384  6041.7     388  6161.7     392
    6416     392    6480     408    6500     408    6550     420   10560     420
#Mann= 5 ,-1,0
     690     .21       0    4523    .055       0  4761.2    .112       0
  6161.7    .098       0    6416    .035       0
Bank Sta=4523,4761.2
XS Rating Curve= 0 ,0
Exp/Cntr=0.3,0.1

Type RM Length L Ch R = 1 ,63971   ,750,1884,950
BEGIN DESCRIPTION:
McCommas Bluff Landfill in ROB.
END DESCRIPTION:
XS GIS Cut Line= 4
  2521208.158365 6944142.7339488        2519101.        6940072.
 2514224.5029896 6936088.4140025 2514217.1723255 6936082.4256196
#Sta/Elev= 30
     110     409     170     400     780     400  1089.7     390  1523.5   383.9
  1543.5     385  2414.2     386  2509.2     388  2516.2     384    2530     370
    2540   364.1    2560   359.3    2600     370    2670     380  2700.7     386
  2733.8     388  2785.9     390  2836.8     390  3125.4   389.9  3374.9     388
  3662.7   389.3    4270     384    4300     374    5514     374    5550   386.2
    6237   387.3    6320     408    6340     408    6390     420   11000     420
#Mann= 6 ,-1,0
     110    .098       0  1543.5     .21       0  2509.2    .055       0
  2733.8    .168       0  2836.8    .112       0    4270    .035       0
Bank Sta=2509.2,2733.8
XS Rating Curve= 0 ,0
Exp/Cntr=0.3,0.1

Type RM Length L Ch R = 1 ,62087   ,558,623,58
BEGIN DESCRIPTION:
McCommas Bluff Landfill in ROB.
END DESCRIPTION:
XS GIS Cut Line= 3
  2521918.241499 6944249.4642267        2520099.        6939774.
 2514357.0745302 6935860.2220578
#Sta/Elev= 30
     120     410     160     400  1287.8     399  1321.5     398  1365.8   390.6
  1464.1   391.4  1577.6   386.8  1589.9     382    1655     365    1685     360
    1715     365    1730     370    1750     380    1795     386  1831.3     388
  2374.7   388.7  3661.7     388  3686.1     386    3827   385.4  3839.6     384
  3860.1     386    4200     386    4239     373    5644     373    5680     385
    5888     385    5980     408    6000     408    6050     420   11900     420
#Mann= 6 ,-1,0
     120    .098       0  1464.1    .196       0  1577.6    .055       0
    1795    .112       0  3860.1    .098       0    4200    .035       0
Bank Sta=1577.6,1795
XS Rating Curve= 0 ,0
Exp/Cntr=0.3,0.1

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
Type RM Length L Ch R = 3 ,61455   ,,,
BEGIN DESCRIPTION:
Trinity Forest Trail Pedestrian Bridge
Data from Trinity Forest Trail Hydraulic Analyis Phase II & III Report, 19 January 2010
END DESCRIPTION:
Node Name=Trinity Trail Br
Bridge Culvert--1,0,-1,-1, 0
Deck Dist Width WeirC Skew NumUp NumDn MinLoCord MaxHiCord MaxSubmerge Is_Ogee
3.5,12,2.6,0, 15, 15, , , 0.98, 0, 0,0,,
  1921.2  1921.2 1940.13 1958.29  1974.5 1988.19 2015.79 2015.79 2210.79 2210.79
  2258.7 2278.22 2296.16 2317.75 2317.75
     386   390.3   391.3   392.3   393.3   394.3   394.3   399.5   399.5   394.3
   394.3   393.3   392.3   391.3     387
           384.9   385.9   386.9   387.9   388.9   388.9   386.5   386.5   388.9
   388.9   387.9   386.9   385.9
  1921.2  1921.2 1940.13 1958.29  1974.5 1988.19 2015.79 2015.79 2210.79 2210.79
  2258.7 2278.22 2296.16 2317.75 2317.75
     386   390.3   391.3   392.3   393.3   394.3   394.3   399.5   399.5   394.3
   394.3   393.3   392.3   391.3     387
           384.9   385.9   386.9   387.9   388.9   388.9   386.5   386.5   388.9
   388.9   387.9   386.9   385.9
Pier Skew, UpSta & Num, DnSta & Num=  ,1925.64, 2 ,1925.64, 2 , 0 , 0 , 0 ,,
     1.5     1.5
       0     390
     1.5     1.5
       0     390
Pier Skew, UpSta & Num, DnSta & Num=  ,1943.94, 2 ,1943.94, 2 , 0 , 0 , 0 ,,
     1.5     1.5
       0     390
     1.5     1.5
       0     390
Pier Skew, UpSta & Num, DnSta & Num=  ,1961.94, 2 ,1961.94, 2 , 0 , 0 , 0 ,,
     1.5     1.5
       0     390
     1.5     1.5
       0     390
Pier Skew, UpSta & Num, DnSta & Num=  ,1979.94, 2 ,1979.94, 2 , 0 , 0 , 0 ,,
     1.5     1.5
       0     390
     1.5     1.5
       0     390
Pier Skew, UpSta & Num, DnSta & Num=  ,1997.94, 2 ,1997.94, 2 , 0 , 0 , 0 ,,
     1.5     1.5
       0     390
     1.5     1.5
       0     390
Pier Skew, UpSta & Num, DnSta & Num=  ,2017.94, 2 ,2017.941, 2 , 0 , 0 , 0 ,,
     1.5     1.5
       0     390
     1.5     1.5
       0     390
Pier Skew, UpSta & Num, DnSta & Num=  ,2208.79, 2 ,2208.79, 2 , 0 , 0 , 0 ,,
     1.5     1.5
       0     390
     1.5     1.5
       0     390
Pier Skew, UpSta & Num, DnSta & Num=  ,2228.79, 2 ,2228.79, 2 , 0 , 0 , 0 ,,
     1.5     1.5
       0     390
     1.5     1.5
       0     390
Pier Skew, UpSta & Num, DnSta & Num=  ,2246.79, 2 ,2246.79, 2 , 0 , 0 , 0 ,,
     1.5     1.5
       0     390
     1.5     1.5
       0     390
Pier Skew, UpSta & Num, DnSta & Num=  ,2264.79, 2 ,2264.79, 2 , 0 , 0 , 0 ,,
     1.5     1.5
       0     390
     1.5     1.5
       0     390
Pier Skew, UpSta & Num, DnSta & Num=  ,2282.79, 2 ,2282.79, 2 , 0 , 0 , 0 ,,
     1.5     1.5
       0     390
     1.5     1.5
       0     390
Pier Skew, UpSta & Num, DnSta & Num=  ,2300.79, 2 ,2300.79, 2 , 0 , 0 , 0 ,,
     1.5     1.5
       0     390
     1.5     1.5
       0     390
BR Coef=-1 , 0 , 0 ,, 0 ,,,0.8,-1,,0,
WSPro=,,,, 1 ,,,, 0 ,,,, 0 ,,,,-1 ,-1 ,-1 , 0 , 0 , 0 , 0 , 0
BC Design=,, 0 ,, 0 ,,,,,,
BC Use User HTab Curves=0
BC User HTab FreeFlow(D)= 0

Type RM Length L Ch R = 1 ,61445   ,328,491,740
BEGIN DESCRIPTION:
Downstream bounding cross-section for Trinity Forest Trail Pedestrian Bridge.
Cross-section added for Trinity Trails project.
McCommas Bluff Landfill in ROB.
END DESCRIPTION:
XS GIS Cut Line= 6
  2522267.996631 6943615.4673965 2522117.5772557 6943353.8918988
 2521056.1059271 6940972.0997159        2520099.        6939774.
 2514492.7811239 6935908.2423248 2514304.5110196 6935779.0264964
#Sta/Elev= 30
  570.89     410  637.02     403  985.38     397 1096.09     383    1255     379
 1291.72     374 1323.98     376 1349.32     384 1771.72     384 1905.34     387
 2004.76     388 2040.27     379    2053  367.87    2056  356.91    2064  349.68
    2075  345.99    2109  347.38 2151.39     373  2178.1     377 2200.97     385
    3766     386 4106.52  386.11 4146.07     373 5792.46     373 5828.46     385
  6021.3     385 6115.67  407.55 6138.95  408.36 6187.47     42012048.46     420
#Mann= 6 ,-1,0
  570.89    .098       0 1905.34    .196       0 2004.76    .055       0
 2200.97    .112       0    3766    .098       0 4106.52    .035       0
Bank Sta=2004.76,2200.97
XS Rating Curve= 0 ,0
Exp/Cntr=0.3,0.1

Type RM Length L Ch R = 1 ,60954   ,1150,1503,850
BEGIN DESCRIPTION:
McCommas Bluff Landfill in ROB.
Approx. 650 feet upstream of right bank of Elam Creek.
END DESCRIPTION:
XS GIS Cut Line= 6
  2522532.327606 6943112.9785209        2522355.        6942874.
        2521250.        6940573.        2520099.        6939774.
 2514477.3195585 6935892.7908201 2514356.0443303  6935809.062381
#Sta/Elev= 30
     940     410    1016   404.9  1204.1     400    1257     394    1280     386
  1301.3   385.4  1552.5     384  1579.9     386  1875.5   386.3  2014.4   389.3
  2241.9     384  2250.5     382    2290     365    2320     360  2425.2     382
  2443.7   390.1  2996.8   386.2  3566.5     386  3578.7     384  3626.5     384
  3641.5     386    4030   386.2    4070     373    5914     373    5950     385
    6138     385    6230     408    6250     408    6300     420   12170     420
#Mann= 5 ,-1,0
     940     .21       0  2241.9    .063       0  2443.7   .0985       0
  3578.7    .098       0    4030    .035       0
Bank Sta=2241.9,2443.7
XS Rating Curve= 0 ,0
Exp/Cntr=0.3,0.1

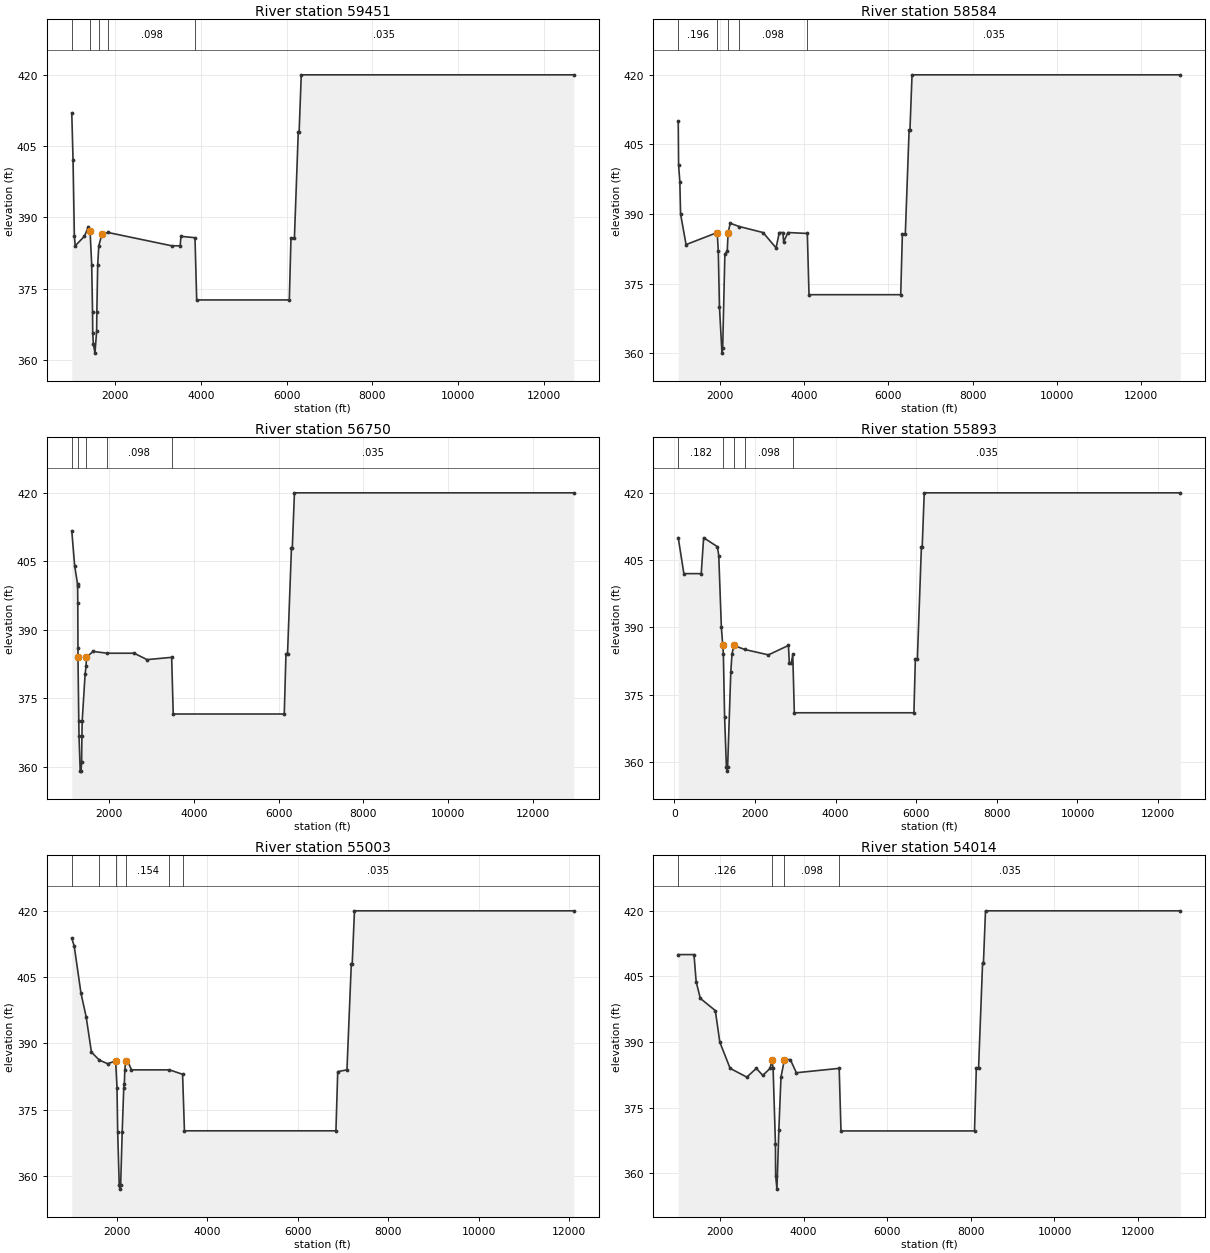
Type RM Length L Ch R = 1 ,59451   ,950,867,600
BEGIN DESCRIPTION:
McCommas Bluff Landfill in ROB.
END DESCRIPTION:
XS GIS Cut Line= 3
   2523571.17734 6942761.9507955        2521825.        6940315.
 2514647.7003918 6935382.3417416
#Sta/Elev= 30
     985     412  1014.9     402  1045.5     386  1066.1     384  1279.3     386
  1372.6     388  1412.2   387.1    1450     380    1470     370    1474   365.6
    1490   363.3    1526   361.4    1565     366    1570     370    1590     380
  1615.5     384  1689.8   386.5  1831.5   386.8  3318.8     384  3515.3     384
  3532.4     386    3860   385.7    3900   372.6    6061   372.6    6100   385.6
    6180   385.6    6270     408    6290     408    6340     420   12700     420
#Mann= 5 ,-1,0
     985    .196       0  1412.2    .055       0  1615.5    .168       0
  1831.5    .098       0    3860    .035       0
Bank Sta=1412.2,1689.8
XS Rating Curve= 0 ,0
Exp/Cntr=0.3,0.1

Type RM Length L Ch R = 1 ,58584   ,1400,1834,1000
BEGIN DESCRIPTION:
McCommas Bluff Landfill in ROB.
END DESCRIPTION:
XS GIS Cut Line= 3
        2524457.        6942115.        2521825.        6940315.
 2514612.6984001 6935358.2863345
#Sta/Elev= 30
    1000     410  1008.7   400.5    1038     397  1055.8     390    1186   383.4
  1927.6     386  1952.7     382    1980     370    2040     360    2057     361
  2108.8   381.3  2165.4     382  2185.8     386  2236.5     388    2450   387.3
  3016.9     386    3326   382.7  3404.5     386  3489.6     386  3506.4     384
  3609.5     386    4070   385.8    4110   372.6    6291   372.6    6330   385.6
    6400   385.6    6490     408    6510     408    6560     420   12940     420
#Mann= 5 ,-1,0
    1000    .196       0  1927.6    .055       0  2185.8    .126       0
    2450    .098       0    4070    .035       0
Bank Sta=1927.6,2185.8
XS Rating Curve= 0 ,0
Exp/Cntr=0.3,0.1

Type RM Length L Ch R = 1 ,56750   ,870,857,700
BEGIN DESCRIPTION:
McCommas Bluff Landfill in ROB.
END DESCRIPTION:
XS GIS Cut Line= 4
  2525010.129413 6941011.0042398        2523054.        6940225.
        2523054.        6940225.   2515017.01437 6934702.5123749
#Sta/Elev= 30
  1110.4   411.7  1179.1     404  1247.4     400    1249   399.6  1252.5     396
  1256.9   386.1  1257.4     384    1276     370    1282   366.7    1310   359.1
    1329   359.1    1343   361.1    1350   366.7    1356     370    1426   380.4
  1447.1     382  1458.2     384  1613.3   385.3    1946   384.9  2584.7   384.9
  2888.8   383.5    3470     384    3507   371.6    6130   371.6    6170   384.8
    6207   384.8    6300     408    6320     408    6370     420   12970     420
#Mann= 5 ,-1,0
  1110.4     .14       0  1257.4    .055       0  1458.2    .154       0
    1946    .098       0    3470    .035       0
Bank Sta=1257.4,1458.2
XS Rating Curve= 0 ,0
Exp/Cntr=0.3,0.1

Type RM Length L Ch R = 1 ,55893   ,890,890,800
BEGIN DESCRIPTION:
McCommas Bluff Landfill in ROB.
END DESCRIPTION:
XS GIS Cut Line= 4
  2525960.466482 6940375.3213813        2523265.        6939679.
 2515256.4125755 6934285.4789883 2515247.6168798 6934279.5553757
#Sta/Elev= 30
     100     410     240     402     670     402     730     410  1071.6     408
  1104.9     406  1169.7     390  1204.8     386  1219.2     384    1250     370
    1294     359    1310     358    1325     359  1403.2     380  1431.7     384
  1478.6     386    1750   385.1  2336.3   383.9  2832.7     386  2854.6     382
  2902.8     382    2940     384    2979     371    5944     371    5980     383
    6030     383    6130     408    6150     408    6200     420   12550     420
#Mann= 5 ,-1,0
     100    .182       0  1204.8    .055       0  1478.6    .182       0
    1750    .098       0    2940    .035       0
Bank Sta=1204.8,1478.6
XS Rating Curve= 0 ,0
Exp/Cntr=0.3,0.1

Type RM Length L Ch R = 1 ,55003   ,1000,989,1000
BEGIN DESCRIPTION:
McCommas Bluff Landfill in ROB.
END DESCRIPTION:
XS GIS Cut Line= 3
        2525912.        6939386.        2523363.        6938913.
 2516239.8178141 6934261.3777259
#Sta/Elev= 30
    1000   413.8  1054.5     412  1202.9   401.4    1318     396  1435.2     388
    1610   386.2  1791.6   385.4    1970     386    2000     380    2015     370
    2049     358    2065     357    2081     358    2115     370  2149.5     380
  2162.5   380.9  2173.3     384  2191.2     386    2230   386.1  2320.4     384
    3160     384    3450     383    3491   370.2    6840   370.2    6880   383.6
    7084     384    7180     408    7200     408    7250     420   12100     420
#Mann= 6 ,-1,0
    1000    .112       0    1610    .182       0    1970    .055       0
  2191.2    .154       0    3160    .098       0    3450    .035       0
Bank Sta=1970,2191.2
XS Rating Curve= 0 ,0
Exp/Cntr=0.3,0.1

Type RM Length L Ch R = 1 ,54014   ,1000,986,1000
BEGIN DESCRIPTION:
McCommas Bluff Landfill in ROB.
END DESCRIPTION:
XS GIS Cut Line= 5
        2527329.        6938648.        2527329.        6938648.
        2522705.        6937786. 2516555.5437802 6933840.5230515
 2516555.5437802 6933840.5230515
#Sta/Elev= 30
    1000     410    1377     410  1428.8   403.8  1528.1     400  1887.2   397.2
  1994.3     390  2241.2     384    2641     382  2867.9     384  3022.4   382.4
  3198.4     384  3242.4     386  3269.2     384    3325   366.8    3330   359.5
    3361   356.4    3407     370  3457.8     382  3540.3     386  3681.3     386
    3826     383    4850     384    4893   369.7    8087   369.7    8130     384
    8184     384    8280     408    8300     408    8350     420   13010     420
#Mann= 4 ,-1,0
    1000    .126       0  3242.4    .055       0  3540.3    .098       0
    4850    .035       0
Bank Sta=3242.4,3540.3
XS Rating Curve= 0 ,0
Exp/Cntr=0.3,0.1