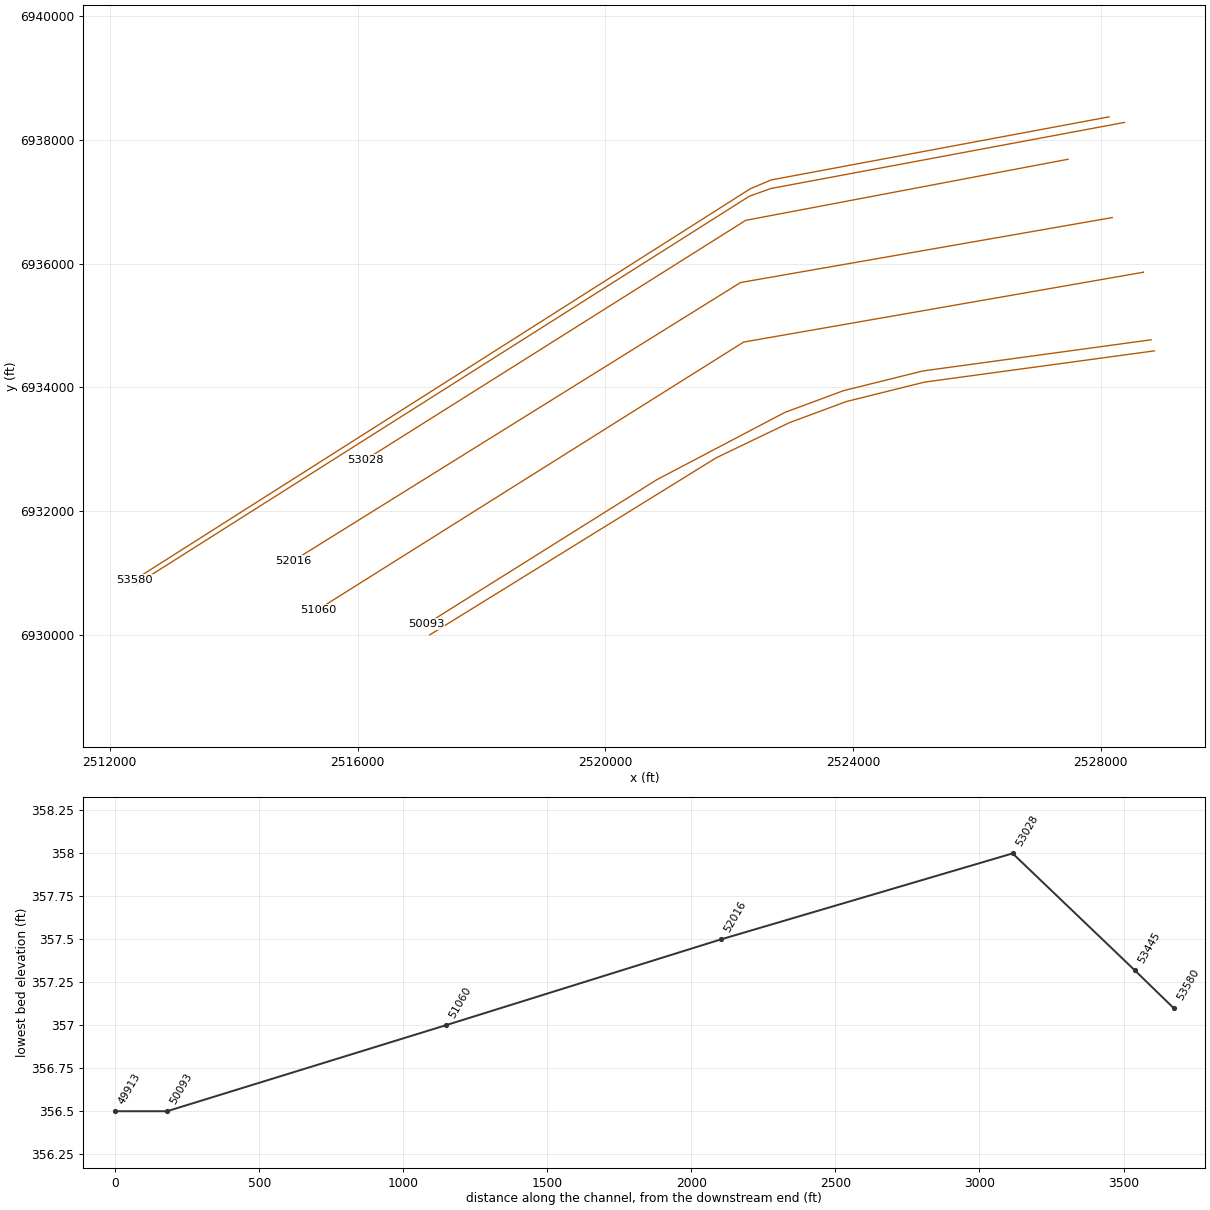
HEC-RAS study CDC_Consolidated_Model.prj: Upper Trinity CDC Consolidated Model

--- CDC_Consolidated_Model.g13 (geometry) --- (continued)

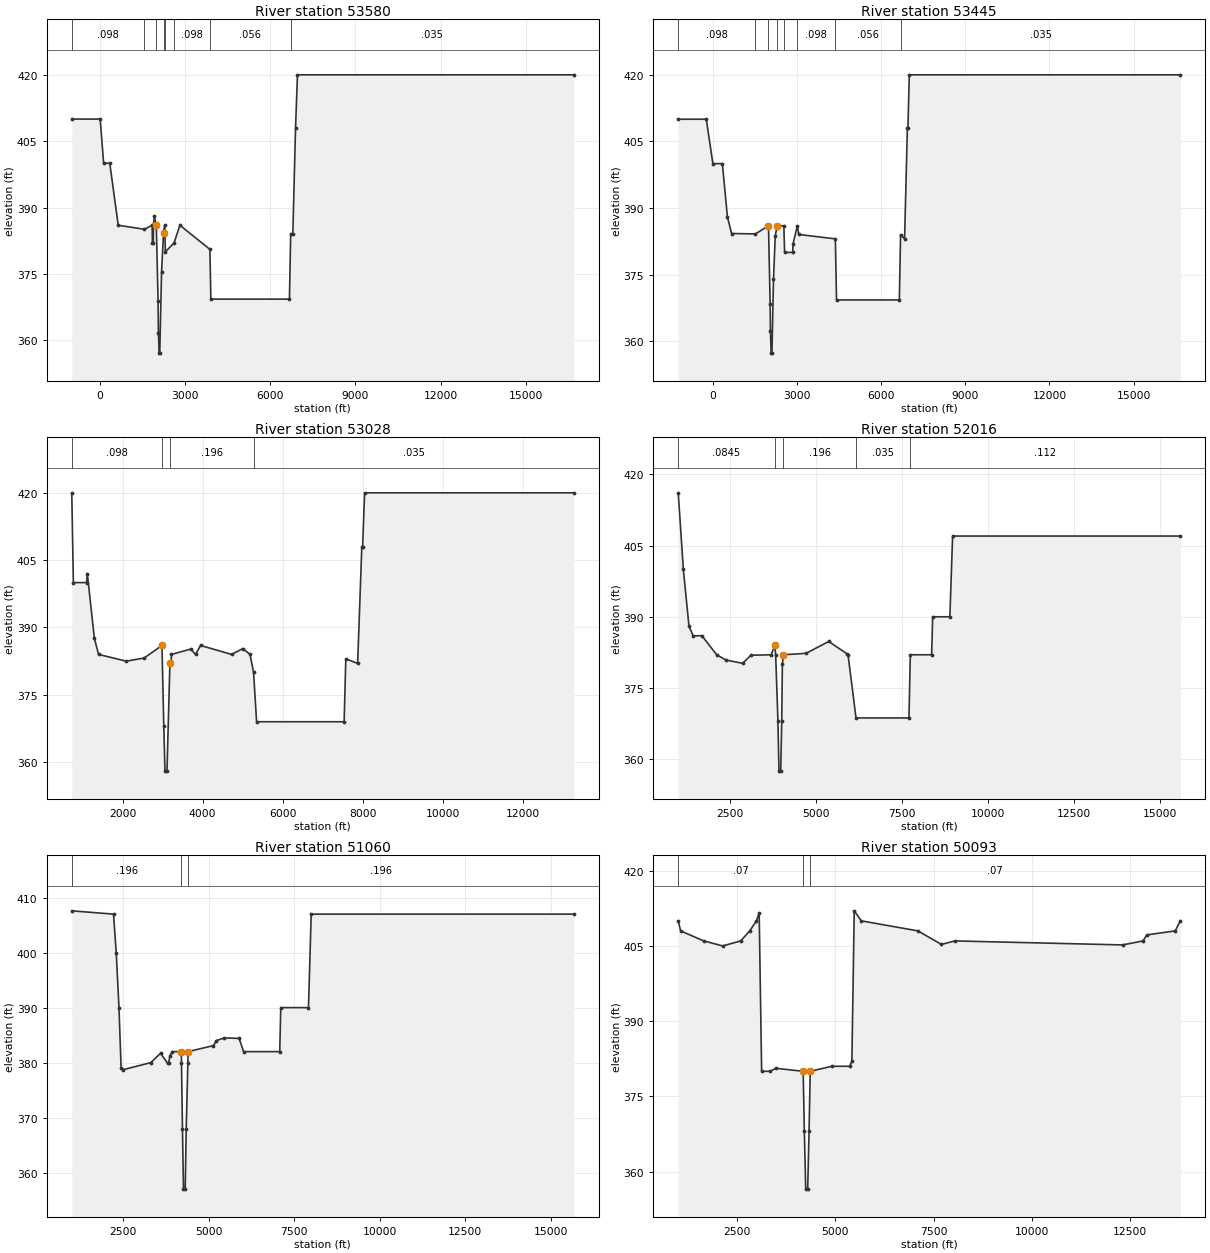
Type RM Length L Ch R = 1 ,53580   ,137,135,137
BEGIN DESCRIPTION:
This cross section corresponds to cross section 53580 of the non-georeferenced CDC model which was the source of this model.
END DESCRIPTION:
XS GIS Cut Line= 6
2528134.545594136938371.381576282527151.562526856938187.68538839
 2522681.91497016937352.41442113 2522346.33690116937211.70636922
2514507.659337016932230.012920542512397.706701066930889.08045615
#Sta/Elev= 30
   -1000     410    1.66     410  123.42     400  339.04  400.04   637.2     386
 1560.69  385.09 1833.54     386 1842.56     382 1872.12     382 1879.06     386
 1912.85     388 1980.13     386 2042.72  368.81 2053.62  361.72 2079.63   357.1
 2101.64   357.1  2164.4  375.36 2234.19  384.24 2276.09     386 2298.65     380
 2605.45     382 2811.49     386 3868.96  380.56 3902.74   369.3 6673.04   369.3
 6717.14     384 6791.98     384 6887.98     408 6955.98     42016698.65     420
#Mann= 8 ,-1,0
   -1000    .098       0 1560.69    .126       0 1980.13    .055       0
 2234.19    .126       0 2276.09    .065       0 2605.45    .098       0
 3868.96    .056       0 6717.14    .035       0
Bank Sta=1980.13,2234.19
XS Rating Curve= 0 ,0
Exp/Cntr=0.3,0.1

Type RM Length L Ch R = 1 ,53445   ,430,424,430
BEGIN DESCRIPTION:
This cross section corresponds to cross section 53445 of the non-georeferenced CDC model which was the source of this model.
END DESCRIPTION:
XS GIS Cut Line= 6
2528385.19297907 6938281.52359962527402.239190856938097.67080463
2522672.603965076937213.034450552522329.419284026937089.92019546
2514537.64845026 6932152.9057913  2512425.8735386930814.84498553
#Sta/Elev= 30
   -1235     410    -235     410       0     400  338.25     400  518.31     388
  667.45  384.26 1517.26  384.17 1983.06     386  2041.9  368.44 2052.16  362.41
 2076.61  357.32 2105.46  357.32 2161.35  373.92 2223.48  383.69 2294.57     386
 2530.53     386 2557.02     380 2843.71     380 2860.12     382 3013.26     386
 3060.59  384.04 4366.94  383.06 4408.22   369.3 6648.46   369.3 6692.56     384
 6835.04  383.07 6934.76     408 6954.76     408 7002.76     42016665.47     420
#Mann= 8 ,-1,0
   -1235    .098       0 1517.26    .126       0 1983.06    .055       0
 2294.57    .196       0 2530.53    .065       0 3013.26    .098       0
 4366.94    .056       0 6692.56    .035       0
Bank Sta=1983.06,2294.57
XS Rating Curve= 0 ,0
Exp/Cntr=0.3,0.1

Type RM Length L Ch R = 1 ,53028   ,1010,1012,1010
BEGIN DESCRIPTION:
McCommas Bluff Landfill in ROB.
END DESCRIPTION:
XS GIS Cut Line= 4
  2527474.142623 6937686.3417764        2522268.        6936699.
 2516146.2766189 6932841.6099349 2516133.2579616 6932833.4066829
#Sta/Elev= 30
     730     420     770     400  1100.8     400  1118.6     402  1294.5   387.6
  1399.2     384  2090.8   382.5  2540.8   383.2  2984.8     386    3030     368
    3060     358    3110     358  3183.1     382  3211.7     382  3221.9     384
  3705.5   385.2  3823.4     384  3949.6     386  4724.1     384  5005.4   385.3
  5185.3     384  5274.4     380    5350     369    7538     369    7580     383
    7876     382    7980     408    8000     408    8050     420   13280     420
#Mann= 4 ,-1,0
     730    .098       0  2984.8    .055       0  3183.1    .196       0
  5274.4    .035       0
Bank Sta=2984.8,3183.1
XS Rating Curve= 0 ,0
Exp/Cntr=0.3,0.1

Type RM Length L Ch R = 1 ,52016   ,990,956,990
BEGIN DESCRIPTION:
Approx. 700 feet upstream of  left bank of Five Mile Creek.  Old Trinity River channel in ROB removed from
conveyance.
Baseline project - McCommas Bluff Landfill - in ROB.  Project represented as complete per design plans by HDR Inc.  Project consists of fill area and swale.
END DESCRIPTION:
XS GIS Cut Line= 3
  2528187.681335 6936743.9442616        2522185.        6935694.
  2514962.274626 6931197.1709806
#Sta/Elev= 30
    1000   416.1  1148.6     400  1312.4     388  1435.2     386  1689.6     386
  2118.3     382  2386.1   380.9  2870.2   380.2  3115.9   381.9  3702.7     382
  3810.1     384  3833.2     382    3900     368    3930   357.5    3980   357.5
    4010     368  4028.3     380  4059.7     382  4718.5   382.3  5376.1   384.8
  5909.1   382.2    5940   381.9    6170   368.7    7710   368.7    7750     382
    8370     382    8400     390    8900     390    8980     407   15602     407
#Mann= 5 ,-1,0
    1000   .0845       0  3810.1    .055       0  4059.7    .196       0
    6170    .035       0    7750    .112       0
Bank Sta=3810.1,4059.7
XS Rating Curve= 0 ,0
Exp/Cntr=0.3,0.1

Type RM Length L Ch R = 1 ,51060   ,1000,967,1000
BEGIN DESCRIPTION:
Five Mile Creek.
END DESCRIPTION:
Node Name=Five Mile Creek
XS GIS Cut Line= 6
  2528693.157324 6935861.0275038 2528693.1573247 6935861.0275038
        2528693.        6935861.        2522235.        6934732.
        2515360.        6930408. 2515359.8648058 6930407.9149702
#Sta/Elev= 30
    1000   407.6    2220     407    2300     400    2380     390  2441.9   379.1
  2491.6   378.7  3310.2     380  3594.8   381.7  3799.3   379.9  3831.9     380
  3870.5   381.2  3934.6     382  4204.1     382  4207.6     380    4236     368
    4266     357    4316     357    4346     368  4394.4     380  4399.1     382
  5143.1   383.1  5227.3     384  5459.8   384.5  5892.2   384.4  6023.8     382
    7080     382    7110     390    7920     390    8000     407   15678     407
#Mann= 3 ,-1,0
    1000    .196       0  4204.1    .055       0  4399.1    .196       0
Bank Sta=4204.1,4399.1
XS Rating Curve= 0 ,0
Exp/Cntr=0.3,0.1

Type RM Length L Ch R = 1 ,50093   ,180,180,180
BEGIN DESCRIPTION:
Upstream bounding cross-section for IH 20 bridge.
END DESCRIPTION:
XS GIS Cut Line= 6
  2528815.044427 6934768.8285682   2525130.48148 6934265.4539368
 2523848.2626528 6933946.6702578 2522898.9956545 6933594.4901915
 2520832.4677499 6932507.5896098 2517114.3335148 6930175.4140286
#Sta/Elev= 30
    1000     410    1060     408    1650     406    2130     405    2590     406
    2820     408    2990     410    3060   411.6    3123     380    3339     380
    3483   380.6    4180     380    4210     368    4245   356.5    4295   356.5
    4330     368    4360     380    4908     381    5364     381    5420     382
    5480     412    5660     410    7100     408    7700   405.3    8040     406
   12310   405.2   12830     406   12930   407.2   13650     408   13780     410
#Mann= 3 ,0,0
    1000     .07       0    4180    .056       0    4360     .07       0
Bank Sta=4180,4360
XS Rating Curve= 0 ,0
Exp/Cntr=0.5,0.3

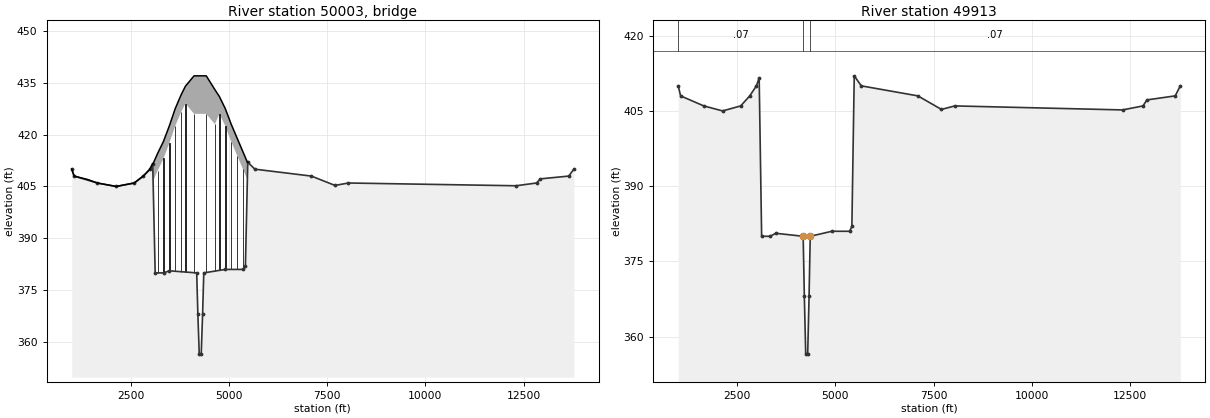
Type RM Length L Ch R = 3 ,50003   ,,,
BEGIN DESCRIPTION:
IH 20
Data from bridge plans.  Bridge length 2400 feet. Perched bridge - minimum low chord elev. 406.6.  Bridge width set at 178 feet.
END DESCRIPTION:
Node Name=IH 20
Bridge Culvert--1,0,-1,-1, 0
Deck Dist Width WeirC Skew NumUp NumDn MinLoCord MaxHiCord MaxSubmerge Is_Ogee
1,178,2.6,0, 26, 26, , , 0.95, 0, ,,,
    1000    1060    1410    1650    2130    2590    2820    2990    3060    3070
    3183    3333    3483    3633    3783    3893    4113    4423    4643    4758
    4908    5058    5208    5358    5470    5480
     410     408     407     406     405     406     408     410   411.6   411.6
   414.5     418   422.5   427.5   431.5     434     437     437     433     431
   427.5     423     419     415     412     412
     410     408     407     406     405     406     408     410   411.6   406.6
   409.5     413   417.5   422.5   426.5     429     426     426     423     426
   422.5     418     414     410     407     412
    1000    1060    1410    1650    2130    2590    2820    2990    3060    3070
    3183    3333    3483    3633    3783    3893    4113    4423    4643    4758
    4908    5058    5208    5358    5470    5480
     410     408     407     406     405     406     408     410   411.6   411.6
   414.5     418   422.5   427.5   431.5     434     437     437     433     431
   427.5     423     419     415     412     412
     410     408     407     406     405     406     408     410   411.6   406.6
   409.5     413   417.5   422.5   426.5     429     426     426     423     426
   422.5     418     414     410     407     412
Pier Skew, UpSta & Num, DnSta & Num=  ,3186, 2 ,3186, 2 , 0 , 0 , 0 ,,
       6       6
       0     410
       6       6
       0     410
Pier Skew, UpSta & Num, DnSta & Num=  ,3336, 2 ,3336, 2 , 0 , 0 , 0 ,,
       6       6
       0   413.5
       6       6
       0   413.5
Pier Skew, UpSta & Num, DnSta & Num=  ,3486, 2 ,3486, 2 , 0 , 0 , 0 ,,
       6       6
       0     418
       6       6
       0     418
Pier Skew, UpSta & Num, DnSta & Num=  ,3636, 2 ,3636, 2 , 0 , 0 , 0 ,,
       6       6
       0     423
       6       6
       0     423
Pier Skew, UpSta & Num, DnSta & Num=  ,3786, 2 ,3786, 2 , 0 , 0 , 0 ,,
       6       6
       0     427
       6       6
       0     427
Pier Skew, UpSta & Num, DnSta & Num=  ,3895, 2 ,3895, 2 , 0 , 0 , 0 ,,
       4       4
       0   429.5
       4       4
       0   429.5
Pier Skew, UpSta & Num, DnSta & Num=  ,4115, 2 ,4115, 2 , 0 , 0 , 0 ,,
       4       4
       0   426.5
       4       4
       0   426.5
Pier Skew, UpSta & Num, DnSta & Num=  ,4425, 2 ,4425, 2 , 0 , 0 , 0 ,,
       4       4
       0   426.5
       4       4
       0   426.5
Pier Skew, UpSta & Num, DnSta & Num=  ,4645, 2 ,4645, 2 , 0 , 0 , 0 ,,
       4       4
       0   423.5
       4       4
       0   423.5
Pier Skew, UpSta & Num, DnSta & Num=  ,4761, 2 ,4761, 2 , 0 , 0 , 0 ,,
       6       6
       0   426.5
       6       6
       0   426.5
Pier Skew, UpSta & Num, DnSta & Num=  ,4911, 2 ,4911, 2 , 0 , 0 , 0 ,,
       6       6
       0     423
       6       6
       0     423
Pier Skew, UpSta & Num, DnSta & Num=  ,5061, 2 ,5061, 2 , 0 , 0 , 0 ,,
       6       6
       0   418.5
       6       6
       0   418.5
Pier Skew, UpSta & Num, DnSta & Num=  ,5211, 2 ,5211, 2 , 0 , 0 , 0 ,,
       6       6
       0   414.5
       6       6
       0   414.5
Pier Skew, UpSta & Num, DnSta & Num=  ,5361, 2 ,5361, 2 , 0 , 0 , 0 ,,
       6       6
       0   410.5
       6       6
       0   410.5
BR Coef= 1 , 0 , 0 ,1.05, 0 ,,,0.8,-1,0.5,1,
WSPro=,,,, 1 ,,,, 0 ,,,, 0 ,,,,-1 ,-1 ,-1 , 0 , 0 , 0 , 0 , 0
BC Design=,, 0 ,, 0 ,,,,,,
BC HTab HWMax=412
BC Use User HTab Curves=0
BC User HTab FreeFlow(D)= 0

Type RM Length L Ch R = 1 ,49913   ,1000,1116,1220
BEGIN DESCRIPTION:
Downstream bounding cross-section for IH 20 bridge.
END DESCRIPTION:
XS GIS Cut Line= 6
  2528868.308224 6934590.0023417        2525156.        6934085.
        2523895.        6933771.        2522975.        6933430.
        2521795.        6932863. 2517167.0185856 6930000.6433261
#Sta/Elev= 30
    1000     410    1060     408    1650     406    2130     405    2590     406
    2820     408    2990     410    3060   411.6    3123     380    3339     380
    3483   380.6    4180     380    4210     368    4245   356.5    4295   356.5
    4330     368    4360     380    4908     381    5364     381    5420     382
    5480     412    5660     410    7100     408    7700   405.3    8040     406
   12310   405.2   12830     406   12930   407.2   13650     408   13780     410
#Mann= 3 ,0,0
    1000     .07       0    4180    .056       0    4360     .07       0
Bank Sta=4180,4360
XS Rating Curve= 0 ,0
Exp/Cntr=0.5,0.3